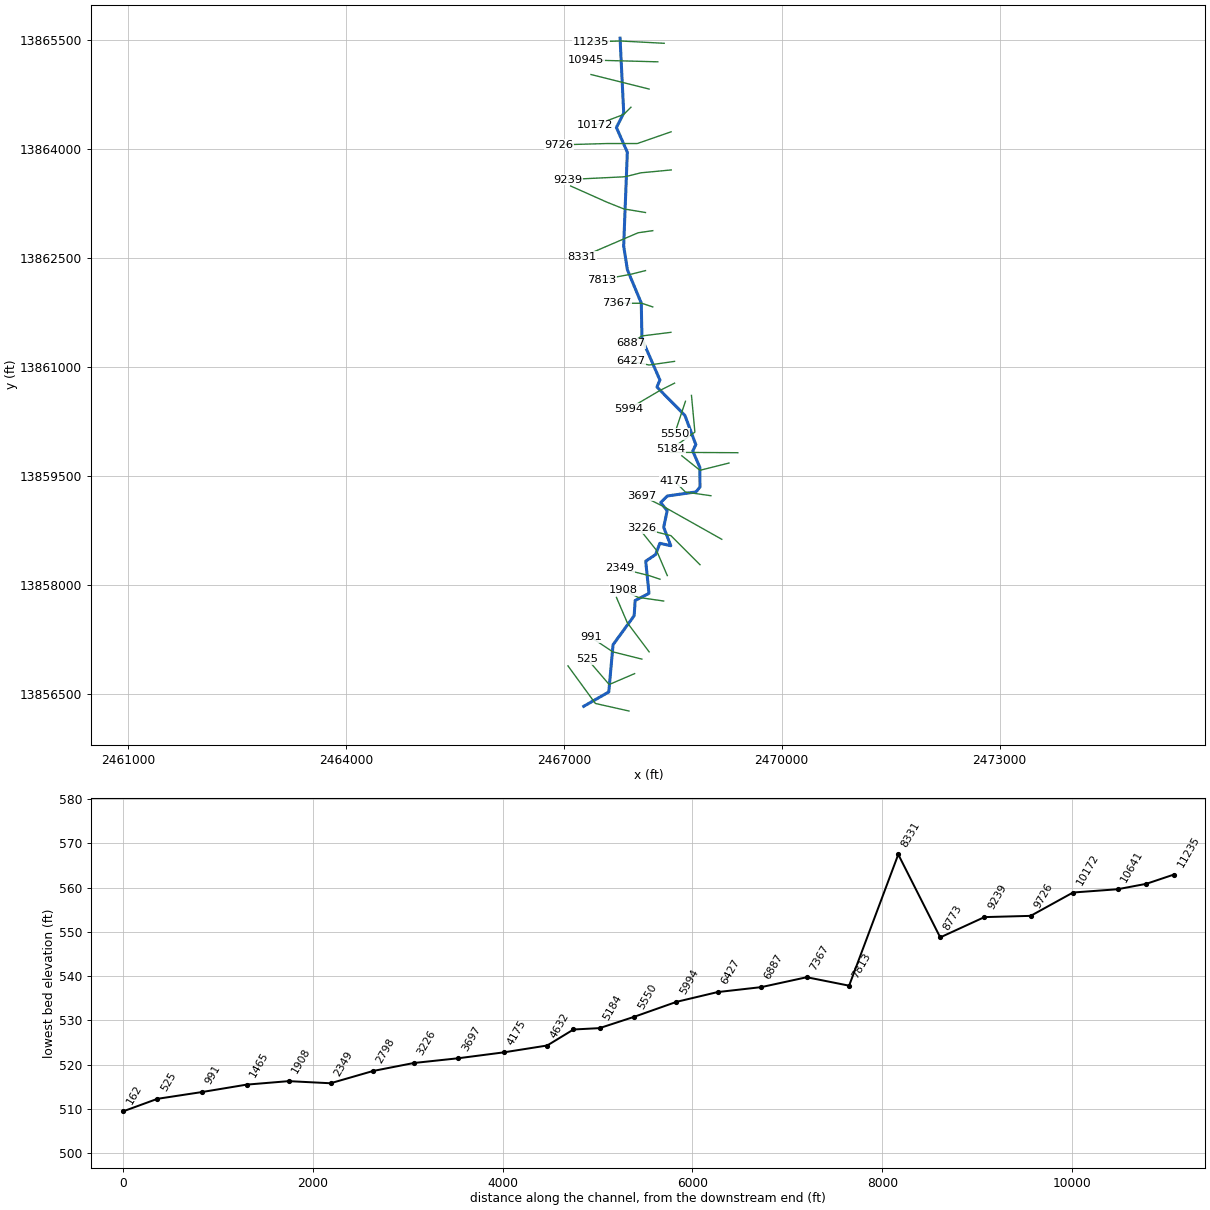
--- Devil Hollow.prj (project) ---

Proj Title=Devil Hollow Base Level Engineering
Current Plan=p01
Default Exp/Contr=0.3,0.1
English Units
Geom File=g01
Flow File=f01
Plan File=p01
Y Axis Title=Elevation
X Axis Title(PF)=Main Channel Distance
X Axis Title(XS)=Station
BEGIN DESCRIPTION:
Devil Hollow
END DESCRIPTION:
DSS Export Rating Curves= 0
DSS Export Rating Curve Sorted= 0
DSS Export Volume Flow Curves= 0
DXF OffsetX= 0
DXF OffsetY= 0
DXF ScaleX= 1
DXF ScaleY= 10

--- Devil Hollow.p01 (plan) ---

Plan Title=Multiple Run
Short Identifier=Multiple
Geom File=g01
Flow File=f01
Subcritical Flow
K Sum by GR= 0
Std Step Tol= 0.01
Critical Tol= 0.01
Num of Std Step Trials= 20
Max Error Tol= 0.3
Flow Tol Ratio= 0.001
Split Flow NTrial= 30
Split Flow Tol= 0.02
Split Flow Ratio= 0.02
Log Output Level= 0
Friction Slope Method= 1
Unsteady Friction Slope Method= 2
Unsteady Bridges Friction Slope Method= 1
Parabolic Critical Depth
Global Vel Dist=  1 , 1 , 1
Global Log Level= 0
CheckData=True
Encroach Param= -1, 0, 0, 0
BEGIN DESCRIPTION:
Multiple Run
END DESCRIPTION:

--- Devil Hollow.f01 (steady flow) ---

Flow Title=Multiple
Number of Profiles=7
Profile Names=10-year,25-year,50-year,1pct_min,100-year,1pct_plu,500-year
River Rch & RM= Devil Hollow,Reach-1,11235
    1014    1679    2296    1520    3032    6050    5236
River Rch & RM= Devil Hollow,Reach-1,8331
    1113    1847    2528    1674    3339    6663    5772
River Rch & RM= Devil Hollow,Reach-1,4909
    1215    2024    2778    1844    3679    7341    6391
River Rch & RM= Devil Hollow,Reach-1,4175
    1249    2078    2851    1890    3770    7523    6535
River Rch & RM= Devil Hollow,Reach-1,991
    1334    2222    3049    2021    4032    8045    6991
Boundary for River Rch & Prof#=Devil Hollow,Reach-1,1
Up Type=0
Dn Type=3
Dn Slope=0.005
Boundary for River Rch & Prof#=Devil Hollow,Reach-1,2
Up Type=0
Dn Type=3
Dn Slope=0.005
Boundary for River Rch & Prof#=Devil Hollow,Reach-1,3
Up Type=0
Dn Type=3
Dn Slope=0.005
Boundary for River Rch & Prof#=Devil Hollow,Reach-1,4
Up Type=0
Dn Type=3
Dn Slope=0.005
Boundary for River Rch & Prof#=Devil Hollow,Reach-1,5
Up Type=0
Dn Type=3
Dn Slope=0.005
Boundary for River Rch & Prof#=Devil Hollow,Reach-1,6
Up Type=0
Dn Type=3
Dn Slope=0.005
Boundary for River Rch & Prof#=Devil Hollow,Reach-1,7
Up Type=0
Dn Type=3
Dn Slope=0.005

--- Devil Hollow.g01 (geometry) ---

Geom Title=Existing Conditions

River Reach=Devil Hollow,Reach-1
Reach XY= 30
      2467775.00     13865525.00      2467825.29     13864495.17
      2467724.71     13864295.18      2467875.04     13863955.02
      2467824.55     13862664.81      2467876.22     13862335.50
      2468066.92     13861878.30      2468076.20     13861385.50
      2468323.33     13860818.95      2468282.83     13860721.60
      2468667.18     13860331.19      2468817.73     13859928.44
      2468775.12     13859840.41      2468873.78     13859614.50
      2468875.09     13859344.87      2468819.35     13859276.98
      2468426.44     13859221.46      2468333.95     13859131.69
      2468423.36     13859018.97      2468375.37     13858790.17
      2468473.40     13858536.17      2468322.42     13858570.02
      2468264.61     13858414.90      2468128.04     13858323.58
      2468173.12     13857880.69      2467982.37     13857781.38
      2467969.19     13857572.71      2467678.54     13857173.54
      2467619.55     13856522.53      2467275.00     13856325.00

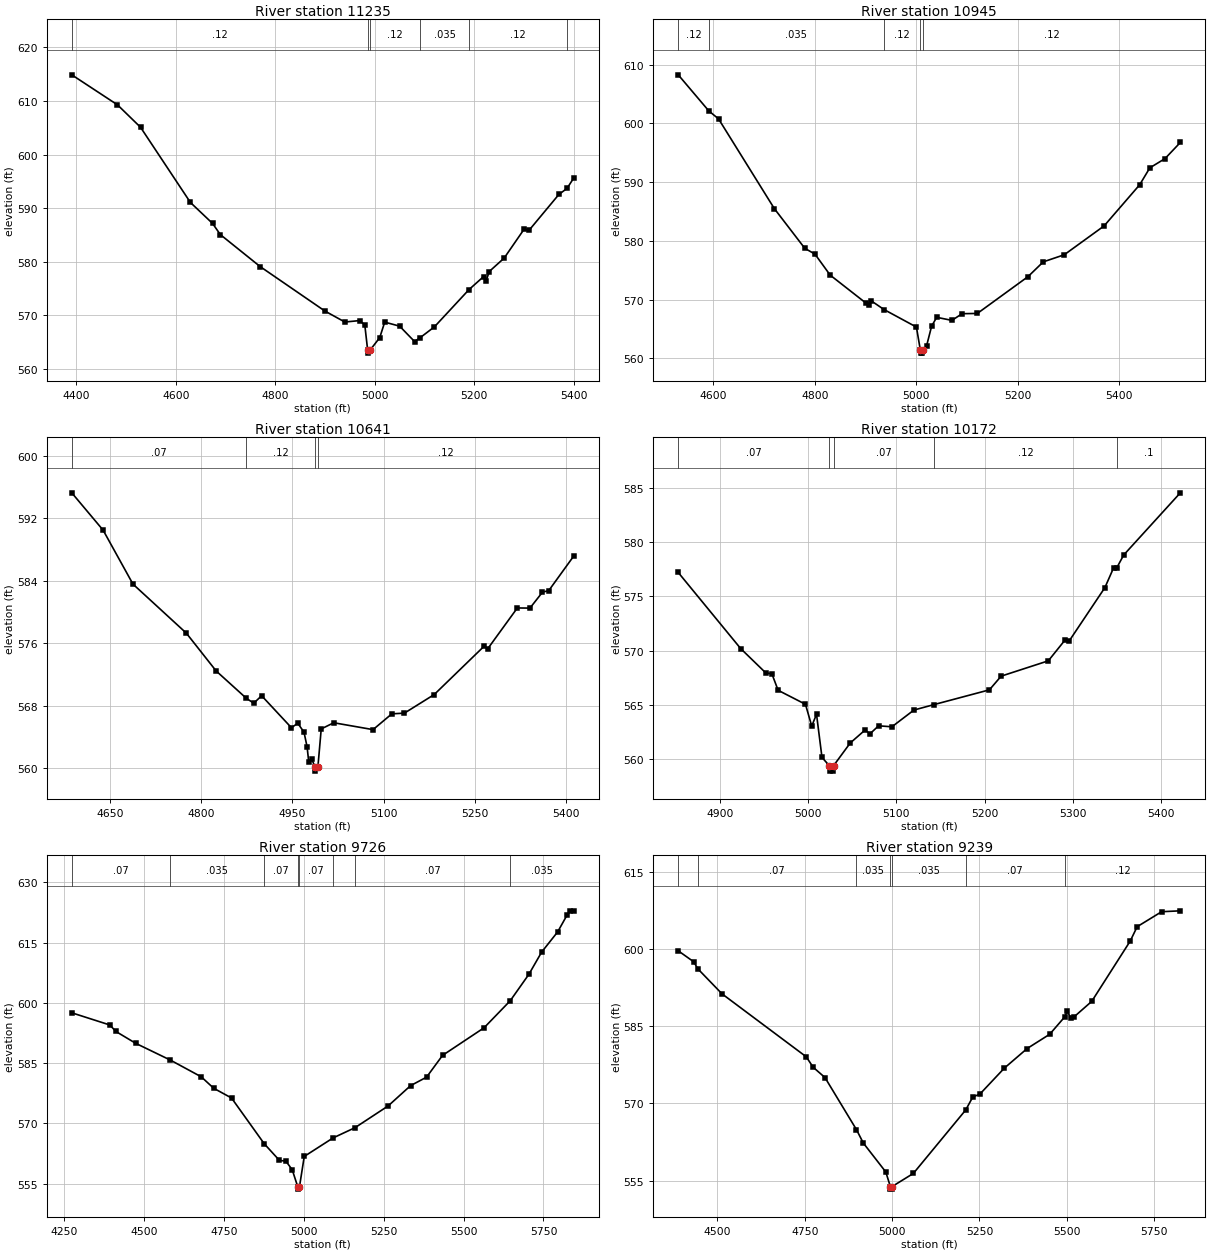
Type RM Length L Ch R = 1,11235,290,290,290
BEGIN DESCRIPTION:
Devil Hollow 23.0
END DESCRIPTION:
XS GIS Cut Line= 3
      2468383.05     13865455.28      2467784.08     13865486.53
      2467375.03     13865475.00
#Sta/Elev= 30
  4391.1  614.86  4483.0  609.26  4529.3  605.08  4629.5  591.06  4674.1  587.14
  4689.6  585.07  4769.7  579.10  4899.8  570.81  4939.9  568.76  4969.9  569.03
  4980.0  568.20  4985.8  563.46  4986.0  562.96  4990.1  563.46  5010.0  565.85
  5020.0  568.74  5050.0  567.99  5080.0  565.12  5090.9  565.82  5120.0  567.87
  5189.4  574.81  5218.9  577.25  5223.9  576.48  5230.1  578.18  5260.1  580.69
  5300.1  586.07  5310.1  585.87  5370.1  592.56  5386.4  593.68  5400.1  595.65
#Mann=6,-1,0
  4391.1    0.12       0  4985.8    0.05       0  4990.1    0.12       0
  5090.9   0.035       0  5189.4    0.12       0  5386.4    0.07       0
Bank Sta=4985.8,4990.1
Exp/Cntr=0.3,0.1

Type RM Length L Ch R = 1,10945,304,304,304
BEGIN DESCRIPTION:
X18867
END DESCRIPTION:
XS GIS Cut Line= 2
      2468294.46     13865200.07      2467304.90     13865226.11
#Sta/Elev= 30
  4530.7  608.29  4590.9  602.15  4610.2  600.78  4720.2  585.49  4780.2  578.73
  4800.3  577.74  4830.3  574.16  4900.3  569.43  4906.7  569.02  4911.7  569.75
  4936.4  568.30  5000.3  565.31  5008.1  561.37  5008.4  560.87  5012.2  560.87
  5012.5  561.37  5020.3  562.10  5030.3  565.47  5040.3  566.97  5070.3  566.45
  5090.4  567.59  5120.4  567.63  5220.4  573.91  5250.4  576.42  5291.8  577.63
  5370.4  582.55  5440.5  589.56  5460.5  592.44  5490.5  594.02  5520.6  596.76
#Mann=5,-1,0
  4530.7    0.12       0  4590.9   0.035       0  4936.4    0.12       0
  5008.1    0.05       0  5012.5    0.12       0
Bank Sta=5008.1,5012.5
Exp/Cntr=0.3,0.1

Type RM Length L Ch R = 1,10641,469,469,469
BEGIN DESCRIPTION:
Devil Hollow 22.0
END DESCRIPTION:
XS GIS Cut Line= 3
      2468174.99     13864825.00      2467775.00     13864925.00
      2467375.01     13865025.00
#Sta/Elev= 30
  4587.6  595.25  4639.1  590.47  4688.1  583.57  4775.7  577.30  4824.7  572.46
  4874.3  568.96  4886.5  568.33  4899.4  569.29  4948.4  565.19  4958.7  565.77
  4969.0  564.63  4974.1  562.75  4976.7  560.87  4981.9  561.13  4987.4  560.14
  4987.7  559.64  4991.8  560.14  4997.3  565.04  5017.9  565.83  5082.4  564.95
  5113.3  566.97  5133.9  567.06  5182.9  569.44  5265.3  575.66  5270.5  575.27
  5319.4  580.52  5340.1  580.50  5360.7  582.54  5371.0  582.74  5412.2  587.18
#Mann=4,-1,0
  4587.6    0.07       0  4874.3    0.12       0  4987.4    0.05       0
  4991.8    0.12       0
Bank Sta=4987.4,4991.8
Exp/Cntr=0.3,0.1

Type RM Length L Ch R = 1,10172,446,446,446
BEGIN DESCRIPTION:
Devil Hollow 21.0
END DESCRIPTION:
XS GIS Cut Line= 3
      2467925.01     13864575.01      2467825.00     13864475.00
      2467425.03     13864325.01
#Sta/Elev= 30
  4853.0  577.18  4923.7  570.18  4952.0  567.95  4959.1  567.85  4966.1  566.34
  4997.1  565.05  5004.2  563.04  5009.6  564.14  5015.8  560.16  5024.1  559.40
  5024.4  558.90  5028.5  558.90  5028.9  559.40  5047.8  561.49  5064.7  562.69
  5070.1  562.33  5079.9  563.07  5095.0  562.98  5119.9  564.52  5143.0  565.03
  5205.4  566.38  5218.7  567.64  5272.1  569.05  5290.8  570.94  5296.1  570.92
  5336.2  575.79  5346.0  577.60  5349.5  577.59  5357.5  578.79  5421.6  584.51
#Mann=5,-1,0
  4853.0    0.07       0  5024.1    0.05       0  5028.9    0.07       0
  5143.0    0.12       0  5349.5     0.1       0
Bank Sta=5024.1,5028.9
Exp/Cntr=0.3,0.1

Type RM Length L Ch R = 1,9726,487,487,487
BEGIN DESCRIPTION:
Devil Hollow 20.0
END DESCRIPTION:
XS GIS Cut Line= 5
      2468477.46     13864236.34      2468013.00     13864075.00
      2467775.00     13864075.00      2467600.68     13864075.00
      2466934.44     13864056.20
#Sta/Elev= 30
  4274.6  597.52  4393.6  594.49  4412.7  592.87  4474.9  589.91  4583.2  585.74
  4679.5  581.59  4718.5  578.74  4774.3  576.31  4876.6  564.92  4924.3  560.76
  4944.3  560.60  4964.3  558.42  4981.8  554.12  4982.2  553.62  4986.7  554.12
  5001.8  561.76  5092.0  566.37  5160.6  568.92  5264.3  574.34  5334.3  579.38
  5384.4  581.50  5434.4  586.92  5564.4  593.80  5646.1  600.52  5704.5  607.11
  5744.5  612.65  5794.5  617.67  5824.5  621.94  5834.5  622.91  5845.1  622.85
#Mann=8,-1,0
  4274.6    0.07       0  4583.2   0.035       0  4876.6    0.07       0
  4981.8    0.05       0  4986.7    0.07       0  5092.0   0.035       0
  5160.6    0.07       0  5646.1   0.035       0
Bank Sta=4981.8,4986.7
Exp/Cntr=0.3,0.1

Type RM Length L Ch R = 1,9239,466,466,466
BEGIN DESCRIPTION:
Devil Hollow 19.0
END DESCRIPTION:
XS GIS Cut Line= 5
      2468479.63     13863711.15      2468061.41     13863671.60
      2467875.00     13863625.00      2467833.54     13863616.71
      2467051.67     13863578.77
#Sta/Elev= 30
  4387.8  599.61  4432.6  597.45  4443.2  596.16  4513.0  591.26  4754.1  579.04
  4774.1  577.00  4807.9  575.00  4898.0  564.89  4917.6  562.29  4982.0  556.67
  4995.0  553.84  4995.4  553.34  4999.6  553.34  5000.0  553.84  5060.9  556.39
  5210.9  568.72  5231.1  571.24  5251.1  571.77  5321.2  576.82  5386.7  580.64
  5451.3  583.41  5493.9  586.76  5501.4  587.85  5511.4  586.62  5521.4  586.81
  5571.5  589.79  5681.6  601.49  5701.6  604.29  5771.7  607.20  5825.1  607.37
#Mann=7,-1,0
  4387.8    0.12       0  4443.2    0.07       0  4898.0   0.035       0
  4995.0   0.035       0  5000.0   0.035       0  5210.9    0.07       0
  5493.9    0.12       0
Bank Sta=4995,5000
Exp/Cntr=0.3,0.1

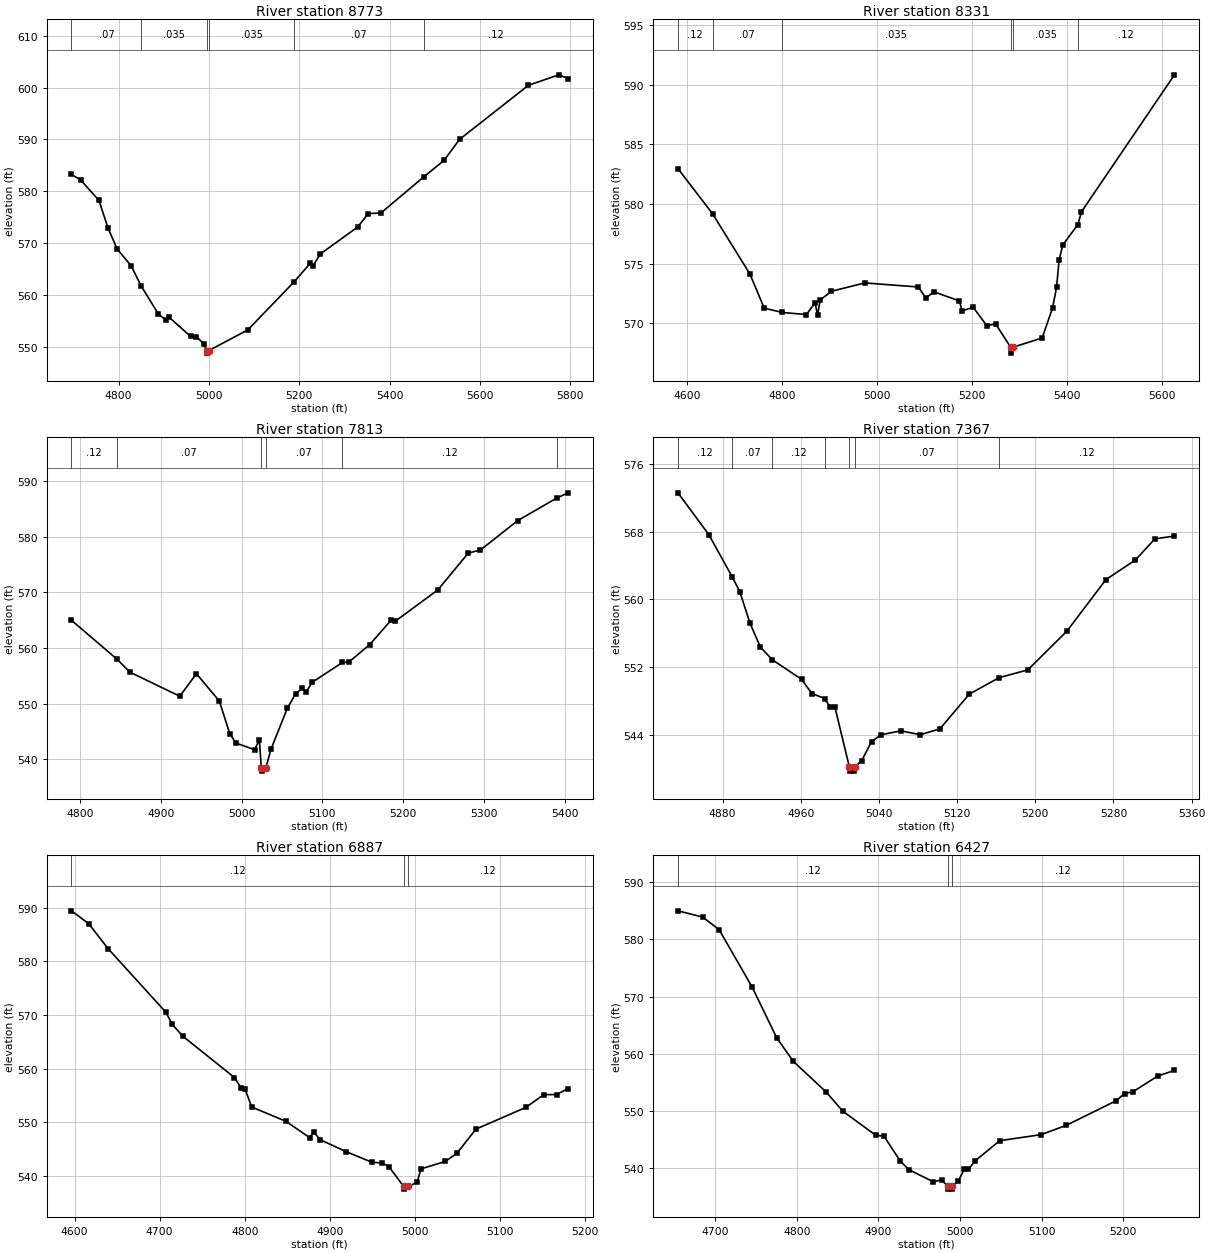
Type RM Length L Ch R = 1,8773,442,442,442
BEGIN DESCRIPTION:
Devil Hollow 18.0
END DESCRIPTION:
XS GIS Cut Line= 4
      2468124.97     13863125.00      2467825.00     13863175.00
      2467592.29     13863268.08      2467095.02     13863489.80
#Sta/Elev= 30
  4695.8  583.26  4716.0  582.18  4756.6  578.24  4776.9  572.83  4797.1  568.83
  4827.6  565.64  4850.3  561.67  4888.4  556.27  4906.1  555.05  4911.2  555.73
  4959.4  551.98  4972.0  551.95  4989.8  550.49  4994.9  549.25  4995.2  548.75
  4999.9  549.25  5086.1  553.23  5189.1  562.56  5224.7  566.13  5230.1  565.50
  5246.4  567.88  5329.3  573.09  5352.5  575.67  5381.2  575.83  5475.4  582.76
  5520.6  585.96  5554.8  590.01  5707.4  600.46  5774.8  602.48  5795.0  601.76
#Mann=6,-1,0
  4695.8    0.07       0  4850.3   0.035       0  4994.9   0.035       0
  4999.9   0.035       0  5189.1    0.07       0  5475.4    0.12       0
Bank Sta=4994.9,4999.9
Exp/Cntr=0.3,0.1

Type RM Length L Ch R = 1,8331,518,518,518
BEGIN DESCRIPTION:
Devil Hollow 17.0
END DESCRIPTION:
XS GIS Cut Line= 3
      2468225.01     13862875.00      2468023.67     13862845.91
      2467248.86     13862513.10
#Sta/Elev= 30
  4580.3  582.97  4653.2  579.19  4731.9  574.15  4762.2  571.28  4799.6  570.92
  4851.2  570.74  4869.3  571.72  4874.8  570.71  4880.2  571.96  4903.8  572.69
  4974.4  573.39  5087.0  573.05  5103.1  572.12  5119.7  572.65  5173.7  571.88
  5179.2  571.05  5202.7  571.35  5231.7  569.80  5249.8  569.97  5281.6  568.01
  5282.0  567.51  5286.9  568.01  5348.2  568.78  5370.0  571.29  5378.5  573.01
  5383.9  575.34  5391.8  576.58  5423.5  578.28  5431.0  579.35  5627.0  590.82
#Mann=6,-1,0
  4580.3    0.12       0  4653.2    0.07       0  4799.6   0.035       0
  5281.6   0.035       0  5286.9   0.035       0  5423.5    0.12       0
Bank Sta=5281.6,5286.9
Exp/Cntr=0.3,0.1

Type RM Length L Ch R = 1,7813,446,446,446
BEGIN DESCRIPTION:
Devil Hollow 16.0
END DESCRIPTION:
XS GIS Cut Line= 3
      2468125.01     13862325.00      2467925.00     13862275.00
      2467523.70     13862200.08
#Sta/Elev= 30
  4789.5  564.98  4846.1  557.94  4861.7  555.65  4923.5  551.31  4944.1  555.37
  4972.5  550.42  4985.4  544.54  4993.1  542.88  5016.0  541.69  5022.0  543.44
  5024.4  538.33  5024.8  537.83  5029.8  538.33  5036.4  541.79  5056.7  549.19
  5066.9  551.76  5074.7  552.71  5079.8  552.05  5087.2  553.81  5124.8  557.39
  5132.4  557.43  5158.4  560.58  5185.1  565.01  5190.2  564.81  5242.9  570.46
  5280.5  577.08  5295.6  577.63  5341.5  582.91  5389.7  586.96  5403.9  587.92
#Mann=6,-1,0
  4789.5    0.12       0  4846.1    0.07       0  5024.4    0.05       0
  5029.8    0.07       0  5124.8    0.12       0  5389.7     0.1       0
Bank Sta=5024.4,5029.8
Exp/Cntr=0.3,0.1

Type RM Length L Ch R = 1,7367,480,480,480
BEGIN DESCRIPTION:
Devil Hollow 15.0
END DESCRIPTION:
XS GIS Cut Line= 3
      2468225.03     13861824.99      2468075.00     13861875.00
      2467725.04     13861875.00
#Sta/Elev= 30
  4834.3  572.58  4865.9  567.65  4890.0  562.63  4897.6  560.92  4908.1  557.19
  4918.7  554.38  4930.9  552.88  4960.8  550.57  4971.4  548.90  4984.5  548.31
  4989.8  547.32  4994.9  547.32  5009.7  540.24  5010.1  539.74  5014.7  539.74
  5015.2  540.24  5022.4  540.98  5032.4  543.23  5042.4  544.04  5062.4  544.49
  5082.4  544.04  5102.4  544.73  5132.4  548.82  5163.0  550.77  5192.4  551.69
  5232.4  556.27  5272.4  562.35  5302.4  564.65  5322.4  567.15  5342.4  567.48
#Mann=7,-1,0
  4834.3    0.12       0  4890.0    0.07       0  4930.9    0.12       0
  4984.5    0.07       0  5009.7    0.05       0  5015.2    0.07       0
  5163.0    0.12       0
Bank Sta=5009.7,5015.2
Exp/Cntr=0.3,0.1

Type RM Length L Ch R = 1,6887,460,460,460
BEGIN DESCRIPTION:
Devil Hollow 14.0
END DESCRIPTION:
XS GIS Cut Line= 3
      2468475.02     13861475.00      2468075.00     13861425.00
      2467925.01     13861325.01
#Sta/Elev= 30
  4596.4  589.42  4616.6  587.03  4639.3  582.38  4707.3  570.49  4714.8  568.23
  4727.4  566.00  4787.9  558.32  4795.5  556.44  4800.5  556.12  4808.1  552.82
  4848.4  550.15  4876.1  547.12  4881.1  548.12  4888.7  546.72  4918.9  544.50
  4949.1  542.53  4961.7  542.37  4969.3  541.70  4986.7  538.00  4987.1  537.50
  4992.3  538.00  5002.5  538.78  5007.0  541.27  5035.6  542.67  5049.1  544.16
  5071.6  548.69  5130.2  552.74  5151.3  555.13  5166.3  555.14  5179.8  556.26
#Mann=3,-1,0
  4596.4    0.12       0  4986.7    0.05       0  4992.3    0.12       0
Bank Sta=4986.7,4992.3
Exp/Cntr=0.3,0.1

Type RM Length L Ch R = 1,6427,433,433,433
BEGIN DESCRIPTION:
Devil Hollow 13.0
END DESCRIPTION:
XS GIS Cut Line= 3
      2468524.96     13861074.99      2468175.00     13861025.00
      2467924.97     13861075.01
#Sta/Elev= 30
  4654.3  584.96  4684.6  583.87  4704.8  581.67  4745.2  571.67  4775.5  562.76
  4795.7  558.69  4836.1  553.31  4856.3  549.99  4896.7  545.78  4906.8  545.63
  4927.0  541.24  4937.1  539.80  4967.4  537.65  4977.5  538.00  4984.8  536.88
  4985.3  536.38  4990.0  536.38  4990.4  536.88  4997.7  537.76  5005.3  539.82
  5010.4  539.82  5018.0  541.25  5048.6  544.83  5099.6  545.90  5130.2  547.51
  5191.4  551.81  5201.6  553.07  5211.8  553.36  5242.4  556.13  5262.8  557.10
#Mann=3,-1,0
  4654.3    0.12       0  4984.8    0.05       0  4990.4    0.12       0
Bank Sta=4984.8,4990.4
Exp/Cntr=0.3,0.1

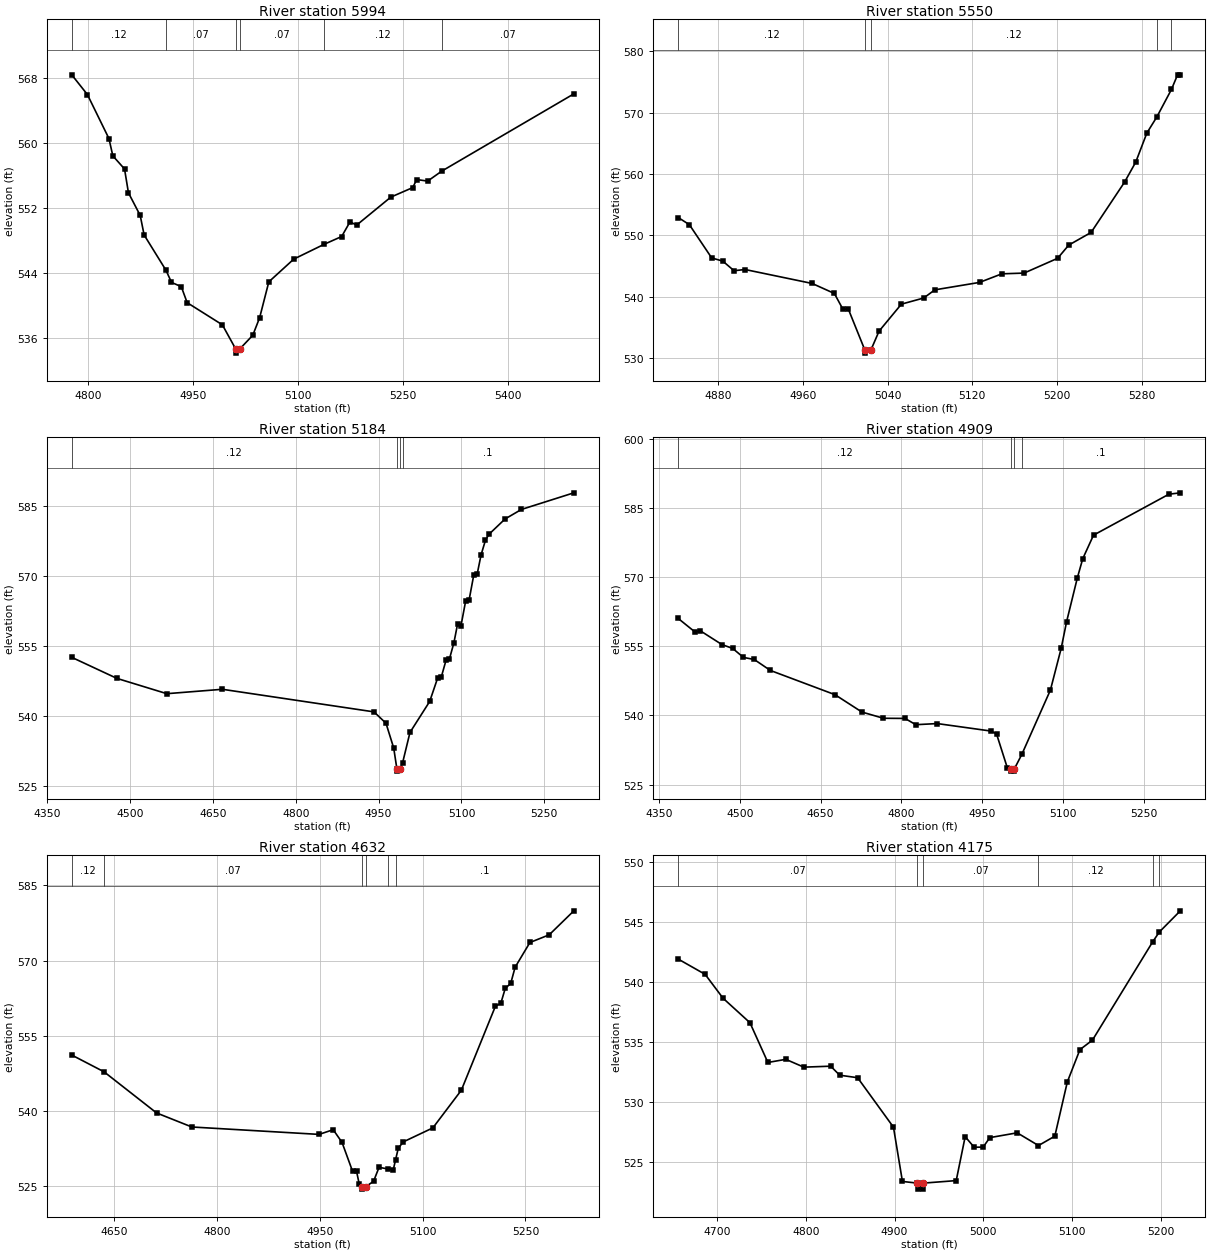
Type RM Length L Ch R = 1,5994,444,444,444
BEGIN DESCRIPTION:
Devil Hollow 12.0
END DESCRIPTION:
XS GIS Cut Line= 3
      2468524.97     13860774.98      2468325.00     13860675.00
      2467899.34     13860424.43
#Sta/Elev= 30
  4776.3  568.37  4798.6  565.95  4829.4  560.54  4835.0  558.41  4851.7  556.80
  4857.3  553.87  4874.1  551.09  4879.7  548.69  4911.1  544.33  4918.8  542.86
  4932.8  542.34  4941.2  540.37  4991.5  537.65  5010.6  534.67  5011.1  534.17
  5016.3  534.67  5035.0  536.37  5044.8  538.53  5057.9  542.93  5093.5  545.72
  5137.1  547.55  5162.0  548.50  5173.9  550.30  5183.4  549.90  5232.2  553.34
  5263.5  554.51  5269.3  555.50  5284.9  555.31  5305.1  556.54  5493.8  566.03
#Mann=6,-1,0
  4776.3    0.12       0  4911.1    0.07       0  5010.6    0.05       0
  5016.3    0.07       0  5137.1    0.12       0  5305.1    0.07       0
Bank Sta=5010.6,5016.3
Exp/Cntr=0.3,0.1

Type RM Length L Ch R = 1,5550,366,366,366
BEGIN DESCRIPTION:
Devil Hollow 11.0
END DESCRIPTION:
XS GIS Cut Line= 3
      2468674.99     13860524.98      2468625.00     13860375.00
      2468525.01     13860075.02
#Sta/Elev= 30
  4842.2  552.89  4852.7  551.73  4873.8  546.31  4884.3  545.79  4894.9  544.23
  4905.4  544.42  4968.7  542.15  4989.7  540.52  4997.7  537.97  5002.9  537.97
  5018.5  531.30  5019.0  530.80  5024.2  531.30  5031.9  534.38  5053.0  538.78
  5074.1  539.78  5084.6  541.11  5126.8  542.32  5147.9  543.72  5168.9  543.84
  5200.6  546.25  5211.1  548.40  5232.2  550.46  5263.8  558.65  5274.4  561.92
  5284.9  566.66  5294.3  569.27  5308.1  573.75  5313.9  576.14  5316.5  576.14
#Mann=5,-1,0
  4842.2    0.12       0  5018.5    0.05       0  5024.2    0.12       0
  5294.3     0.1       0  5308.1    0.12       0
Bank Sta=5018.5,5024.2
Exp/Cntr=0.3,0.1

Type RM Length L Ch R = 1,5184,275,275,275
BEGIN DESCRIPTION:
X18866
END DESCRIPTION:
XS GIS Cut Line= 3
      2468758.04     13860606.34      2468804.92     13860101.11
      2468478.36     13859867.86
#Sta/Elev= 30
  4394.7  552.56  4476.4  548.06  4566.8  544.79  4667.2  545.73  4941.7  540.90
  4963.4  538.47  4977.4  533.16  4983.1  528.73  4983.6  528.23  4988.9  528.73
  4993.4  529.98  5006.8  536.50  5042.5  543.13  5057.2  548.25  5063.4  548.31
  5072.0  551.91  5078.1  552.15  5086.3  555.67  5092.9  559.64  5099.0  559.25
  5107.6  564.61  5113.8  564.81  5122.4  570.26  5128.5  570.40  5135.5  574.48
  5143.3  577.55  5149.4  578.83  5178.9  582.15  5208.4  584.18  5303.4  587.74
#Mann=4,-1,0
  4394.7    0.12       0  4983.1    0.05       0  4988.9    0.12       0
  4993.4     0.1       0
Bank Sta=4983.1,4988.9
Exp/Cntr=0.3,0.1

Type RM Length L Ch R = 1,4909,277,277,277
BEGIN DESCRIPTION:
X18865
END DESCRIPTION:
XS GIS Cut Line= 2
      2469396.07     13859817.26      2468463.78     13859822.47
#Sta/Elev= 30
  4385.7  561.05  4416.8  558.12  4426.8  558.37  4466.8  555.39  4486.8  554.55
  4506.8  552.60  4526.8  552.15  4556.8  549.77  4676.8  544.51  4726.8  540.74
  4766.8  539.39  4806.8  539.36  4826.8  538.00  4866.8  538.24  4966.8  536.61
  4976.8  535.98  4996.8  528.63  5003.6  528.42  5004.1  527.92  5009.4  527.92
  5009.9  528.42  5023.7  531.55  5076.8  545.52  5096.8  554.58  5106.8  560.33
  5126.8  569.86  5136.8  574.01  5156.8  579.13  5296.8  588.02  5318.0  588.32
#Mann=4,-1,0
  4385.7    0.12       0  5003.6    0.05       0  5009.9    0.12       0
  5023.7     0.1       0
Bank Sta=5003.6,5009.9
Exp/Cntr=0.3,0.1

Type RM Length L Ch R = 1,4632,457,457,457
BEGIN DESCRIPTION:
Devil Hollow 10.0
END DESCRIPTION:
XS GIS Cut Line= 3
      2469275.01     13859675.00      2468875.00     13859575.00
      2468624.98     13859775.02
#Sta/Elev= 30
  4588.1  551.10  4635.2  547.75  4711.8  539.53  4763.3  536.72  4948.9  535.24
  4969.5  536.18  4982.4  533.64  4997.8  527.85  5003.6  527.85  5007.6  525.24
  5010.9  524.80  5011.4  524.30  5017.2  524.80  5028.4  525.87  5036.4  528.66
  5049.3  528.33  5057.2  528.21  5060.5  530.15  5064.4  532.45  5071.7  533.74
  5114.9  536.54  5156.5  544.08  5206.1  560.84  5214.1  561.46  5220.5  564.42
  5228.5  565.42  5234.9  568.65  5256.5  573.60  5284.6  575.13  5320.6  579.93
#Mann=6,-1,0
  4588.1    0.12       0  4635.2    0.07       0  5010.9    0.05       0
  5017.2    0.07       0  5049.3    0.12       0  5060.5     0.1       0
Bank Sta=5010.9,5017.2
Exp/Cntr=0.3,0.1

Type RM Length L Ch R = 1,4175,478,478,478
BEGIN DESCRIPTION:
Devil Hollow 9.0
END DESCRIPTION:
XS GIS Cut Line= 3
      2469025.03     13859225.00      2468675.00     13859275.00
      2468525.01     13859424.99
#Sta/Elev= 30
  4656.3  541.91  4686.6  540.64  4706.8  538.65  4737.1  536.61  4757.3  533.30
  4777.5  533.56  4797.8  532.91  4828.1  532.99  4838.2  532.24  4858.4  532.03
  4898.8  527.91  4908.9  523.39  4925.8  523.25  4926.3  522.75  4931.9  522.75
  4932.4  523.25  4969.5  523.46  4979.6  527.12  4989.7  526.24  4999.8  526.25
  5007.4  527.04  5038.2  527.44  5062.2  526.38  5080.6  527.16  5094.7  531.68
  5108.9  534.37  5123.0  535.16  5190.8  543.34  5198.4  544.17  5222.0  545.93
#Mann=6,-1,0
  4656.3    0.07       0  4925.8    0.05       0  4932.4    0.07       0
  5062.2    0.12       0  5190.8     0.1       0  5198.4    0.12       0
Bank Sta=4925.8,4932.4
Exp/Cntr=0.3,0.1

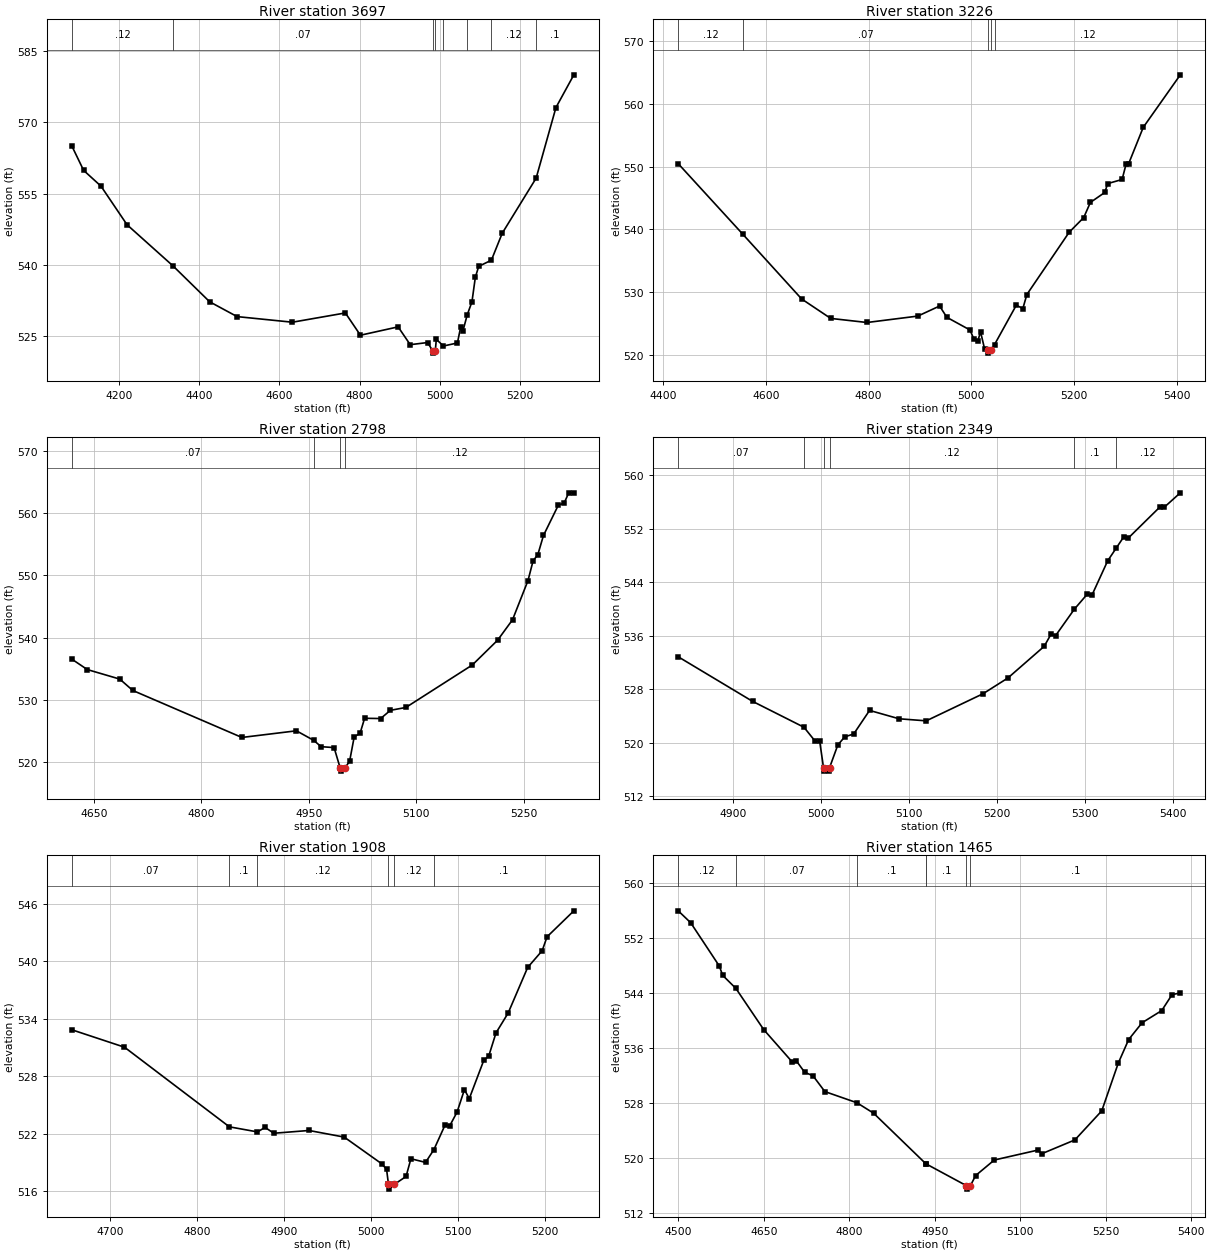
Type RM Length L Ch R = 1,3697,471,471,471
BEGIN DESCRIPTION:
Devil Hollow 8.0
END DESCRIPTION:
XS GIS Cut Line= 3
      2469174.96     13858625.02      2468375.00     13859075.00
      2468075.04     13859224.98
#Sta/Elev= 30
  4081.8  565.07  4111.4  559.90  4154.7  556.58  4219.8  548.45  4334.8  539.76
  4426.0  532.23  4494.5  529.11  4632.5  527.93  4764.7  529.88  4802.3  525.19
  4896.4  526.95  4926.6  523.20  4970.0  523.65  4982.6  521.92  4983.1  521.42
  4989.2  521.92  4991.7  524.32  5009.6  522.92  5044.4  523.56  5052.7  526.99
  5058.3  526.14  5068.9  529.49  5080.7  532.23  5089.1  537.38  5097.5  539.69
  5129.2  540.99  5156.2  546.66  5240.9  558.27  5290.3  573.13  5335.0  580.02
#Mann=8,-1,0
  4081.8    0.12       0  4334.8    0.07       0  4982.6    0.05       0
  4989.2    0.07       0  5009.6    0.12       0  5068.9     0.1       0
  5129.2    0.12       0  5240.9     0.1       0
Bank Sta=4982.6,4989.2
Exp/Cntr=0.3,0.1

Type RM Length L Ch R = 1,3226,428,428,428
BEGIN DESCRIPTION:
Devil Hollow 7.0
END DESCRIPTION:
XS GIS Cut Line= 3
      2468875.00     13858275.00      2468475.00     13858675.00
      2468075.00     13858775.00
#Sta/Elev= 30
  4429.3  550.46  4554.7  539.28  4669.7  528.95  4726.3  525.86  4797.0  525.21
  4896.0  526.23  4938.4  527.83  4952.6  526.03  4997.6  524.02  5005.3  522.55
  5013.0  522.33  5018.2  523.71  5025.9  521.07  5032.9  520.84  5033.4  520.34
  5039.5  520.84  5045.5  521.71  5087.8  527.96  5100.6  527.43  5108.4  529.66
  5190.8  539.56  5219.2  541.90  5232.1  544.30  5260.4  545.90  5265.6  547.29
  5293.9  547.95  5301.6  550.37  5306.8  550.49  5335.1  556.24  5407.3  564.59
#Mann=5,-1,0
  4429.3    0.12       0  4554.7    0.07       0  5032.9    0.05       0
  5039.5    0.07       0  5045.5    0.12       0
Bank Sta=5032.9,5039.5
Exp/Cntr=0.3,0.1

Type RM Length L Ch R = 1,2798,449,449,449
BEGIN DESCRIPTION:
Devil Hollow 6.0
END DESCRIPTION:
XS GIS Cut Line= 3
      2468424.98     13858125.04      2468275.00     13858475.00
      2468075.00     13858725.00
#Sta/Elev= 30
  4619.3  536.54  4641.0  534.86  4686.3  533.33  4704.5  531.50  4856.8  523.95
  4932.9  525.02  4957.0  523.49  4967.4  522.47  4985.5  522.32  4994.0  519.04
  4994.5  518.54  5000.7  519.04  5007.2  520.15  5013.6  524.06  5021.7  524.60
  5028.1  527.03  5050.5  526.99  5064.1  528.31  5085.7  528.77  5178.5  535.60
  5213.7  539.57  5234.6  542.86  5256.2  549.17  5263.4  552.37  5269.8  553.28
  5277.8  556.41  5298.6  561.29  5306.6  561.60  5313.0  563.24  5320.2  563.26
#Mann=4,-1,0
  4619.3    0.07       0  4957.0    0.12       0  4994.0    0.05       0
  5000.7    0.12       0
Bank Sta=4994,5000.7
Exp/Cntr=0.3,0.1

Type RM Length L Ch R = 1,2349,441,441,441
BEGIN DESCRIPTION:
Devil Hollow 5.0
END DESCRIPTION:
XS GIS Cut Line= 3
      2468325.03     13858074.99      2468175.00     13858125.00
      2467774.96     13858225.01
#Sta/Elev= 30
  4837.7  532.86  4922.1  526.20  4980.6  522.32  4993.2  520.25  4998.4  520.25
  5002.8  516.26  5003.3  515.76  5009.1  515.76  5009.6  516.26  5019.0  519.66
  5026.8  520.88  5037.1  521.32  5055.1  524.84  5088.6  523.59  5119.5  523.28
  5184.0  527.33  5212.3  529.69  5253.5  534.42  5261.3  536.24  5266.4  536.01
  5287.8  539.98  5302.5  542.23  5307.7  542.05  5325.7  547.22  5335.1  549.06
  5343.7  550.75  5348.9  550.59  5385.0  555.26  5390.1  555.24  5408.2  557.38
#Mann=6,-1,0
  4837.7    0.07       0  4980.6    0.12       0  5002.8    0.05       0
  5009.6    0.12       0  5287.8     0.1       0  5335.1    0.12       0
Bank Sta=5002.8,5009.6
Exp/Cntr=0.3,0.1

Type RM Length L Ch R = 1,1908,443,443,443
BEGIN DESCRIPTION:
Devil Hollow 4.0
END DESCRIPTION:
XS GIS Cut Line= 3
      2468375.01     13857775.00      2468025.00     13857825.00
      2467824.97     13857925.02
#Sta/Elev= 30
  4655.8  532.87  4716.4  531.05  4837.0  522.74  4869.3  522.21  4878.0  522.68
  4888.1  522.07  4928.5  522.36  4969.0  521.67  5012.2  518.88  5017.7  518.31
  5019.9  516.74  5020.4  516.24  5026.7  516.74  5040.1  517.56  5045.7  519.41
  5062.5  519.03  5072.1  520.36  5084.8  522.90  5090.4  522.86  5098.8  524.29
  5107.2  526.62  5112.8  525.69  5129.5  529.69  5135.1  530.11  5143.5  532.54
  5157.5  534.62  5179.9  539.37  5196.6  541.12  5202.2  542.57  5233.0  545.28
#Mann=6,-1,0
  4655.8    0.07       0  4837.0     0.1       0  4869.3    0.12       0
  5019.9    0.05       0  5026.7    0.12       0  5072.1     0.1       0
Bank Sta=5019.9,5026.7
Exp/Cntr=0.3,0.1

Type RM Length L Ch R = 1,1465,474,474,474
BEGIN DESCRIPTION:
Devil Hollow 3.0
END DESCRIPTION:
XS GIS Cut Line= 3
      2468174.97     13857075.03      2467875.00     13857475.00
      2467725.02     13857824.96
#Sta/Elev= 30
  4499.8  555.99  4521.6  554.26  4571.6  547.98  4577.9  546.58  4600.9  544.69
  4649.8  538.68  4699.8  533.97  4707.0  534.13  4721.6  532.47  4736.2  531.96
  4757.0  529.66  4813.3  528.03  4842.5  526.51  4933.7  519.18  4934.7  519.12
  5005.4  515.95  5005.9  515.45  5012.3  515.95  5021.5  517.43  5054.2  519.69
  5130.3  521.13  5137.6  520.61  5195.6  522.62  5242.7  526.85  5271.7  533.81
  5289.9  537.24  5313.5  539.69  5347.9  541.46  5366.0  543.78  5380.5  544.03
#Mann=7,-1,0
  4499.8    0.12       0  4600.9    0.07       0  4813.3     0.1       0
  4933.7    0.07       0  4934.7     0.1       0  5005.4    0.05       0
  5012.3     0.1       0
Bank Sta=5005.4,5012.3
Exp/Cntr=0.3,0.1

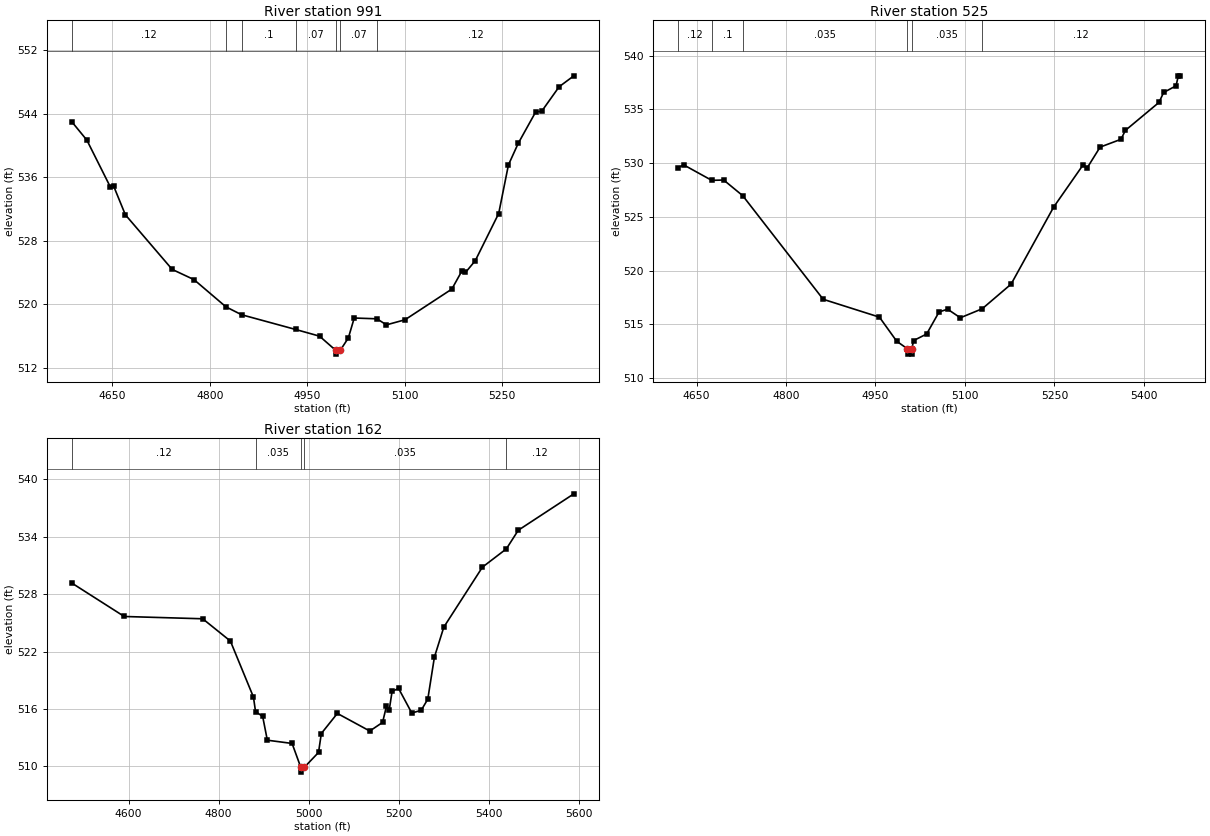
Type RM Length L Ch R = 1,991,466,466,466
BEGIN DESCRIPTION:
Devil Hollow 2.0
END DESCRIPTION:
XS GIS Cut Line= 3
      2468074.99     13856975.00      2467675.00     13857075.00
      2467374.96     13857275.02
#Sta/Elev= 30
  4587.6  542.98  4610.8  540.67  4646.9  534.79  4652.0  534.90  4670.1  531.28
  4742.2  524.41  4775.7  523.13  4825.0  519.70  4849.1  518.71  4932.2  516.86
  4969.0  516.02  4993.6  514.26  4994.1  513.76  5001.1  514.26  5013.4  515.80
  5022.4  518.30  5057.4  518.20  5072.0  517.44  5100.6  518.08  5172.7  521.94
  5187.7  524.15  5193.7  524.03  5208.7  525.50  5244.8  531.44  5259.8  537.55
  5274.8  540.25  5301.9  544.23  5310.9  544.28  5337.9  547.38  5360.5  548.75
#Mann=7,-1,0
  4587.6    0.12       0  4825.0    0.07       0  4849.1     0.1       0
  4932.2    0.07       0  4993.6    0.05       0  5001.1    0.07       0
  5057.4    0.12       0
Bank Sta=4993.6,5001.1
Exp/Cntr=0.3,0.1

Type RM Length L Ch R = 1,525,363,363,363
BEGIN DESCRIPTION:
Devil Hollow 1.0
END DESCRIPTION:
XS GIS Cut Line= 3
      2467975.01     13856775.00      2467625.00     13856625.00
      2467324.99     13856975.02
#Sta/Elev= 30
  4619.3  529.59  4628.4  529.84  4675.5  528.40  4695.5  528.43  4727.5  526.97
  4862.3  517.34  4956.6  515.68  4985.6  513.44  5003.4  512.74  5003.9  512.24
  5010.6  512.24  5011.1  512.74  5013.8  513.50  5035.8  514.11  5056.6  516.16
  5070.9  516.42  5092.3  515.62  5129.0  516.46  5177.4  518.75  5248.7  525.91
  5298.1  529.84  5304.7  529.54  5326.6  531.49  5361.7  532.22  5368.9  533.04
  5425.4  535.65  5433.1  536.57  5453.9  537.19  5457.8  538.12  5461.1  538.12
#Mann=6,-1,0
  4619.3    0.12       0  4675.5     0.1       0  4727.5   0.035       0
  5003.4   0.035       0  5011.1   0.035       0  5129.0    0.12       0
Bank Sta=5003.4,5011.1
Exp/Cntr=0.3,0.1

Type RM Length L Ch R = 1,162,0,0,0
BEGIN DESCRIPTION:
X18864
END DESCRIPTION:
XS GIS Cut Line= 3
      2467898.63     13856259.98      2467435.12     13856364.13
      2467058.39     13856881.17
#Sta/Elev= 30
  4473.8  529.17  4590.3  525.67  4764.5  525.43  4826.0  523.10  4877.2  517.24
  4881.8  515.73  4897.7  515.21  4908.0  512.73  4963.0  512.39  4982.3  509.89
  4982.8  509.39  4990.1  509.89  5021.7  511.45  5027.9  513.43  5063.5  515.53
  5135.5  513.69  5163.9  514.59  5172.4  516.26  5178.6  515.87  5185.0  517.83
  5199.4  518.15  5228.8  515.57  5249.7  515.86  5264.3  517.02  5279.0  521.42
  5299.9  524.56  5385.6  530.83  5438.7  532.74  5465.2  534.69  5588.6  538.50
#Mann=5,-1,0
  4473.8    0.12       0  4881.8   0.035       0  4982.3   0.035       0
  4990.1   0.035       0  5438.7    0.12       0
Bank Sta=4982.3,4990.1
Exp/Cntr=0.3,0.1

Chan Stop Cuts=-1