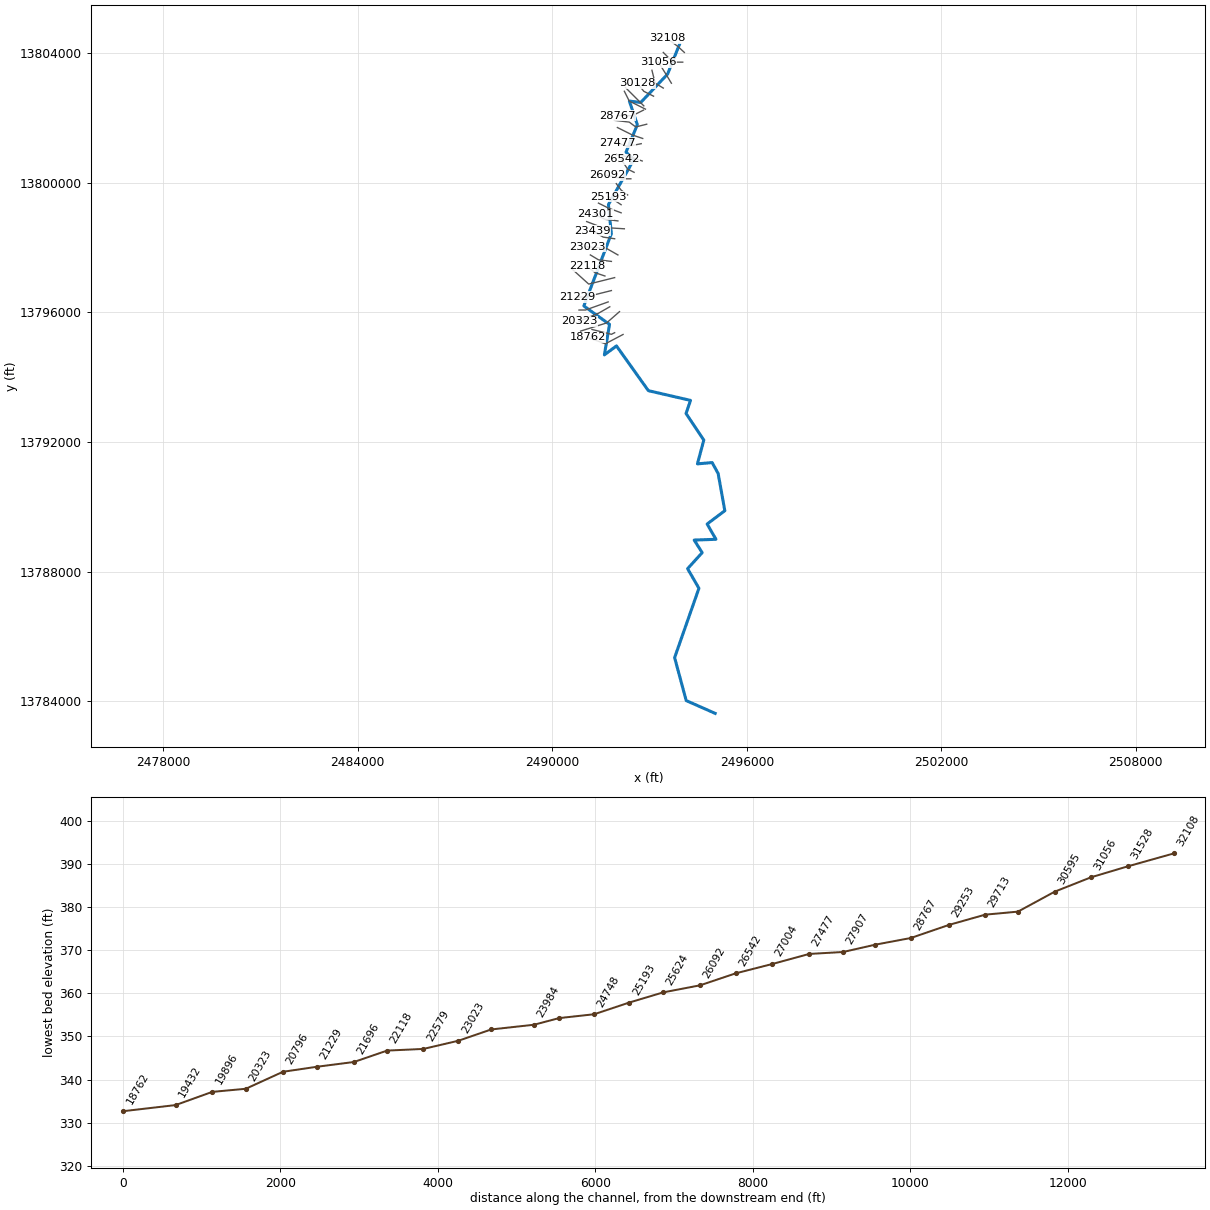
--- EAST ELM CREEK.prj (project) ---

Proj Title=EAST ELM CREEK Base Level Engineering
Current Plan=p01
Default Exp/Contr=0.3,0.1
English Units
Geom File=g01
Flow File=f01
Plan File=p01
Y Axis Title=Elevation
X Axis Title(PF)=Main Channel Distance
X Axis Title(XS)=Station
BEGIN DESCRIPTION:
EAST ELM CREEK
END DESCRIPTION:
DSS Export Rating Curves= 0
DSS Export Rating Curve Sorted= 0
DSS Export Volume Flow Curves= 0
DXF OffsetX= 0
DXF OffsetY= 0
DXF ScaleX= 1
DXF ScaleY= 10

--- EAST ELM CREEK.p01 (plan) ---

Plan Title=Multiple Run
Short Identifier=Multiple
Geom File=g01
Flow File=f01
Subcritical Flow
K Sum by GR= 0
Std Step Tol= 0.01
Critical Tol= 0.01
Num of Std Step Trials= 20
Max Error Tol= 0.3
Flow Tol Ratio= 0.001
Split Flow NTrial= 30
Split Flow Tol= 0.02
Split Flow Ratio= 0.02
Log Output Level= 0
Friction Slope Method= 1
Unsteady Friction Slope Method= 2
Unsteady Bridges Friction Slope Method= 1
Parabolic Critical Depth
Global Vel Dist=  1 , 1 , 1
Global Log Level= 0
CheckData=True
Encroach Param= -1, 0, 0, 0
BEGIN DESCRIPTION:
Multiple Run
END DESCRIPTION:

--- EAST ELM CREEK.f01 (steady flow) ---

Flow Title=Multiple
Number of Profiles=7
Profile Names=10-year,25-year,50-year,1pct_min,100-year,1pct_plu,500-year
River Rch & RM= EAST ELM CREEK,Reach-1,32108
     677    1084    1450     939    1873    3738    3095
River Rch & RM= EAST ELM CREEK,Reach-1,25193
     939    1524    2056    1341    2676    5340    4489
River Rch & RM= EAST ELM CREEK,Reach-1,15792
    1801    3010    4140    2747    5480   10935    9515
River Rch & RM= EAST ELM CREEK,Reach-1,9096
    1897    3163    4342    2873    5733   11439    9904
Boundary for River Rch & Prof#=EAST ELM CREEK,Reach-1,1
Up Type=0
Dn Type=3
Dn Slope=0.005
Boundary for River Rch & Prof#=EAST ELM CREEK,Reach-1,2
Up Type=0
Dn Type=3
Dn Slope=0.005
Boundary for River Rch & Prof#=EAST ELM CREEK,Reach-1,3
Up Type=0
Dn Type=3
Dn Slope=0.005
Boundary for River Rch & Prof#=EAST ELM CREEK,Reach-1,4
Up Type=0
Dn Type=3
Dn Slope=0.005
Boundary for River Rch & Prof#=EAST ELM CREEK,Reach-1,5
Up Type=0
Dn Type=3
Dn Slope=0.005
Boundary for River Rch & Prof#=EAST ELM CREEK,Reach-1,6
Up Type=0
Dn Type=3
Dn Slope=0.005
Boundary for River Rch & Prof#=EAST ELM CREEK,Reach-1,7
Up Type=0
Dn Type=3
Dn Slope=0.005

--- EAST ELM CREEK.g01 (geometry) ---

Geom Title=Existing Conditions
Program Version=4.10

River Reach=EAST ELM CREEK  ,Reach-1
Reach XY= 30
        2493925.       13804275.      2493558.56     13803358.21
      2492731.33     13802482.34      2492378.74     13802523.48
      2492625.26     13801794.96      2492274.94     13800944.99
      2492517.17     13800721.78      2491732.89     13799328.66
      2491823.47     13798430.83      2490974.79     13796199.91
      2491765.99     13795632.06      2491608.29     13794691.29
      2491981.49      13794966.1      2492964.89     13793585.38
      2494264.98     13793285.05      2494126.63     13792881.04
      2494674.76     13792059.78      2494478.54     13791326.46
      2494932.01     13791366.01      2495116.93     13791028.31
      2495322.96     13789880.85      2494776.96      13789469.1
      2495049.42     13788997.99      2494378.35     13788973.75
       2494624.3      13788585.7      2494174.68     13788090.85
      2494524.45     13787485.63      2493774.54     13785345.16
      2494132.31     13784019.28        2495025.       13783625.

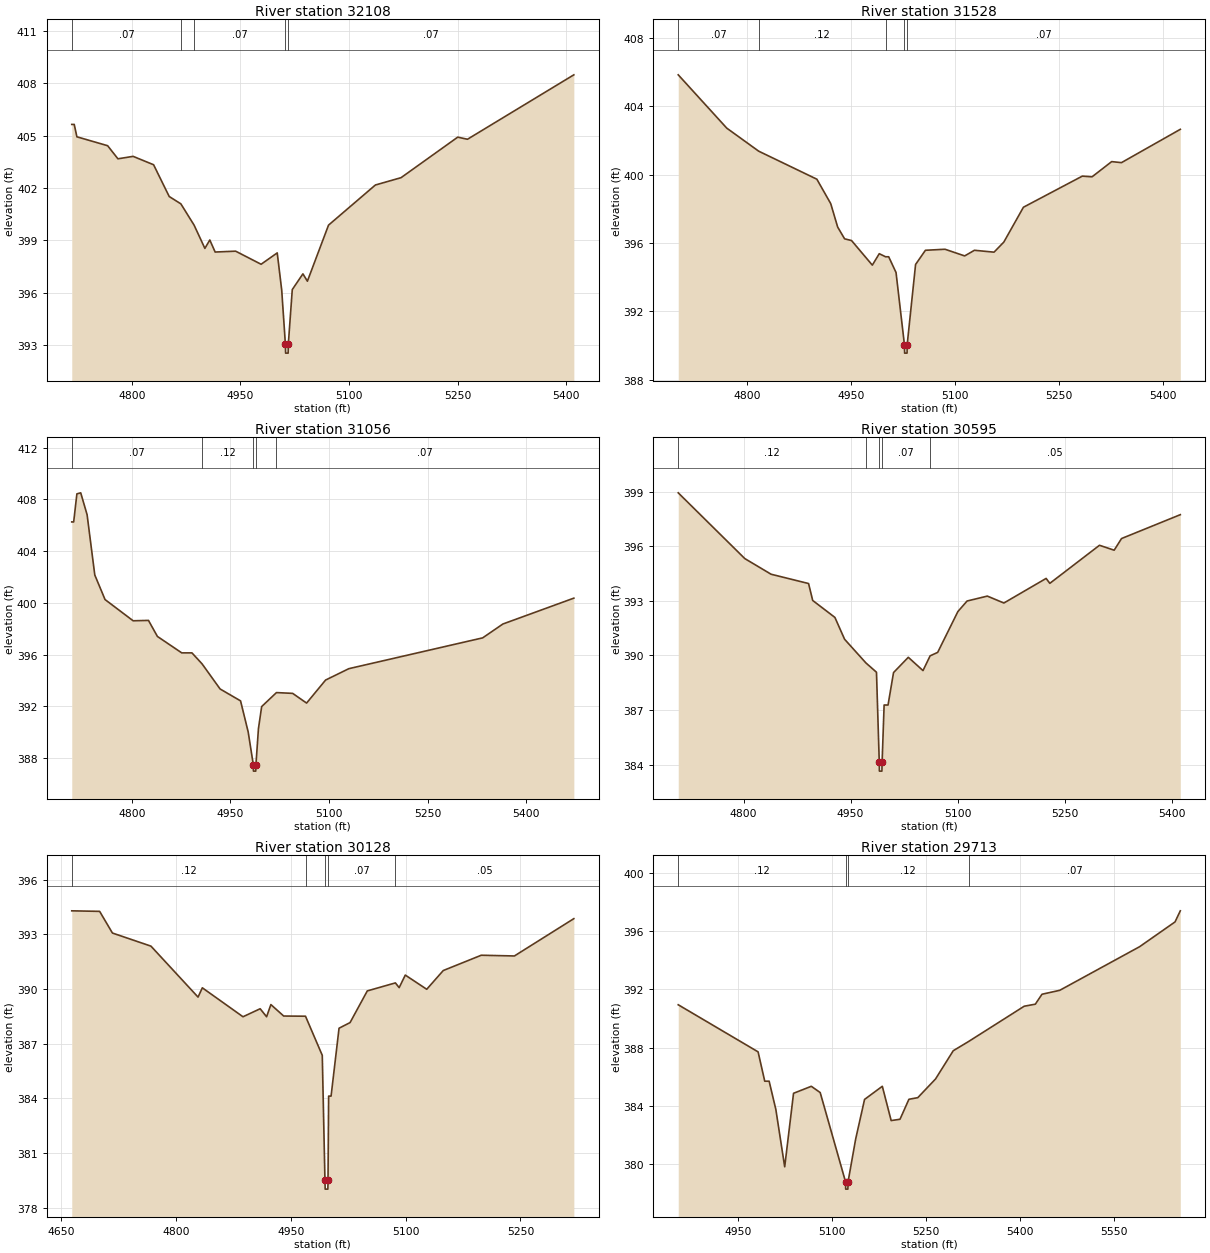
Type RM Length L Ch R = 1 ,32108   ,580,580,580
BEGIN DESCRIPTION:
EAST ELM CREEK 60.0
END DESCRIPTION:
XS GIS Cut Line= 3
      2494075.01     13804024.99      2493873.84     13804210.89
      2493535.91     13804460.44
#Sta/Elev= 30
  4716.8  405.64  4720.2  405.64  4723.9  404.93  4766.4  404.42  4780.6  403.67
  4801.6  403.81  4829.9  403.33  4851.5  401.51  4867.6  401.09  4885.9  399.87
  4900.8  398.54  4907.6  399.02    4915  398.33  4943.3  398.38  4978.5  397.63
  5000.8  398.28    5007  396.15  5012.1  393.04  5012.4  392.54  5015.9  392.54
  5016.1  393.04  5021.6  396.18  5036.3  397.08  5042.5  396.66  5071.7  399.87
  5136.5  402.17    5172  402.59  5250.3  404.91  5263.8  404.79  5410.8  408.48
#Mann= 5 ,-1 , 0
  4716.8     .07       0  4867.6     .12       0  4885.9     .07       0
  5012.1     .05       0  5016.1     .07       0
Bank Sta=5012.1,5016.1
XS Rating Curve= 0 ,0
Exp/Cntr=0.3,0.1

Type RM Length L Ch R = 1 ,31528   ,472,472,472
BEGIN DESCRIPTION:
EAST ELM CREEK 59.0
END DESCRIPTION:
XS GIS Cut Line= 3
      2494025.02       13803725.        2493725.       13803725.
      2493424.99     13804025.01
#Sta/Elev= 30
  4700.8  405.85  4770.8  402.73  4816.9  401.38  4900.8  399.74  4920.8  398.31
  4930.8  396.94  4940.8  396.25  4950.8  396.15  4980.8  394.71  4990.8  395.38
  4999.9   395.2  5004.4   395.2    5015  394.28  5027.1  390.06  5027.4  389.56
  5030.9  389.56  5031.1  390.06  5043.2  394.75  5057.4  395.58  5085.7  395.64
    5114  395.25  5128.1  395.58  5156.4  395.47  5170.5  396.06  5198.8   398.1
  5283.7  399.92  5297.8  399.88  5326.1  400.77  5340.2  400.71  5425.1  402.66
#Mann= 5 ,-1 , 0
  4700.8     .07       0  4816.9     .12       0  4999.9     .07       0
  5027.1     .05       0  5031.1     .07       0
Bank Sta=5027.1,5031.1
XS Rating Curve= 0 ,0
Exp/Cntr=0.3,0.1

Type RM Length L Ch R = 1 ,31056   ,461,461,461
BEGIN DESCRIPTION:
EAST ELM CREEK 58.0
END DESCRIPTION:
XS GIS Cut Line= 3
      2493675.01     13803074.98        2493525.       13803325.
      2493274.98     13803725.03
#Sta/Elev= 30
  4708.9  406.25  4711.8  406.25  4716.7  408.42  4722.5   408.5  4732.2  406.81
  4743.9  402.15  4759.5  400.25  4802.2  398.61  4825.5  398.64  4839.1   397.4
  4876.1  396.13  4891.6  396.13    4907  395.28  4934.4  393.34  4965.5  392.42
  4977.1  390.02  4984.9  387.49  4985.1  386.99  4988.6  386.99  4988.9  387.49
  4992.7  390.27  4997.6  391.98  5020.1  393.06  5044.7     393  5065.9  392.25
  5094.8  394.03  5130.2  394.91  5333.6  397.29  5364.3  398.36  5472.2  400.36
#Mann= 5 ,-1 , 0
  4708.9     .07       0    4907     .12       0  4984.9     .05       0
  4988.9     .12       0  5020.1     .07       0
Bank Sta=4984.9,4988.9
XS Rating Curve= 0 ,0
Exp/Cntr=0.3,0.1

Type RM Length L Ch R = 1 ,30595   ,467,467,467
BEGIN DESCRIPTION:
EAST ELM CREEK 57.0
END DESCRIPTION:
XS GIS Cut Line= 3
      2493424.99     13802925.01        2493175.       13803075.
      2493075.01     13803474.95
#Sta/Elev= 30
  4708.4  398.93  4801.7  395.32  4838.6  394.46  4891.1  393.95  4896.9  393.02
    4928  392.09  4941.6  390.89  4971.5  389.59  4986.3  389.08  4990.2  384.15
  4990.4  383.65  4993.9  383.65  4994.2  384.15    4997  387.28  5002.5  387.28
  5010.2  389.06  5030.9   389.9  5051.5  389.17  5061.5  389.98  5072.1  390.17
  5100.4  392.41  5113.3  392.99  5141.7  393.26  5164.9  392.88  5224.1  394.23
  5229.3  393.96  5298.9  396.05  5319.5  395.78  5329.8  396.42  5412.2  397.73
#Mann= 5 ,-1 , 0
  4708.4     .12       0  4971.5     .07       0  4990.2     .05       0
  4994.2     .07       0  5061.5     .05       0
Bank Sta=4990.2,4994.2
XS Rating Curve= 0 ,0
Exp/Cntr=0.3,0.1

Type RM Length L Ch R = 1 ,30128   ,415,415,415
BEGIN DESCRIPTION:
EAST ELM CREEK 56.0
END DESCRIPTION:
XS GIS Cut Line= 3
      2493125.02     13802674.99        2492825.       13802825.
        2492625.     13803075.01
#Sta/Elev= 30
  4664.1   394.3  4700.5  394.27  4717.2  393.08  4767.5  392.36    4829  389.56
  4834.6  390.07  4887.7  388.48  4910.1  388.92  4918.5  388.48  4924.1  389.15
  4940.8  388.52  4969.3  388.51  4991.2  386.36  4994.7  379.51    4995  379.01
  4998.5  379.01  4998.7  379.51  4999.5  384.12  5002.7  384.12  5013.1  387.85
  5027.5  388.16    5050   389.9  5086.7  390.34  5091.6  390.08  5099.6  390.77
  5127.6  389.99  5149.2  391.02  5198.8  391.86  5242.1  391.82  5319.7  393.87
#Mann= 5 ,-1 , 0
  4664.1     .12       0  4969.3     .07       0  4994.7     .05       0
  4998.7     .07       0  5086.7     .05       0
Bank Sta=4994.7,4998.7
XS Rating Curve= 0 ,0
Exp/Cntr=0.3,0.1

Type RM Length L Ch R = 1 ,29713   ,460,460,460
BEGIN DESCRIPTION:
EAST ELM CREEK 55.0
END DESCRIPTION:
XS GIS Cut Line= 4
      2492824.99     13802375.01        2492725.       13802475.
        2492425.       13802775.      2492259.09     13802940.91
#Sta/Elev= 30
  4854.9  390.95  4982.2  387.72  4992.8  385.71  4999.8  385.71  5010.5  383.77
  5024.6  379.84  5038.7  384.88    5067  385.36  5081.2  384.93  5121.6  378.81
  5121.8  378.31  5125.3  378.31  5125.6  378.81  5137.7  381.74  5151.9  384.46
  5180.2  385.36  5194.3  383.01  5208.4   383.1  5222.6  384.47  5236.7  384.58
    5265  385.86  5293.3   387.8  5317.7  388.43  5406.4  390.85  5424.1  390.99
  5434.7  391.67    5463  391.94  5590.3  394.93  5646.8  396.63  5655.2  397.39
#Mann= 4 ,-1 , 0
  4854.9     .12       0  5121.6     .05       0  5125.6     .12       0
  5317.7     .07       0
Bank Sta=5121.6,5125.6
XS Rating Curve= 0 ,0
Exp/Cntr=0.3,0.1

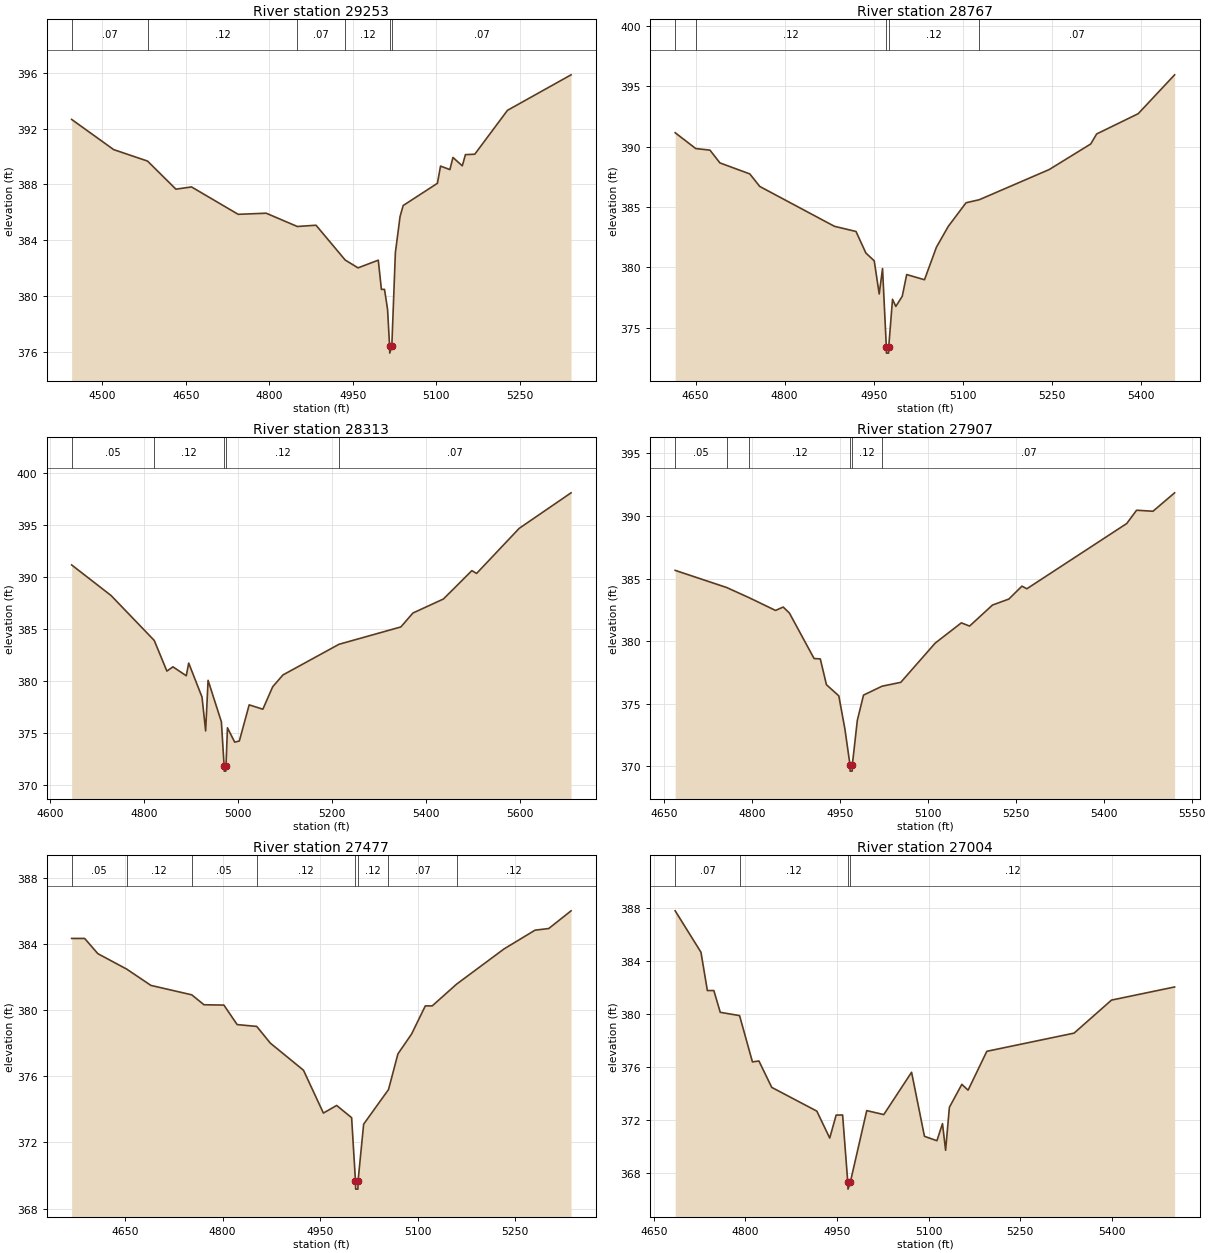
Type RM Length L Ch R = 1 ,29253   ,486,486,486
BEGIN DESCRIPTION:
EAST ELM CREEK 54.0
END DESCRIPTION:
XS GIS Cut Line= 4
      2492875.04     13802274.98        2492375.       13802525.
        2492325.       13802625.      2492223.91     13802827.17
#Sta/Elev= 30
    4445  392.65  4520.5  390.49  4581.3  389.67  4632.3  387.66  4660.3  387.82
  4744.1  385.86  4794.4  385.94  4850.3  384.99  4883.9  385.08  4936.3  382.59
  4959.3  382.03  4995.7  382.58  5001.3  380.49  5006.9  380.49  5012.4  379.05
    5016  376.43  5016.3  375.93    5020  376.43  5026.4  383.12  5034.8   385.7
  5040.4  386.49  5101.9  388.08  5107.5  389.31  5124.3  389.06  5129.8  389.93
  5146.6  389.33  5152.2  390.13    5169  390.16  5227.7   393.3  5341.9  395.84
#Mann= 6 ,-1 , 0
    4445     .07       0  4581.3     .12       0  4850.3     .07       0
  4936.3     .12       0    5016     .05       0    5020     .07       0
Bank Sta=5016,5020
XS Rating Curve= 0 ,0
Exp/Cntr=0.3,0.1

Type RM Length L Ch R = 1 ,28767   ,454,454,454
BEGIN DESCRIPTION:
EAST ELM CREEK 53.0
END DESCRIPTION:
XS GIS Cut Line= 5
      2492814.92     13802244.96        2492675.       13802175.
        2492475.       13802075.        2492275.       13802075.
      2492013.74       13802075.
#Sta/Elev= 30
  4615.6  391.14  4650.3  389.83  4674.2   389.7    4691  388.64  4741.3  387.73
  4758.1  386.69  4883.8  383.39  4920.2  382.96  4936.9  381.17  4950.9  380.53
  4959.3  377.78  4964.9  379.89  4971.3  373.38  4971.5  372.88    4975  372.88
  4975.3  373.38  4981.7  377.34  4987.3  376.75  4998.1  377.59  5005.6  379.39
  5035.6  378.96  5055.6  381.65  5075.6  383.38  5105.6  385.34  5127.8  385.59
  5245.6  388.09  5315.6  390.21  5325.6  391.04  5395.6  392.72  5456.9  395.94
#Mann= 5 ,-1 , 0
  4615.6     .07       0  4650.3     .12       0  4971.3     .05       0
  4975.3     .12       0  5127.8     .07       0
Bank Sta=4971.3,4975.3
XS Rating Curve= 0 ,0
Exp/Cntr=0.3,0.1

Type RM Length L Ch R = 1 ,28313   ,406,406,406
BEGIN DESCRIPTION:
EAST ELM CREEK 52.0
END DESCRIPTION:
XS GIS Cut Line= 5
      2492914.02     13801809.75        2492775.       13801775.
        2492575.       13801725.        2492375.       13801875.
      2491915.49     13801929.64
#Sta/Elev= 30
  4645.5  391.17  4729.5  388.22  4821.2   383.9  4848.1  380.95    4861  381.36
  4889.3   380.5  4894.5  381.72  4922.8  378.45  4930.5  375.19  4935.7  380.06
    4964  376.07  4969.8  371.82    4970  371.32  4973.5  371.32  4973.8  371.82
  4976.9  375.49  4992.4  374.11  5002.2  374.22  5023.1   377.7  5052.2  377.28
  5073.1  379.44    5095  380.58  5214.1  383.53  5345.7   385.2  5371.4  386.54
  5436.3  387.89  5496.7  390.62  5506.8  390.35  5597.4  394.69  5707.7  398.11
#Mann= 5 ,-1 , 0
  4645.5     .05       0  4821.2     .12       0  4969.8     .05       0
  4973.8     .12       0  5214.1     .07       0
Bank Sta=4969.8,4973.8
XS Rating Curve= 0 ,0
Exp/Cntr=0.3,0.1

Type RM Length L Ch R = 1 ,27907   ,430,430,430
BEGIN DESCRIPTION:
EAST ELM CREEK 51.0
END DESCRIPTION:
XS GIS Cut Line= 5
      2492789.97     13801370.01        2492625.       13801425.
        2492475.       13801475.        2492275.       13801575.
      2492009.46     13801707.77
#Sta/Elev= 30
  4668.4  385.66  4756.3  384.29  4794.5  383.48  4839.7  382.46  4852.8  382.73
  4863.4  382.25  4905.5  378.62  4916.1  378.59  4926.6  376.53  4947.7  375.64
  4958.2  372.97  4966.8  370.13    4967  369.63  4970.5  369.63  4970.8  370.13
  4979.3  373.68  4989.9   375.7  5021.5  376.41  5053.5  376.72  5112.2  379.85
  5156.9  381.47  5170.9  381.21    5210  382.89    5238  383.37  5260.3   384.4
  5268.7  384.19  5439.2   389.4    5456  390.46    5484  390.38  5520.9  391.85
#Mann= 6 ,-1 , 0
  4668.4     .05       0  4756.3     .07       0  4794.5     .12       0
  4966.8     .05       0  4970.8     .12       0  5021.5     .07       0
Bank Sta=4966.8,4970.8
XS Rating Curve= 0 ,0
Exp/Cntr=0.3,0.1

Type RM Length L Ch R = 1 ,27477   ,473,473,473
BEGIN DESCRIPTION:
EAST ELM CREEK 50.0
END DESCRIPTION:
XS GIS Cut Line= 5
      2492744.57     13801208.91        2492575.       13801175.
        2492325.       13801125.        2492175.       13801175.
      2492002.42     13801232.53
#Sta/Elev= 30
    4568  384.34    4588  384.34  4608.3  383.42  4652.9  382.48  4689.9   381.5
  4752.7  380.93  4771.5  380.33  4802.1  380.31  4822.5  379.13  4852.6  379.02
  4873.5  378.01  4924.5  376.37  4955.1  373.78  4975.5  374.24  4998.5   373.5
  5004.4  369.68  5004.7  369.18  5008.2  369.18  5008.4  369.68    5017  373.11
  5055.2   375.2  5069.7  377.36  5090.7  378.56  5111.8  380.26  5122.4  380.26
    5160  381.58    5233  383.71  5280.5  384.84  5301.6  384.94  5335.9  386.01
#Mann= 8 ,-1 , 0
    4568     .05       0  4652.9     .12       0  4752.7     .05       0
  4852.6     .12       0  5004.4     .05       0  5008.4     .12       0
  5055.2     .07       0    5160     .12       0
Bank Sta=5004.4,5008.4
XS Rating Curve= 0 ,0
Exp/Cntr=0.3,0.1

Type RM Length L Ch R = 1 ,27004   ,462,462,462
BEGIN DESCRIPTION:
EAST ELM CREEK 49.0
END DESCRIPTION:
XS GIS Cut Line= 3
      2492775.02     13800674.99        2492475.       13800775.
      2491983.74     13800875.07
#Sta/Elev= 30
    4685   387.8  4727.2  384.68  4737.7  381.79  4748.3  381.79  4758.8  380.15
  4790.4   379.9  4811.5  376.41  4822.1  376.48  4843.1  374.49  4916.9   372.7
    4938  370.67  4948.5   372.4  4959.1  372.41  4967.6  367.32  4967.9  366.82
  4971.6  367.32  4998.6  372.74  5026.5  372.44    5072  375.63  5093.1   370.8
  5113.5  370.47  5122.6  371.76  5127.7  369.75  5133.9  372.99  5154.3  374.72
  5164.5  374.28  5195.2  377.21    5338  378.58  5399.3  381.07  5502.6  382.06
#Mann= 4 ,-1 , 0
    4685     .07       0  4790.4     .12       0  4967.6     .05       0
  4971.6     .12       0
Bank Sta=4967.6,4971.6
XS Rating Curve= 0 ,0
Exp/Cntr=0.3,0.1

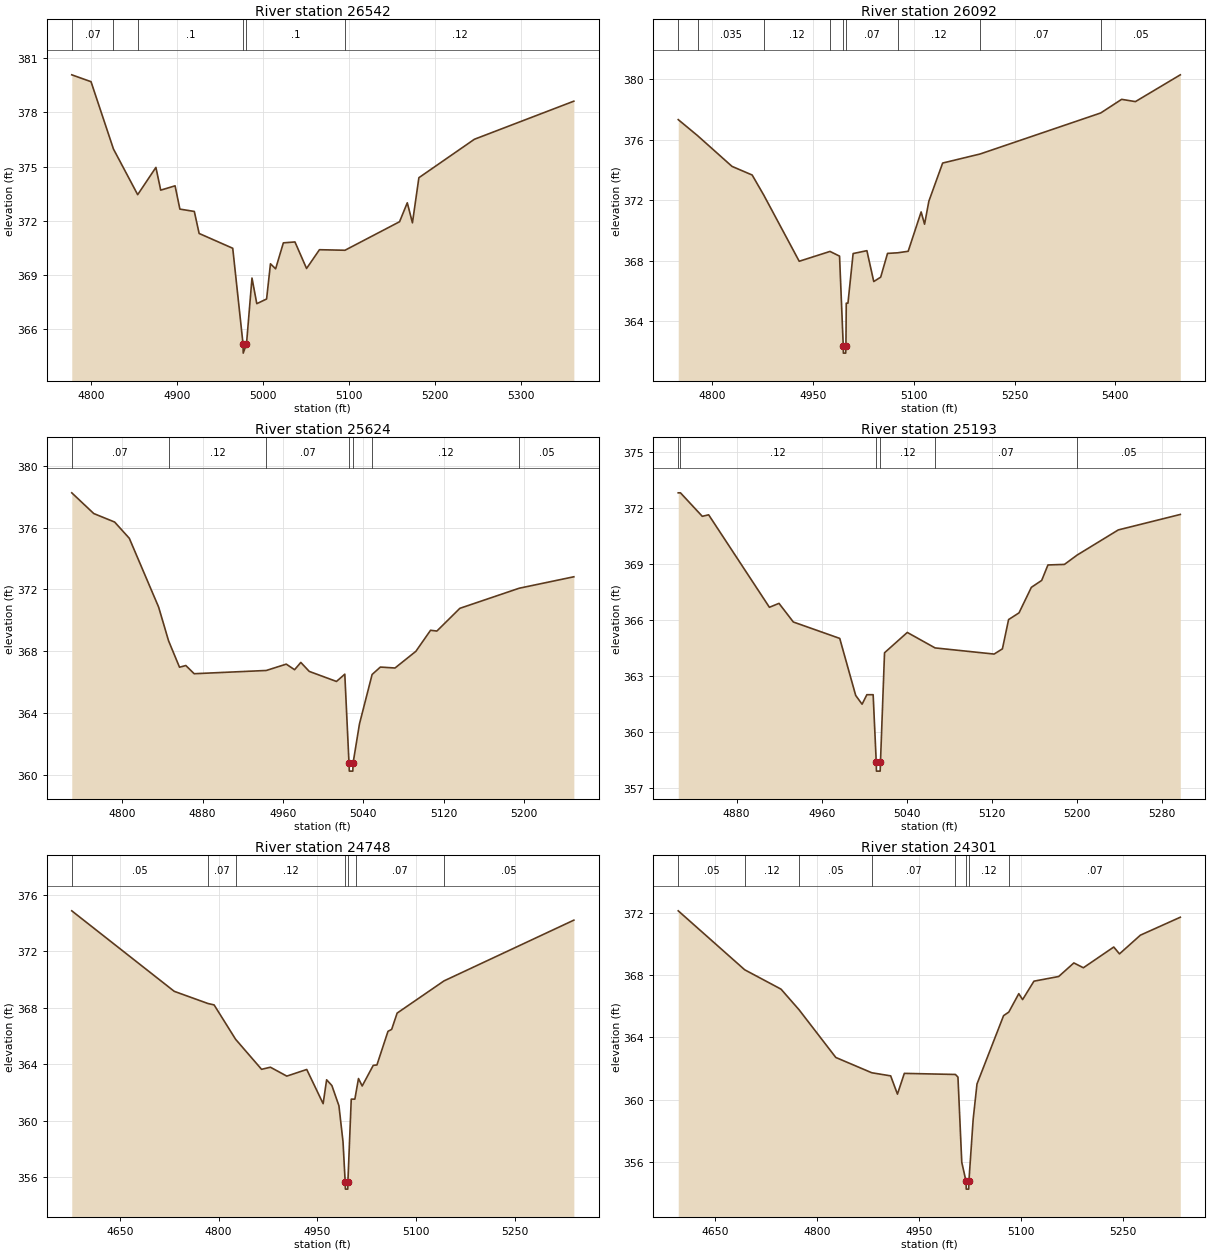
Type RM Length L Ch R = 1 ,26542   ,450,450,450
BEGIN DESCRIPTION:
EAST ELM CREEK 48.0
END DESCRIPTION:
XS GIS Cut Line= 3
      2492525.03     13800324.98        2492325.       13800425.
        2492125.       13800725.
#Sta/Elev= 30
  4777.2  380.08  4799.6   379.7  4825.7  375.97  4853.9  373.44  4875.1  374.95
  4880.7  373.69  4897.4  373.93    4903  372.64  4919.8  372.51  4925.4  371.29
  4964.5  370.47  4976.5  365.16  4976.7  364.66  4980.5  365.16  4986.9  368.82
  4992.5   367.4  5003.9  367.66  5008.4  369.61  5014.4  369.33  5023.4  370.77
  5036.9  370.82  5050.4  369.35  5065.4  370.39  5095.1  370.36  5158.6  371.94
  5167.6  372.99  5173.6  371.88  5181.1  374.38  5245.7  376.51  5361.4  378.62
#Mann= 6 ,-1 , 0
  4777.2     .07       0  4825.7     .12       0  4853.9      .1       0
  4976.5     .05       0  4980.5      .1       0  5095.1     .12       0
Bank Sta=4976.5,4980.5
XS Rating Curve= 0 ,0
Exp/Cntr=0.3,0.1

Type RM Length L Ch R = 1 ,26092   ,468,468,468
BEGIN DESCRIPTION:
EAST ELM CREEK 47.0
END DESCRIPTION:
XS GIS Cut Line= 3
      2492424.96       13800125.        2492175.       13800125.
      2491689.76     13800232.69
#Sta/Elev= 30
  4749.6  377.32  4778.4  376.26  4829.6  374.23  4859.6  373.66  4876.9  372.33
  4929.6  367.96  4975.4  368.61  4989.6   368.3  4995.1  362.39  4995.3  361.89
  4998.8  361.89  4999.1  362.39  4999.6  365.19  5002.1  365.19  5009.8  368.47
  5030.3  368.66  5040.5  366.62  5050.8  366.91    5061  368.48  5076.2  368.52
  5091.7  368.62    5111  371.22  5116.1  370.41  5122.5  371.93    5143  374.45
  5198.8  375.05  5378.2  377.76  5409.3  378.66  5429.8  378.51  5496.6  380.28
#Mann= 9 ,-1 , 0
  4749.6     .07       0  4778.4    .035       0  4876.9     .12       0
  4975.4     .07       0  4995.1     .05       0  4999.1     .07       0
  5076.2     .12       0  5198.8     .07       0  5378.2     .05       0
Bank Sta=4995.1,4999.1
XS Rating Curve= 0 ,0
Exp/Cntr=0.3,0.1

Type RM Length L Ch R = 1 ,25624   ,431,431,431
BEGIN DESCRIPTION:
EAST ELM CREEK 46.0
END DESCRIPTION:
XS GIS Cut Line= 3
      2492325.01     13799624.99        2492125.       13799775.
      2491975.01     13799974.99
#Sta/Elev= 30
  4749.7  378.25  4771.6  376.91  4792.4  376.36    4807  375.31  4836.2  370.86
  4846.1  368.68    4857  366.97  4863.3  367.08  4871.6  366.55  4943.4  366.76
  4963.3  367.17  4971.6  366.81  4977.8  367.28  4986.2   366.7  5013.3  366.05
  5021.6  366.52  5025.8  360.75  5026.1  360.25  5029.6  360.25  5029.8  360.75
  5036.2   363.3  5048.8   366.5    5057  366.98  5071.6  366.92  5092.4     368
    5107  369.36  5113.3  369.31  5136.2  370.78  5195.3  372.08  5249.7  372.82
#Mann= 7 ,-1 , 0
  4749.7     .07       0  4846.1     .12       0  4943.4     .07       0
  5025.8     .05       0  5029.8     .07       0  5048.8     .12       0
  5195.3     .05       0
Bank Sta=5025.8,5029.8
XS Rating Curve= 0 ,0
Exp/Cntr=0.3,0.1

Type RM Length L Ch R = 1 ,25193   ,445,445,445
BEGIN DESCRIPTION:
EAST ELM CREEK 45.0
END DESCRIPTION:
XS GIS Cut Line= 3
      2492125.03     13799324.98        2491975.       13799425.
      2491724.97     13799575.02
#Sta/Elev= 30
  4825.2  372.82  4827.3  372.82  4847.8  371.56  4853.8  371.64  4910.9  366.68
  4919.9  366.89  4933.4  365.89    4977  365.01    4992  361.95    4998  361.48
  5002.5  361.99  5008.4  361.99  5011.3  358.39  5011.5  357.89    5015  357.89
  5015.3  358.39  5019.1  364.24  5040.5  365.33  5066.6   364.5  5122.1  364.17
  5129.9  364.45  5135.7  366.02  5145.5  366.38  5157.1  367.75  5166.8  368.12
  5172.7  368.95  5188.2  368.98  5200.1  369.48  5238.8  370.83  5297.1  371.66
#Mann= 6 ,-1 , 0
  4825.2     .07       0  4827.3     .12       0  5011.3     .05       0
  5015.3     .12       0  5066.6     .07       0  5200.1     .05       0
Bank Sta=5011.3,5015.3
XS Rating Curve= 0 ,0
Exp/Cntr=0.3,0.1

Type RM Length L Ch R = 1 ,24748   ,447,447,447
BEGIN DESCRIPTION:
EAST ELM CREEK 44.0
END DESCRIPTION:
XS GIS Cut Line= 3
      2492124.96     13799075.01        2491725.       13799225.
      2491424.97     13799375.01
#Sta/Elev= 30
  4577.1  374.87  4732.8  369.17  4783.9  368.31  4793.3  368.21  4825.9  365.78
  4865.4  363.65  4878.8   363.8  4903.7  363.17    4934  363.64  4958.9  361.22
  4964.2  362.91  4972.2   362.5  4982.9  361.07  4989.1  358.52  4992.4  355.67
  4992.7  355.17  4996.3  355.17  4996.5  355.67  5001.6  361.54  5007.1  361.54
  5009.5  362.18  5012.6     363  5018.2  362.47    5035  363.93  5040.6  363.96
  5057.4  366.34    5063  366.48  5071.3  367.63  5142.5  369.91  5339.7  374.21
#Mann= 7 ,-1 , 0
  4577.1     .05       0  4783.9     .07       0  4825.9     .12       0
  4992.4     .05       0  4996.5     .12       0  5009.5     .07       0
  5142.5     .05       0
Bank Sta=4992.4,4996.5
XS Rating Curve= 0 ,0
Exp/Cntr=0.3,0.1

Type RM Length L Ch R = 1 ,24301   ,317,317,317
BEGIN DESCRIPTION:
EAST ELM CREEK 43.0
END DESCRIPTION:
XS GIS Cut Line= 3
      2492025.04     13798824.99        2491625.       13798875.
      2491324.97     13799025.02
#Sta/Elev= 30
  4596.3  372.11  4694.1  368.33  4747.5  367.09    4774  365.77  4828.1  362.71
    4881  361.73  4908.8  361.53  4918.8  360.36  4928.9  361.69  5004.1  361.62
  5007.8  361.45  5013.4  355.99  5019.7  354.77    5020  354.27  5023.6  354.27
  5023.9  354.77  5030.2  358.76  5035.8  361.01  5074.9  365.39  5082.6  365.62
  5097.3   366.8  5102.9  366.42  5119.6   367.6    5156   367.9  5178.3  368.77
  5192.3  368.46    5237  369.79  5245.4  369.35  5276.2  370.55  5334.9   371.7
#Mann= 8 ,-1 , 0
  4596.3     .05       0  4694.1     .12       0    4774     .05       0
    4881     .07       0  5004.1     .12       0  5019.7     .05       0
  5023.9     .12       0  5082.6     .07       0
Bank Sta=5019.7,5023.9
XS Rating Curve= 0 ,0
Exp/Cntr=0.3,0.1

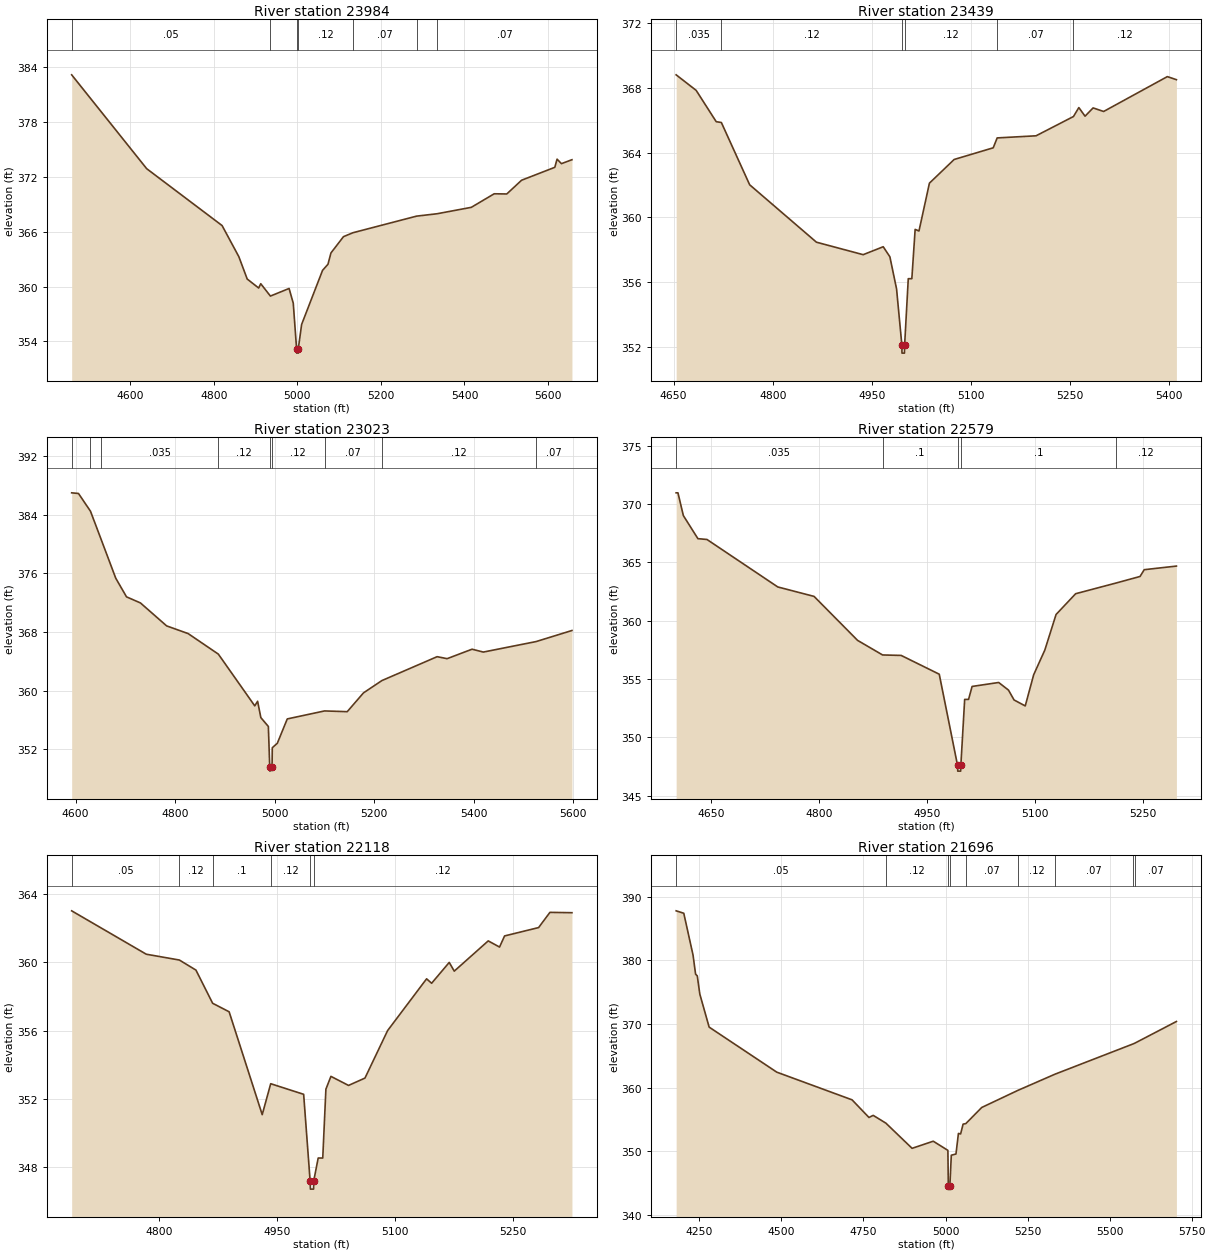
Type RM Length L Ch R = 1 ,23984   ,545,545,545
BEGIN DESCRIPTION:
X19083
END DESCRIPTION:
XS GIS Cut Line= 3
      2492224.16     13798582.09      2491531.64     13798625.14
      2491061.57     13798804.56
#Sta/Elev= 30
  4460.1  383.12  4639.6  372.87    4820  366.66    4860  363.27  4880.1  360.82
  4907.5  359.84  4912.5  360.31  4935.6  358.96  4980.3  359.79  4990.3  358.18
  4998.2  353.23  4998.5  352.73  5002.1  352.73  5002.4  353.23  5010.3  355.86
  5060.4  361.77  5073.3  362.43  5080.5  363.67  5110.5  365.45  5133.3  365.88
  5285.4  367.69  5334.5  367.95  5416.3  368.65  5471.1  370.13  5501.2  370.11
  5536.6  371.61  5616.1  373.02  5621.5  373.91    5632  373.42  5657.1  373.85
#Mann= 7 ,-1 , 0
  4460.1     .05       0  4935.6     .12       0  4998.2     .05       0
  5002.4     .12       0  5133.3     .07       0  5285.4     .12       0
  5334.5     .07       0
Bank Sta=4998.2,5002.4
XS Rating Curve= 0 ,0
Exp/Cntr=0.3,0.1

Type RM Length L Ch R = 1 ,23439   ,416,416,416
BEGIN DESCRIPTION:
EAST ELM CREEK 42.0
END DESCRIPTION:
XS GIS Cut Line= 3
      2491925.04     13798274.99        2491575.       13798325.
        2491225.       13798525.
#Sta/Elev= 30
  4653.9  368.79  4684.2  367.83  4714.5   365.9  4722.3  365.85  4765.1  362.01
  4866.1  358.47  4936.8   357.7  4967.1  358.19  4977.2  357.57  4987.3  355.59
  4995.3  352.13  4995.5  351.63  4999.2  351.63  4999.5  352.13    5005  356.22
  5010.4  356.22  5015.4  359.26  5021.2  359.16    5037  362.11  5074.4  363.57
  5133.5  364.29  5139.5   364.9  5198.3  365.03  5254.9  366.22    5263  366.77
  5272.4  366.24  5284.6  366.75  5300.5  366.53  5396.9  368.68  5410.6  368.49
#Mann= 6 ,-1 , 0
  4653.9    .035       0  4722.3     .12       0  4995.3     .05       0
  4999.5     .12       0  5139.5     .07       0  5254.9     .12       0
Bank Sta=4995.3,4999.5
XS Rating Curve= 0 ,0
Exp/Cntr=0.3,0.1

Type RM Length L Ch R = 1 ,23023   ,444,444,444
BEGIN DESCRIPTION:
EAST ELM CREEK 41.0
END DESCRIPTION:
XS GIS Cut Line= 3
      2492025.02     13797774.99        2491675.       13797975.
      2491075.02       13798025.
#Sta/Elev= 30
  4592.3  386.97    4606  386.88  4630.1  384.46  4650.8  380.74  4680.9  375.32
  4702.5  372.78  4730.5  371.95  4783.1  368.82  4826.3  367.77    4887  364.97
  4960.2  357.91  4965.9  358.54  4972.4  356.31  4987.5   355.1  4990.3  349.51
  4990.6  349.01  4994.9  349.51  4995.4   352.2  5005.5  352.81  5025.5  356.13
  5100.4  357.22    5146  357.12  5178.6  359.68  5215.6  361.36  5326.6  364.62
  5346.7  364.35  5396.8  365.64  5419.4  365.25  5525.4  366.68  5597.5  368.19
#Mann= 9 ,-1 , 0
  4592.3    .035       0  4630.1     .07       0  4650.8    .035       0
    4887     .12       0  4990.3     .05       0  4994.9     .12       0
  5100.4     .07       0  5215.6     .12       0  5525.4     .07       0
Bank Sta=4990.3,4994.9
XS Rating Curve= 0 ,0
Exp/Cntr=0.3,0.1

Type RM Length L Ch R = 1 ,22579   ,461,461,461
BEGIN DESCRIPTION:
EAST ELM CREEK 40.0
END DESCRIPTION:
XS GIS Cut Line= 3
      2491824.97       13797575.        2491425.       13797625.
      2491175.03     13797774.98
#Sta/Elev= 30
  4601.7  370.97  4604.2  370.97  4611.7  369.02  4631.9  367.04  4644.5  366.97
  4742.8   362.9  4793.2  362.09  4853.6  358.32  4888.3  357.07  4914.1  357.03
    4967  355.42  4992.4  347.61  4992.7  347.11  4996.7  347.11    4997  347.61
  5002.3  353.26  5007.7  353.26  5012.6  354.37  5049.5  354.71  5063.1  354.06
  5070.9  353.21  5086.4   352.7  5098.1  355.37  5113.6  357.49  5129.2  360.54
  5156.4  362.32  5212.7  363.24  5245.8   363.8  5251.6  364.38  5296.3  364.69
#Mann= 5 ,-1 , 0
  4601.7    .035       0  4888.3      .1       0  4992.4     .05       0
    4997      .1       0  5212.7     .12       0
Bank Sta=4992.4,4997
XS Rating Curve= 0 ,0
Exp/Cntr=0.3,0.1

Type RM Length L Ch R = 1 ,22118   ,422,422,422
BEGIN DESCRIPTION:
EAST ELM CREEK 39.0
END DESCRIPTION:
XS GIS Cut Line= 3
      2491624.99       13797125.        2491325.       13797225.
      2491074.98     13797425.01
#Sta/Elev= 30
  4688.4  363.01  4783.3  360.47  4825.4  360.13  4846.5  359.54  4867.7   357.6
  4888.7   357.1  4930.8  351.08  4941.6  352.89  4983.5  352.27  4991.7  347.22
  4992.1  346.72  4996.1  346.72  4996.4  347.22    5002  348.54  5007.8  348.54
  5011.8  352.57  5018.2  353.32  5040.6  352.79  5061.5  353.22  5090.3     356
  5139.9  359.03  5146.3  358.77  5168.7  359.99  5175.1  359.48  5218.3  361.25
  5232.7  360.89  5239.1  361.54  5282.4  362.03  5296.8  362.92  5324.8   362.9
#Mann= 6 ,-1 , 0
  4688.4     .05       0  4825.4     .12       0  4867.7      .1       0
  4941.6     .12       0  4991.7     .05       0  4996.4     .12       0
Bank Sta=4991.7,4996.4
XS Rating Curve= 0 ,0
Exp/Cntr=0.3,0.1

Type RM Length L Ch R = 1 ,21696   ,467,467,467
BEGIN DESCRIPTION:
EAST ELM CREEK 38.0
END DESCRIPTION:
XS GIS Cut Line= 3
      2491924.97     13797074.99        2491125.       13796875.
      2490605.83      13797344.1
#Sta/Elev= 30
  4179.3   387.8  4202.5  387.42  4230.8  380.84  4238.5  377.86  4243.7  377.57
  4251.4  374.72  4279.8  369.53  4485.9  362.45  4715.3   358.1  4766.8  355.33
  4779.7  355.66  4818.3  354.44  4898.2  350.48  4962.7   351.6  5007.3  350.16
  5008.6  344.57    5009  344.07  5013.3  344.57  5017.7   349.4  5031.9  349.59
  5039.4  352.82  5046.1  352.74  5053.6  354.28    5062  354.37  5110.4   356.9
  5220.3  359.58  5333.6  362.13  5572.7  366.91  5576.3  366.99  5703.6  370.41
#Mann= 9 ,-1 , 0
  4179.3     .05       0  4818.3     .12       0  5008.6     .05       0
  5013.3     .12       0    5062     .07       0  5220.3     .12       0
  5333.6     .07       0  5572.7     .12       0  5576.3     .07       0
Bank Sta=5008.6,5013.3
XS Rating Curve= 0 ,0
Exp/Cntr=0.3,0.1

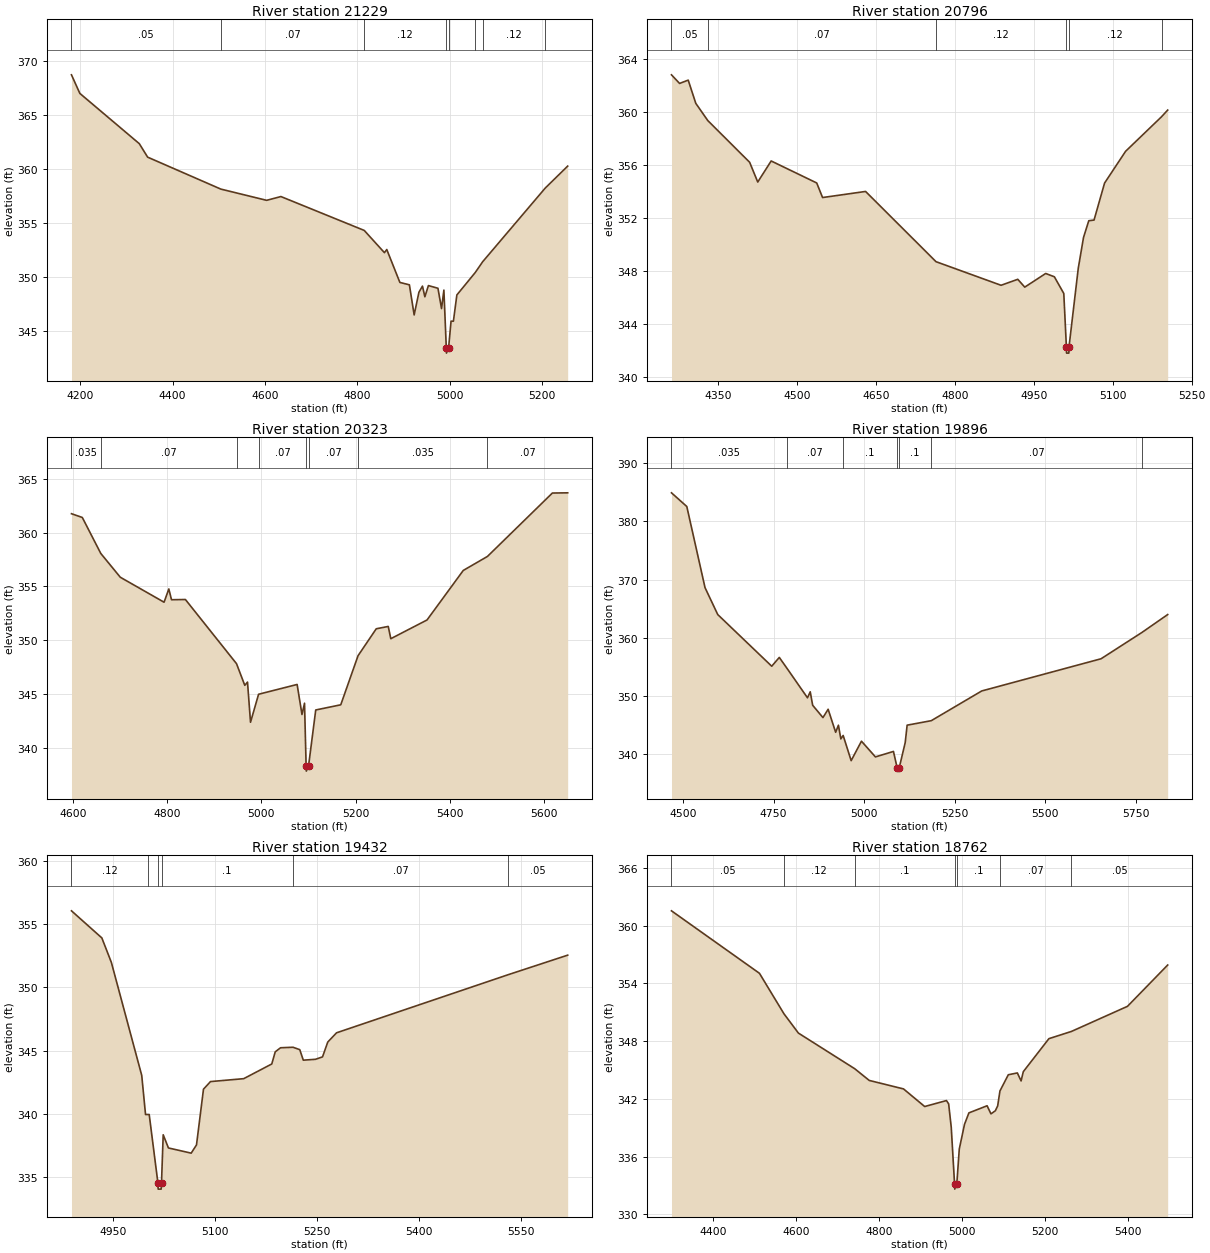
Type RM Length L Ch R = 1 ,21229   ,433,433,433
BEGIN DESCRIPTION:
EAST ELM CREEK 37.0
END DESCRIPTION:
XS GIS Cut Line= 3
      2491825.03     13796675.01        2491025.       13796475.
      2490774.96       13796475.
#Sta/Elev= 30
  4180.9  368.76    4199  367.04  4327.8  362.38  4345.9  361.13  4504.4  358.17
  4603.6  357.13  4634.5  357.48    4815  354.34  4858.7  352.28  4863.8  352.57
  4892.2  349.52  4912.8   349.3  4923.1  346.51  4933.4  348.61  4941.1  349.18
  4946.3  348.19    4954  349.23  4974.6  348.98  4982.4   347.1  4987.5  348.81
  4992.7  343.47  4993.1  342.97  4997.7  343.47    5003  345.93  5008.1  345.93
  5015.6  348.36  5055.6  350.45  5071.5  351.44  5207.1  358.27  5255.6   360.3
#Mann= 8 ,-1 , 0
  4180.9     .05       0  4504.4     .07       0    4815     .12       0
  4992.7     .05       0  4997.7     .12       0  5055.6     .07       0
  5071.5     .12       0  5207.1     .07       0
Bank Sta=4992.7,4997.7
XS Rating Curve= 0 ,0
Exp/Cntr=0.3,0.1

Type RM Length L Ch R = 1 ,20796   ,473,473,473
BEGIN DESCRIPTION:
EAST ELM CREEK 36.0
END DESCRIPTION:
XS GIS Cut Line= 3
      2491724.97     13796324.99        2491025.       13796075.
      2490824.98       13796075.
#Sta/Elev= 30
    4261   362.8  4276.4  362.15  4292.8   362.4  4307.2  360.65    4330  359.35
  4409.6   356.2    4425  354.71  4450.5   356.3  4537.1  354.64  4548.2  353.54
    4630     354  4763.9   348.7  4887.5  346.92  4919.3  347.37  4932.6  346.78
  4972.4  347.81  4988.9  347.56  5006.8   346.3  5011.7   342.3  5012.1   341.8
  5016.4   341.8  5016.8   342.3  5034.3   348.2  5044.3  350.53  5054.3  351.79
  5064.3  351.84  5084.3  354.63  5124.3  357.03  5192.7  359.64  5204.3  360.14
#Mann= 6 ,-1 , 0
    4261     .05       0    4330     .07       0  4763.9     .12       0
  5011.7     .05       0  5016.8     .12       0  5192.7     .07       0
Bank Sta=5011.7,5016.8
XS Rating Curve= 0 ,0
Exp/Cntr=0.3,0.1

Type RM Length L Ch R = 1 ,20323   ,427,427,427
BEGIN DESCRIPTION:
EAST ELM CREEK 35.0
END DESCRIPTION:
XS GIS Cut Line= 3
      2491774.96     13796174.98        2491425.       13795975.
      2490824.97     13795724.99
#Sta/Elev= 30
  4597.2  361.76  4620.2  361.41  4659.4  358.07  4700.8  355.86  4793.7  353.54
  4803.8  354.77  4809.5  353.77    4839  353.79  4947.5  347.83    4965  345.82
  4970.8  346.12  4977.2  342.39  4994.3  344.99  5076.1   345.9  5086.4  343.11
  5091.8  344.16  5095.2  338.35  5095.6  337.85  5100.4  338.35  5115.6  343.53
  5168.7  344.01  5205.4  348.57    5244  351.07  5269.5  351.29  5274.9  350.15
  5351.8  351.89  5428.7  356.49    5480  357.79  5617.8  363.68  5650.3   363.7
#Mann= 8 ,-1 , 0
  4597.2    .035       0  4659.4     .07       0  4947.5     .12       0
  4994.3     .07       0  5095.2     .05       0  5100.4     .07       0
  5205.4    .035       0    5480     .07       0
Bank Sta=5095.2,5100.4
XS Rating Curve= 0 ,0
Exp/Cntr=0.3,0.1

Type RM Length L Ch R = 1 ,19896   ,464,464,464
BEGIN DESCRIPTION:
EAST ELM CREEK 34.0
END DESCRIPTION:
XS GIS Cut Line= 3
      2492075.03     13796025.02        2491675.       13795675.
        2490875.       13795425.
#Sta/Elev= 30
  4468.4   384.9  4510.7  382.55    4561  368.62  4596.1     364  4745.1  355.13
    4766  356.64  4787.9  354.71  4843.8  349.71  4851.4  350.74  4858.1  348.43
  4886.5  346.31  4900.8  347.74  4921.6  343.79  4929.2     345  4935.9  342.65
  4942.3  343.24  4964.4  338.92  4992.8  342.26  5031.4  339.56  5081.1   340.5
  5091.6  337.62    5092  337.12  5096.8  337.62  5113.6  342.03  5118.9  345.01
  5185.5  345.78  5324.7  350.88  5654.2  356.41  5767.1  360.93  5838.1     364
#Mann= 7 ,-1 , 0
  4468.4    .035       0  4787.9     .07       0  4942.3      .1       0
  5091.6     .05       0  5096.8      .1       0  5185.5     .07       0
  5767.1     .12       0
Bank Sta=5091.6,5096.8
XS Rating Curve= 0 ,0
Exp/Cntr=0.3,0.1

Type RM Length L Ch R = 1 ,19432   ,670,670,670
BEGIN DESCRIPTION:
EAST ELM CREEK 33.0
END DESCRIPTION:
XS GIS Cut Line= 3
      2491925.01       13795375.        2491825.       13795325.
      2491224.98     13795475.01
#Sta/Elev= 30
  4888.3  356.03    4933  353.89    4947  351.96  4991.7  343.04  4997.3  339.95
  5000.2  339.95  5002.7  339.95  5015.5  334.56  5015.9  334.06  5020.3  334.06
  5020.8  334.56  5023.3  338.35    5031  337.31  5064.5   336.9  5072.3  337.55
  5082.6  341.95  5092.9  342.55  5141.8  342.78  5183.1  343.94  5188.2   344.9
    5196  345.22  5214.3  345.26  5224.3  345.07  5229.5  344.24  5247.5  344.31
  5257.8   344.5  5265.5  345.67  5278.4   346.4  5530.6  350.98  5618.6  352.53
#Mann= 6 ,-1 , 0
  4888.3     .12       0  5000.2      .1       0  5015.5     .05       0
  5020.8      .1       0  5214.3     .07       0  5530.6     .05       0
Bank Sta=5015.5,5020.8
XS Rating Curve= 0 ,0
Exp/Cntr=0.3,0.1

Type RM Length L Ch R = 1 ,18762   ,384,384,384
BEGIN DESCRIPTION:
EAST ELM CREEK 32.0
END DESCRIPTION:
XS GIS Cut Line= 3
      2492184.69     13795320.22       2491639.3     13795033.17
      2491093.82     13795226.96
#Sta/Elev= 30
  4300.2  361.54  4512.1  355.05  4571.2  350.84  4605.9  348.84  4741.5  345.14
  4776.6  343.92  4859.1  343.04  4910.1  341.21  4962.5  341.83  4967.8  341.49
  4974.1  339.04  4982.1  333.13  4982.5  332.63  4987.4  333.13  4993.4  336.79
    5006  339.36  5016.6  340.55  5060.4  341.29  5069.7  340.45  5080.3  340.77
  5085.9  341.28  5091.4  342.83  5111.5  344.51  5133.3   344.7  5142.3  343.87
  5147.6  344.83  5209.3  348.26  5263.5  349.01  5398.6  351.62  5495.4  355.91
#Mann= 7 ,-1 , 0
  4300.2     .05       0  4571.2     .12       0  4741.5      .1       0
  4982.1     .05       0  4987.4      .1       0  5091.4     .07       0
  5263.5     .05       0
Bank Sta=4982.1,4987.4
XS Rating Curve= 0 ,0
Exp/Cntr=0.3,0.1