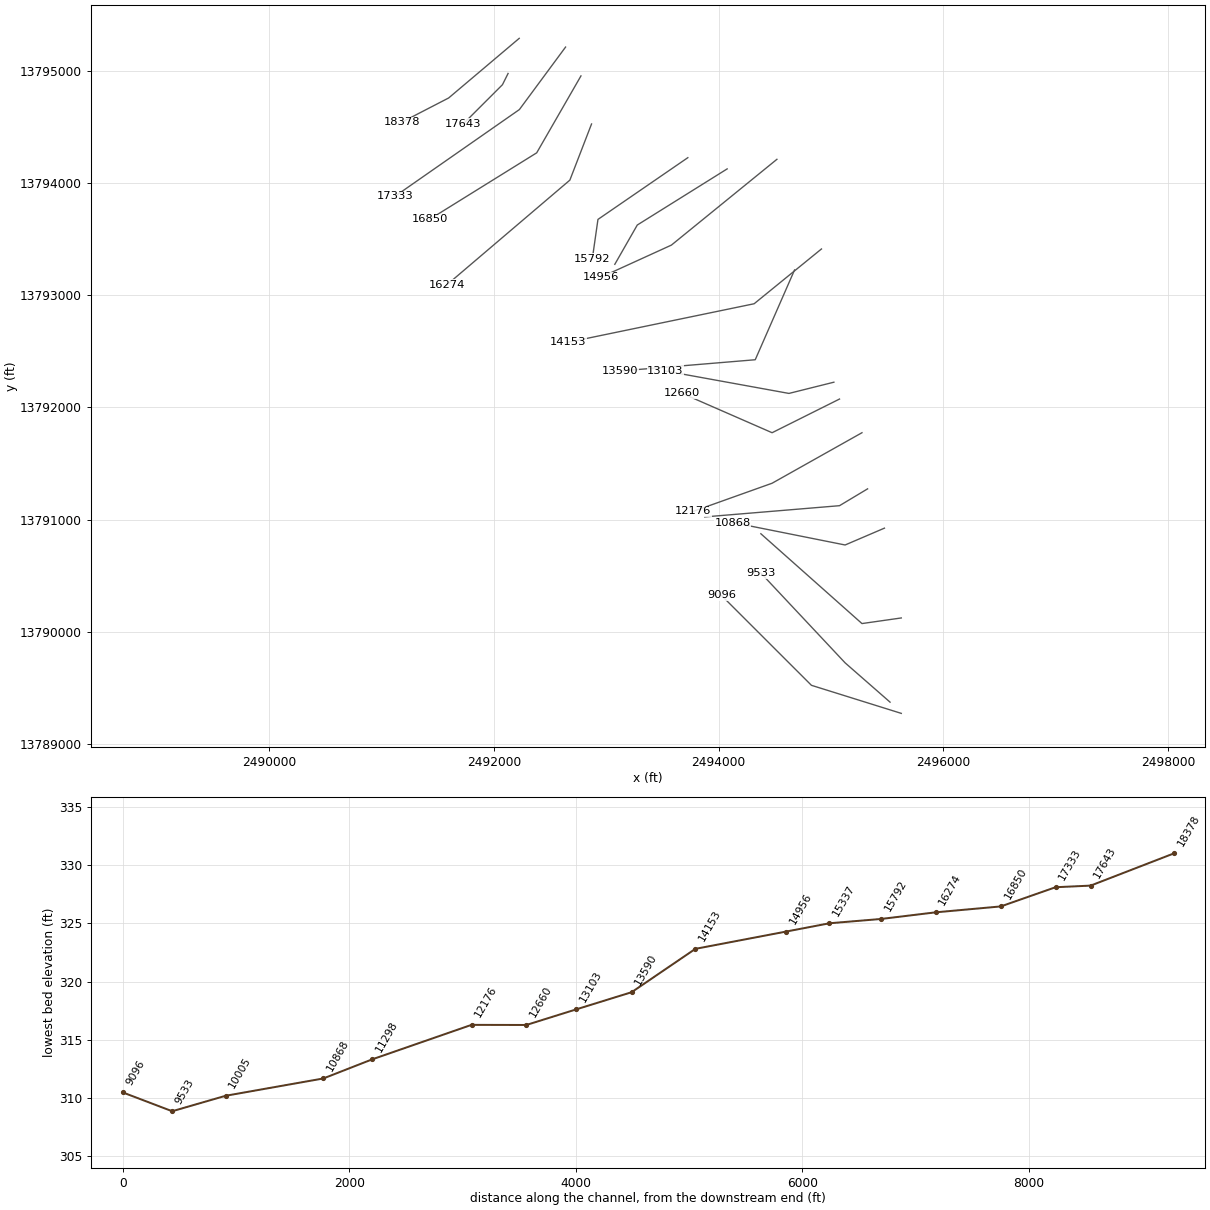
HEC-RAS study EAST ELM CREEK.prj: EAST ELM CREEK Base Level Engineering

--- EAST ELM CREEK.g01 (geometry) --- (continued)

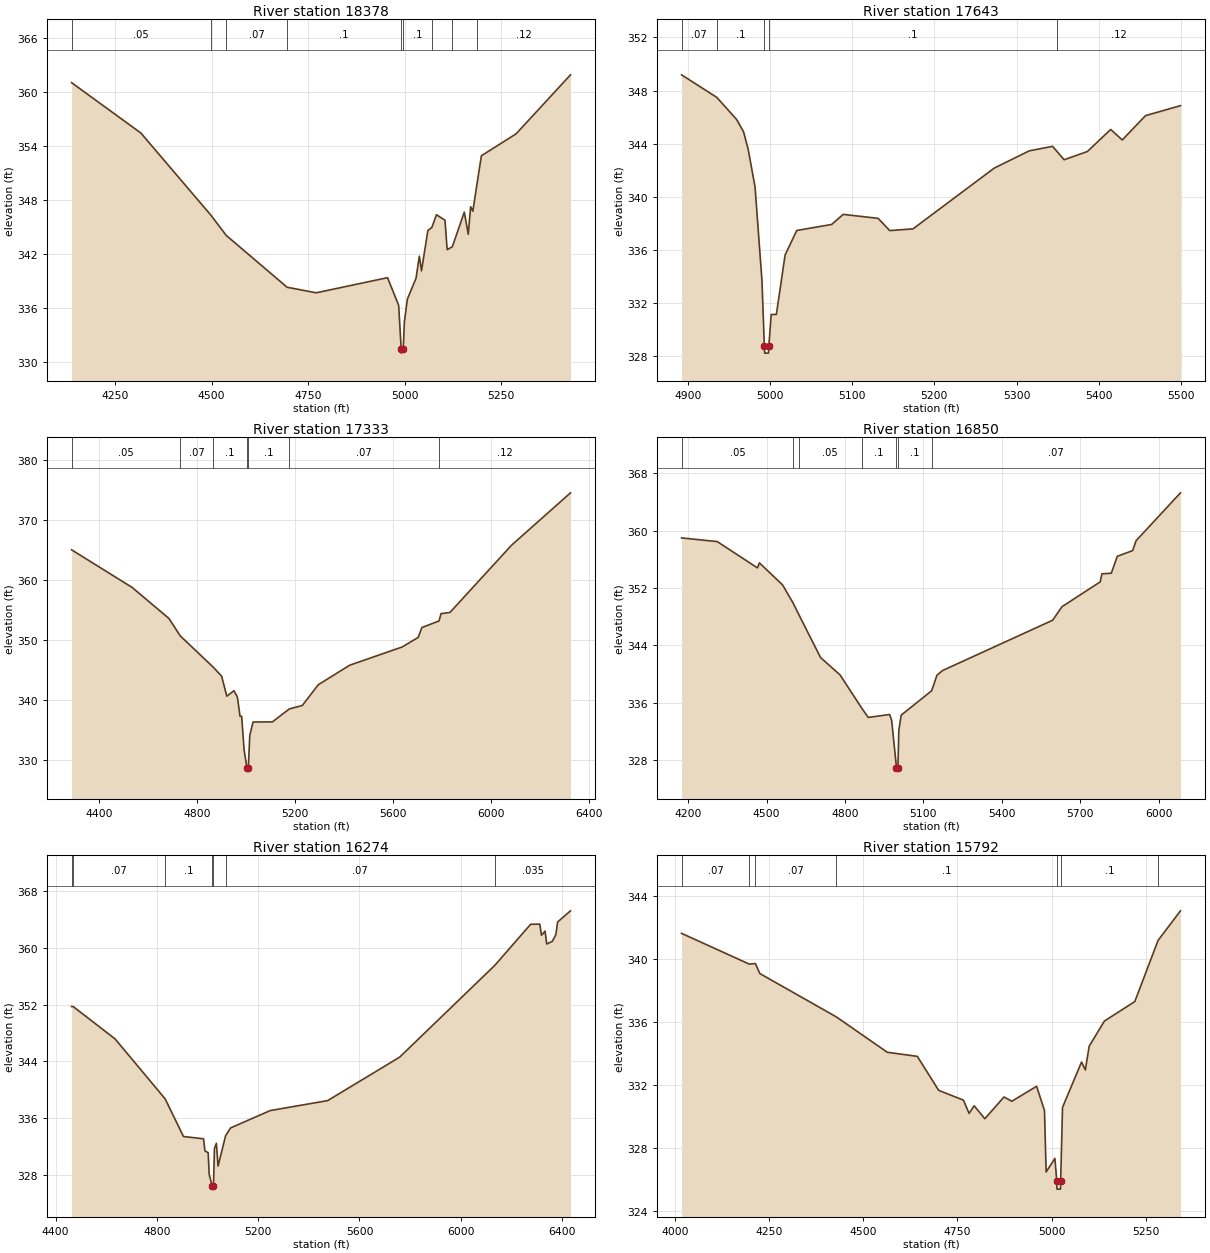
Type RM Length L Ch R = 1 ,18378   ,735,735,735
BEGIN DESCRIPTION:
EAST ELM CREEK 31.0
END DESCRIPTION:
XS GIS Cut Line= 3
      2492224.24     13795287.97      2491596.24     13794756.86
      2491179.99     13794541.57
#Sta/Elev= 30
  4137.9  361.06  4317.1  355.47  4498.6  346.33  4537.9   344.1  4695.5  338.34
  4770.9  337.72  4955.5   339.4  4984.3  336.33  4990.8  331.52  4991.2  331.02
  4996.2  331.52  4999.1   334.5  5006.8  337.01  5029.3  339.35  5037.8  341.79
  5043.4  340.16  5059.9  344.64  5070.2  344.98  5082.1  346.39  5104.2  345.78
  5109.8  342.51  5123.2  342.84  5154.1  346.68  5164.4  344.22  5170.6  347.28
  5176.3  346.78  5186.6   349.7  5198.4  352.94  5288.3  355.38    5429  361.93
#Mann= 9 ,-1 , 0
  4137.9     .05       0  4498.6     .12       0  4537.9     .07       0
  4695.5      .1       0  4990.8     .05       0  4996.2      .1       0
  5070.2     .12       0  5123.2     .07       0  5186.6     .12       0
Bank Sta=4990.8,4996.2
XS Rating Curve= 0 ,0
Exp/Cntr=0.3,0.1

Type RM Length L Ch R = 1 ,17643   ,310,310,310
BEGIN DESCRIPTION:
EAST ELM CREEK 30.0
END DESCRIPTION:
XS GIS Cut Line= 3
      2492124.99     13794974.98        2492075.       13794875.
      2491724.97     13794524.97
#Sta/Elev= 30
  4892.6  349.19  4935.5  347.49  4959.7  345.82    4968   344.9  4973.6  343.59
    4982  340.74  4990.4  333.68  4993.3  328.75  4993.7  328.25  4998.3  328.25
  4998.7  328.75  5001.6  331.16  5007.9  331.16  5018.5  335.63  5032.7  337.48
  5075.1  337.93  5089.2  338.69  5131.7  338.39  5145.8  337.47  5174.1   337.6
  5273.1  342.18  5315.5  343.47  5343.8  343.81  5349.7  343.39  5357.9   342.8
  5386.2  343.42  5414.5  345.08  5428.6  344.29  5456.9  346.12  5499.4  346.87
#Mann= 5 ,-1 , 0
  4892.6     .07       0  4935.5      .1       0  4993.3     .05       0
  4998.7      .1       0  5349.7     .12       0
Bank Sta=4993.3,4998.7
XS Rating Curve= 0 ,0
Exp/Cntr=0.3,0.1

Type RM Length L Ch R = 1 ,17333   ,483,483,483
BEGIN DESCRIPTION:
EAST ELM CREEK 29.0
END DESCRIPTION:
XS GIS Cut Line= 3
      2492636.69     13795210.12      2492225.67     13794653.53
      2491121.04     13793882.86
#Sta/Elev= 30
  4286.9  364.97  4534.7  358.69  4685.1  353.52  4730.7  350.64    4865  345.45
  4900.2  343.91    4921  340.59  4950.3   341.5  4964.5  340.44  4975.2  337.24
  4981.9  337.24  4991.8  331.65  5003.5  328.61    5004  328.11    5009  328.61
    5015  334.06  5028.4  336.29  5107.5  336.31  5176.2  338.46  5229.6  339.04
    5295   342.5  5423.3  345.75    5638  348.79  5703.3  350.38  5718.2  352.02
  5788.5  353.12  5796.6  354.34  5833.1  354.54  6084.6  365.73  6325.7  374.46
#Mann= 7 ,-1 , 0
  4286.9     .05       0  4730.7     .07       0    4865      .1       0
  5003.5     .05       0    5009      .1       0  5176.2     .07       0
  5788.5     .12       0
Bank Sta=5003.5,5009
XS Rating Curve= 0 ,0
Exp/Cntr=0.3,0.1

Type RM Length L Ch R = 1 ,16850   ,576,576,576
BEGIN DESCRIPTION:
EAST ELM CREEK 28.0
END DESCRIPTION:
XS GIS Cut Line= 3
      2492773.73     13794953.28      2492379.81     13794268.19
      2491429.69     13793677.57
#Sta/Elev= 30
  4174.8  358.99  4311.2  358.48  4465.1  354.81  4472.7  355.51  4561.4  352.43
  4601.5  349.92    4623  348.33  4706.5  342.31  4781.3  339.88  4864.6  335.22
  4889.1  333.95  4970.8  334.36  4978.6  333.57  4997.1  326.96  4997.5  326.46
  5002.6  326.96  5006.1  332.15  5015.2  334.27  5131.7  337.67  5152.1  339.84
  5173.4  340.49  5594.8  347.51  5630.3  349.39  5776.7  352.86  5783.2  353.98
  5819.2  354.07  5842.1  356.43  5900.9  357.22  5913.7  358.59  6083.8  365.28
#Mann= 7 ,-1 , 0
  4174.8     .05       0  4601.5     .07       0    4623     .05       0
  4864.6      .1       0  4997.1     .05       0  5002.6      .1       0
  5131.7     .07       0
Bank Sta=4997.1,5002.6
XS Rating Curve= 0 ,0
Exp/Cntr=0.3,0.1

Type RM Length L Ch R = 1 ,16274   ,482,482,482
BEGIN DESCRIPTION:
EAST ELM CREEK 27.0
END DESCRIPTION:
XS GIS Cut Line= 3
      2492867.91      13794525.1        2492675.       13794025.
      2491583.44     13793095.04
#Sta/Elev= 30
  4463.4  351.74  4469.1  351.75    4635  347.17  4832.8   338.7  4905.2  333.38
  4984.4  333.06  4989.8  331.36  5002.7  331.09  5006.6  328.04  5018.1  326.45
  5018.5  325.95  5023.6  326.45  5027.4   331.7  5035.1  332.42  5041.7   329.2
  5071.5   333.5  5091.4   334.6  5248.1  337.05  5474.3  338.45  5758.7  344.59
  6134.3  357.55  6275.9  363.36  6312.2  363.38  6318.8   361.8    6333  362.39
  6339.6  360.57  6361.6  360.95  6375.9  361.93  6382.4  363.68  6433.4  365.26
#Mann= 7 ,-1 , 0
  4463.4     .05       0  4469.1     .07       0  4832.8      .1       0
  5018.1     .05       0  5023.6      .1       0  5071.5     .07       0
  6134.3    .035       0
Bank Sta=5018.1,5023.6
XS Rating Curve= 0 ,0
Exp/Cntr=0.3,0.1

Type RM Length L Ch R = 1 ,15792   ,455,455,455
BEGIN DESCRIPTION:
EAST ELM CREEK 26.0
END DESCRIPTION:
XS GIS Cut Line= 3
      2493725.03     13794225.02        2492925.       13793675.
        2492875.     13793325.02
#Sta/Elev= 30
  4017.6  341.62  4197.1  339.67  4213.6   339.7  4225.3  339.07  4428.8  336.31
  4563.7  334.07  4643.4  333.81  4700.2  331.65  4765.9  331.03  4780.8  330.19
  4794.3  330.67  4822.7  329.85  4873.5  331.23  4894.4  330.96  4960.1  331.91
    4981  330.37  4985.4  326.47  5008.7  327.33  5013.7  325.88  5014.2  325.38
  5023.4  325.38  5023.9  325.88  5028.9  330.57  5079.4  333.45  5089.5  332.95
  5099.6  334.45    5140  336.05  5220.8  337.29  5282.5  341.17    5342  343.05
#Mann= 7 ,-1 , 0
  4017.6     .07       0  4197.1     .05       0  4213.6     .07       0
  4428.8      .1       0  5013.7     .05       0  5023.9      .1       0
  5282.5    .035       0
Bank Sta=5013.7,5023.9
XS Rating Curve= 0 ,0
Exp/Cntr=0.3,0.1

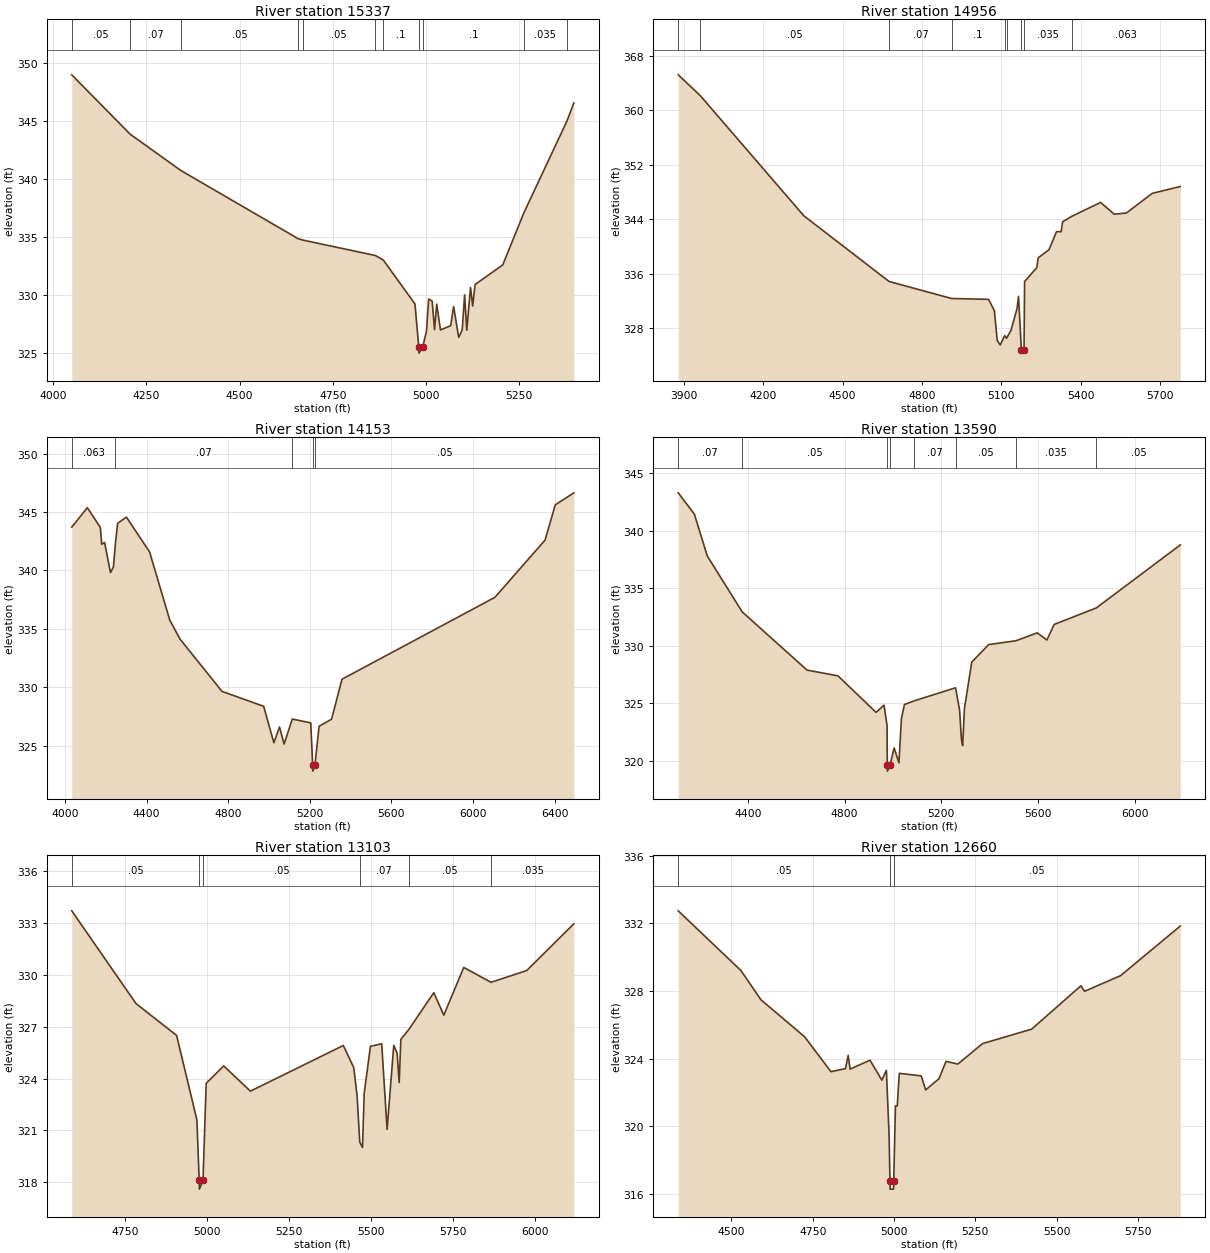
Type RM Length L Ch R = 1 ,15337   ,381,381,381
BEGIN DESCRIPTION:
EAST ELM CREEK 25.0
END DESCRIPTION:
XS GIS Cut Line= 3
      2494075.03     13794125.02        2493275.       13793625.
      2493075.02     13793275.04
#Sta/Elev= 30
    4050  348.99  4206.4  343.88  4342.9  340.74  4657.2  334.87    4670  334.75
  4864.5  333.42  4885.5  333.03  4970.4  329.25  4980.7  325.51  4981.2  325.01
  4990.9  325.51  5001.3  326.89  5007.1  329.67  5016.5   329.5  5022.9  327.04
  5028.7  329.23  5038.8  327.01  5066.1  327.37  5074.1  329.02  5087.7  326.37
  5097.1  327.01  5103.6  330.03  5109.3  326.98  5119.4  330.67  5125.2  329.07
  5131.6  330.92  5205.8  332.61  5262.7  337.11  5377.9     345  5396.5  346.57
#Mann= 11 ,-1 , 0
    4050     .05       0  4206.4     .07       0  4342.9     .05       0
  4657.2     .07       0    4670     .05       0  4864.5     .07       0
  4885.5      .1       0  4980.7     .05       0  4990.9      .1       0
  5262.7    .035       0  5377.9    .063       0
Bank Sta=4980.7,4990.9
XS Rating Curve= 0 ,0
Exp/Cntr=0.3,0.1

Type RM Length L Ch R = 1 ,14956   ,803,803,803
BEGIN DESCRIPTION:
EAST ELM CREEK 24.0
END DESCRIPTION:
XS GIS Cut Line= 3
      2494517.92     13794210.42      2493578.66     13793446.12
      2492952.24     13793160.25
#Sta/Elev= 30
    3878  365.22  3961.2  362.17    4353   344.5  4675.5  334.84  4912.3  332.33
  5052.1  332.21    5074  330.55    5085  326.14  5096.3  325.51  5113.3  326.87
  5120.1  326.49  5136.9  327.65  5159.9  330.86  5165.4  332.65  5176.1   324.8
  5176.6   324.3  5186.3   324.8  5188.4  334.83  5234.5  336.87    5240  338.32
  5280.6   339.5  5309.1  342.16  5326.7  342.15  5332.2  343.61    5366   344.4
  5475.9  346.46  5527.4  344.73  5573.5   344.9  5671.1  347.79  5777.5   348.8
#Mann= 9 ,-1 , 0
    3878     .07       0  3961.2     .05       0  4675.5     .07       0
  4912.3      .1       0  5113.3    .063       0  5120.1    .035       0
  5176.1     .05       0  5186.3    .035       0    5366    .063       0
Bank Sta=5176.1,5186.3
XS Rating Curve= 0 ,0
Exp/Cntr=0.3,0.1

Type RM Length L Ch R = 1 ,14153   ,563,563,563
BEGIN DESCRIPTION:
EAST ELM CREEK 23.0
END DESCRIPTION:
XS GIS Cut Line= 3
      2494914.53     13793411.88      2494315.09     13792923.77
      2492662.35     13792581.23
#Sta/Elev= 30
  4033.7   343.7  4109.9  345.37  4173.9  343.68  4180.3  342.24  4194.7  342.39
  4223.4  339.81  4237.8  340.28  4247.7  342.31  4258.6  344.03  4301.7  344.56
  4415.1  341.58  4514.2  335.74  4563.8  334.13  4769.9  329.64  4974.2  328.36
  5024.4  325.24  5051.9  326.59  5074.6  325.13  5114.5  327.27  5205.1  326.94
  5214.4  323.31  5214.9  322.81  5225.5  323.31    5246  326.65  5307.2  327.26
  5358.3  330.68  6107.7  337.69  6353.4  342.59  6403.6  345.61  6494.6  346.64
#Mann= 5 ,-1 , 0
  4033.7    .063       0  4247.7     .07       0  5114.5     .05       0
  5214.4     .05       0  5225.5     .05       0
Bank Sta=5214.4,5225.5
XS Rating Curve= 0 ,0
Exp/Cntr=0.3,0.1

Type RM Length L Ch R = 1 ,13590   ,487,487,487
BEGIN DESCRIPTION:
EAST ELM CREEK 22.0
END DESCRIPTION:
XS GIS Cut Line= 3
        2494675.       13793225.        2494325.       13792425.
      2493124.97       13792325.
#Sta/Elev= 30
  4111.3  343.29    4178  341.44  4231.4   337.8  4376.1  332.93  4644.2  327.87
  4772.1  327.37  4929.9  324.19  4962.7  324.82  4975.5  323.03  4976.1  319.58
  4976.6  319.08  4987.5  319.58  5004.6   321.1  5024.6   319.8  5034.7  323.64
  5047.2  324.87  5086.9  325.19  5258.8  326.33  5275.5  324.37    5283  321.84
  5288.1  321.31  5295.6  324.53  5325.7  328.56  5395.9  330.09  5508.8  330.42
  5596.6  331.11  5636.8  330.49  5666.9  331.84  5841.5  333.28  6188.7  338.76
#Mann= 8 ,-1 , 0
  4111.3     .07       0  4376.1     .05       0  4976.1     .05       0
  4987.5     .05       0  5086.9     .07       0  5258.8     .05       0
  5508.8    .035       0  5841.5     .05       0
Bank Sta=4976.1,4987.5
XS Rating Curve= 0 ,0
Exp/Cntr=0.3,0.1

Type RM Length L Ch R = 1 ,13103   ,443,443,443
BEGIN DESCRIPTION:
EAST ELM CREEK 21.0
END DESCRIPTION:
XS GIS Cut Line= 3
      2495025.01       13792225.        2494625.       13792125.
      2493524.96     13792325.01
#Sta/Elev= 30
    4588  333.69  4783.9  328.33  4907.6  326.49  4969.4  321.61  4976.5  318.11
    4977  317.61    4988  318.11  4997.7  323.72  5051.1  324.73  5132.5  323.27
  5415.8  325.91  5447.5  324.63  5457.7  323.02  5465.9  320.32  5474.2  320.02
  5479.3  323.13  5498.4  325.86  5532.7  326.01  5549.2  321.06  5569.5  325.92
  5579.7  325.47    5586  323.77  5591.1  326.26  5615.2  326.83  5691.5  328.96
    5722  327.66  5782.9  330.42  5866.1  329.56  5974.8  330.24  6118.4  332.94
#Mann= 6 ,-1 , 0
    4588     .05       0  4976.5     .05       0    4988     .05       0
  5465.9     .07       0  5615.2     .05       0  5866.1    .035       0
Bank Sta=4976.5,4988
XS Rating Curve= 0 ,0
Exp/Cntr=0.3,0.1

Type RM Length L Ch R = 1 ,12660   ,484,484,484
BEGIN DESCRIPTION:
EAST ELM CREEK 20.0
END DESCRIPTION:
XS GIS Cut Line= 3
      2495075.01       13792075.        2494475.       13791775.
      2493675.04     13792124.98
#Sta/Elev= 30
  4336.3  332.75  4529.2  329.21  4590.7  327.48  4724.8  325.29  4805.9  323.22
  4850.6   323.4    4859  324.19  4864.6  323.37  4926.1   323.9  4962.4  322.72
  4976.4   323.3  4984.8  319.44  4987.4  316.76  4987.9  316.26  4998.5  316.26
    4999  316.76  5004.3  321.19  5009.9  321.19  5016.1  323.12  5083.5  322.97
  5097.2  322.14  5138.1   322.8  5159.9  323.83  5196.2  323.67  5271.8  324.88
  5423.1  325.74  5574.7  328.31  5585.6  327.98  5696.7  328.91  5880.3  331.85
#Mann= 3 ,-1 , 0
  4336.3     .05       0  4987.4     .05       0    4999     .05       0
Bank Sta=4987.4,4999
XS Rating Curve= 0 ,0
Exp/Cntr=0.3,0.1

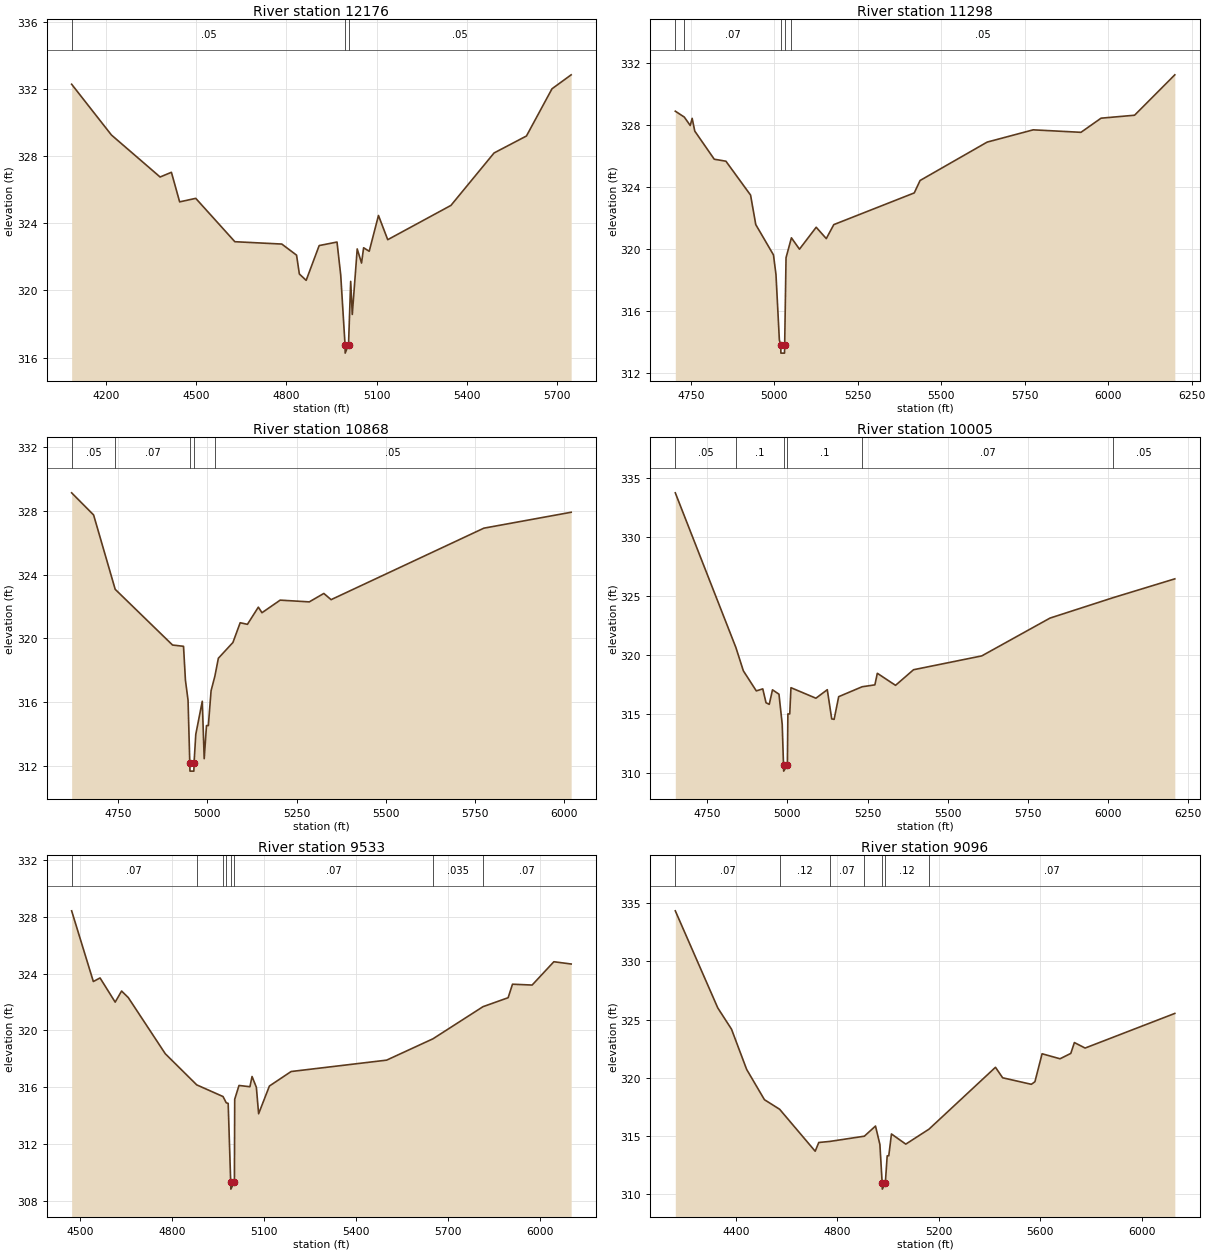
Type RM Length L Ch R = 1 ,12176   ,878,878,878
BEGIN DESCRIPTION:
EAST ELM CREEK 19.0
END DESCRIPTION:
XS GIS Cut Line= 3
      2495275.01       13791775.        2494475.       13791325.
      2493774.99       13791075.
#Sta/Elev= 30
    4086  332.27  4218.3  329.25  4380.2  326.75  4417.8  327.03  4445.2  325.27
  4498.7  325.48  4628.8   322.9  4784.9  322.76    4834   322.1  4843.3  320.98
  4865.9   320.6  4909.2  322.67  4968.5  322.88  4980.9  320.91  4995.2  316.77
  4995.7  316.27  5006.8  316.77    5014  320.54  5019.3  318.57  5035.7  322.47
  5050.1  321.63    5057  322.54  5075.6  322.33  5106.4  324.46  5137.2  323.02
  5347.4  325.06  5490.8  328.18  5598.5  329.19  5683.5     332  5747.2  332.83
#Mann= 3 ,-1 , 0
    4086     .05       0  4995.2     .05       0  5006.8     .05       0
Bank Sta=4995.2,5006.8
XS Rating Curve= 0 ,0
Exp/Cntr=0.3,0.1

Type RM Length L Ch R = 1 ,11298   ,430,430,430
BEGIN DESCRIPTION:
EAST ELM CREEK 18.0
END DESCRIPTION:
XS GIS Cut Line= 3
      2495324.96     13791274.98        2495075.       13791125.
      2493874.96       13791025.
#Sta/Elev= 30
  4703.7  328.87  4730.7  328.49  4748.4  327.95  4754.2  328.41    4762  327.59
  4820.3  325.78  4855.3  325.65  4929.1  323.47  4944.7  321.57  4997.7  319.62
  5005.2  318.35  5015.3  314.15  5019.4   313.8  5019.9   313.3  5030.7   313.3
  5031.2   313.8  5035.3  319.44  5051.4  320.72  5075.5  319.99  5125.6   321.4
  5155.8  320.67  5178.3  321.57  5419.2  323.61  5436.7  324.41  5637.4  326.88
  5775.4  327.67  5918.4  327.51  5978.6  328.42  6078.9  328.61  6199.4  331.21
#Mann= 5 ,-1 , 0
  4703.7     .05       0  4730.7     .07       0  5019.4     .05       0
  5031.2     .07       0  5051.4     .05       0
Bank Sta=5019.4,5031.2
XS Rating Curve= 0 ,0
Exp/Cntr=0.3,0.1

Type RM Length L Ch R = 1 ,10868   ,863,863,863
BEGIN DESCRIPTION:
EAST ELM CREEK 17.0
END DESCRIPTION:
XS GIS Cut Line= 3
      2495474.98     13790924.99        2495125.       13790775.
      2494124.98       13790975.
#Sta/Elev= 30
  4619.5  329.14  4681.1  327.75  4741.6  323.08  4902.4  319.58  4933.2   319.5
  4938.6  317.36  4945.9  316.11  4950.8  312.16  4951.3  311.66  4962.2  311.66
  4962.7  312.16  4967.6  313.97  4985.8  316.05  4991.2  312.44  4997.6  314.52
  5002.8  314.52  5010.5  316.71  5021.3  317.64  5030.9  318.75  5071.7  319.74
  5092.1  320.98  5112.4  320.88    5143  321.96  5153.2  321.61  5204.2   322.4
  5285.8  322.29  5326.6  322.82    5347  322.43  5775.3  326.92  6020.1  327.92
#Mann= 5 ,-1 , 0
  4619.5     .05       0  4741.6     .07       0  4950.8     .05       0
  4962.7     .07       0  5021.3     .05       0
Bank Sta=4950.8,4962.7
XS Rating Curve= 0 ,0
Exp/Cntr=0.3,0.1

Type RM Length L Ch R = 1 ,10005   ,472,472,472
BEGIN DESCRIPTION:
EAST ELM CREEK 16.0
END DESCRIPTION:
XS GIS Cut Line= 3
      2495625.04     13790125.01        2495275.       13790075.
      2494375.04     13790874.97
#Sta/Elev= 30
  4650.4  333.72  4839.5  320.62  4862.6  318.66    4903  316.96  4923.2  317.13
  4933.3  315.96  4943.4  315.82  4953.5  317.05  4973.7  316.68  4983.8  314.14
  4987.9  310.67  4988.4  310.17  4999.9  310.67  5001.5  315.01  5007.3  315.01
  5011.1  317.23  5088.9  316.34  5124.4  317.06  5138.2  314.59  5145.7  314.55
  5159.9  316.47  5233.1  317.31  5272.8  317.47  5280.4  318.45  5337.2  317.43
  5393.3  318.75  5606.1  319.92  5818.9  323.12    6016  324.85  6208.1  326.44
#Mann= 6 ,-1 , 0
  4650.4     .05       0  4839.5      .1       0  4987.9     .05       0
  4999.9      .1       0  5233.1     .07       0    6016     .05       0
Bank Sta=4987.9,4999.9
XS Rating Curve= 0 ,0
Exp/Cntr=0.3,0.1

Type RM Length L Ch R = 1 ,9533    ,437,437,437
BEGIN DESCRIPTION:
EAST ELM CREEK 15.0
END DESCRIPTION:
XS GIS Cut Line= 3
      2495525.02     13789374.98        2495125.       13789725.
      2494375.01     13790524.99
#Sta/Elev= 30
    4473  328.41  4543.7  323.44  4565.6  323.69  4614.9  321.99  4635.8  322.77
  4657.6  322.31  4778.2  318.36  4880.8  316.17  4966.5  315.35  4976.9  314.91
  4983.2  314.87  4991.4  309.34  4991.9  308.84  5003.5  309.34  5004.5  315.16
  5018.5  316.13  5054.1  316.04    5061  316.76  5075.1     316  5082.4  314.14
  5117.6  316.09  5188.4  317.11  5499.6  317.91  5650.6  319.41  5813.8  321.67
  5895.7   322.3  5909.9  323.25  5973.9  323.19  6044.7  324.83  6101.1  324.67
#Mann= 8 ,-1 , 0
    4473     .07       0  4880.8      .1       0  4966.5     .12       0
  4976.9     .07       0  4991.4     .05       0  5003.5     .07       0
  5650.6    .035       0  5813.8     .07       0
Bank Sta=4991.4,5003.5
XS Rating Curve= 0 ,0
Exp/Cntr=0.3,0.1

Type RM Length L Ch R = 1 ,9096    ,425,425,425
BEGIN DESCRIPTION:
EAST ELM CREEK 14.0
END DESCRIPTION:
XS GIS Cut Line= 3
      2495624.97     13789275.01        2494825.       13789525.
      2494024.99     13790325.01
#Sta/Elev= 30
  4161.6  334.33  4329.2     326  4383.2  324.18  4442.9  320.73  4513.1  318.13
    4573  317.31  4713.2  313.71  4727.3  314.46  4770.6  314.55    4907     315
    4951  315.87  4968.3  314.29  4977.3  310.96  4977.8  310.46  4989.6  310.96
  4997.1  313.32  5003.3  313.32  5013.9  315.19  5070.4  314.32  5161.7   315.6
    5424  320.91  5452.3  320.01  5565.4  319.45  5579.5  319.67  5607.8  322.07
  5678.5  321.64    5721   322.1  5735.1  323.03  5777.5  322.56  6131.1  325.53
#Mann= 7 ,-1 , 0
  4161.6     .07       0    4573     .12       0  4770.6     .07       0
    4907     .12       0  4977.3     .05       0  4989.6     .12       0
  5161.7     .07       0
Bank Sta=4977.3,4989.6
XS Rating Curve= 0 ,0
Exp/Cntr=0.3,0.1