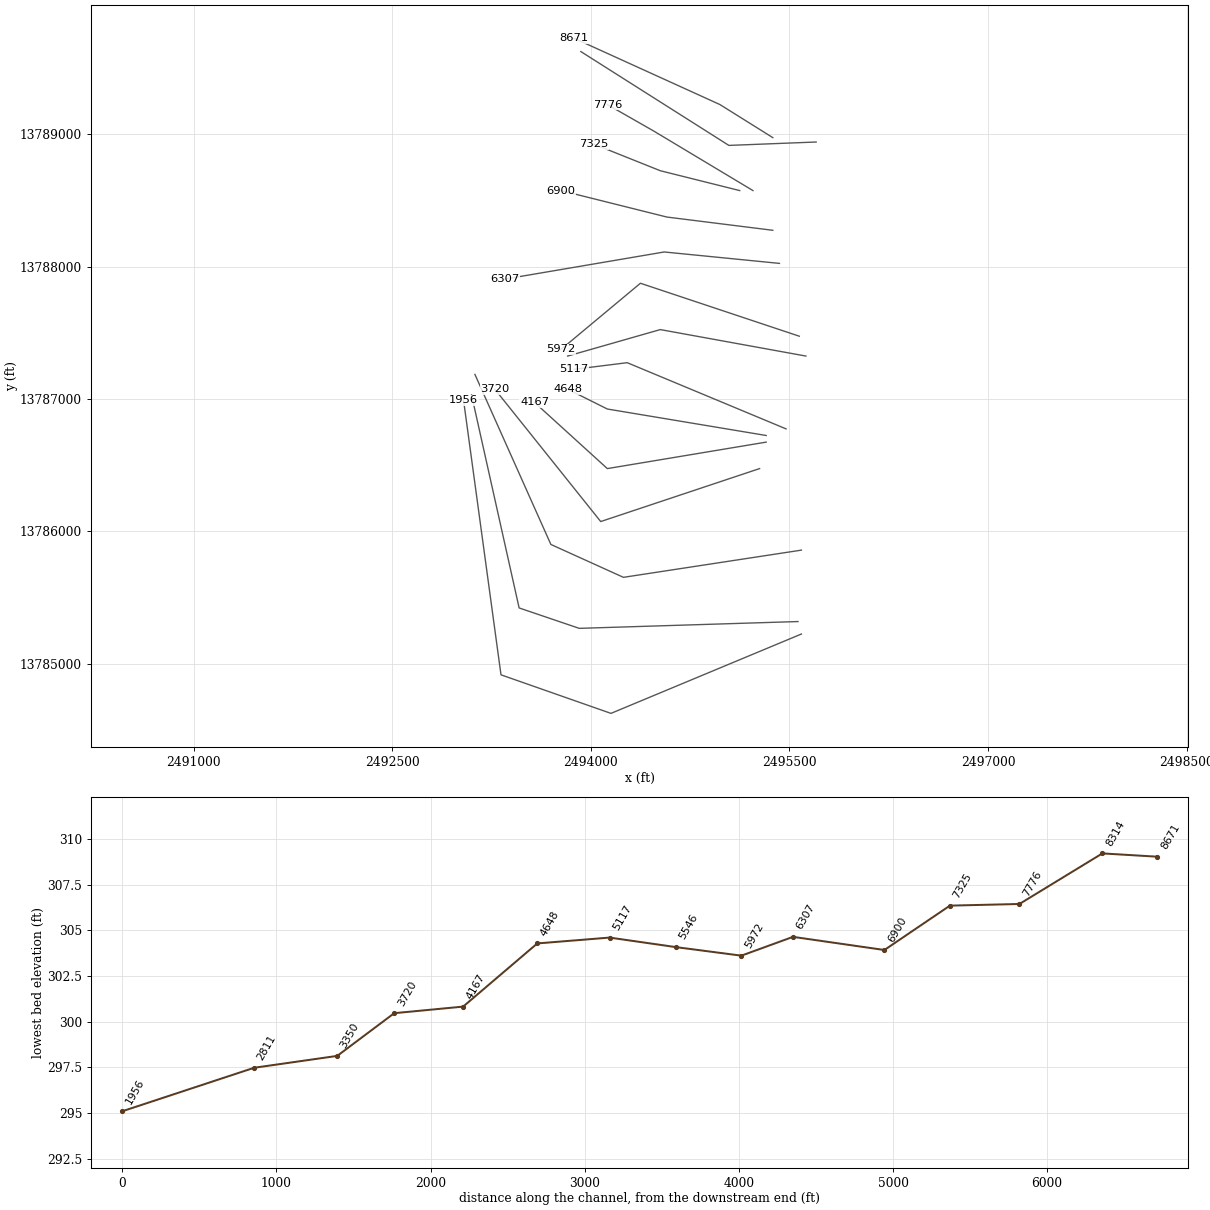
HEC-RAS study EAST ELM CREEK.prj: EAST ELM CREEK Base Level Engineering

--- EAST ELM CREEK.g01 (geometry) --- (continued)

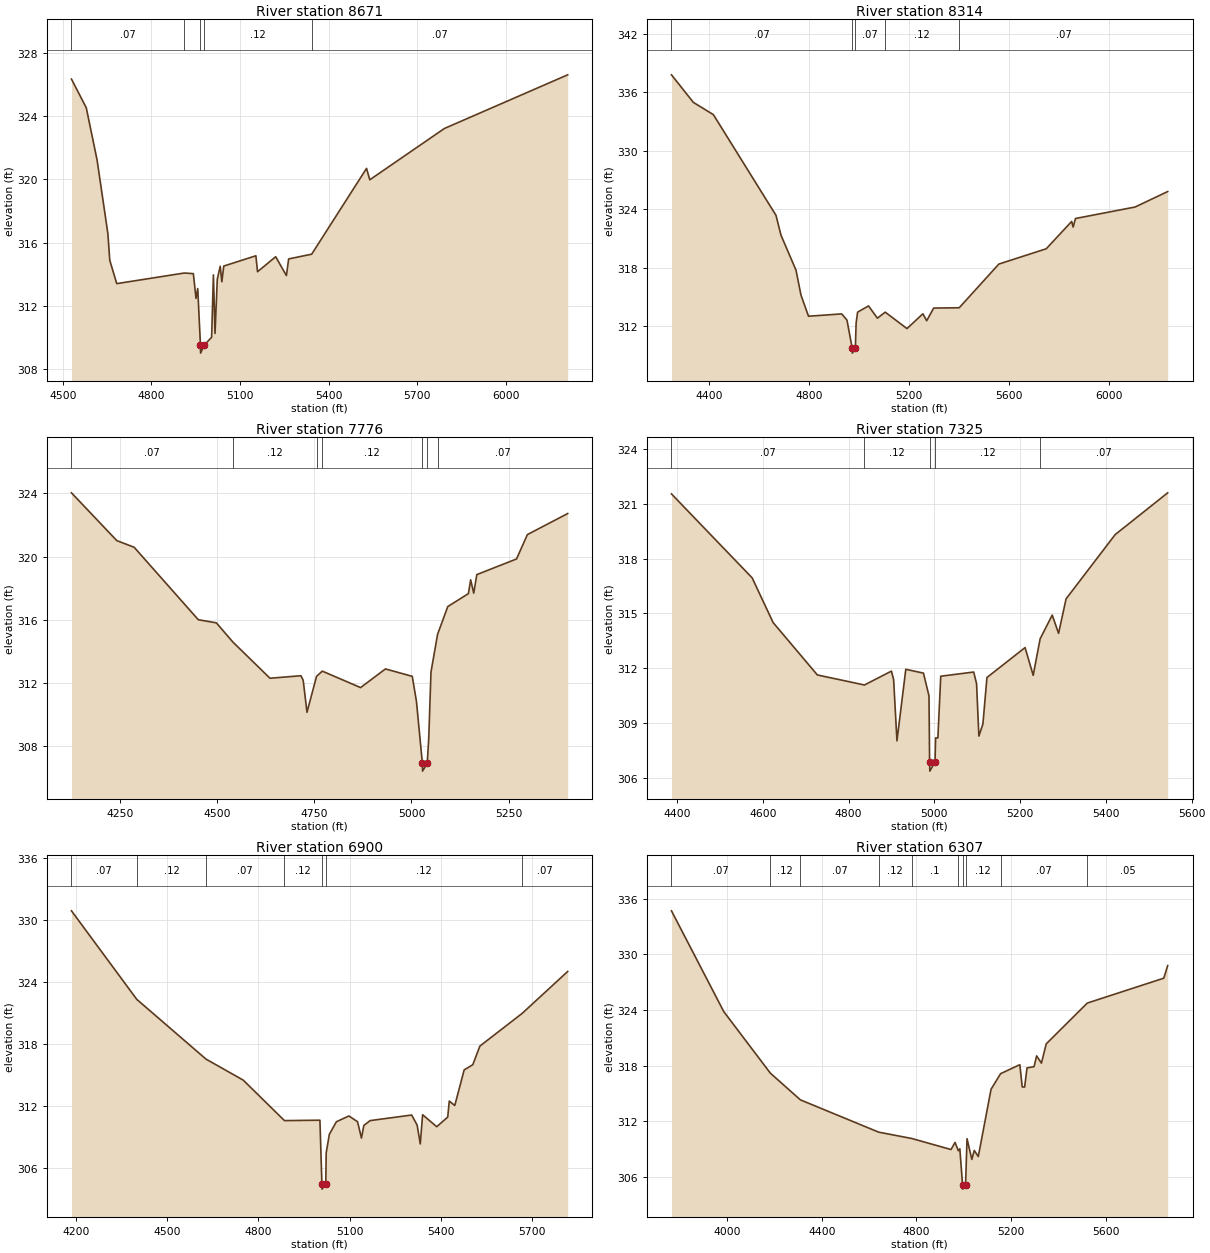
Type RM Length L Ch R = 1 ,8671    ,357,357,357
BEGIN DESCRIPTION:
EAST ELM CREEK 13.0
END DESCRIPTION:
XS GIS Cut Line= 3
      2495375.01     13788974.99        2494975.       13789225.
      2493875.01     13789724.99
#Sta/Elev= 30
  4529.5  326.34  4579.6  324.53  4616.2  321.23  4652.7  316.59  4659.2  314.89
  4682.8  313.42  4911.4  314.09  4942.2  314.05  4951.1  312.49    4957  313.11
  4966.2  309.53  4966.7  309.03  4978.5  309.53    5004  310.03    5010  313.97
  5015.5  310.27  5023.2   313.7  5033.1  314.52  5038.6  313.54  5045.1  314.53
  5153.9  315.18  5159.4  314.17  5220.9  315.12  5257.2  313.93  5264.8  314.98
  5342.8  315.28  5528.5   320.7  5539.5  319.98  5792.1  323.22  6209.5  326.61
#Mann= 5 ,-1 , 0
  4529.5     .07       0  4911.4     .12       0  4966.2     .05       0
  4978.5     .12       0  5342.8     .07       0
Bank Sta=4966.2,4978.5
XS Rating Curve= 0 ,0
Exp/Cntr=0.3,0.1

Type RM Length L Ch R = 1 ,8314    ,538,538,538
BEGIN DESCRIPTION:
EAST ELM CREEK 12.0
END DESCRIPTION:
XS GIS Cut Line= 3
      2495702.35     13788941.88      2495042.96     13788916.19
      2493925.01       13789625.
#Sta/Elev= 30
  4249.7   337.8  4337.1  334.97  4417.2  333.71  4667.4  323.37  4687.4  321.33
  4747.4  317.74  4767.4  315.17  4797.5     313  4930.2  313.24  4951.3   312.6
  4972.2  309.71  4972.7  309.21  4984.7  309.71  4987.8   312.3  4993.7  313.42
  5037.4  314.06  5072.9   312.8  5104.1  313.42  5191.1  311.73  5254.7  313.25
  5269.9  312.54  5297.9  313.84  5399.9  313.87  5558.4  318.36  5747.8  319.93
  5849.5  322.74  5855.4  322.16  5864.7  323.04  6103.1  324.22  6233.3  325.81
#Mann= 5 ,-1 , 0
  4249.7     .07       0  4972.2     .05       0  4984.7     .07       0
  5104.1     .12       0  5399.9     .07       0
Bank Sta=4972.2,4984.7
XS Rating Curve= 0 ,0
Exp/Cntr=0.3,0.1

Type RM Length L Ch R = 1 ,7776    ,451,451,451
BEGIN DESCRIPTION:
EAST ELM CREEK 11.0
END DESCRIPTION:
XS GIS Cut Line= 3
      2495225.03     13788574.98        2494475.       13789025.
      2494124.99       13789225.
#Sta/Elev= 30
  4124.4  324.03  4241.1  321.01  4285.8  320.59    4451  316.01  4497.6  315.81
  4540.4  314.59  4635.6  312.31  4715.3  312.47  4721.1  312.18  4730.9  310.16
  4755.5  312.43  4770.3  312.76  4868.9  311.72    4933   312.9    5002  312.43
  5012.8  310.84    5028  306.94  5028.5  306.44  5040.6  306.94  5044.4  308.51
  5050.2   312.7  5067.1  315.08  5093.4  316.84  5146.6  317.66  5152.4  318.53
  5160.3  317.69  5168.2  318.86  5270.5  319.85  5298.5  321.39  5402.2  322.72
#Mann= 7 ,-1 , 0
  4124.4     .07       0  4540.4     .12       0  4755.5     .07       0
  4770.3     .12       0    5028     .05       0  5040.6     .12       0
  5067.1     .07       0
Bank Sta=5028,5040.6
XS Rating Curve= 0 ,0
Exp/Cntr=0.3,0.1

Type RM Length L Ch R = 1 ,7325    ,425,425,425
BEGIN DESCRIPTION:
EAST ELM CREEK 10.0
END DESCRIPTION:
XS GIS Cut Line= 3
      2495124.96     13788575.01        2494525.       13788725.
      2494025.04     13788924.99
#Sta/Elev= 30
  4387.2  321.54  4575.3  316.94  4624.2  314.49  4727.3  311.62  4837.1  311.07
    4900  311.83  4905.1  311.37  4912.9  308.01  4933.5  311.93  4974.7  311.72
  4987.6  310.47    4989  306.85  4989.5  306.35  5001.6  306.85    5003  308.17
  5008.3  308.17    5015  311.55  5091.8  311.78  5098.5  311.14  5103.9  308.27
  5113.3  308.93  5122.7  311.48  5211.6  313.12  5230.5   311.6  5246.7   313.6
  5274.9   314.9  5289.7   313.9  5307.2  315.79  5421.6  319.31  5544.1   321.6
#Mann= 5 ,-1 , 0
  4387.2     .07       0  4837.1     .12       0    4989     .05       0
  5001.6     .12       0  5246.7     .07       0
Bank Sta=4989,5001.6
XS Rating Curve= 0 ,0
Exp/Cntr=0.3,0.1

Type RM Length L Ch R = 1 ,6900    ,593,593,593
BEGIN DESCRIPTION:
EAST ELM CREEK 9.0
END DESCRIPTION:
XS GIS Cut Line= 3
      2495375.03       13788275.        2494575.       13788375.
      2493774.98     13788575.01
#Sta/Elev= 30
  4185.4  330.85  4400.1  322.28  4627.6   316.5  4749.8  314.47  4885.5  310.55
    5002  310.59  5008.5  304.42    5009  303.92  5021.2  304.42  5022.6  307.43
  5032.9  309.22  5056.1  310.44  5097.3     311  5125.7  310.44  5138.5  308.86
  5146.3  310.08  5166.9  310.55  5303.5  311.09  5321.5  310.12  5331.8  308.29
  5339.5  311.12  5385.9  309.96    5422  310.89  5427.2  312.44  5445.2  312.01
  5476.1  315.46  5504.5  315.96  5527.7  317.76  5666.9  320.93  5816.3  324.98
#Mann= 7 ,-1 , 0
  4185.4     .07       0  4400.1     .12       0  4627.6     .07       0
  4885.5     .12       0  5008.5     .05       0  5021.2     .12       0
  5666.9     .07       0
Bank Sta=5008.5,5021.2
XS Rating Curve= 0 ,0
Exp/Cntr=0.3,0.1

Type RM Length L Ch R = 1 ,6307    ,335,335,335
BEGIN DESCRIPTION:
EAST ELM CREEK 8.0
END DESCRIPTION:
XS GIS Cut Line= 3
      2495424.95       13788025.      2494554.86     13788111.25
      2493348.76     13787905.96
#Sta/Elev= 30
  3764.3  334.72  3985.3  323.83  4182.2  317.18  4309.2  314.29    4640   310.8
  4780.6  310.11    4946  308.92  4963.1  309.69  4977.1  308.79  4983.4     309
  4994.8  305.14  4995.3  304.64  5007.6  305.14  5013.8  310.09  5034.1  307.85
  5044.3  308.82  5061.4  308.16  5115.3  315.43  5155.7  317.12    5237  318.09
  5247.1  315.69  5257.3  315.67  5267.4  317.74  5297.2  317.88    5308  319.04
  5328.3  318.26  5348.6  320.34  5522.2  324.75  5845.6  327.44  5862.1   328.8
#Mann= 10 ,-1 , 0
  3764.3     .07       0  4182.2     .12       0  4309.2     .07       0
    4640     .12       0  4780.6      .1       0  4977.1     .12       0
  4994.8     .05       0  5007.6     .12       0  5155.7     .07       0
  5522.2     .05       0
Bank Sta=4994.8,5007.6
XS Rating Curve= 0 ,0
Exp/Cntr=0.3,0.1

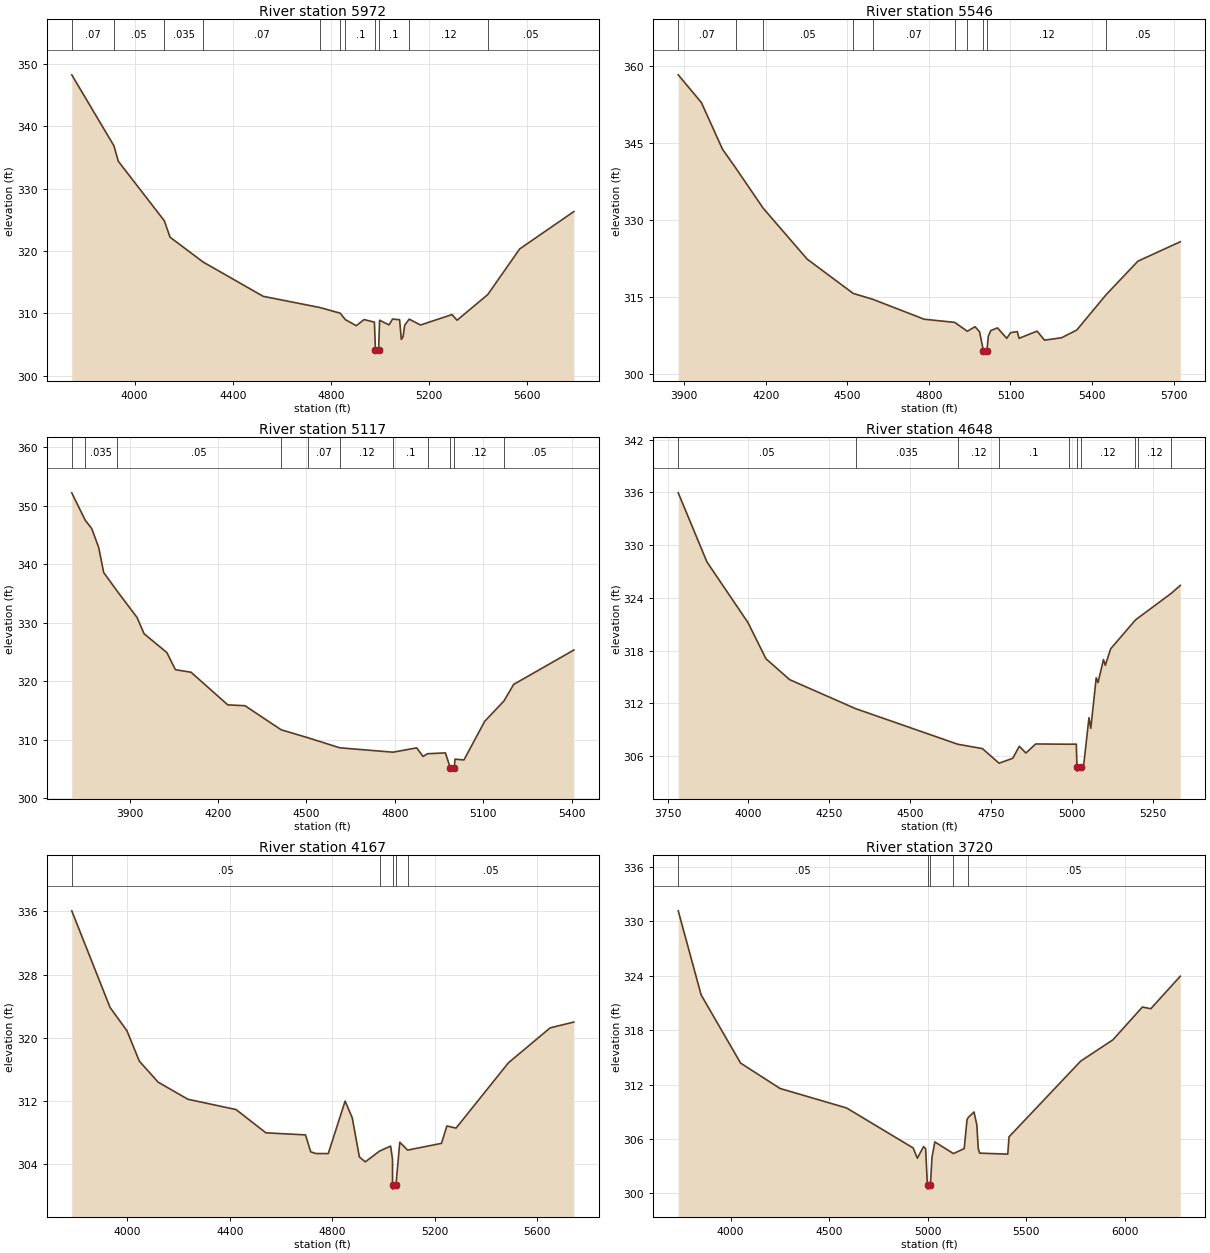
Type RM Length L Ch R = 1 ,5972    ,426,426,426
BEGIN DESCRIPTION:
EAST ELM CREEK 7.0
END DESCRIPTION:
XS GIS Cut Line= 3
      2495575.03     13787474.99        2494375.       13787875.
      2493774.98     13787374.98
#Sta/Elev= 30
    3744  348.24  3915.8  336.86  3933.8  334.37  4121.1  324.84  4144.6   322.2
  4279.2  318.22  4524.1  312.72  4754.2  310.93  4837.8  310.02    4859  308.98
  4903.5  308.01  4935.2  308.99  4977.3  308.58  4981.5  304.11    4982  303.61
  4994.3  304.11  4998.4  308.88  5036.9  308.14  5051.3  309.07  5079.9  308.97
    5087  305.81  5094.2  306.25  5100.7  308.09  5119.1  309.06  5165.2  308.12
  5293.4  309.79  5314.2  308.89  5439.2     313  5569.3  320.32    5790  326.31
#Mann= 11 ,-1 , 0
    3744     .07       0  3915.8     .05       0  4121.1    .035       0
  4279.2     .07       0  4754.2     .12       0  4837.8     .07       0
    4859      .1       0  4981.5     .05       0  4994.3      .1       0
  5119.1     .12       0  5439.2     .05       0
Bank Sta=4981.5,4994.3
XS Rating Curve= 0 ,0
Exp/Cntr=0.3,0.1

Type RM Length L Ch R = 1 ,5546    ,429,429,429
BEGIN DESCRIPTION:
EAST ELM CREEK 6.0
END DESCRIPTION:
XS GIS Cut Line= 3
      2495624.99       13787325.        2494525.       13787525.
      2493825.03     13787325.01
#Sta/Elev= 30
  3878.4   358.2  3963.5  352.81    4041  343.75    4090  340.07  4190.6  332.27
  4352.3  322.37  4521.7  315.69  4593.1  314.56    4783  310.67    4895  310.06
  4941.4  308.33  4969.7  309.22  4986.3  308.23  5000.4  304.58  5000.9  304.08
  5013.3  304.58  5018.5  307.37  5027.6  308.47  5052.3  308.99  5086.1  306.96
  5100.4  308.05  5125.1  308.26  5131.6  306.96  5197.9  308.36  5225.2   306.6
  5287.6  307.07  5343.5  308.56  5450.9   315.4  5568.4  321.96  5724.4  325.74
#Mann= 10 ,-1 , 0
  3878.4     .07       0    4090    .035       0  4190.6     .05       0
  4521.7    .035       0  4593.1     .07       0    4895      .1       0
  4941.4     .12       0  5000.4     .05       0  5013.3     .12       0
  5450.9     .05       0
Bank Sta=5000.4,5013.3
XS Rating Curve= 0 ,0
Exp/Cntr=0.3,0.1

Type RM Length L Ch R = 1 ,5117    ,469,469,469
BEGIN DESCRIPTION:
EAST ELM CREEK 5.0
END DESCRIPTION:
XS GIS Cut Line= 3
      2495474.97     13786775.01        2494275.       13787275.
      2493874.98       13787225.
#Sta/Elev= 30
  3703.8  352.22  3749.4  347.54  3771.5   346.1  3795.3  342.84  3812.1  338.58
  3857.3  335.44  3925.3  330.89  3949.1  328.11  4026.1   324.9  4055.3  321.96
  4108.4  321.52    4233  315.94  4291.5  315.79  4414.2  311.67  4505.1  310.31
  4613.1  308.59  4793.4  307.84  4873.8  308.58  4895.4  307.11  4910.7  307.58
  4971.3  307.72  4988.1   305.1  4988.6   304.6  5001.1   305.1  5003.8  306.65
    5034  306.51  5104.5  313.12  5169.6  316.59  5202.8  319.44  5406.9  325.32
#Mann= 11 ,-1 , 0
  3703.8     .07       0  3749.4    .035       0  3857.3     .05       0
  4414.2    .035       0  4505.1     .07       0  4613.1     .12       0
  4793.4      .1       0  4910.7     .12       0  4988.1     .05       0
  5001.1     .12       0  5169.6     .05       0
Bank Sta=4988.1,5001.1
XS Rating Curve= 0 ,0
Exp/Cntr=0.3,0.1

Type RM Length L Ch R = 1 ,4648    ,481,481,481
BEGIN DESCRIPTION:
EAST ELM CREEK 4.0
END DESCRIPTION:
XS GIS Cut Line= 3
      2495324.98       13786725.        2494125.       13786925.
      2493825.04     13787074.98
#Sta/Elev= 30
    3783  335.94  3871.7  328.08  3998.4  321.19  4054.2  317.06  4127.7  314.68
  4331.1  311.39  4646.9  307.34  4723.3  306.84  4774.6  305.18    4817  305.74
  4837.3  307.11  4857.6  306.34    4888  307.37  4991.4  307.34  5013.5  307.35
  5015.4  304.78  5015.9  304.28  5028.4  304.78  5035.9  304.87  5052.6  310.36
  5058.2  309.15    5075   314.9  5080.6  314.35  5097.4  316.97    5103  316.32
  5119.7   318.2  5195.8  321.46  5204.5  321.71  5307.5  324.52  5334.9  325.41
#Mann= 10 ,-1 , 0
    3783     .05       0  4331.1    .035       0  4646.9     .12       0
  4774.6      .1       0  4991.4     .12       0  5015.4     .05       0
  5028.4     .12       0  5195.8    .035       0  5204.5     .12       0
  5307.5    .035       0
Bank Sta=5015.4,5028.4
XS Rating Curve= 0 ,0
Exp/Cntr=0.3,0.1

Type RM Length L Ch R = 1 ,4167    ,447,447,447
BEGIN DESCRIPTION:
EAST ELM CREEK 3.0
END DESCRIPTION:
XS GIS Cut Line= 3
      2495324.97     13786674.99        2494125.       13786475.
      2493575.02     13786974.98
#Sta/Elev= 30
  3783.5  336.07    3933  323.83  3998.9  320.88  4047.1  317.04  4120.6  314.37
  4237.1   312.2  4424.7   310.9  4541.3  307.95  4695.9  307.69  4716.2  305.54
  4736.4  305.33  4784.6  305.32  4850.5  311.97  4878.4  309.84  4906.2   304.9
  4929.1  304.27    4985  305.64  5028.1  306.27  5035.5  304.59  5035.7  301.32
  5036.2  300.82  5048.8  301.32  5063.9  306.76  5094.3  305.76  5226.7  306.62
  5247.7  308.82  5283.5  308.55  5488.2  316.83  5651.1  321.25  5743.3  321.98
#Mann= 5 ,-1 , 0
  3783.5     .05       0    4985     .07       0  5035.7     .05       0
  5048.8     .07       0  5094.3     .05       0
Bank Sta=5035.7,5048.8
XS Rating Curve= 0 ,0
Exp/Cntr=0.3,0.1

Type RM Length L Ch R = 1 ,3720    ,370,370,370
BEGIN DESCRIPTION:
EAST ELM CREEK 2.0
END DESCRIPTION:
XS GIS Cut Line= 3
      2495275.04     13786475.01        2494075.       13786075.
      2493274.99     13787075.01
#Sta/Elev= 30
  3734.9  331.16  3850.9  321.89  4051.2  314.36  4251.5  311.56  4588.8  309.41
  4926.1     305  4947.2  303.87  4978.8  305.15  4989.3  304.93  4997.2   301.3
  5000.5  300.96    5001  300.46  5013.6  300.96  5021.5  303.98  5035.9  305.67
  5130.2  304.38  5184.7  304.93  5199.2  308.12  5205.4  308.36  5234.4  308.97
  5248.8  307.56    5256  304.94  5263.2  304.43  5405.7  304.32  5412.1  306.23
  5775.4  314.58  5938.7  316.93  6088.4  320.55  6130.8  320.36  6280.5  323.95
#Mann= 5 ,-1 , 0
  3734.9     .05       0  5000.5     .05       0  5013.6     .05       0
  5130.2     .07       0  5205.4     .05       0
Bank Sta=5000.5,5013.6
XS Rating Curve= 0 ,0
Exp/Cntr=0.3,0.1

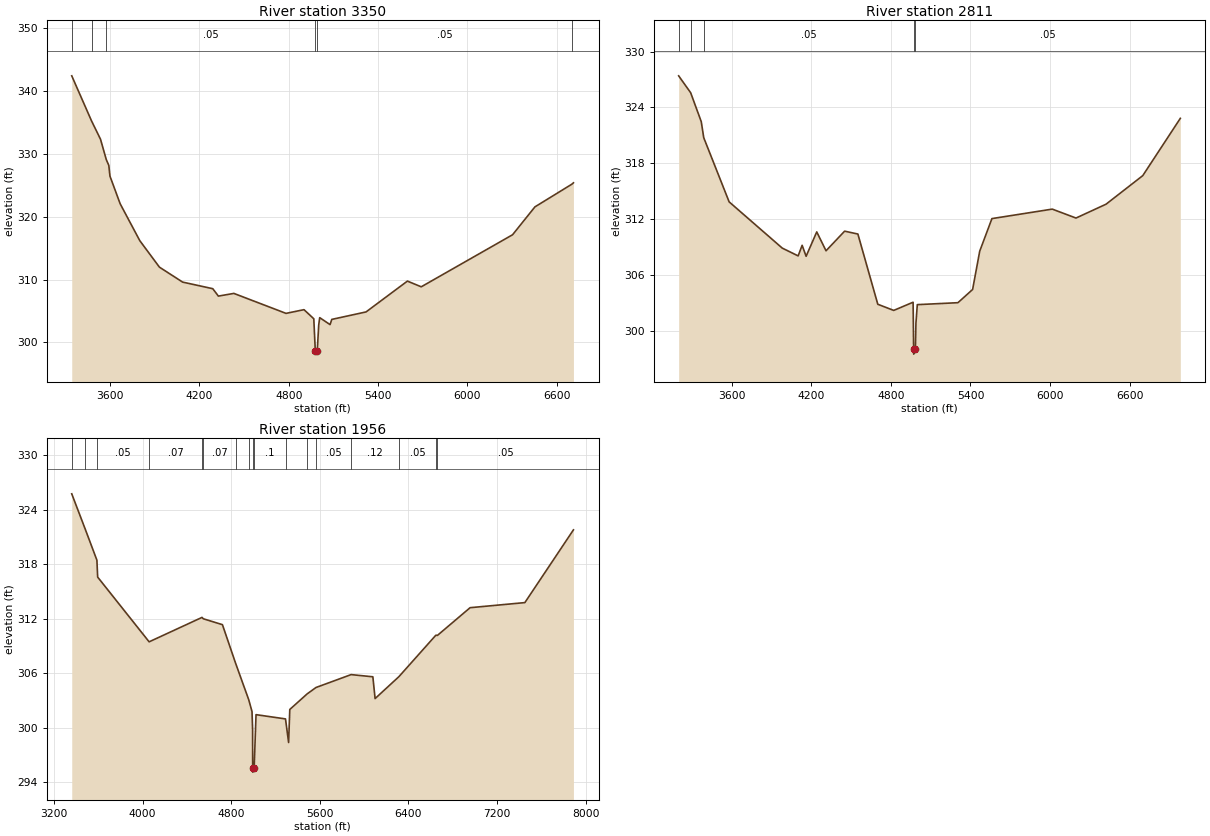
Type RM Length L Ch R = 1 ,3350    ,539,539,539
BEGIN DESCRIPTION:
X19082
END DESCRIPTION:
XS GIS Cut Line= 4
      2495591.04     13785859.14      2494246.58     13785653.62
      2493698.54     13785901.95      2493124.83     13787186.38
#Sta/Elev= 30
    3343  342.44  3475.7  335.27    3536  332.35  3574.9   329.1  3591.9  328.17
  3599.5  326.47    3668  322.07  3799.9  316.19  3931.8  311.97  4087.6  309.59
  4289.9  308.54  4327.6  307.36  4431.5  307.79  4781.7  304.61  4902.4   305.2
  4968.3  303.75  4978.3  298.62  4978.8  298.12  4991.5  298.62  5001.2  302.75
    5008  303.93  5077.3  302.82  5089.1  303.65  5319.1  304.84  5596.9  309.75
  5689.7  308.84  6302.9  317.13  6453.1  321.57  6701.5  325.19  6711.5   325.4
#Mann= 6 ,-1 , 0
    3343     .05       0  3475.7    .035       0  3574.9     .05       0
  4978.3     .05       0  4991.5     .05       0  6701.5    .035       0
Bank Sta=4978.3,4991.5
XS Rating Curve= 0 ,0
Exp/Cntr=0.3,0.1

Type RM Length L Ch R = 1 ,2811    ,855,855,855
BEGIN DESCRIPTION:
X19081
END DESCRIPTION:
XS GIS Cut Line= 4
      2495565.28     13785319.65      2493912.62     13785268.27
      2493458.77     13785422.41      2493099.36     13787031.19
#Sta/Elev= 30
  3200.7  327.39  3291.3  325.57  3371.1  322.46  3389.8  320.74  3581.2  313.84
  3981.4  308.87  4101.4  308.03  4131.4  309.17  4161.4  307.99  4241.5  310.61
  4311.5  308.58  4451.6  310.69  4551.6  310.38  4701.7  302.83  4821.8  302.17
  4967.8  303.05  4971.8  297.97  4972.3  297.47    4985  297.97  4989.1   300.8
  4999.5  302.79  5305.8     303  5416.3  304.42  5469.9  308.54  5561.9  312.04
  6016.7  313.06  6195.5   312.1  6422.2  313.59  6698.8  316.66  6981.9  322.82
#Mann= 5 ,-1 , 0
  3200.7     .05       0  3291.3    .035       0  3389.8     .05       0
  4971.8     .05       0    4985     .05       0
Bank Sta=4971.8,4985
XS Rating Curve= 0 ,0
Exp/Cntr=0.3,0.1

Type RM Length L Ch R = 1 ,1956    ,0,0,0
BEGIN DESCRIPTION:
EAST ELM CREEK 1.0
END DESCRIPTION:
XS GIS Cut Line= 4
      2495591.01     13785225.46      2494152.39     13784626.03
      2493321.76     13784917.18      2493039.17     13786989.52
#Sta/Elev= 30
  3359.8  325.74  3481.6  321.85    3587  318.43  3593.8  316.57  4058.6  309.44
    4536  312.13  4547.6  311.98  4720.5  311.33  4839.2  307.09  4957.8  303.07
  4987.6  301.76  4992.9  299.79  4993.5  295.59    4994  295.09  5007.1  295.59
  5023.9  301.42  5290.1  300.95  5318.1  298.35  5328.8  301.99  5484.8   303.7
  5565.4  304.41  5882.3  305.83  6078.9  305.59  6099.1  303.19  6314.5  305.61
  6647.8  310.17  6662.3  310.15  6956.9   313.2  7451.5  313.76    7890  321.77
#Mann= 17 ,-1 , 0
  3359.8     .05       0  3481.6    .035       0    3587     .05       0
  4058.6     .07       0    4536     .05       0  4547.6     .07       0
  4839.2     .05       0  4957.8      .1       0  4993.5     .05       0
  5007.1      .1       0  5290.1     .05       0  5484.8     .07       0
  5565.4     .05       0  5882.3     .12       0  6314.5     .05       0
  6647.8     .12       0  6662.3     .05       0
Bank Sta=4993.5,5007.1
XS Rating Curve= 0 ,0
Exp/Cntr=0.3,0.1

Chan Stop Cuts=-1
Use User Specified Reach Order=0
Composite Channel Slope=5