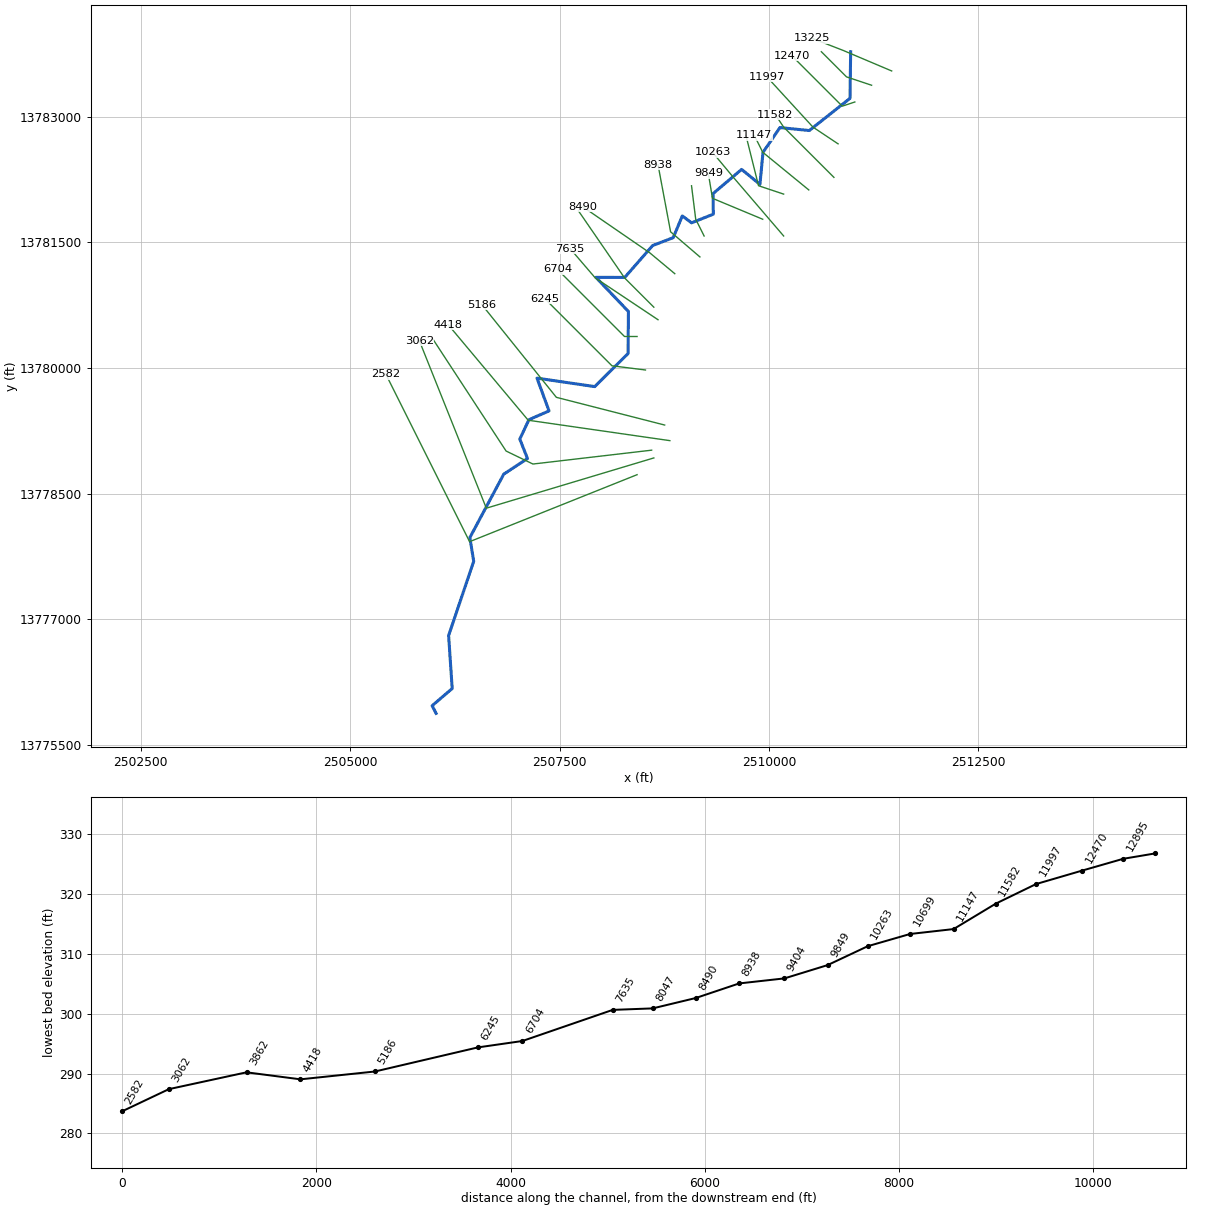
--- EAST ROCKY CREEK.prj (project) ---

Proj Title=EAST ROCKY CREEK Base Level Engineering
Current Plan=p01
Default Exp/Contr=0.3,0.1
English Units
Geom File=g01
Flow File=f01
Plan File=p01
BEGIN DESCRIPTION:
EAST ROCKY CREEK
END DESCRIPTION:

--- EAST ROCKY CREEK.p01 (plan) ---

Plan Title=Multiple Run
Short Identifier=Multiple
Geom File=g01
Flow File=f01
Subcritical Flow
K Sum by GR= 0
Std Step Tol= 0.01
Critical Tol= 0.01
Num of Std Step Trials= 20
Max Error Tol= 0.3
Flow Tol Ratio= 0.001
Split Flow NTrial= 30
Split Flow Tol= 0.02
Split Flow Ratio= 0.02
Log Output Level= 0
Friction Slope Method= 1
Unsteady Friction Slope Method= 2
Unsteady Bridges Friction Slope Method= 1
Parabolic Critical Depth
Global Vel Dist=  1 , 1 , 1
Global Log Level= 0
CheckData=True
Encroach Param= -1, 0, 0, 0
BEGIN DESCRIPTION:
Multiple Run
END DESCRIPTION:

--- EAST ROCKY CREEK.f01 (steady flow) ---

Flow Title=Multiple
Number of Profiles=7
Profile Names=10-year,25-year,50-year,1pct_min,100-year,1pct_plu,500-year
River Rch & RM= EAST ROCKY CREEK,Reach-1,13225
     709    1141    1530     994    1983    3956    3295
River Rch & RM= EAST ROCKY CREEK,Reach-1,8938
     886    1433    1927    1254    2502    4991    4172
Boundary for River Rch & Prof#=EAST ROCKY CREEK,Reach-1,1
Up Type=0
Dn Type=3
Dn Slope=0.005
Boundary for River Rch & Prof#=EAST ROCKY CREEK,Reach-1,2
Up Type=0
Dn Type=3
Dn Slope=0.005
Boundary for River Rch & Prof#=EAST ROCKY CREEK,Reach-1,3
Up Type=0
Dn Type=3
Dn Slope=0.005
Boundary for River Rch & Prof#=EAST ROCKY CREEK,Reach-1,4
Up Type=0
Dn Type=3
Dn Slope=0.005
Boundary for River Rch & Prof#=EAST ROCKY CREEK,Reach-1,5
Up Type=0
Dn Type=3
Dn Slope=0.005
Boundary for River Rch & Prof#=EAST ROCKY CREEK,Reach-1,6
Up Type=0
Dn Type=3
Dn Slope=0.005
Boundary for River Rch & Prof#=EAST ROCKY CREEK,Reach-1,7
Up Type=0
Dn Type=3
Dn Slope=0.005

--- EAST ROCKY CREEK.g01 (geometry) ---

Geom Title=Existing Conditions

River Reach=EAST ROCKY CREEK,Reach-1
Reach XY= 30
      2510975.00     13783775.00      2510967.25     13783218.81
      2510481.73     13782834.11      2510130.61     13782869.41
      2509928.48     13782573.74      2509891.74     13782191.19
      2509673.03     13782370.08      2509332.35     13782081.38
      2509335.17     13781835.36      2509074.91     13781732.31
      2508965.00     13781814.04      2508855.90     13781554.49
      2508611.43     13781461.53      2508277.29     13781080.11
      2507932.64     13781081.55      2508321.54     13780673.50
      2508317.21     13780171.58      2507918.97     13779776.61
      2507229.97     13779877.59      2507373.63     13779486.53
      2507133.13     13779381.07      2507024.76     13779150.08
      2507116.16     13778918.05      2506832.81     13778731.21
      2506428.13     13777973.37      2506474.31     13777690.84
      2506174.77     13776804.62      2506217.20     13776171.58
      2505977.92     13775966.66      2506025.00     13775875.00

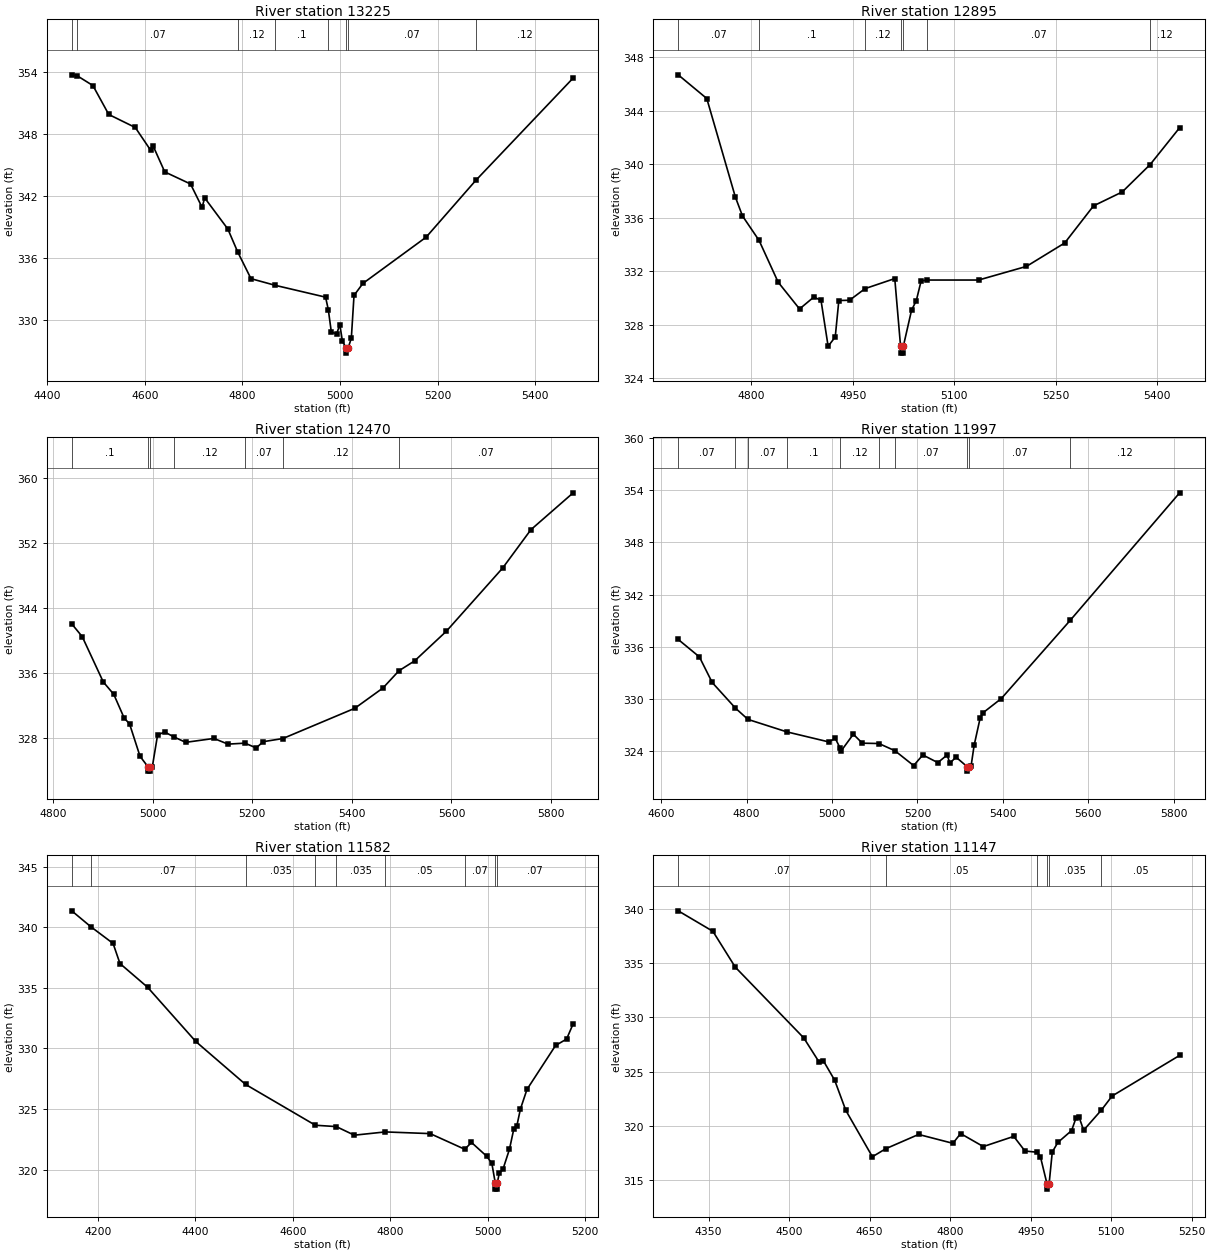
Type RM Length L Ch R = 1,13225,330,330,330
BEGIN DESCRIPTION:
X19085
END DESCRIPTION:
XS GIS Cut Line= 3
      2511464.93     13783545.45      2510885.28     13783790.81
      2510514.14     13783934.97
#Sta/Elev= 30
  4450.4  353.73  4462.2  353.62  4493.8  352.69  4526.3  349.89  4580.6  348.63
  4611.9  346.44  4617.3  346.83  4641.0  344.33  4693.8  343.16  4717.5  340.90
  4722.9  341.81  4770.3  338.80  4790.3  336.60  4817.7  333.99  4867.9  333.34
  4970.6  332.20  4976.2  330.99  4982.4  328.82  4993.3  328.64  4999.8  329.55
  5005.2  327.91  5013.0  327.28  5013.2  326.78  5017.0  327.28  5023.4  328.24
  5028.9  332.37  5047.1  333.53  5176.7  338.01  5278.3  343.50  5478.0  353.42
#Mann=8,-1,0
  4450.4   0.035       0  4462.2    0.07       0  4790.3    0.12       0
  4867.9     0.1       0  4976.2    0.07       0  5013.0    0.05       0
  5017.0    0.07       0  5278.3    0.12       0
Bank Sta=5013,5017
Exp/Cntr=0.3,0.1

Type RM Length L Ch R = 1,12895,425,425,425
BEGIN DESCRIPTION:
EAST ROCKY CREEK 19.0
END DESCRIPTION:
XS GIS Cut Line= 3
      2511225.04     13783374.99      2510925.00     13783475.00
      2510625.03     13783774.97
#Sta/Elev= 30
  4692.4  346.67  4734.6  344.90  4776.8  337.54  4787.3  336.13  4811.8  334.30
  4840.0  331.18  4871.6  329.18  4892.7  330.07  4903.3  329.82  4913.8  326.39
  4924.3  327.09  4929.6  329.81  4945.4  329.83  4968.4  330.70  5012.2  331.45
  5020.8  326.38  5021.1  325.88  5024.6  325.88  5024.8  326.38  5037.0  329.09
  5044.0  329.80  5051.1  331.27  5059.6  331.34  5136.0  331.34  5206.7  332.36
  5263.2  334.11  5305.7  336.88  5348.1  337.92  5389.4  339.97  5432.9  342.72
#Mann=7,-1,0
  4692.4    0.07       0  4811.8     0.1       0  4968.4    0.12       0
  5020.8    0.05       0  5024.8    0.12       0  5059.6    0.07       0
  5389.4    0.12       0
Bank Sta=5020.8,5024.8
Exp/Cntr=0.3,0.1

Type RM Length L Ch R = 1,12470,473,473,473
BEGIN DESCRIPTION:
EAST ROCKY CREEK 18.0
END DESCRIPTION:
XS GIS Cut Line= 3
      2511025.02     13783175.01      2510875.00     13783125.00
      2510274.98     13783725.02
#Sta/Elev= 30
  4837.6  342.06  4858.7  340.48  4900.9  334.90  4922.0  333.37  4943.0  330.43
  4953.6  329.74  4974.7  325.73  4991.1  324.40  4991.4  323.90  4994.9  323.90
  4995.1  324.40  4999.3  324.40  5009.9  328.35  5024.0  328.73  5043.0  328.11
  5066.4  327.45  5123.0  327.93  5151.3  327.23  5185.5  327.35  5207.9  326.76
  5222.0  327.53  5261.5  327.92  5405.9  331.65  5462.4  334.15  5494.6  336.28
  5526.1  337.50  5589.7  341.15  5702.8  348.95  5759.4  353.67  5844.3  358.22
#Mann=7,-1,0
  4837.6     0.1       0  4991.1    0.05       0  4995.1     0.1       0
  5043.0    0.12       0  5185.5    0.07       0  5261.5    0.12       0
  5494.6    0.07       0
Bank Sta=4991.1,4995.1
Exp/Cntr=0.3,0.1

Type RM Length L Ch R = 1,11997,415,415,415
BEGIN DESCRIPTION:
EAST ROCKY CREEK 17.0
END DESCRIPTION:
XS GIS Cut Line= 3
      2510825.01     13782674.99      2510525.00     13782875.00
      2509975.01     13783474.99
#Sta/Elev= 30
  4639.8  336.83  4689.4  334.82  4719.4  331.87  4773.8  328.92  4803.1  327.62
  4894.4  326.18  4992.9  325.02  5007.5  325.45  5018.6  324.36  5021.6  324.00
  5050.0  325.91  5071.0  324.88  5109.9  324.84  5147.4  324.01  5191.2  322.30
  5212.8  323.52  5247.9  322.64  5269.5  323.51  5276.3  322.59  5290.5  323.27
  5316.9  322.16  5317.1  321.66  5320.9  322.16  5325.9  322.28  5333.0  324.65
  5347.2  327.81  5354.0  328.39  5396.6  330.02  5557.8  339.02  5814.3  353.72
#Mann=10,-1,0
  4639.8    0.07       0  4773.8   0.035       0  4803.1    0.07       0
  4894.4     0.1       0  5018.6    0.12       0  5109.9     0.1       0
  5147.4    0.07       0  5316.9    0.05       0  5320.9    0.07       0
  5557.8    0.12       0
Bank Sta=5316.9,5320.9
Exp/Cntr=0.3,0.1

Type RM Length L Ch R = 1,11582,435,435,435
BEGIN DESCRIPTION:
EAST ROCKY CREEK 16.0
END DESCRIPTION:
XS GIS Cut Line= 3
      2510774.99     13782275.01      2510175.00     13782875.00
      2510074.99     13783025.01
#Sta/Elev= 30
  4146.5  341.35  4185.3  340.05  4231.3  338.66  4245.5  337.00  4302.0  335.05
  4401.0  330.57  4503.1  327.03  4646.4  323.66  4689.2  323.55  4726.3  322.84
  4789.7  323.11  4881.9  322.97  4952.8  321.68  4966.7  322.24  4998.0  321.10
  5008.5  320.51  5015.5  318.89  5015.8  318.39  5019.3  318.39  5019.5  318.89
  5023.6  319.68  5031.1  320.01  5044.6  321.68  5053.6  323.37  5059.6  323.58
  5067.1  325.00  5080.6  326.62  5139.2  330.24  5161.8  330.77  5175.3  332.03
#Mann=9,-1,0
  4146.5   0.035       0  4185.3    0.07       0  4503.1   0.035       0
  4646.4    0.07       0  4689.2   0.035       0  4789.7    0.05       0
  4952.8    0.07       0  5015.5    0.05       0  5019.5    0.07       0
Bank Sta=5015.5,5019.5
Exp/Cntr=0.3,0.1

Type RM Length L Ch R = 1,11147,448,448,448
BEGIN DESCRIPTION:
EAST ROCKY CREEK 15.0
END DESCRIPTION:
XS GIS Cut Line= 3
      2510475.02     13782124.98      2509925.00     13782575.00
      2509824.98     13782775.03
#Sta/Elev= 30
  4293.3  339.84  4357.9  337.95  4399.6  334.64  4527.3  328.10  4556.0  325.86
  4563.9  325.98  4584.8  324.20  4605.6  321.41  4655.1  317.13  4680.0  317.87
  4741.2  319.19  4805.1  318.37  4819.5  319.27  4861.8  318.07  4918.5  319.01
  4939.4  317.66  4961.5  317.55  4968.1  317.15  4980.4  314.64  4980.7  314.14
  4984.4  314.64  4990.3  317.57  5000.7  318.45  5026.3  319.55  5034.7  320.74
  5040.3  320.78  5048.7  319.58  5081.8  321.44  5101.8  322.74  5227.6  326.49
#Mann=6,-1,0
  4293.3    0.07       0  4680.0    0.05       0  4961.5   0.035       0
  4980.4   0.035       0  4984.4   0.035       0  5081.8    0.05       0
Bank Sta=4980.4,4984.4
Exp/Cntr=0.3,0.1

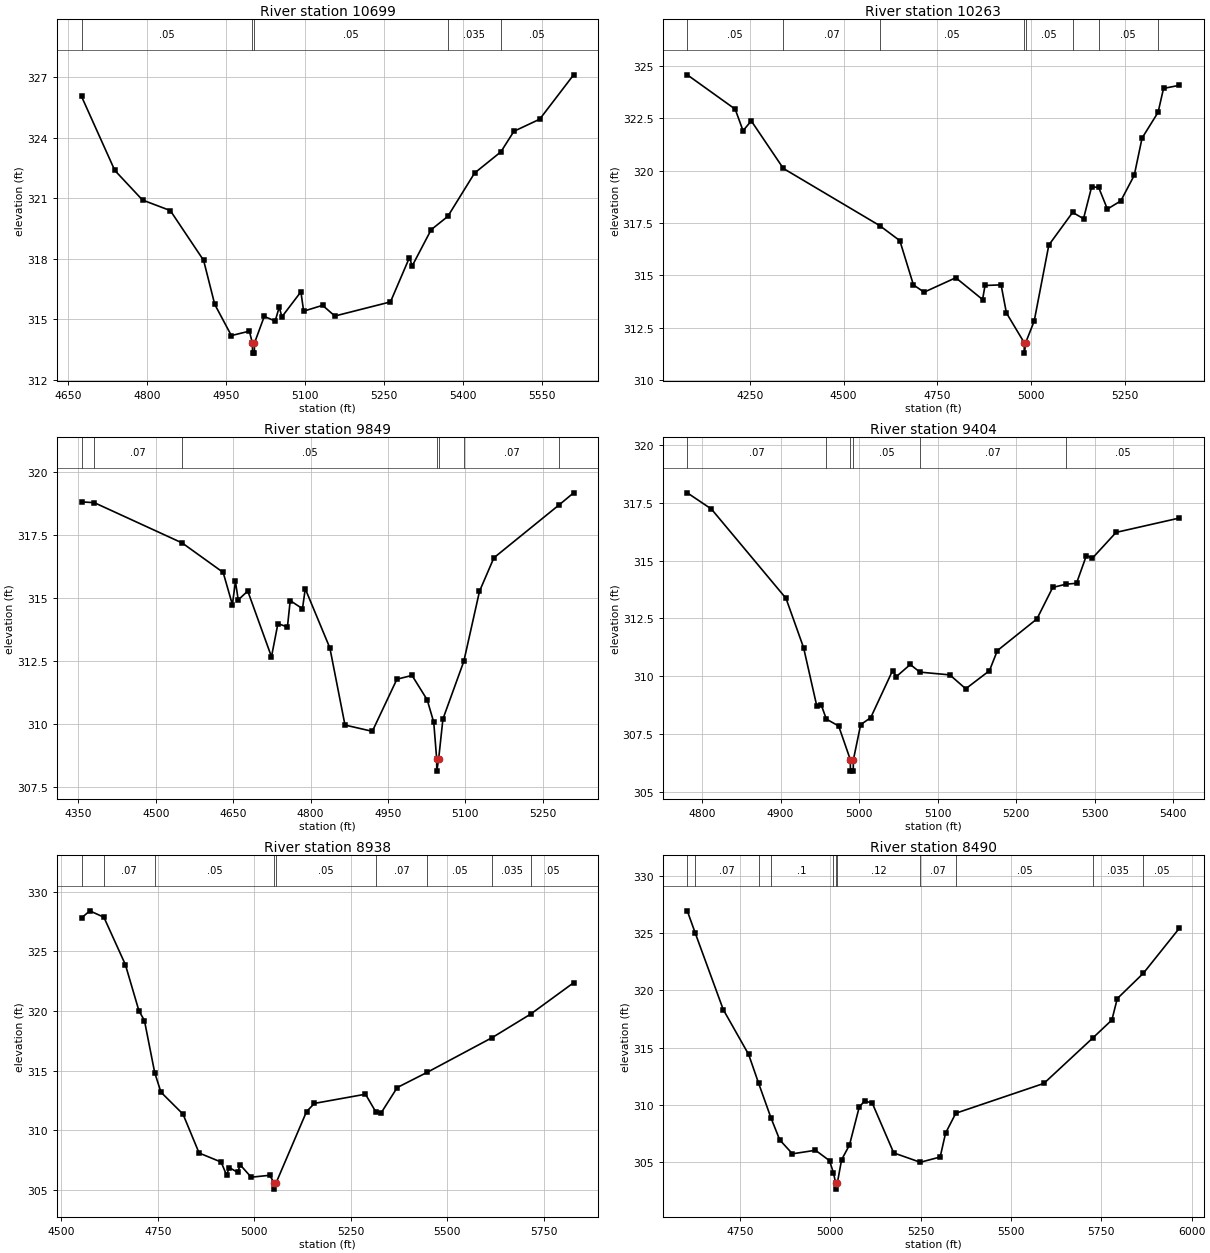
Type RM Length L Ch R = 1,10699,436,436,436
BEGIN DESCRIPTION:
EAST ROCKY CREEK 14.0
END DESCRIPTION:
XS GIS Cut Line= 3
      2510174.99     13782075.00      2509875.00     13782175.00
      2509725.00     13782775.02
#Sta/Elev= 30
  4676.2  326.05  4739.4  322.38  4792.1  320.91  4844.8  320.39  4908.1  317.92
  4929.2  315.74  4960.8  314.19  4995.0  314.41  5000.7  313.82  5001.0  313.32
  5004.5  313.32  5004.7  313.82  5023.3  315.14  5044.0  314.91  5051.7  315.60
  5056.8  315.12  5092.9  316.36  5098.1  315.40  5134.1  315.69  5157.3  315.16
  5263.0  315.86  5299.1  318.06  5304.2  317.64  5340.3  319.44  5371.9  320.10
  5422.8  322.25  5472.7  323.30  5497.5  324.32  5546.5  324.92  5610.9  327.12
#Mann=5,-1,0
  4676.2    0.05       0  5000.7    0.05       0  5004.7    0.05       0
  5371.9   0.035       0  5472.7    0.05       0
Bank Sta=5000.7,5004.7
Exp/Cntr=0.3,0.1

Type RM Length L Ch R = 1,10263,414,414,414
BEGIN DESCRIPTION:
EAST ROCKY CREEK 13.0
END DESCRIPTION:
XS GIS Cut Line= 3
      2510174.99     13781575.01      2509575.00     13782275.00
      2509325.03     13782574.96
#Sta/Elev= 30
  4083.1  324.57  4210.9  322.93  4231.8  321.90  4253.8  322.37  4339.3  320.10
  4596.2  317.37  4650.0  316.65  4686.2  314.54  4714.7  314.19  4799.2  314.88
  4870.6  313.84  4877.2  314.51  4920.0  314.54  4934.2  313.20  4981.6  311.78
  4981.9  311.28  4985.6  311.78  5008.3  312.81  5047.3  316.44  5110.8  318.00
  5139.8  317.70  5161.2  319.20  5179.8  319.21  5203.5  318.16  5239.3  318.55
  5275.1  319.77  5296.0  321.55  5338.7  322.78  5353.2  323.92  5395.5  324.07
#Mann=8,-1,0
  4083.1    0.05       0  4339.3    0.07       0  4596.2    0.05       0
  4981.6    0.05       0  4985.6    0.05       0  5110.8    0.07       0
  5179.8    0.05       0  5338.7   0.035       0
Bank Sta=4981.6,4985.6
Exp/Cntr=0.3,0.1

Type RM Length L Ch R = 1,9849,445,445,445
BEGIN DESCRIPTION:
EAST ROCKY CREEK 12.0
END DESCRIPTION:
XS GIS Cut Line= 3
      2509924.97     13781775.01      2509325.00     13782025.00
      2509275.00     13782324.99
#Sta/Elev= 30
  4355.9  318.81  4380.6  318.78  4551.0  317.18  4630.5  316.01  4648.4  314.73
  4654.3  315.65  4659.7  314.92  4678.2  315.27  4724.2  312.66  4736.7  313.98
  4755.1  313.84  4760.5  314.89  4784.3  314.57  4789.7  315.36  4837.4  313.01
  4866.7  309.95  4919.7  309.70  4967.4  311.77  4996.7  311.92  5026.1  310.95
  5038.8  310.06  5044.4  308.62  5044.7  308.12  5048.4  308.62  5056.6  310.19
  5097.1  312.48  5127.5  315.26  5155.4  316.59  5282.4  318.70  5310.0  319.17
#Mann=7,-1,0
  4355.9    0.05       0  4380.6    0.07       0  4551.0    0.05       0
  5044.4    0.05       0  5048.4    0.05       0  5097.1    0.07       0
  5282.4    0.05       0
Bank Sta=5044.4,5048.4
Exp/Cntr=0.3,0.1

Type RM Length L Ch R = 1,9404,466,466,466
BEGIN DESCRIPTION:
EAST ROCKY CREEK 11.0
END DESCRIPTION:
XS GIS Cut Line= 3
      2509224.98     13781575.04      2509125.00     13781775.00
      2509075.00     13782175.02
#Sta/Elev= 30
  4781.2  317.93  4811.9  317.23  4906.9  313.37  4929.3  311.24  4946.1  308.72
  4951.7  308.77  4958.3  308.15  4974.0  307.85  4988.8  306.40  4989.0  305.90
  4992.5  305.90  4992.8  306.40  5002.0  307.91  5014.8  308.21  5042.6  310.24
  5047.6  309.99  5065.2  310.51  5077.4  310.18  5115.6  310.06  5135.8  309.46
  5166.0  310.24  5176.1  311.11  5226.5  312.48  5246.6  313.84  5263.4  313.98
  5276.9  314.02  5289.5  315.22  5297.0  315.10  5327.3  316.22  5407.9  316.84
#Mann=6,-1,0
  4781.2    0.07       0  4958.3    0.05       0  4988.8    0.05       0
  4992.8    0.05       0  5077.4    0.07       0  5263.4    0.05       0
Bank Sta=4988.8,4992.8
Exp/Cntr=0.3,0.1

Type RM Length L Ch R = 1,8938,448,448,448
BEGIN DESCRIPTION:
EAST ROCKY CREEK 10.0
END DESCRIPTION:
XS GIS Cut Line= 3
      2509175.04     13781324.97      2508825.00     13781625.00
      2508674.99     13782425.03
#Sta/Elev= 30
  4552.4  327.80  4573.8  328.40  4610.4  327.86  4666.0  323.89  4701.2  320.01
  4715.4  319.20  4742.0  314.83  4758.2  313.19  4815.3  311.35  4857.0  308.09
  4914.1  307.33  4928.4  306.22  4934.9  306.87  4956.9  306.47  4963.5  307.10
  4992.0  306.06  5039.7  306.22  5052.1  305.56  5052.3  305.06  5056.2  305.56
  5135.5  311.57  5155.9  312.25  5288.1  313.02  5315.4  311.51  5328.8  311.46
  5370.4  313.58  5448.2  314.86  5616.5  317.77  5716.1  319.74  5827.4  322.37
#Mann=9,-1,0
  4552.4    0.05       0  4610.4    0.07       0  4742.0    0.05       0
  5052.1    0.05       0  5056.2    0.05       0  5315.4    0.07       0
  5448.2    0.05       0  5616.5   0.035       0  5716.1    0.05       0
Bank Sta=5052.1,5056.2
Exp/Cntr=0.3,0.1

Type RM Length L Ch R = 1,8490,443,443,443
BEGIN DESCRIPTION:
EAST ROCKY CREEK 9.0
END DESCRIPTION:
XS GIS Cut Line= 3
      2508874.97     13781125.03      2508575.00     13781375.00
      2507775.00     13781925.00
#Sta/Elev= 30
  4604.8  326.97  4626.9  325.02  4704.3  318.33  4774.6  314.40  4802.3  311.87
  4836.5  308.84  4860.5  306.93  4895.7  305.71  4959.5  306.02  4998.3  305.11
  5009.2  304.04  5015.6  303.12  5015.8  302.62  5019.7  303.12  5031.7  305.19
  5053.5  306.48  5080.5  309.80  5095.4  310.34  5116.6  310.14  5175.9  305.79
  5249.4  304.97  5304.4  305.43  5319.3  307.52  5347.6  309.26  5591.3  311.87
  5727.4  315.87  5779.4  317.42  5794.3  319.29  5866.5  321.51  5966.1  325.45
#Mann=11,-1,0
  4604.8    0.05       0  4626.9    0.07       0  4802.3    0.05       0
  4836.5     0.1       0  5009.2    0.12       0  5015.6    0.05       0
  5019.7    0.12       0  5249.4    0.07       0  5347.6    0.05       0
  5727.4   0.035       0  5866.5    0.05       0
Bank Sta=5015.6,5019.7
Exp/Cntr=0.3,0.1

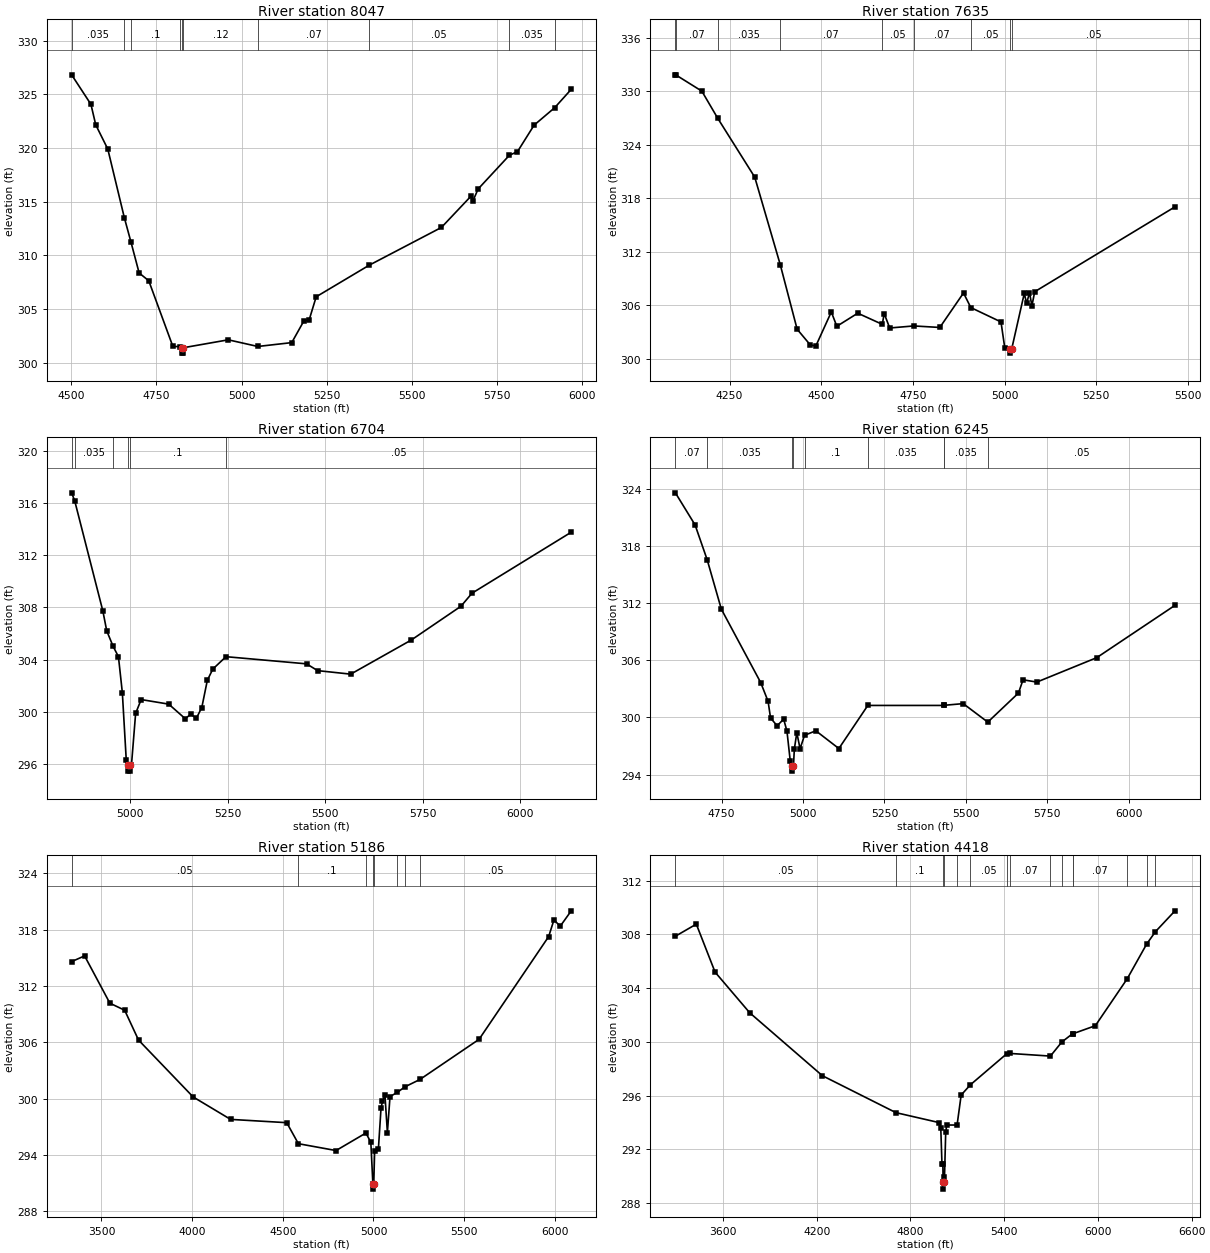
Type RM Length L Ch R = 1,8047,412,412,412
BEGIN DESCRIPTION:
EAST ROCKY CREEK 8.0
END DESCRIPTION:
XS GIS Cut Line= 3
      2508624.99     13780725.01      2508275.00     13781075.00
      2507724.99     13781875.01
#Sta/Elev= 30
  4501.4  326.82  4558.0  324.07  4572.1  322.16  4607.5  319.90  4655.9  313.52
  4675.1  311.28  4699.4  308.36  4727.7  307.63  4798.4  301.51  4818.4  301.50
  4824.6  301.39  4824.9  300.89  4828.5  300.89  4828.7  301.39  4961.0  302.13
  5047.6  301.51  5147.2  301.87  5183.1  303.91  5198.0  303.96  5218.9  306.14
  5374.3  309.08  5586.3  312.60  5672.9  315.51  5679.0  315.09  5693.9  316.18
  5785.9  319.33  5809.4  319.66  5858.2  322.13  5918.7  323.76  5967.2  325.47
#Mann=10,-1,0
  4501.4   0.035       0  4655.9    0.07       0  4675.1     0.1       0
  4818.4    0.12       0  4824.6    0.05       0  4828.7    0.12       0
  5047.6    0.07       0  5374.3    0.05       0  5785.9   0.035       0
  5918.7    0.05       0
Bank Sta=4824.6,4828.7
Exp/Cntr=0.3,0.1

Type RM Length L Ch R = 1,7635,931,931,931
BEGIN DESCRIPTION:
EAST ROCKY CREEK 7.0
END DESCRIPTION:
XS GIS Cut Line= 3
      2508675.02     13780574.99      2507925.00     13781075.00
      2507624.99     13781425.01
#Sta/Elev= 30
  4102.3  331.86  4103.1  331.86  4174.4  330.03  4218.0  326.97  4318.7  320.38
  4388.2  310.57  4434.3  303.32  4470.4  301.55  4485.4  301.45  4527.5  305.26
  4542.5  303.65  4599.6  305.12  4666.5  303.87  4671.7  305.08  4686.7  303.46
  4752.4  303.69  4823.4  303.52  4888.0  307.39  4907.9  305.75  4990.2  304.14
  5000.7  301.18  5015.2  301.14  5015.5  300.64  5019.6  301.14  5053.7  307.34
  5060.2  306.21  5067.9  307.44  5074.5  305.95  5082.2  307.53  5464.7  317.05
#Mann=9,-1,0
  4102.3    0.05       0  4103.1    0.07       0  4218.0   0.035       0
  4388.2    0.07       0  4666.5    0.05       0  4752.4    0.07       0
  4907.9    0.05       0  5015.2    0.05       0  5019.6    0.05       0
Bank Sta=5015.2,5019.6
Exp/Cntr=0.3,0.1

Type RM Length L Ch R = 1,6704,459,459,459
BEGIN DESCRIPTION:
EAST ROCKY CREEK 6.0
END DESCRIPTION:
XS GIS Cut Line= 3
      2508424.97     13780375.00      2508275.00     13780375.00
      2507475.03     13781174.97
#Sta/Elev= 30
  4850.0  316.79  4857.9  316.17  4930.0  307.73  4940.0  306.20  4956.4  305.01
  4970.0  304.22  4980.0  301.47  4990.0  296.32  4995.2  295.94  4995.6  295.44
  4999.4  295.44  4999.7  295.94  5003.5  295.94  5014.1  299.87  5028.3  300.93
  5099.0  300.58  5141.4  299.46  5155.5  299.81  5169.7  299.49  5183.8  300.32
  5198.0  302.41  5212.1  303.27  5245.8  304.22  5452.5  303.67  5480.8  303.15
  5565.7  302.88  5721.2  305.50  5848.5  308.09  5876.8  309.09  6131.3  313.77
#Mann=6,-1,0
  4850.0    0.05       0  4857.9   0.035       0  4956.4     0.1       0
  4995.2    0.05       0  4999.7     0.1       0  5245.8    0.05       0
Bank Sta=4995.2,4999.7
Exp/Cntr=0.3,0.1

Type RM Length L Ch R = 1,6245,1059,1059,1059
BEGIN DESCRIPTION:
EAST ROCKY CREEK 5.0
END DESCRIPTION:
XS GIS Cut Line= 3
      2508525.02     13779975.00      2508125.00     13780025.00
      2507325.00     13780825.00
#Sta/Elev= 30
  4608.1  323.56  4668.6  320.19  4705.9  316.52  4749.2  311.36  4870.1  303.66
  4892.8  301.69  4900.4  299.94  4920.5  299.13  4940.7  299.82  4950.8  298.55
  4960.8  295.46  4966.2  294.87  4966.5  294.37  4970.7  294.87  4973.4  296.67
  4981.0  298.40  4991.1  296.72  5004.7  298.13  5039.5  298.60  5110.2  296.74
  5199.1  301.26  5431.8  301.26  5432.2  301.27  5492.1  301.45  5567.6  299.51
  5661.8  302.56  5675.9  303.95  5718.3  303.71  5902.2  306.27  6142.6  311.76
#Mann=9,-1,0
  4608.1    0.07       0  4705.9   0.035       0  4966.2   0.035       0
  4970.7   0.035       0  5004.7     0.1       0  5199.1   0.035       0
  5431.8    0.05       0  5432.2   0.035       0  5567.6    0.05       0
Bank Sta=4966.2,4970.7
Exp/Cntr=0.3,0.1

Type RM Length L Ch R = 1,5186,768,768,768
BEGIN DESCRIPTION:
EAST ROCKY CREEK 4.0
END DESCRIPTION:
XS GIS Cut Line= 3
      2508754.17     13779317.71      2507460.93     13779648.78
      2506571.18     13780755.79
#Sta/Elev= 30
  3335.4  314.59  3406.8  315.20  3546.2  310.16  3627.8  309.41  3704.3  306.23
  4005.5  300.17  4212.0  297.78  4521.6  297.43  4585.8  295.19  4793.5  294.46
  4958.4  296.33  4985.4  295.33  4996.8  290.85  4997.1  290.35  5001.4  290.85
  5006.3  294.37  5027.1  294.63  5041.5  298.95  5049.4  299.70  5063.2  300.36
  5076.7  296.38  5091.1  300.21  5132.4  300.67  5172.7  301.24  5255.9  302.03
  5582.3  306.31  5966.2  317.26  5995.0  319.02  6030.2  318.37  6090.6  320.00
#Mann=8,-1,0
  3335.4    0.05       0  4585.8     0.1       0  4958.4    0.07       0
  4996.8    0.05       0  5001.4    0.07       0  5132.4    0.05       0
  5172.7   0.035       0  5255.9    0.05       0
Bank Sta=4996.8,5001.4
Exp/Cntr=0.3,0.1

Type RM Length L Ch R = 1,4418,556,556,556
BEGIN DESCRIPTION:
EAST ROCKY CREEK 3.0
END DESCRIPTION:
XS GIS Cut Line= 3
      2508816.32     13779131.47      2507125.00     13779375.00
      2506168.82     13780516.48
#Sta/Elev= 30
  3295.7  307.86  3429.6  308.76  3549.6  305.19  3771.7  302.16  4236.6  297.48
  4707.7  294.73  4984.3  293.99  4994.4  293.57  5001.9  290.94  5007.7  290.94
  5009.3  289.54  5009.6  289.04  5014.0  289.54  5018.1  289.91  5025.9  293.26
  5032.4  293.81  5098.7  293.81  5124.8  296.04  5183.5  296.80  5416.1  299.11
  5434.3  299.14  5696.1  298.94  5769.3  299.99  5838.6  300.61  5841.8  300.61
  5983.6  301.20  6188.0  304.70  6312.3  307.28  6368.4  308.20  6493.5  309.75
#Mann=15,-1,0
  3295.7    0.05       0  4707.7     0.1       0  5009.3    0.05       0
  5014.0     0.1       0  5098.7    0.07       0  5183.5    0.05       0
  5416.1   0.035       0  5434.3    0.07       0  5696.1    0.05       0
  5769.3    0.07       0  5838.6    0.05       0  5841.8    0.07       0
  6188.0    0.05       0  6312.3   0.035       0  6368.4    0.05       0
Bank Sta=5009.3,5014
Exp/Cntr=0.3,0.1

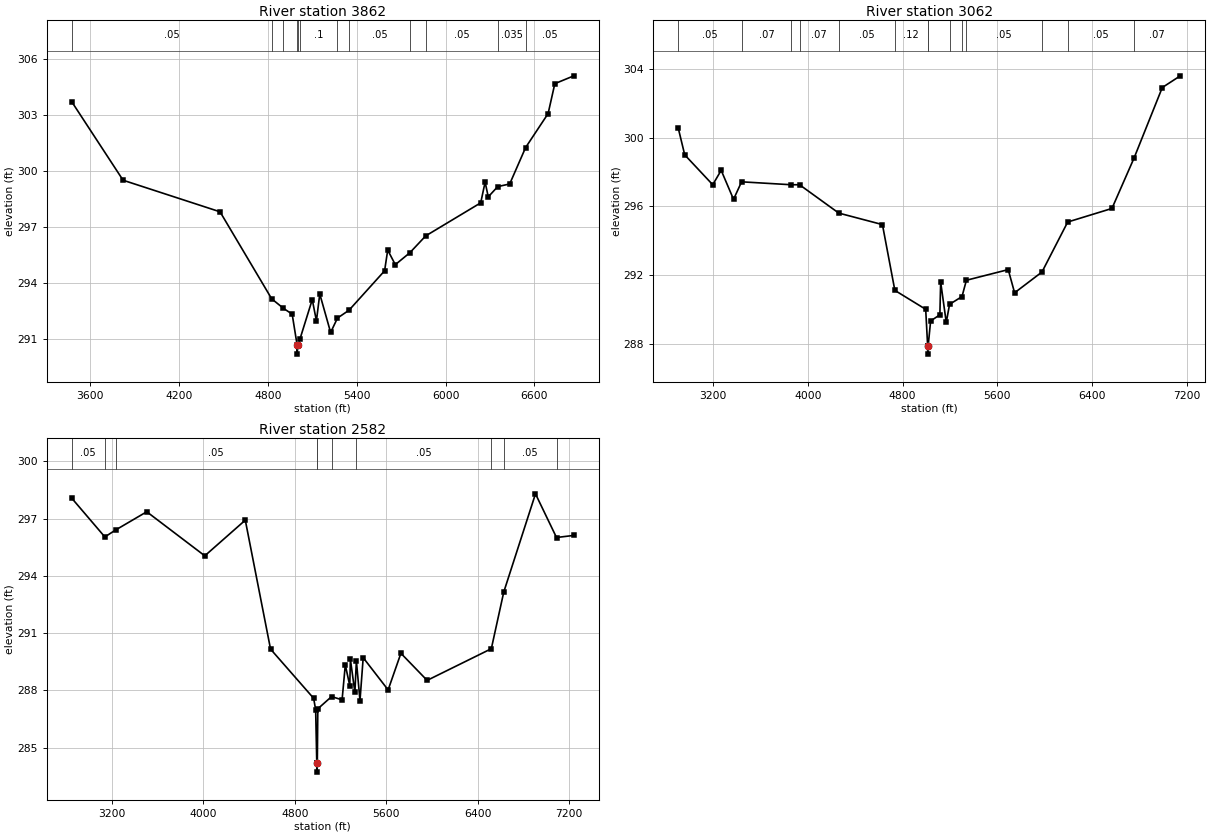
Type RM Length L Ch R = 1,3862,800,800,800
BEGIN DESCRIPTION:
X19084
END DESCRIPTION:
XS GIS Cut Line= 4
      2508599.03     13779017.67      2507181.59     13778852.13
      2506860.86     13779007.32      2505982.19     13780351.17
#Sta/Elev= 30
  3476.9  303.72  3823.3  299.52  4477.7  297.83  4826.4  293.17  4906.0  292.66
  4964.6  292.35  4997.8  290.71  4998.2  290.21  5002.5  290.71  5016.9  291.01
  5100.2  293.13  5128.3  291.99  5150.9  293.43  5224.2  291.37  5270.3  292.14
  5348.2  292.56  5588.4  294.67  5609.5  295.78  5660.8  295.00  5759.1  295.64
  5865.9  296.54  6237.2  298.31  6267.0  299.42  6288.1  298.63  6352.2  299.18
  6432.9  299.32  6540.3  301.27  6692.2  303.09  6737.5  304.69  6865.9  305.11
#Mann=12,-1,0
  3476.9    0.05       0  4826.4     0.1       0  4906.0    0.07       0
  4997.8    0.05       0  5002.5    0.07       0  5016.9     0.1       0
  5270.3    0.07       0  5348.2    0.05       0  5759.1   0.035       0
  5865.9    0.05       0  6352.2   0.035       0  6540.3    0.05       0
Bank Sta=4997.8,5002.5
Exp/Cntr=0.3,0.1

Type RM Length L Ch R = 1,3062,480,480,480
BEGIN DESCRIPTION:
EAST ROCKY CREEK 2.0
END DESCRIPTION:
XS GIS Cut Line= 3
      2508625.03     13778925.01      2506625.00     13778325.00
      2505824.99     13780325.03
#Sta/Elev= 30
  2904.8  300.56  2959.6  299.00  3196.3  297.26  3267.6  298.10  3372.0  296.41
  3440.0  297.43  3858.4  297.26  3929.8  297.26  4261.2  295.61  4630.1  294.94
  4735.1  291.11  4995.6  290.01  5012.0  287.90  5012.4  287.40  5016.8  287.90
  5037.3  289.33  5115.4  289.69  5122.1  291.60  5169.3  289.25  5197.5  290.30
  5302.3  290.75  5339.6  291.70  5693.0  292.32  5746.8  290.97  5978.1  292.18
  6195.5  295.09  6569.4  295.88  6756.5  298.82  6994.8  302.92  7147.0  303.60
#Mann=14,-1,0
  2904.8    0.05       0  3440.0    0.07       0  3858.4    0.05       0
  3929.8    0.07       0  4261.2    0.05       0  4735.1    0.12       0
  5012.0    0.05       0  5016.8    0.12       0  5197.5    0.05       0
  5302.3    0.07       0  5339.6    0.05       0  5978.1   0.035       0
  6195.5    0.05       0  6756.5    0.07       0
Bank Sta=5012,5016.8
Exp/Cntr=0.3,0.1

Type RM Length L Ch R = 1,2582,0,0,0
BEGIN DESCRIPTION:
EAST ROCKY CREEK 1.0
END DESCRIPTION:
XS GIS Cut Line= 3
      2508425.02     13778725.01      2506425.00     13777925.00
      2505424.98     13779925.04
#Sta/Elev= 30
  2849.7  298.07  3138.9  296.04  3232.1  296.40  3505.4  297.36  4012.9  295.05
  4367.0  296.92  4587.8  290.16  4964.7  287.58  4982.2  286.98  4992.0  284.21
  4992.3  283.71  4996.8  284.21  5001.1  287.03  5121.4  287.67  5213.4  287.50
  5241.4  289.33  5280.5  288.25  5286.1  289.62  5325.2  287.89  5338.4  289.54
  5369.9  287.46  5397.9  289.71  5615.9  288.02  5727.7  289.94  5956.9  288.52
  6518.4  290.18  6627.0  293.15  6904.4  298.30  7088.3  296.01  7239.9  296.12
#Mann=10,-1,0
  2849.7    0.05       0  3138.9    0.07       0  3232.1    0.05       0
  4992.0    0.05       0  4996.8    0.05       0  5121.4     0.1       0
  5338.4    0.05       0  6518.4   0.035       0  6627.0    0.05       0
  7088.3    0.07       0
Bank Sta=4992,4996.8
Exp/Cntr=0.3,0.1

Chan Stop Cuts=-1