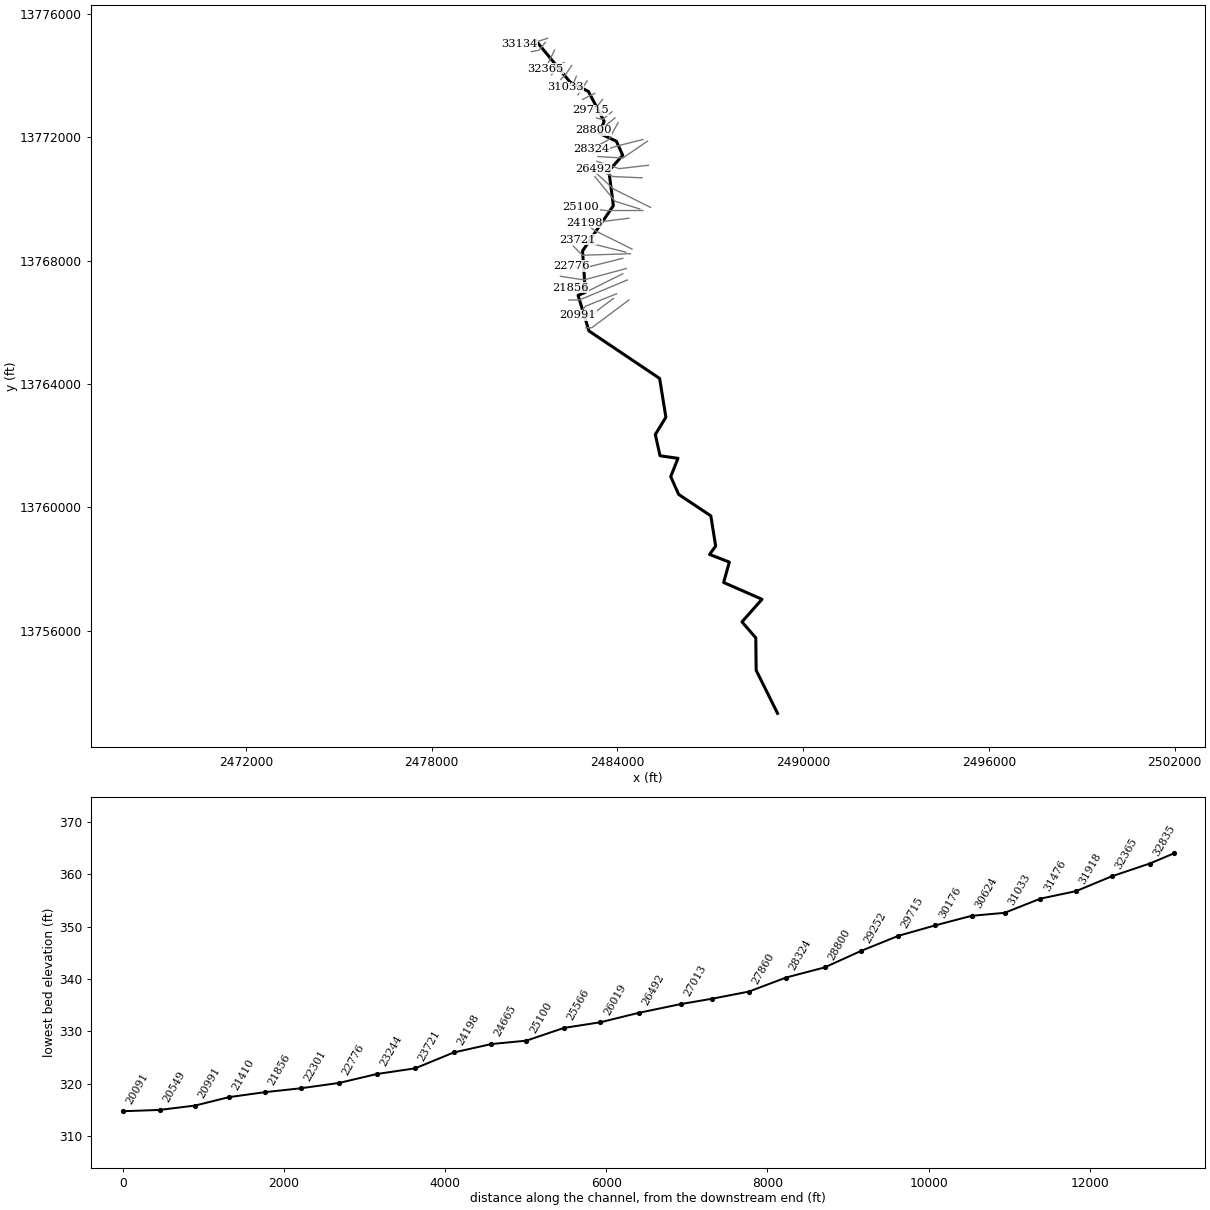
--- EAST TINSLEY CREEK.prj (project) ---

Proj Title=EAST TINSLEY CREEK Base Level Engineering
Current Plan=p01
Default Exp/Contr=0.3,0.1
English Units
Geom File=g01
Flow File=f01
Plan File=p01
Y Axis Title=Elevation
X Axis Title(PF)=Main Channel Distance
X Axis Title(XS)=Station
BEGIN DESCRIPTION:
EAST TINSLEY CREEK
END DESCRIPTION:
DSS Export Rating Curves= 0
DSS Export Rating Curve Sorted= 0
DSS Export Volume Flow Curves= 0
DXF OffsetX= 0
DXF OffsetY= 0
DXF ScaleX= 1
DXF ScaleY= 10

--- EAST TINSLEY CREEK.p01 (plan) ---

Plan Title=Multiple Run
Short Identifier=Multiple
Geom File=g01
Flow File=f01
Subcritical Flow
K Sum by GR= 0
Std Step Tol= 0.01
Critical Tol= 0.01
Num of Std Step Trials= 20
Max Error Tol= 0.3
Flow Tol Ratio= 0.001
Split Flow NTrial= 30
Split Flow Tol= 0.02
Split Flow Ratio= 0.02
Log Output Level= 0
Friction Slope Method= 1
Unsteady Friction Slope Method= 2
Unsteady Bridges Friction Slope Method= 1
Parabolic Critical Depth
Global Vel Dist=  1 , 1 , 1
Global Log Level= 0
CheckData=True
Encroach Param= -1, 0, 0, 0
BEGIN DESCRIPTION:
Multiple Run
END DESCRIPTION:

--- EAST TINSLEY CREEK.f01 (steady flow) ---

Flow Title=Multiple
Number of Profiles=7
Profile Names=10-year,25-year,50-year,1pct_min,100-year,1pct_plu,500-year
River Rch & RM= EAST TINSLEY CRE,Reach-1,33134
     818    1333    1805    1183    2360    4708    3995
River Rch & RM= EAST TINSLEY CRE,Reach-1,27407
    1053    1727    2345    1539    3071    6127    5218
River Rch & RM= EAST TINSLEY CRE,Reach-1,20991
    1296    2146    2932    1935    3860    7702    6631
River Rch & RM= EAST TINSLEY CRE,Reach-1,19241
    1496    2488    3408    2253    4496    8970    7754
River Rch & RM= EAST TINSLEY CRE,Reach-1,15228
    1635    2720    3727    2463    4915    9807    8472
River Rch & RM= EAST TINSLEY CRE,Reach-1,9842
    1753    2913    3988    2632    5252   10478    9028
River Rch & RM= EAST TINSLEY CRE,Reach-1,1738
    1813    3018    4137    2733    5453   10880    9392
Boundary for River Rch & Prof#=EAST TINSLEY CRE,Reach-1,1
Up Type=0
Dn Type=3
Dn Slope=0.005
Boundary for River Rch & Prof#=EAST TINSLEY CRE,Reach-1,2
Up Type=0
Dn Type=3
Dn Slope=0.005
Boundary for River Rch & Prof#=EAST TINSLEY CRE,Reach-1,3
Up Type=0
Dn Type=3
Dn Slope=0.005
Boundary for River Rch & Prof#=EAST TINSLEY CRE,Reach-1,4
Up Type=0
Dn Type=3
Dn Slope=0.005
Boundary for River Rch & Prof#=EAST TINSLEY CRE,Reach-1,5
Up Type=0
Dn Type=3
Dn Slope=0.005
Boundary for River Rch & Prof#=EAST TINSLEY CRE,Reach-1,6
Up Type=0
Dn Type=3
Dn Slope=0.005
Boundary for River Rch & Prof#=EAST TINSLEY CRE,Reach-1,7
Up Type=0
Dn Type=3
Dn Slope=0.005

--- EAST TINSLEY CREEK.g01 (geometry) ---

Geom Title=Existing Conditions
Program Version=4.10

River Reach=EAST TINSLEY CRE,Reach-1
Reach XY= 30
        2481375.       13775125.      2482480.18     13773780.41
      2483064.68     13773485.19      2483572.86     13772519.03
      2483430.46     13772122.55      2483969.42     13771870.24
      2484174.06     13771414.51      2483725.46     13770914.48
      2483871.84     13769783.34      2482876.04     13768314.56
      2482967.79     13766974.65      2482732.21     13766875.35
      2483082.47     13765721.38      2485365.87     13764181.74
       2485567.7     13762924.92      2485225.94     13762364.51
      2485378.45     13761676.19      2485958.72     13761591.75
      2485724.41       13761000.      2485979.95     13760422.49
      2487019.54     13759727.45      2487175.32     13758749.89
       2486978.1     13758476.65      2487617.17     13758228.22
      2487432.69     13757568.53      2488671.55     13757023.52
      2488025.03     13756290.42      2488471.55     13755773.75
      2488483.28     13754721.78        2489175.       13753325.

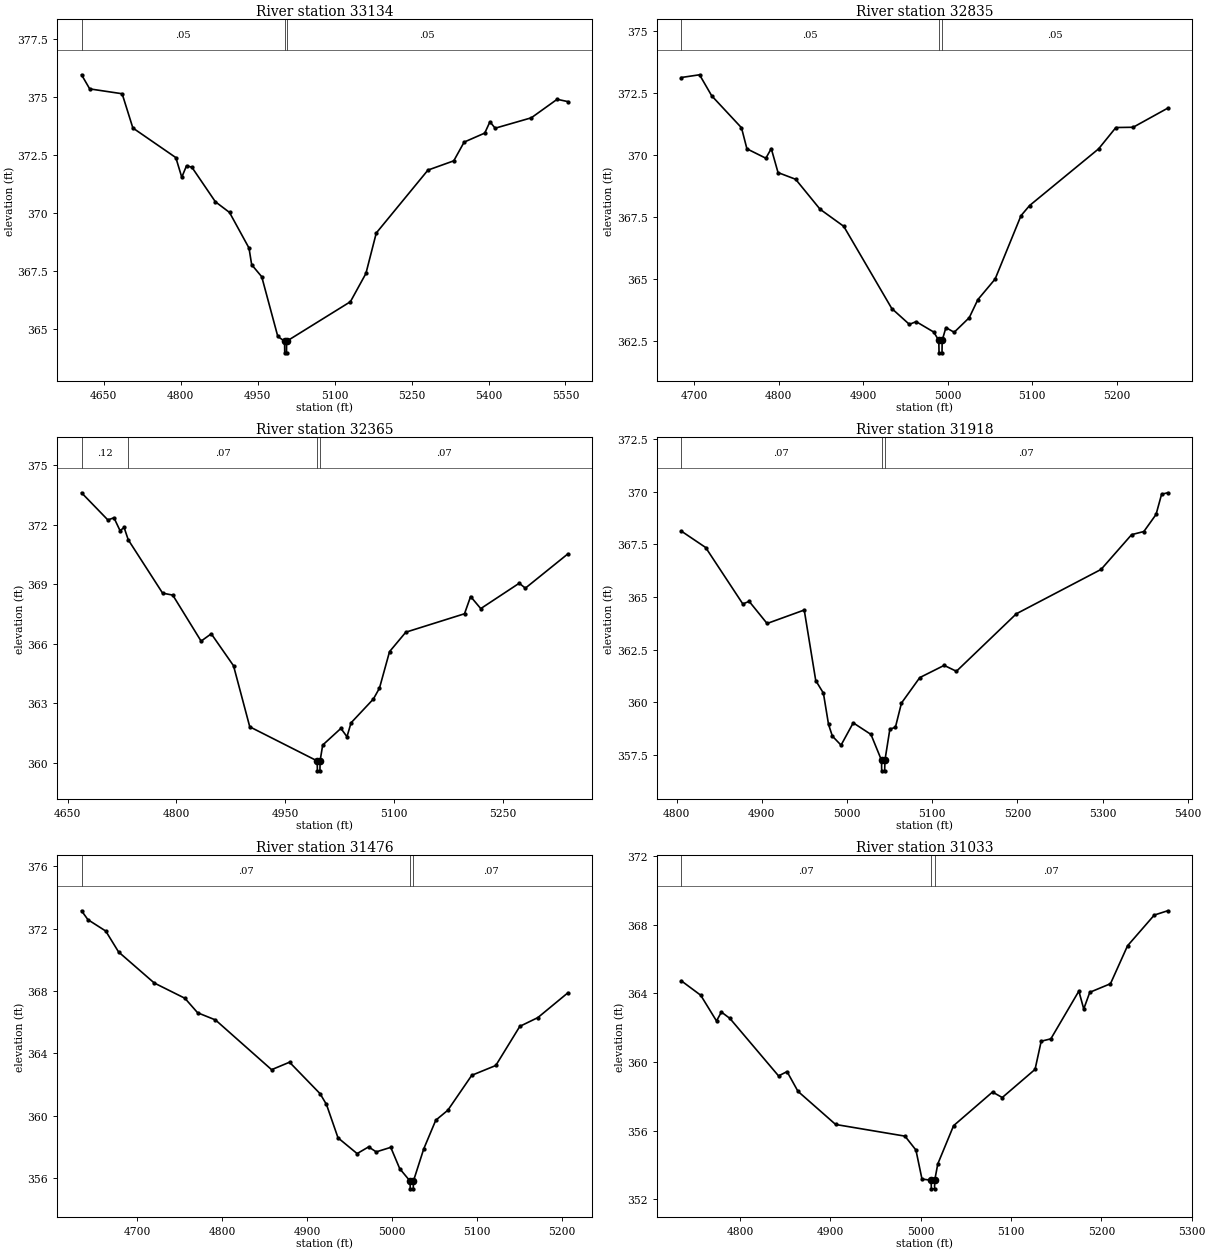
Type RM Length L Ch R = 1 ,33134   ,299,299,299
BEGIN DESCRIPTION:
X19090
END DESCRIPTION:
XS GIS Cut Line= 3
      2481750.64     13775206.07      2481372.99     13775090.26
      2480824.19     13775024.81
#Sta/Elev= 30
    4607  375.97  4622.9  375.36  4686.1  375.15    4707  373.67  4790.7  372.39
  4802.3  371.54  4811.6  372.04  4822.1  371.97  4867.8  370.48  4895.3  370.02
  4933.3  368.48  4938.5  367.76  4958.1  367.24  4989.4  364.66  5002.6  364.45
  5002.9  363.95  5006.4  363.95  5006.6  364.45  5130.9  366.16  5161.1  367.38
  5181.3  369.13    5282  371.85  5332.3  372.25  5352.5  373.06  5392.7  373.45
  5402.8  373.94  5412.9  373.66  5483.4  374.11  5533.7  374.91  5554.7  374.81
#Mann= 3 ,-1 , 0
    4607     .05       0  5002.6     .05       0  5006.6     .05       0
Bank Sta=5002.6,5006.6
XS Rating Curve= 0 ,0
Exp/Cntr=0.3,0.1

Type RM Length L Ch R = 1 ,32835   ,470,470,470
BEGIN DESCRIPTION:
EAST TINSLEY CREEK 65.0
END DESCRIPTION:
XS GIS Cut Line= 3
      2481674.98     13775074.98        2481475.       13774825.
      2481224.98       13774775.
#Sta/Elev= 30
    4685  373.14  4706.6  373.25    4721   372.4  4756.2  371.11  4762.6  370.26
    4785  369.88  4791.4  370.27  4799.4   369.3  4820.2  369.03  4849.1  367.82
  4877.1  367.13  4933.9  363.81  4954.7  363.17  4962.7  363.28  4983.5  362.86
  4989.5  362.52  4989.8  362.02  4993.3  362.02  4993.5  362.52  4997.9  363.04
  5007.7  362.85  5025.5  363.44  5035.7  364.17  5056.1     365  5086.7  367.56
  5096.9  367.97  5178.5  370.26  5198.9  371.12  5219.3  371.13  5260.1   371.9
#Mann= 3 ,-1 , 0
    4685     .05       0  4989.5     .05       0  4993.5     .05       0
Bank Sta=4989.5,4993.5
XS Rating Curve= 0 ,0
Exp/Cntr=0.3,0.1

Type RM Length L Ch R = 1 ,32365   ,447,447,447
BEGIN DESCRIPTION:
EAST TINSLEY CREEK 64.0
END DESCRIPTION:
XS GIS Cut Line= 3
      2481974.99     13774824.98        2481825.       13774525.
        2481675.       13774225.
#Sta/Elev= 30
  4669.2  373.61  4705.5  372.24  4713.9  372.35  4722.3   371.7  4727.9  371.86
  4733.6  371.24    4781  368.55    4795  368.45  4834.1  366.13  4848.1   366.5
  4878.8  364.89  4901.2  361.81  4994.2  360.09  4994.5  359.59    4998  359.59
  4998.2  360.09  5001.8  360.89  5026.9  361.73  5035.3  361.31  5040.9  362.01
  5071.7  363.21  5080.1  363.76    5094   365.6  5116.4  366.58  5197.4  367.51
  5205.8  368.38  5219.8  367.77  5272.9  369.05  5281.3   368.8    5340  370.53
#Mann= 4 ,-1 , 0
  4669.2     .12       0  4733.6     .07       0  4994.2     .05       0
  4998.2     .07       0
Bank Sta=4994.2,4998.2
XS Rating Curve= 0 ,0
Exp/Cntr=0.3,0.1

Type RM Length L Ch R = 1 ,31918   ,442,442,442
BEGIN DESCRIPTION:
EAST TINSLEY CREEK 63.0
END DESCRIPTION:
XS GIS Cut Line= 3
      2482275.04     13774425.03        2482125.       13774325.
      2481875.03     13774025.03
#Sta/Elev= 30
  4805.5  368.13  4834.1  367.35  4877.7  364.67  4885.2  364.79  4906.2  363.74
  4949.8  364.38  4963.3  361.03  4972.3  360.43  4978.3  358.95  4982.8  358.39
    4993  357.96  5007.3  359.02  5028.1  358.47  5040.5  357.24  5040.7  356.74
  5044.2  356.74  5044.5  357.24  5050.3  358.72  5056.8  358.81  5063.9  359.96
  5085.4  361.17    5114  361.75  5128.4  361.47  5198.7   364.2  5298.2  366.31
    5334  367.96  5348.4  368.11  5362.7  368.92  5369.2  369.88  5376.3  369.95
#Mann= 3 ,-1 , 0
  4805.5     .07       0  5040.5     .05       0  5044.5     .07       0
Bank Sta=5040.5,5044.5
XS Rating Curve= 0 ,0
Exp/Cntr=0.3,0.1

Type RM Length L Ch R = 1 ,31476   ,443,443,443
BEGIN DESCRIPTION:
EAST TINSLEY CREEK 62.0
END DESCRIPTION:
XS GIS Cut Line= 3
        2482525.     13774324.99        2482325.       13774025.
      2482174.99     13773874.99
#Sta/Elev= 30
  4634.4  373.14  4641.9  372.57  4662.9  371.84    4678   370.5    4720  368.51
  4756.1  367.53  4771.1   366.6  4792.1  366.14  4858.2  362.95  4879.3  363.43
  4915.3  361.41  4922.8  360.72  4936.4  358.58  4958.9  357.57  4972.4     358
  4981.4  357.68  4998.5  357.97  5009.1   356.6  5021.2  355.81  5021.5  355.31
    5025  355.31  5025.2  355.81  5037.4  357.88  5051.5  359.71  5065.7  360.35
  5093.9  362.59  5122.2  363.22  5150.5  365.73  5171.7  366.29  5207.1  367.88
#Mann= 3 ,-1 , 0
  4634.4     .07       0  5021.2     .05       0  5025.2     .07       0
Bank Sta=5021.2,5025.2
XS Rating Curve= 0 ,0
Exp/Cntr=0.3,0.1

Type RM Length L Ch R = 1 ,31033   ,409,409,409
BEGIN DESCRIPTION:
EAST TINSLEY CREEK 61.0
END DESCRIPTION:
XS GIS Cut Line= 3
      2482674.99     13773974.97        2482575.       13773725.
      2482324.98     13773624.99
#Sta/Elev= 30
  4734.9  364.73  4756.4  363.89  4773.9  362.39  4779.3  362.91  4788.7  362.54
  4842.6  359.19    4852  359.44  4864.1  358.29  4905.8  356.36  4982.6  355.68
  4994.7  354.87  5001.4  353.18  5011.5  353.11  5011.8  352.61  5015.3  352.61
  5015.5  353.11  5018.9  354.06  5036.4  356.29  5079.5  358.25  5090.3  357.93
  5126.6  359.57  5133.4  361.21  5144.1  361.35  5175.1  364.13  5180.5  363.09
  5187.2  364.06  5210.1  364.56    5229  366.77  5258.6  368.56  5273.4  368.81
#Mann= 3 ,-1 , 0
  4734.9     .07       0  5011.5     .05       0  5015.5     .07       0
Bank Sta=5011.5,5015.5
XS Rating Curve= 0 ,0
Exp/Cntr=0.3,0.1

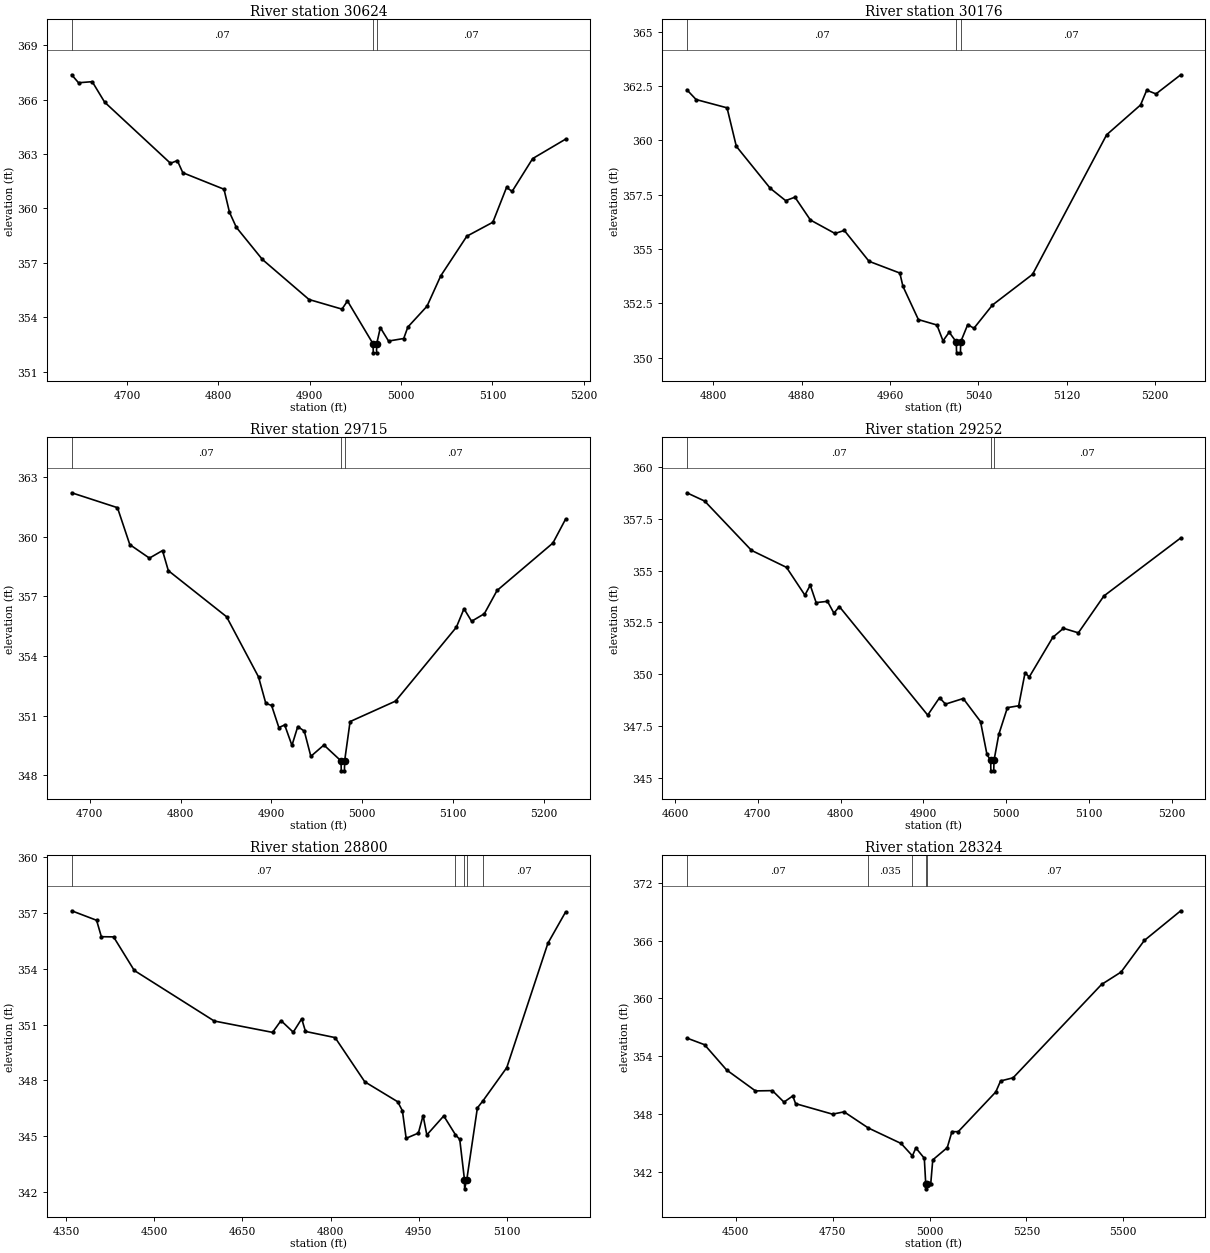
Type RM Length L Ch R = 1 ,30624   ,448,448,448
BEGIN DESCRIPTION:
EAST TINSLEY CREEK 60.0
END DESCRIPTION:
XS GIS Cut Line= 3
      2483025.01     13773825.01        2482825.       13773525.
      2482725.02     13773375.04
#Sta/Elev= 30
  4639.3  367.37  4646.8  366.93  4661.8  366.99  4675.4  365.86  4747.5  362.49
    4755  362.64    4761  361.97  4806.1  361.06  4812.1  359.79  4819.6  358.96
  4848.1  357.19  4899.2  354.98  4935.3  354.45  4941.3   354.9  4969.3  352.54
  4969.6  352.04  4973.1  352.04  4973.3  352.54  4977.3  353.43  4986.3  352.69
  5002.9  352.83  5007.4  353.46  5028.4  354.61  5043.4  356.28    5072  358.47
  5100.5  359.24  5115.5  361.16  5121.6  360.94  5144.1  362.75  5180.1  363.82
#Mann= 3 ,-1 , 0
  4639.3     .07       0  4969.3     .05       0  4973.3     .07       0
Bank Sta=4969.3,4973.3
XS Rating Curve= 0 ,0
Exp/Cntr=0.3,0.1

Type RM Length L Ch R = 1 ,30176   ,461,461,461
BEGIN DESCRIPTION:
EAST TINSLEY CREEK 59.0
END DESCRIPTION:
XS GIS Cut Line= 3
      2483275.04     13773425.02        2483075.       13773325.
      2482874.97     13773224.98
#Sta/Elev= 30
  4775.9  362.33  4784.3  361.88  4812.3   361.5  4820.7  359.73  4851.4   357.8
  4865.4  357.23  4873.8  357.39  4887.8  356.34  4910.1  355.72  4918.5  355.86
  4940.9  354.44  4968.8   353.9  4971.6  353.29  4985.6  351.76  5002.4  351.51
  5007.9  350.78  5013.5  351.18  5019.9  350.73  5020.2  350.23  5023.7  350.23
  5023.9  350.73  5030.3  351.53  5035.9  351.36  5052.7  352.43    5089  353.84
  5156.1  360.26  5186.8  361.63  5192.4  362.31  5200.8  362.14  5223.2  363.02
#Mann= 3 ,-1 , 0
  4775.9     .07       0  5019.9     .05       0  5023.9     .07       0
Bank Sta=5019.9,5023.9
XS Rating Curve= 0 ,0
Exp/Cntr=0.3,0.1

Type RM Length L Ch R = 1 ,29715   ,463,463,463
BEGIN DESCRIPTION:
EAST TINSLEY CREEK 58.0
END DESCRIPTION:
XS GIS Cut Line= 3
      2483524.98     13773224.98        2483325.       13772975.
      2483125.03     13772875.02
#Sta/Elev= 30
  4680.1  362.22  4730.5  361.47  4744.1  359.61  4765.7  358.93  4780.1  359.31
  4786.5   358.3  4850.6  355.98  4885.8  352.95  4893.8  351.62  4900.2  351.51
  4908.2   350.4  4914.6  350.53  4922.6   349.5    4929  350.45  4936.2  350.22
  4943.4  348.95  4957.8  349.52  4976.6  348.72  4976.9  348.22  4980.4  348.22
  4980.6  348.72  4986.6   350.7  5036.6  351.73  5103.6  355.45    5112  356.38
  5120.4  355.75  5134.4  356.13  5148.4   357.3  5209.9  359.69  5223.8  360.89
#Mann= 3 ,-1 , 0
  4680.1     .07       0  4976.6     .05       0  4980.6     .07       0
Bank Sta=4976.6,4980.6
XS Rating Curve= 0 ,0
Exp/Cntr=0.3,0.1

Type RM Length L Ch R = 1 ,29252   ,452,452,452
BEGIN DESCRIPTION:
EAST TINSLEY CREEK 57.0
END DESCRIPTION:
XS GIS Cut Line= 3
      2483825.03     13772825.03        2483525.       13772575.
      2483325.01       13772625.
#Sta/Elev= 30
  4614.3  358.76  4635.8  358.36  4692.4  355.98  4734.7  355.16  4756.9  353.82
  4763.4   354.3  4770.5  353.46  4784.2  353.52    4792  352.95  4798.5  353.27
  4905.3  348.03  4919.6  348.87  4926.8  348.56  4948.2  348.83  4969.1  347.72
  4976.9  346.13  4981.4  345.84  4981.6  345.34  4985.1  345.34  4985.4  345.84
  4991.2   347.1  5001.6  348.39  5015.2  348.48  5022.9  350.07    5028  349.87
  5056.4  351.78  5069.3  352.22  5087.3     352  5118.2  353.78    5211  356.58
#Mann= 3 ,-1 , 0
  4614.3     .07       0  4981.4     .05       0  4985.4     .07       0
Bank Sta=4981.4,4985.4
XS Rating Curve= 0 ,0
Exp/Cntr=0.3,0.1

Type RM Length L Ch R = 1 ,28800   ,476,476,476
BEGIN DESCRIPTION:
EAST TINSLEY CREEK 56.0
END DESCRIPTION:
XS GIS Cut Line= 3
      2483925.02     13772625.02        2483425.       13772225.
      2483225.04       13772225.
#Sta/Elev= 30
  4359.5   357.1  4401.9  356.59    4410  355.71  4430.8   355.7    4466   353.9
    4602  351.19  4701.3  350.58  4715.7  351.21  4736.5  350.59  4750.9  351.31
  4757.3  350.63  4807.7   350.3  4858.2  347.93  4914.2  346.86  4922.2  346.38
  4928.6   344.9  4949.4  345.18  4957.4  346.12  4963.8  345.08  4992.6   346.1
  5012.5  345.09  5019.8  344.84  5027.8  342.69  5028.1  342.19  5031.8  342.69
  5049.8  346.53  5059.3  346.91  5099.8  348.69  5169.8  355.36  5199.8  357.03
#Mann= 5 ,-1 , 0
  4359.5     .07       0  5012.5     .12       0  5027.8     .05       0
  5031.8     .12       0  5059.3     .07       0
Bank Sta=5027.8,5031.8
XS Rating Curve= 0 ,0
Exp/Cntr=0.3,0.1

Type RM Length L Ch R = 1 ,28324   ,464,464,464
BEGIN DESCRIPTION:
EAST TINSLEY CREEK 55.0
END DESCRIPTION:
XS GIS Cut Line= 3
      2484025.02     13772475.04        2483725.       13771925.
       2483155.3     13771616.31
#Sta/Elev= 30
  4373.7   355.9  4419.3  355.21  4476.3  352.59  4550.8  350.42  4594.4  350.45
  4624.3  349.26  4647.1   349.9  4654.3   349.1  4749.6  348.01  4779.5  348.25
  4841.9  346.58  4926.7  344.97  4955.8  343.69  4964.7  344.51  4986.5  343.44
  4990.2  340.77  4990.4  340.27  4994.2  340.77  5003.1  340.79  5008.3  343.27
  5045.7  344.54  5057.8   346.2  5073.9  346.19  5170.9  350.31  5183.3  351.45
  5215.7  351.78  5443.8  361.45  5494.3  362.74  5554.2  366.01  5648.2  369.09
#Mann= 5 ,-1 , 0
  4373.7     .07       0  4841.9    .035       0  4955.8     .07       0
  4990.2     .05       0  4994.2     .07       0
Bank Sta=4990.2,4994.2
XS Rating Curve= 0 ,0
Exp/Cntr=0.3,0.1

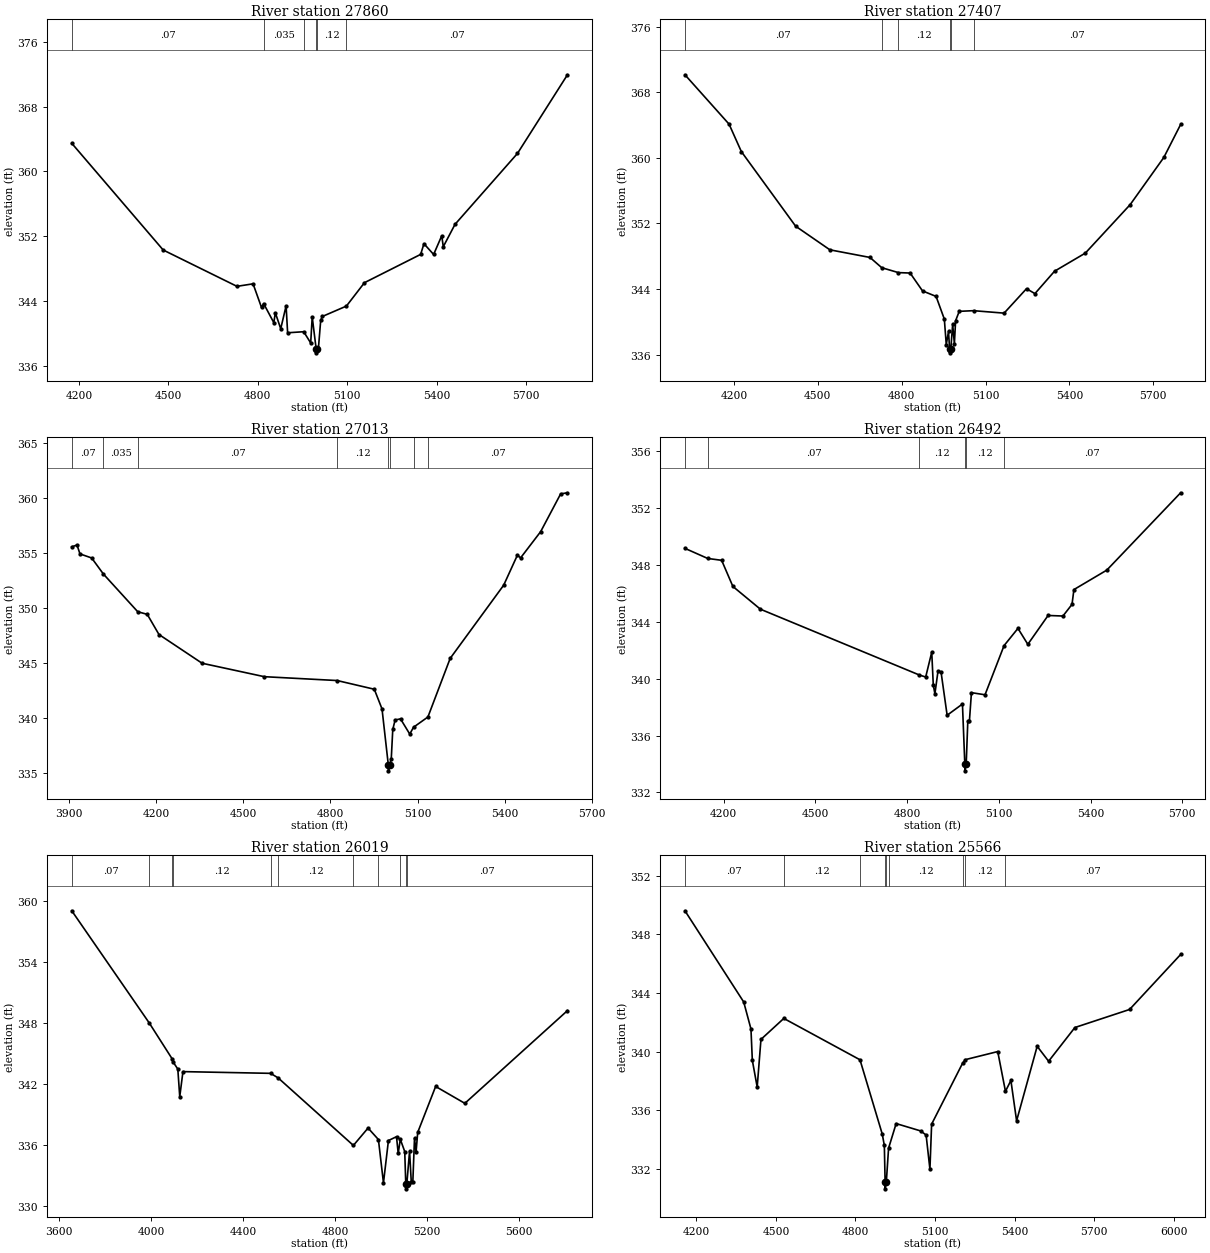
Type RM Length L Ch R = 1 ,27860   ,453,453,453
BEGIN DESCRIPTION:
EAST TINSLEY CREEK 54.0
END DESCRIPTION:
XS GIS Cut Line= 3
      2484825.02     13771925.01        2484025.       13771725.
        2483225.       13771475.
#Sta/Elev= 30
  4175.7  363.48  4482.4  350.29  4729.8   345.8  4783.9  346.11  4812.2  343.19
  4819.3  343.67  4853.5  341.31  4858.6  342.53  4876.7  340.56  4894.7  343.39
  4899.8  340.06  4953.8  340.19  4977.2   338.8  4982.3  342.01  4995.5  338.08
  4995.8  337.58    5000  338.08    5003  338.08  5010.8  341.61  5016.6  342.08
    5097  343.36  5157.5  346.25  5346.1  349.75  5357.1  351.07  5389.6  349.74
  5416.8  352.05    5422   350.7  5461.3  353.46  5670.9  362.23  5838.5  371.95
#Mann= 6 ,-1 , 0
  4175.7     .07       0  4819.3    .035       0  4953.8     .12       0
  4995.5     .05       0    5000     .12       0    5097     .07       0
Bank Sta=4995.5,5000
XS Rating Curve= 0 ,0
Exp/Cntr=0.3,0.1

Type RM Length L Ch R = 1 ,27407   ,394,394,394
BEGIN DESCRIPTION:
EAST TINSLEY CREEK 53.0
END DESCRIPTION:
XS GIS Cut Line= 3
        2484975.       13771875.        2484175.       13771325.
      2483374.98       13771375.
#Sta/Elev= 30
  4025.1  370.13  4182.9  364.11  4226.7  360.77  4420.9  351.67  4543.3  348.79
  4686.7  347.86  4728.8  346.61  4788.5  346.01  4830.2  345.96  4874.6  343.78
  4923.1  343.11  4952.6  340.34  4959.5  337.23  4967.5  338.84  4971.3  336.73
  4971.6  336.23  4975.8  336.73  4982.4  339.71  4988.5  337.34  4992.9  340.15
  5005.9  341.29    5057  341.37  5166.3  341.07  5246.4  344.05  5276.5  343.45
  5346.6  346.18  5456.8  348.39  5617.1   354.3  5737.4  360.05  5797.5  364.07
#Mann= 6 ,-1 , 0
  4025.1     .07       0  4728.8    .035       0  4788.5     .12       0
  4971.3     .05       0  4975.8     .12       0    5057     .07       0
Bank Sta=4971.3,4975.8
XS Rating Curve= 0 ,0
Exp/Cntr=0.3,0.1

Type RM Length L Ch R = 1 ,27013   ,521,521,521
BEGIN DESCRIPTION:
X19089
END DESCRIPTION:
XS GIS Cut Line= 3
      2485003.03     13771092.69      2484061.53     13770981.93
      2483341.61     13771218.55
#Sta/Elev= 30
    3910  355.53  3928.1   355.7  3938.2  354.89  3978.5  354.52  4018.9  353.06
    4137  349.64  4169.8   349.4  4210.1  347.57  4358.5  344.96  4572.6  343.74
  4823.3  343.39  4951.1   342.6  4977.7  340.81  4999.5  335.69  4999.8  335.19
    5004  335.69  5009.5  336.28  5014.7  338.95  5022.8  339.81  5041.3  339.91
  5073.1  338.53  5086.2  339.15  5135.6  340.08  5212.2   345.4  5396.4  352.05
  5443.8  354.79  5454.3  354.52  5523.6  356.91  5592.4  360.34  5615.8  360.44
#Mann= 8 ,-1 , 0
    3910     .07       0  4018.9    .035       0    4137     .07       0
  4823.3     .12       0  4999.5     .05       0    5004     .12       0
  5086.2     .12       0  5135.6     .07       0
Bank Sta=4999.5,5004
XS Rating Curve= 0 ,0
Exp/Cntr=0.3,0.1

Type RM Length L Ch R = 1 ,26492   ,473,473,473
BEGIN DESCRIPTION:
EAST TINSLEY CREEK 52.0
END DESCRIPTION:
XS GIS Cut Line= 3
      2484801.61     13770684.88        2483875.       13770725.
      2483230.82     13770981.92
#Sta/Elev= 30
  4073.4  349.17  4147.9  348.46  4193.4  348.33  4230.2  346.49  4320.2  344.89
  4840.1  340.26  4860.7  340.12  4880.5  341.87  4885.5  339.56  4890.8  338.94
  4900.8  340.51  4910.8  340.49  4930.8  337.43  4980.9  338.22  4988.6  334.02
  4988.9  333.52  4993.2  334.02  4998.4     337  5003.6     337  5010.3  339.02
  5054.7  338.87    5117  342.33  5162.4  343.54  5194.7  342.42    5261  344.45
  5309.5  344.41  5339.2  345.23  5345.4  346.27    5453  347.64  5694.4  353.08
#Mann= 6 ,-1 , 0
  4073.4     .12       0  4147.9     .07       0  4840.1     .12       0
  4988.6     .05       0  4993.2     .12       0    5117     .07       0
Bank Sta=4988.6,4993.2
XS Rating Curve= 0 ,0
Exp/Cntr=0.3,0.1

Type RM Length L Ch R = 1 ,26019   ,453,453,453
BEGIN DESCRIPTION:
EAST TINSLEY CREEK 51.0
END DESCRIPTION:
XS GIS Cut Line= 3
      2485074.98     13769725.01        2483875.       13770325.
      2483274.97     13770875.03
#Sta/Elev= 30
  3654.3  359.08  3991.4  348.04  4089.9  344.55  4094.9  344.21  4115.5  343.51
  4123.9  340.79  4137.8  343.26    4519  343.09  4551.9  342.64    4879     336
  4942.8  337.71  4987.8  336.58  5009.8  332.32  5031.4  336.48  5066.5  336.86
  5073.9  335.22  5083.1   336.6  5102.3   335.4  5106.8  332.23  5107.1  331.73
  5111.4  332.23  5123.3  335.43  5130.7  332.41  5137.4  332.36  5144.8  336.71
  5151.6  335.36  5158.7  337.28  5236.7   341.8  5363.7  340.14  5809.9  349.26
#Mann= 11 ,-1 , 0
  3654.3     .07       0  3991.4     .12       0  4089.9     .07       0
  4094.9     .12       0    4519     .07       0  4551.9     .12       0
    4879     .07       0  4987.8     .12       0  5083.1     .07       0
  5106.8     .05       0  5111.4     .07       0
Bank Sta=5106.8,5111.4
XS Rating Curve= 0 ,0
Exp/Cntr=0.3,0.1

Type RM Length L Ch R = 1 ,25566   ,466,466,466
BEGIN DESCRIPTION:
EAST TINSLEY CREEK 50.0
END DESCRIPTION:
XS GIS Cut Line= 3
      2484725.05     13769674.99        2483925.       13769925.
      2483274.99     13770725.02
#Sta/Elev= 30
    4157  349.61  4378.6  343.39  4405.9  341.55  4411.1  339.41  4429.4  337.59
  4443.6  340.84  4529.8  342.27    4817  339.45  4900.9  334.39  4908.8  333.61
  4911.7  331.15    4912  330.65  4916.4  331.15  4924.8  333.42  4953.3   335.1
  5045.5   334.6  5066.3  334.32  5080.7  331.99  5087.1  335.06  5203.7  339.21
  5214.3  339.46  5336.4  340.01  5365.5   337.3    5386  338.04  5407.5  335.29
  5485.1  340.37  5528.2  339.35  5627.3  341.65  5833.5  342.88    6026  346.63
#Mann= 9 ,-1 , 0
    4157     .07       0  4529.8     .12       0    4817     .07       0
  4911.7     .05       0  4916.4     .07       0  4924.8     .12       0
  5203.7     .07       0  5214.3     .12       0  5365.5     .07       0
Bank Sta=4911.7,4916.4
XS Rating Curve= 0 ,0
Exp/Cntr=0.3,0.1

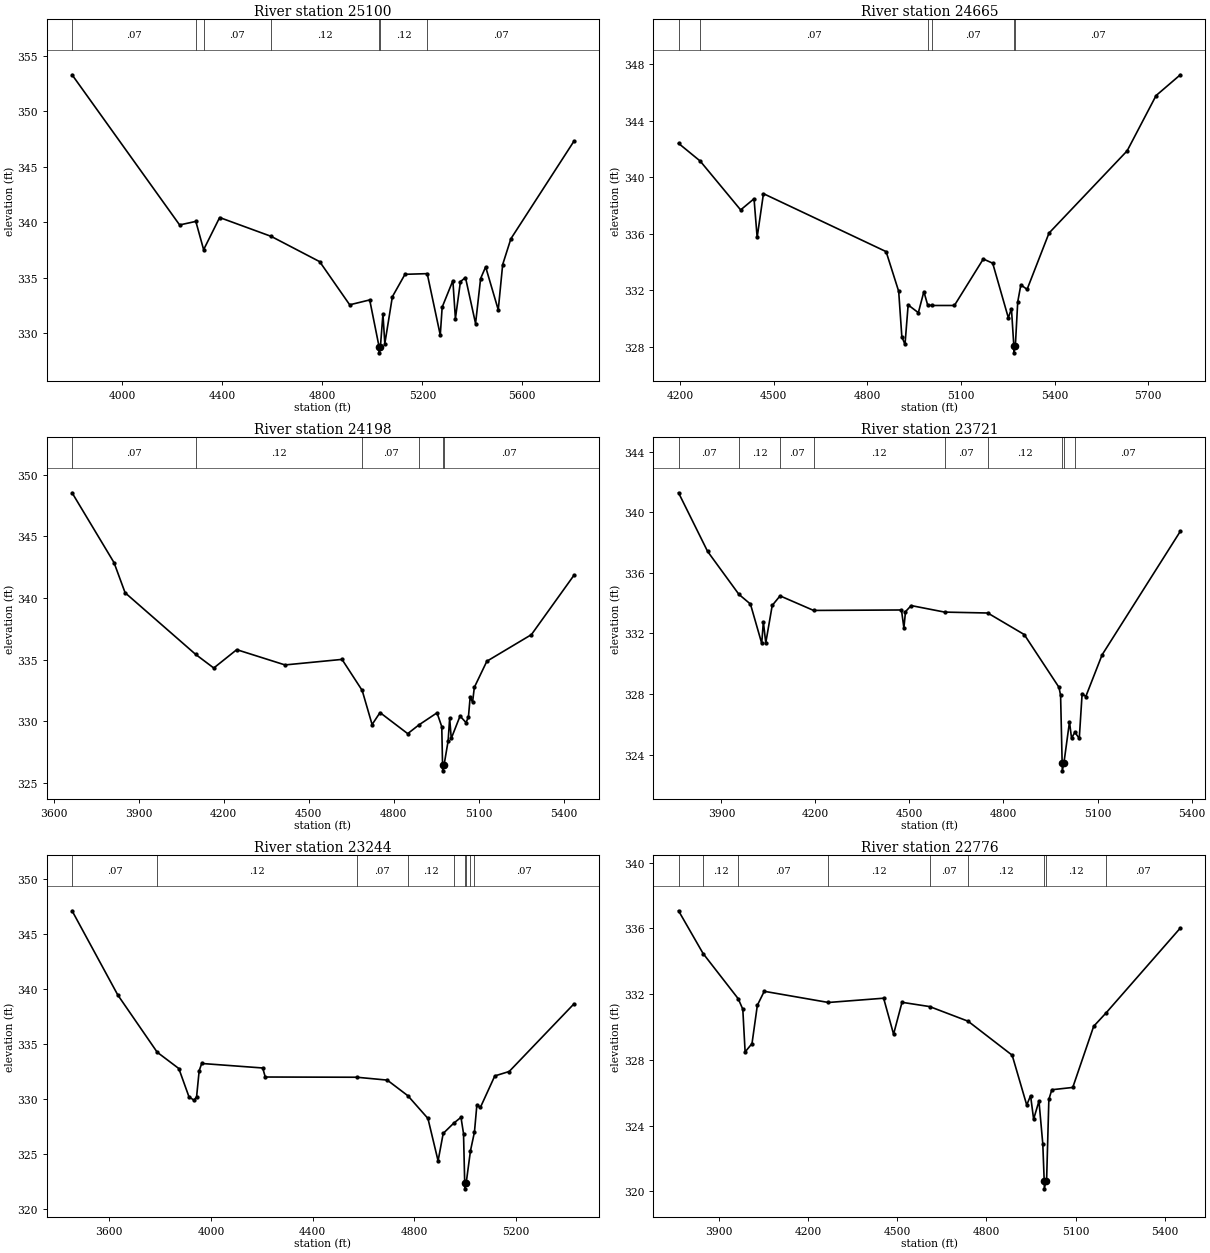
Type RM Length L Ch R = 1 ,25100   ,435,435,435
BEGIN DESCRIPTION:
EAST TINSLEY CREEK 49.0
END DESCRIPTION:
XS GIS Cut Line= 3
      2484825.02       13769625.        2483625.       13769625.
      2482825.05     13769724.99
#Sta/Elev= 30
  3799.7  353.29  4229.7  339.75  4294.5  340.07  4325.7  337.52  4389.7  340.42
  4595.8  338.72  4789.7  336.44  4909.7  332.55  4989.7  332.99  5027.6  328.72
    5028  328.22  5032.3  328.72  5042.6  331.72  5050.1  329.05  5080.3  333.28
  5130.7   335.3  5219.6  335.36  5271.8  329.82  5279.4  332.34  5322.2  334.73
  5332.3  331.31  5352.4  334.64  5372.6  335.01  5412.9  330.86  5433.1  334.92
  5453.2  335.97  5503.6   332.1  5521.3  336.18    5554   338.5  5805.9  347.29
#Mann= 7 ,-1 , 0
  3799.7     .07       0  4294.5     .12       0  4325.7     .07       0
  4595.8     .12       0  5027.6     .05       0  5032.3     .12       0
  5219.6     .07       0
Bank Sta=5027.6,5032.3
XS Rating Curve= 0 ,0
Exp/Cntr=0.3,0.1

Type RM Length L Ch R = 1 ,24665   ,467,467,467
BEGIN DESCRIPTION:
EAST TINSLEY CREEK 48.0
END DESCRIPTION:
XS GIS Cut Line= 3
      2484374.98       13769375.        2483575.       13769275.
      2482774.97       13769325.
#Sta/Elev= 30
  4194.7  342.39  4263.9  341.14  4393.7  337.68  4436.6  338.47  4446.6  335.74
  4466.8  338.83  4859.8  334.73  4900.1  331.92  4910.2  328.71  4920.3  328.16
  4930.4  330.96  4963.1  330.41  4980.8   331.9    4993  330.95  5007.4  330.92
  5078.6  330.92  5171.2  334.21  5201.3  333.91  5251.4  330.05  5261.4  330.69
    5269  328.07  5269.3  327.57  5273.9  328.07  5281.5  331.17  5291.5  332.38
  5311.5  332.06  5381.7  336.04  5632.1  341.86  5724.8  345.77  5802.5  347.24
#Mann= 6 ,-1 , 0
  4194.7     .12       0  4263.9     .07       0    4993     .12       0
  5007.4     .07       0    5269     .05       0  5273.9     .07       0
Bank Sta=5269,5273.9
XS Rating Curve= 0 ,0
Exp/Cntr=0.3,0.1

Type RM Length L Ch R = 1 ,24198   ,477,477,477
BEGIN DESCRIPTION:
EAST TINSLEY CREEK 47.0
END DESCRIPTION:
XS GIS Cut Line= 3
      2484474.99     13768375.01        2483275.       13768975.
      2482925.04     13769224.97
#Sta/Elev= 30
  3664.3  348.54  3812.4  342.87  3851.6  340.42    4101  335.41  4164.6  334.31
  4245.7   335.8  4416.2  334.56  4617.4  335.01  4688.6  332.49  4723.6  329.72
  4751.6  330.69  4849.4  328.98  4888.9  329.69  4952.8  330.67  4969.6  329.55
  4972.4  326.46  4972.9  325.96  4977.9  326.46    4992  328.38  4997.5  330.24
  5003.1  328.59  5034.2  330.41  5055.1  329.88  5063.7  330.32  5069.8  331.93
  5078.4  331.54  5084.6  332.74  5128.8  334.86  5286.1  337.02    5436  341.83
#Mann= 6 ,-1 , 0
  3664.3     .07       0    4101     .12       0  4688.6     .07       0
  4888.9     .12       0  4972.4     .05       0  4977.9     .07       0
Bank Sta=4972.4,4977.9
XS Rating Curve= 0 ,0
Exp/Cntr=0.3,0.1

Type RM Length L Ch R = 1 ,23721   ,477,477,477
BEGIN DESCRIPTION:
EAST TINSLEY CREEK 46.0
END DESCRIPTION:
XS GIS Cut Line= 3
      2484275.01       13768275.        2483075.       13768575.
      2482725.05     13768674.99
#Sta/Elev= 30
  3763.3  341.28  3856.1  337.41  3955.9  334.58  3992.7  333.94  4028.7  331.35
  4033.9  332.77  4041.6  331.38  4062.2  333.85  4087.2  334.48  4194.2  333.52
  4474.5  333.55  4482.3  332.37  4487.4  333.44  4505.5  333.84  4612.3  333.41
  4749.8  333.35  4866.2  331.93    4977  328.45  4982.2  327.92  4987.2  323.44
  4987.6  322.94  4992.7  323.44  5010.6  326.17  5017.1   325.1  5027.8  325.48
  5041.8  325.08  5050.9  328.03  5062.6  327.84  5114.6  330.59  5364.2  338.74
#Mann= 9 ,-1 , 0
  3763.3     .07       0  3955.9     .12       0  4087.2     .07       0
  4194.2     .12       0  4612.3     .07       0  4749.8     .12       0
  4987.2     .05       0  4992.7     .12       0  5027.8     .07       0
Bank Sta=4987.2,4992.7
XS Rating Curve= 0 ,0
Exp/Cntr=0.3,0.1

Type RM Length L Ch R = 1 ,23244   ,468,468,468
BEGIN DESCRIPTION:
EAST TINSLEY CREEK 45.0
END DESCRIPTION:
XS GIS Cut Line= 3
      2484424.99       13768225.        2482875.       13768175.
      2482574.97     13768475.03
#Sta/Elev= 30
  3453.4  347.09  3633.5  339.44  3788.5  334.25  3873.6  332.77  3913.6   330.2
  3933.6  329.89  3943.6  330.22  3953.7  332.57  3963.7  333.23  4203.8  332.82
  4213.8     332  4574.2  331.98    4694  331.72  4775.2   330.3  4854.1  328.24
  4894.1  324.39  4914.2  326.88  4955.2   327.8  4984.2  328.34  4994.2  326.87
  4998.9  322.35  4999.3  321.85  5004.5  322.35  5021.5   325.3  5037.2     327
  5046.6  329.43  5060.8  329.25  5117.3   332.1  5173.9   332.5  5428.5  338.63
#Mann= 9 ,-1 , 0
  3453.4     .07       0  3788.5     .12       0  4574.2     .07       0
  4775.2     .12       0  4955.2     .15       0  4998.9     .05       0
  5004.5     .15       0  5021.5     .12       0  5037.2     .07       0
Bank Sta=4998.9,5004.5
XS Rating Curve= 0 ,0
Exp/Cntr=0.3,0.1

Type RM Length L Ch R = 1 ,22776   ,475,475,475
BEGIN DESCRIPTION:
EAST TINSLEY CREEK 44.0
END DESCRIPTION:
XS GIS Cut Line= 3
      2484174.98       13768075.        2482975.       13767775.
      2482524.98       13767825.
#Sta/Elev= 30
    3763  337.07  3845.7  334.47  3963.9  331.72  3979.4  331.08  3987.2  328.48
  4010.4  328.99  4028.4  331.32  4051.6  332.17  4267.7  331.49  4453.6  331.75
  4487.1  329.56  4515.5   331.5  4608.7  331.24    4738  330.35  4886.5  328.28
  4935.5  325.25  4948.4  325.82  4958.7  324.39  4976.7  325.49  4989.6  322.88
  4994.3  320.65  4994.8  320.15  5000.4  320.65  5002.4  320.65    5010  325.59
    5020  326.18  5090.5  326.32  5160.9  330.04  5203.4  330.87  5452.7  336.02
#Mann= 9 ,-1 , 0
    3763     .07       0  3845.7     .12       0  3963.9     .07       0
  4267.7     .12       0  4608.7     .07       0    4738     .12       0
  4994.3     .05       0  5000.4     .12       0  5203.4     .07       0
Bank Sta=4994.3,5000.4
XS Rating Curve= 0 ,0
Exp/Cntr=0.3,0.1

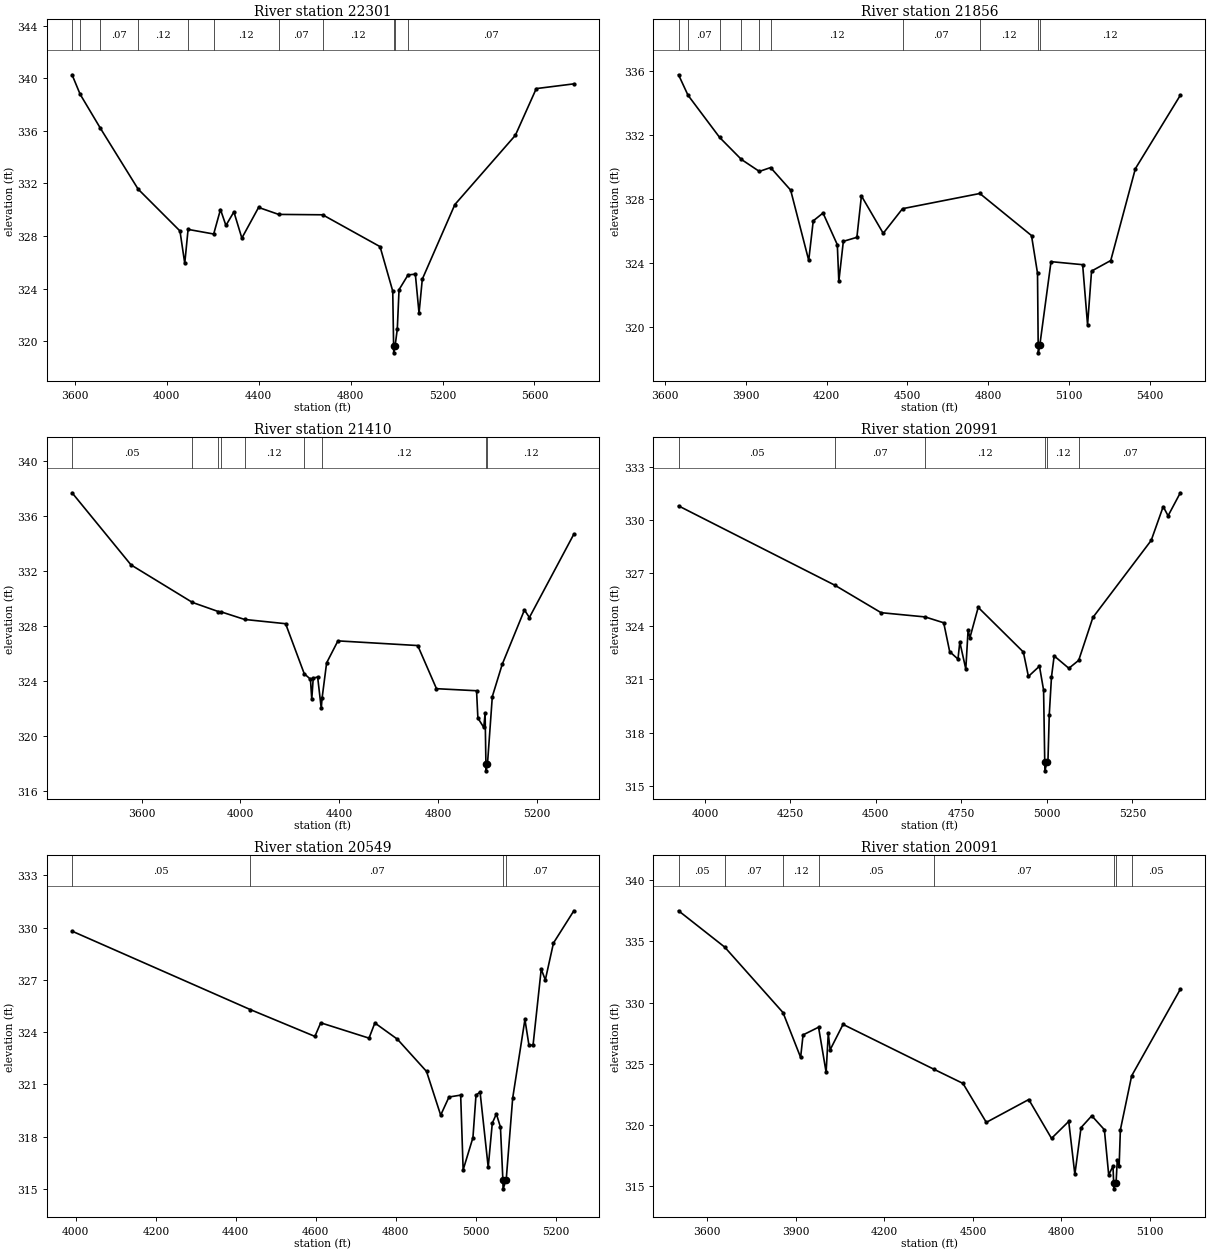
Type RM Length L Ch R = 1 ,22301   ,445,445,445
BEGIN DESCRIPTION:
EAST TINSLEY CREEK 43.0
END DESCRIPTION:
XS GIS Cut Line= 3
      2484288.08      13767744.6        2482925.       13767375.
      2482163.47     13767492.86
#Sta/Elev= 30
  3588.5  340.26  3623.6  338.78  3710.9  336.22  3875.9  331.57  4057.9  328.39
  4078.7  325.93  4093.2  328.51  4204.6  328.16  4234.1  330.02  4257.8  328.81
  4292.5  329.84  4327.1  327.85  4399.9  330.18  4487.1  329.65  4678.6  329.62
  4928.3   327.2  4983.5  323.82  4987.3  319.63  4987.8  319.13  4993.5  319.63
  5003.3  320.93  5010.9  323.93    5050  325.05  5081.8  325.11  5097.9  322.14
  5112.1  324.73  5253.8   330.4  5516.9  335.66  5607.9  339.21  5771.4  339.57
#Mann= 11 ,-1 , 0
  3588.5     .07       0  3623.6     .05       0  3710.9     .07       0
  3875.9     .12       0  4093.2     .07       0  4204.6     .12       0
  4487.1     .07       0  4678.6     .12       0  4987.3     .05       0
  4993.5     .12       0    5050     .07       0
Bank Sta=4987.3,4993.5
XS Rating Curve= 0 ,0
Exp/Cntr=0.3,0.1

Type RM Length L Ch R = 1 ,21856   ,446,446,446
BEGIN DESCRIPTION:
EAST TINSLEY CREEK 42.0
END DESCRIPTION:
XS GIS Cut Line= 3
      2484174.96     13767574.98        2482975.       13766975.
      2482475.01       13767125.
#Sta/Elev= 30
  3650.4  335.77  3685.6  334.49  3803.2  331.85  3883.7  330.48  3950.5  329.73
  3992.3  329.97  4066.8  328.56  4133.9  324.17  4150.7  326.64    4187  327.13
  4240.1  325.15  4245.7  322.86  4262.5  325.36  4312.8  325.61  4329.6   328.2
  4410.6  325.86  4482.3   327.4  4769.4  328.35  4961.3  325.72  4983.6  323.37
  4986.1  318.89  4986.6  318.39  4992.3  318.89  5033.8  324.09  5151.2   323.9
  5169.5  320.14  5184.3   323.5  5255.6  324.16    5347   329.9    5514  334.49
#Mann= 10 ,-1 , 0
  3650.4     .05       0  3685.6     .07       0  3803.2     .05       0
  3883.7     .07       0  3950.5     .05       0  3992.3     .12       0
  4482.3     .07       0  4769.4     .12       0  4986.1     .05       0
  4992.3     .12       0
Bank Sta=4986.1,4992.3
XS Rating Curve= 0 ,0
Exp/Cntr=0.3,0.1

Type RM Length L Ch R = 1 ,21410   ,419,419,419
BEGIN DESCRIPTION:
EAST TINSLEY CREEK 41.0
END DESCRIPTION:
XS GIS Cut Line= 3
      2484325.02     13767375.01        2482775.       13766725.
      2482424.99       13766725.
#Sta/Elev= 30
  3318.7  337.68  3557.3  332.43  3805.7   329.7  3911.3  329.03  3922.3  329.01
  4016.8  328.46  4182.9  328.15  4258.3  324.51  4283.4  324.11  4288.8  322.66
  4294.7  324.19  4312.6  324.27  4327.2  321.98  4330.5  322.72  4348.9   325.3
  4394.7   326.9  4717.6  326.56  4793.5  323.42  4955.7  323.27  4961.1  321.28
  4984.9   320.6  4990.3  321.63  4993.6  317.94  4994.1  317.44  4999.9  317.94
  5019.5  322.85  5059.5  325.19  5149.5  329.15  5169.5   328.6  5349.5  334.67
#Mann= 9 ,-1 , 0
  3318.7     .05       0  3805.7     .07       0  3911.3     .12       0
  3922.3     .07       0  4016.8     .12       0  4258.3     .07       0
  4330.5     .12       0  4993.6     .05       0  4999.9     .12       0
Bank Sta=4993.6,4999.9
XS Rating Curve= 0 ,0
Exp/Cntr=0.3,0.1

Type RM Length L Ch R = 1 ,20991   ,442,442,442
BEGIN DESCRIPTION:
EAST TINSLEY CREEK 40.0
END DESCRIPTION:
XS GIS Cut Line= 3
      2483974.99       13766925.        2482975.       13766525.
      2482725.02     13766225.03
#Sta/Elev= 30
  3922.9   330.8  4380.1  326.32  4515.3  324.77    4644  324.53  4698.4   324.2
  4715.9  322.57  4740.1  322.15  4745.5  323.11    4763  321.59  4769.7  323.78
  4775.1  323.36  4799.3  325.07  4931.3  322.55  4946.1  321.17  4978.4  321.75
  4990.5   320.4  4993.9  316.34  4994.4  315.84  5000.5  316.34  5003.2  316.34
  5007.1  319.01  5013.6  321.14  5021.4  322.33  5064.4  321.63  5093.2  322.08
  5134.7   324.5  5305.2  328.85  5340.3  330.76  5354.6  330.24  5390.4  331.54
#Mann= 6 ,-1 , 0
  3922.9     .05       0  4380.1     .07       0    4644     .12       0
  4993.9     .05       0  5000.5     .12       0  5093.2     .07       0
Bank Sta=4993.9,5000.5
XS Rating Curve= 0 ,0
Exp/Cntr=0.3,0.1

Type RM Length L Ch R = 1 ,20549   ,458,458,458
BEGIN DESCRIPTION:
EAST TINSLEY CREEK 39.0
END DESCRIPTION:
XS GIS Cut Line= 3
      2483875.01     13766775.01        2483075.       13766175.
      2482824.97     13766124.99
#Sta/Elev= 30
  3990.5  329.79  4436.2  325.29  4597.8  323.75  4612.4  324.53  4733.2  323.65
  4747.8  324.52  4804.1  323.59    4877  321.74  4912.4  319.23  4933.2  320.27
  4962.4  320.38  4968.6  316.09  4993.1  317.94  5000.7  320.37  5010.9  320.56
  5031.3  316.24  5041.5  318.77  5051.7   319.3  5061.9  318.54    5068   315.5
  5068.5     315  5076.2   315.5  5092.5  320.21  5123.1  324.72  5133.3  323.23
  5143.5  323.26  5163.9  327.61  5174.1  326.99  5194.5  329.11  5245.5  330.96
#Mann= 4 ,-1 , 0
  3990.5     .05       0  4436.2     .07       0    5068     .05       0
  5076.2     .07       0
Bank Sta=5068,5076.2
XS Rating Curve= 0 ,0
Exp/Cntr=0.3,0.1

Type RM Length L Ch R = 1 ,20091   ,418,418,418
BEGIN DESCRIPTION:
EAST TINSLEY CREEK 38.0
END DESCRIPTION:
XS GIS Cut Line= 3
      2484375.02     13766725.02        2483175.       13765825.
      2482975.03       13765825.
#Sta/Elev= 30
  3502.6  337.51  3658.9  334.54  3856.5  329.18  3916.2  325.51  3924.5  327.35
    3977  327.98  4002.6  324.29  4009.9  327.47  4016.2  326.13  4059.9  328.21
  4368.5  324.53  4466.2  323.38  4545.3  320.19  4689.1  322.06  4766.2  318.88
  4824.5  320.27  4845.3  315.93  4866.2  319.76  4902.6  320.73  4945.3  319.59
  4959.9   315.9  4974.5   316.6  4976.7  315.25  4977.2  314.75  4984.9  315.25
  4989.1  317.13  4995.3   316.6  4999.5  319.58  5037.7     324  5202.6  331.09
#Mann= 8 ,-1 , 0
  3502.6     .05       0  3658.9     .07       0  3856.5     .12       0
    3977     .05       0  4368.5     .07       0  4976.7     .05       0
  4984.9     .07       0  5037.7     .05       0
Bank Sta=4976.7,4984.9
XS Rating Curve= 0 ,0
Exp/Cntr=0.3,0.1