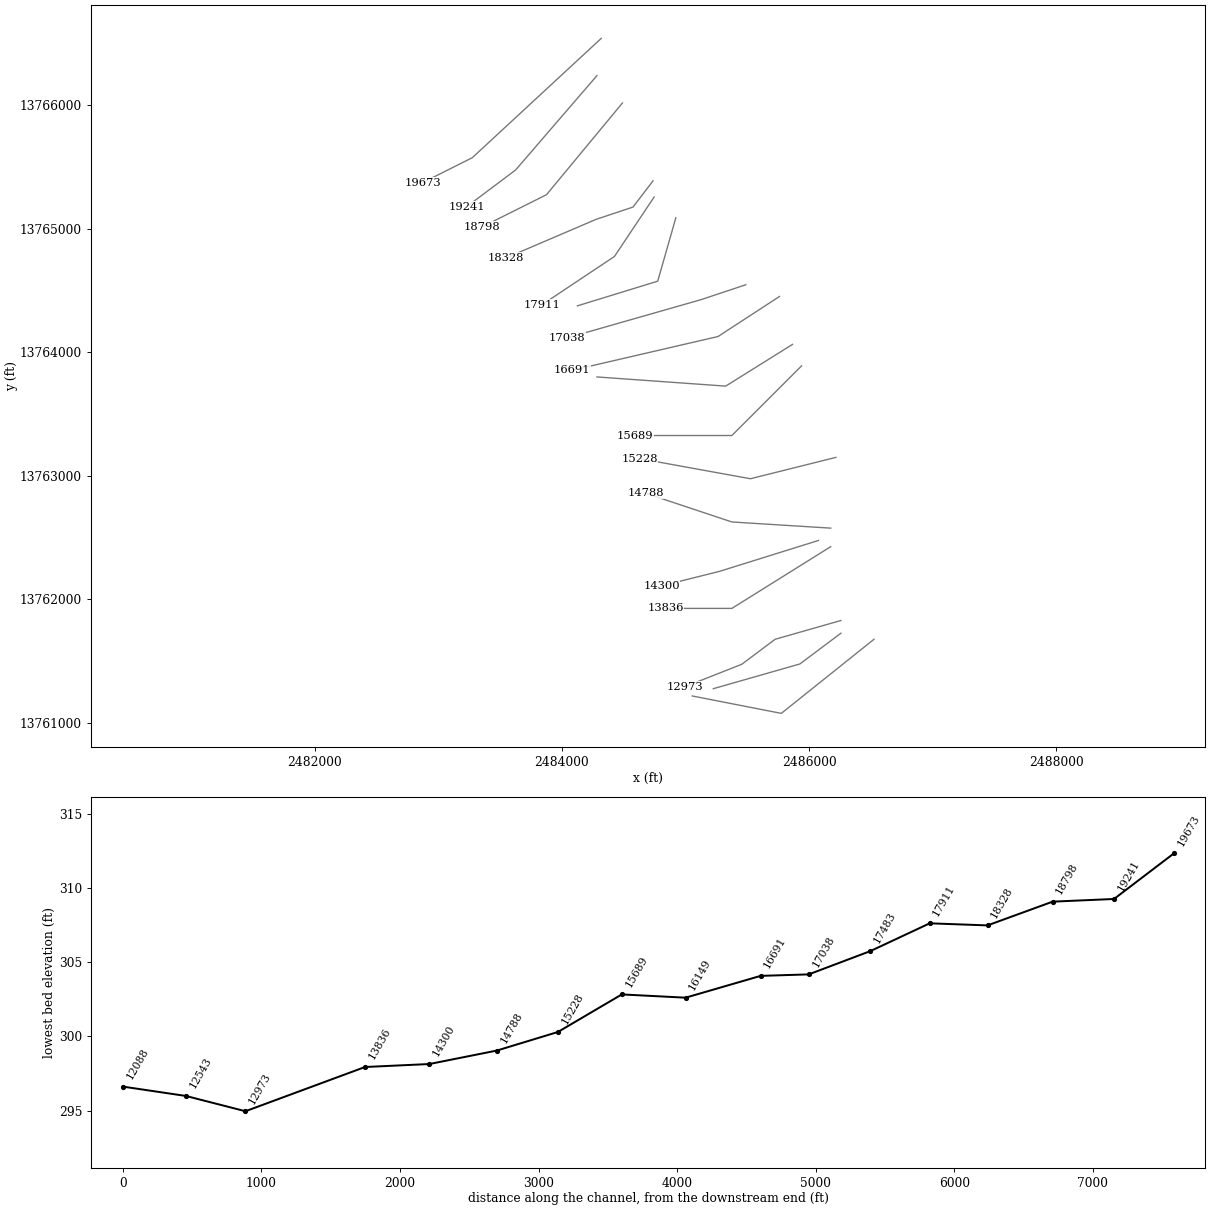
HEC-RAS study EAST TINSLEY CREEK.prj: EAST TINSLEY CREEK Base Level Engineering

--- EAST TINSLEY CREEK.g01 (geometry) --- (continued)

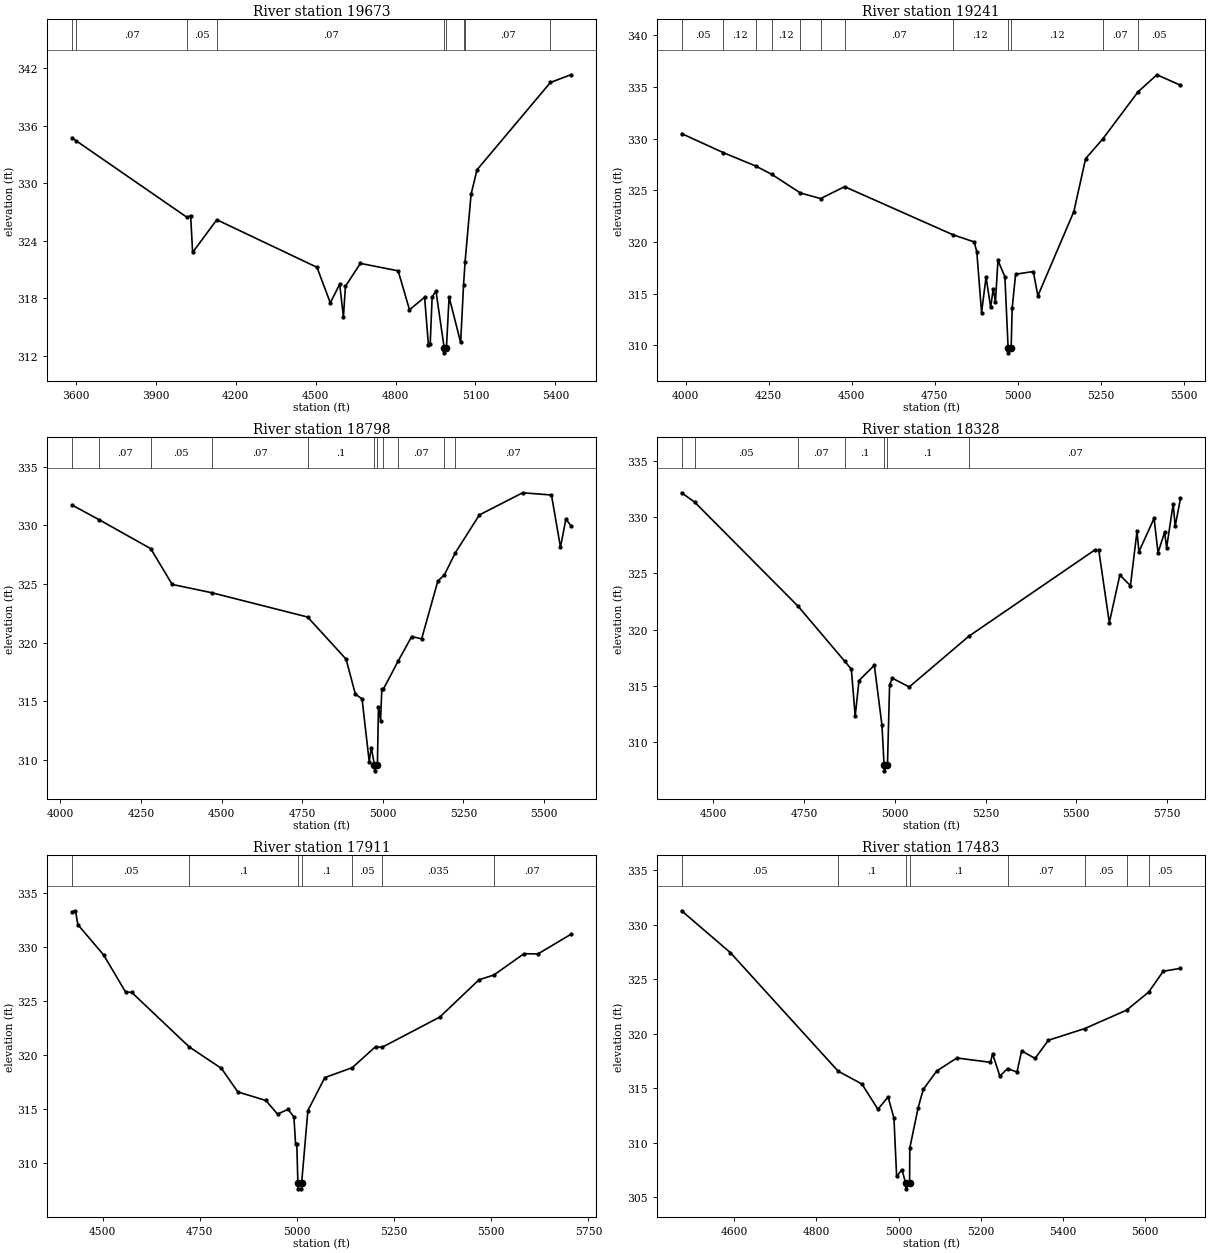
Type RM Length L Ch R = 1 ,19673   ,432,432,432
BEGIN DESCRIPTION:
EAST TINSLEY CREEK 37.0
END DESCRIPTION:
XS GIS Cut Line= 3
      2484318.29      13766541.3        2483275.       13765575.
      2482873.36     13765373.26
#Sta/Elev= 30
    3586  334.77  3601.6  334.45  4018.5  326.45  4031.4  326.65  4038.8   322.8
  4129.4  326.21  4505.4  321.25  4555.3  317.54  4590.5  319.49  4604.6  316.08
    4612  319.26  4668.2  321.66  4809.9  320.88  4852.4  316.82  4909.1  318.13
  4923.3  313.19  4930.1  313.29  4937.4  318.17  4951.6  318.79  4982.6  312.83
  4983.1  312.33  4990.9  312.83    5001  318.15  5044.3  313.41  5055.1  319.36
  5060.8  321.79  5083.4  328.87  5105.7  331.42  5381.1  340.53  5457.5  341.33
#Mann= 9 ,-1 , 0
    3586     .05       0  3601.6     .07       0  4018.5     .05       0
  4129.4     .07       0  4982.6     .05       0  4990.9     .07       0
  5055.1     .05       0  5060.8     .07       0  5381.1     .05       0
Bank Sta=4982.6,4990.9
XS Rating Curve= 0 ,0
Exp/Cntr=0.3,0.1

Type RM Length L Ch R = 1 ,19241   ,443,443,443
BEGIN DESCRIPTION:
EAST TINSLEY CREEK 36.0
END DESCRIPTION:
XS GIS Cut Line= 4
      2484283.09     13766239.26        2483625.       13765475.
        2483425.       13765325.       2483230.8     13765179.35
#Sta/Elev= 30
  3987.9  330.48  4113.9  328.63  4212.2  327.32    4260  326.52  4345.4  324.73
  4406.1  324.19  4478.5  325.34  4803.5   320.7  4868.6  319.99  4876.3  319.03
  4890.6  313.15  4904.1   316.6    4918  313.65  4925.7  315.48  4932.3  314.17
  4939.9   318.2  4960.8  316.62  4970.5  309.76    4971  309.26  4979.7  309.76
  4982.7  313.59  4993.1  316.87  5046.4  317.13    5060  314.77  5168.3  322.93
  5203.7  328.05  5254.8  329.94  5361.8  334.53  5418.3  336.17  5489.2  335.16
#Mann= 12 ,-1 , 0
  3987.9     .05       0  4113.9     .12       0  4212.2     .07       0
    4260     .12       0  4345.4     .07       0  4406.1     .12       0
  4478.5     .07       0  4803.5     .12       0  4970.5     .05       0
  4979.7     .12       0  5254.8     .07       0  5361.8     .05       0
Bank Sta=4970.5,4979.7
XS Rating Curve= 0 ,0
Exp/Cntr=0.3,0.1

Type RM Length L Ch R = 1 ,18798   ,470,470,470
BEGIN DESCRIPTION:
EAST TINSLEY CREEK 35.0
END DESCRIPTION:
XS GIS Cut Line= 4
      2484489.47     13766017.68        2483875.       13765275.
        2483675.       13765175.      2483353.92     13765014.46
#Sta/Elev= 30
  4036.2  331.74  4120.1  330.49  4280.4  328.02  4346.9  324.97  4469.9  324.26
  4766.7  322.19  4886.1   318.6  4914.8  315.62  4935.6  315.21  4957.8  309.87
  4964.3  311.06    4974  309.58  4974.5  309.08  4983.2  309.58  4986.5  314.56
    4993  313.37  4996.9  316.04  5001.6  316.04  5047.9  318.46  5089.6  320.53
  5120.3  320.33  5170.6  325.26  5190.8  325.78  5224.5  327.65  5299.2  330.89
  5433.4  332.78  5522.8  332.59  5550.7  328.14  5567.5  330.54  5582.7  329.99
#Mann= 11 ,-1 , 0
  4036.2     .05       0  4120.1     .07       0  4280.4     .05       0
  4469.9     .07       0  4766.7      .1       0    4974     .05       0
  4983.2      .1       0  5001.6     .12       0  5047.9     .07       0
  5190.8     .12       0  5224.5     .07       0
Bank Sta=4974,4983.2
XS Rating Curve= 0 ,0
Exp/Cntr=0.3,0.1

Type RM Length L Ch R = 1 ,18328   ,417,417,417
BEGIN DESCRIPTION:
EAST TINSLEY CREEK 34.0
END DESCRIPTION:
XS GIS Cut Line= 5
      2484737.14     13765387.57        2484575.       13765175.
        2484275.       13765075.        2483925.       13764925.
      2483548.21     13764763.52
#Sta/Elev= 30
  4412.8  332.14  4448.5  331.32  4733.6  322.08  4862.4  317.19  4880.4   316.5
    4891  312.32  4901.5  315.49  4943.7  316.84  4964.8  311.52  4970.6  307.98
  4971.1  307.48  4979.9  307.98  4985.8  315.13  4993.7  315.69  5039.9  314.92
  5204.2  319.42  5551.2  327.07  5562.1  327.03  5591.1  320.62  5620.1  324.85
  5649.2   323.9  5667.3  328.71  5672.7  326.92  5714.4  329.87  5725.3  326.83
  5743.5  328.65  5748.9  327.25    5767  331.15  5772.5  329.17  5787.1  331.64
#Mann= 7 ,-1 , 0
  4412.8    .035       0  4448.5     .05       0  4733.6     .07       0
  4862.4      .1       0  4970.6     .05       0  4979.9      .1       0
  5204.2     .07       0
Bank Sta=4970.6,4979.9
XS Rating Curve= 0 ,0
Exp/Cntr=0.3,0.1

Type RM Length L Ch R = 1 ,17911   ,428,428,428
BEGIN DESCRIPTION:
EAST TINSLEY CREEK 33.0
END DESCRIPTION:
XS GIS Cut Line= 5
      2484745.94     13765256.41        2484625.       13765075.
        2484425.       13764775.        2484125.       13764575.
      2483838.48     13764383.99
#Sta/Elev= 30
  4421.2  333.25  4430.4  333.33  4436.4  332.05  4502.5  329.26  4559.6   325.8
  4574.6   325.8  4722.8  320.75    4806  318.75  4848.1  316.58  4920.2  315.79
  4950.2  314.53  4977.3  314.97  4992.3  314.27  4996.8  311.72  4999.8  311.72
  5002.6  308.12  5003.1  307.62  5011.6  307.62  5012.1  308.12  5028.3  314.86
  5071.9  317.91  5142.2  318.82  5202.6  320.77  5218.3  320.69  5367.9  323.51
  5468.5  326.95  5506.8  327.39  5584.2  329.36  5620.2  329.34  5704.7  331.15
#Mann= 7 ,-1 , 0
  4421.2     .05       0  4722.8      .1       0  5002.6     .05       0
  5012.1      .1       0  5142.2     .05       0  5218.3    .035       0
  5506.8     .07       0
Bank Sta=5002.6,5012.1
XS Rating Curve= 0 ,0
Exp/Cntr=0.3,0.1

Type RM Length L Ch R = 1 ,17483   ,445,445,445
BEGIN DESCRIPTION:
EAST TINSLEY CREEK 32.0
END DESCRIPTION:
XS GIS Cut Line= 4
      2484921.57       13765088.        2484875.       13764925.
        2484775.       13764575.        2484125.       13764375.
#Sta/Elev= 30
    4472  331.29  4590.8  327.44  4852.8  316.56  4910.6  315.38  4949.6  313.06
  4974.3  314.19  4988.6  312.24  4995.1  306.89  5008.1  307.52  5017.1  306.25
  5017.6  305.75  5026.6  306.25  5027.1   309.5  5047.4  313.19  5059.8  314.88
  5092.5  316.57  5141.5  317.77  5223.3  317.37  5228.5  318.15  5246.2  316.11
  5264.9  316.79    5288  316.48  5299.1  318.42  5331.8  317.73  5364.5   319.4
  5452.7  320.47  5554.8  322.17  5608.5  323.83  5643.7  325.74  5685.6     326
#Mann= 8 ,-1 , 0
    4472     .05       0  4852.8      .1       0  5017.1     .05       0
  5026.6      .1       0  5264.9     .07       0  5452.7     .05       0
  5554.8    .035       0  5608.5     .05       0
Bank Sta=5017.1,5026.6
XS Rating Curve= 0 ,0
Exp/Cntr=0.3,0.1

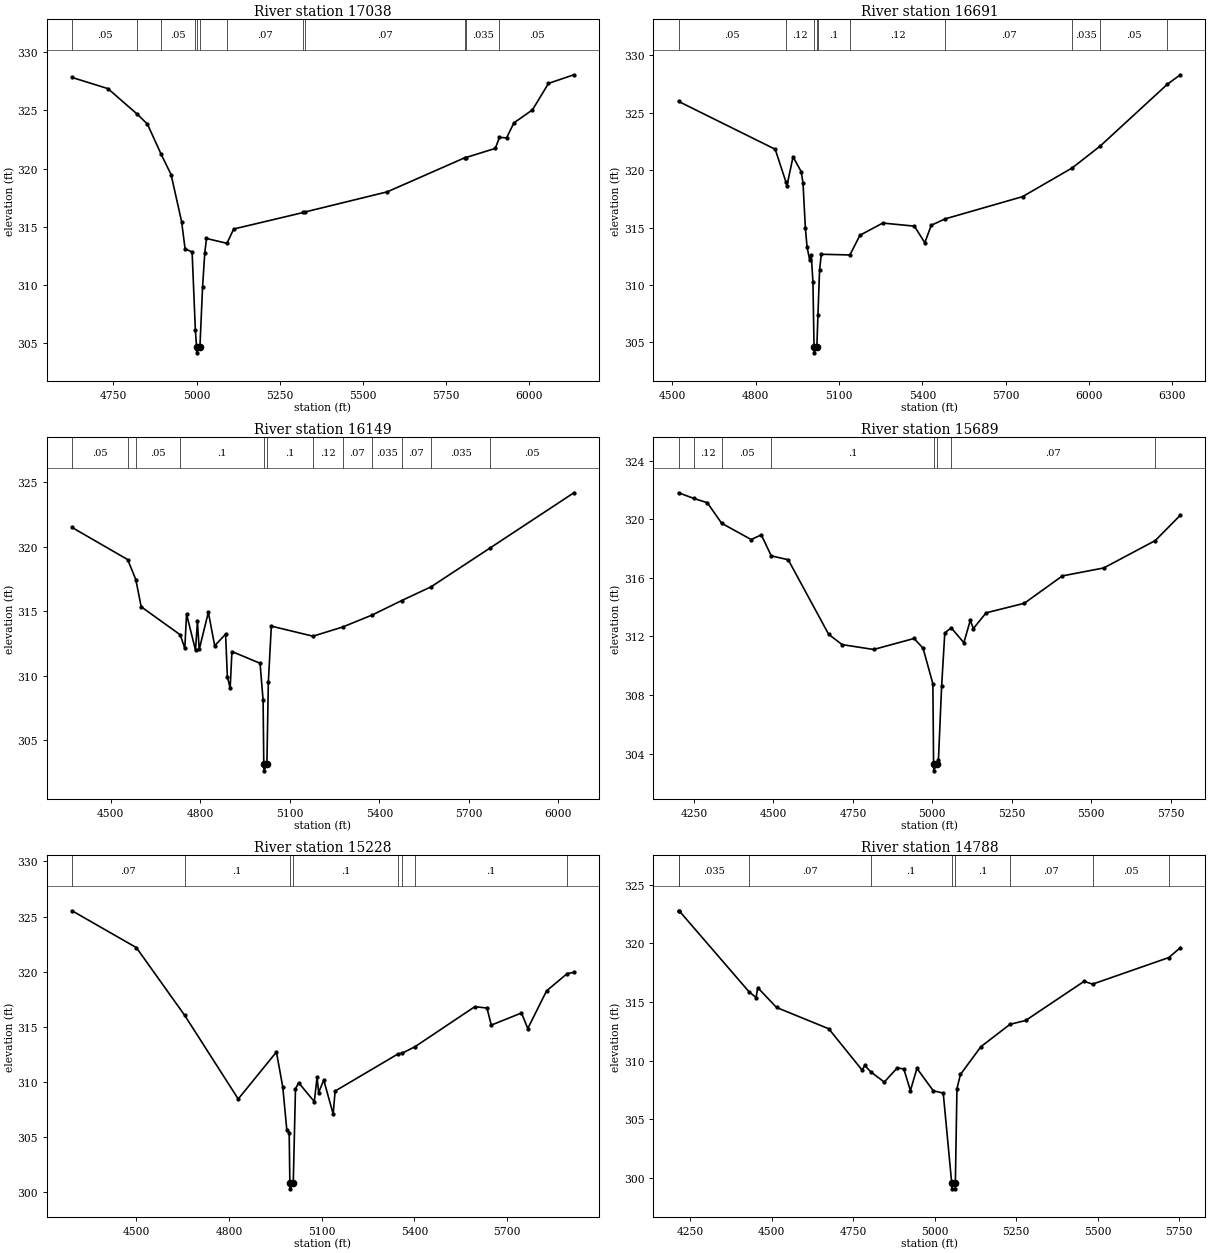
Type RM Length L Ch R = 1 ,17038   ,347,347,347
BEGIN DESCRIPTION:
EAST TINSLEY CREEK 31.0
END DESCRIPTION:
XS GIS Cut Line= 5
      2485487.38     13764545.79        2485275.       13764475.
        2485125.       13764425.        2484425.       13764225.
      2484041.63     13764115.47
#Sta/Elev= 30
  4625.8  327.82  4733.7  326.86  4821.3  324.68  4852.3  323.82  4893.6  321.23
  4923.5  319.48  4955.1  315.45  4965.6  313.11  4986.7  312.84  4996.4  306.18
  5000.1  304.68  5000.6  304.18  5010.2  304.68  5018.2  309.84  5024.7  312.73
  5029.9     314  5091.4  313.58  5111.8  314.81  5321.4  316.23  5327.5  316.28
  5573.3     318  5807.6  320.94  5809.2  320.94  5898.3  321.73  5910.8  322.68
  5932.1  322.63  5954.2  323.92  6010.1  325.04  6058.2  327.31  6134.5  328.05
#Mann= 12 ,-1 , 0
  4625.8     .05       0  4821.3     .12       0  4893.6     .05       0
  4996.4      .1       0  5000.1     .05       0  5010.2      .1       0
  5091.4     .07       0  5321.4     .12       0  5327.5     .07       0
  5807.6     .05       0  5809.2    .035       0  5910.8     .05       0
Bank Sta=5000.1,5010.2
XS Rating Curve= 0 ,0
Exp/Cntr=0.3,0.1

Type RM Length L Ch R = 1 ,16691   ,542,542,542
BEGIN DESCRIPTION:
EAST TINSLEY CREEK 30.0
END DESCRIPTION:
XS GIS Cut Line= 3
      2485760.26     13764450.95      2485263.09     13764126.71
      2484081.54     13763852.94
#Sta/Elev= 30
  4522.3  325.99  4870.3  321.82  4908.7  318.98  4912.5  318.63  4934.5  321.16
  4963.9  319.87  4970.3   318.9    4979  314.92    4985   313.3  4994.1  312.21
  5000.1  312.62  5006.1  310.27  5010.1  304.58  5010.6  304.08  5020.2  304.58
  5024.2  307.41    5030  311.29  5036.3  312.67  5139.2  312.61  5175.5  314.33
  5257.6  315.39  5371.4  315.12  5408.9  313.67  5432.1   315.2    5483  315.76
  5760.6  317.69  5939.9   320.2  6040.3   322.1  6282.3  327.49  6328.7  328.31
#Mann= 10 ,-1 , 0
  4522.3     .05       0  4908.7     .12       0  5010.1     .05       0
  5020.2     .12       0  5024.2      .1       0  5139.2     .12       0
    5483     .07       0  5939.9    .035       0  6040.3     .05       0
  6282.3     .07       0
Bank Sta=5010.1,5020.2
XS Rating Curve= 0 ,0
Exp/Cntr=0.3,0.1

Type RM Length L Ch R = 1 ,16149   ,460,460,460
BEGIN DESCRIPTION:
EAST TINSLEY CREEK 29.0
END DESCRIPTION:
XS GIS Cut Line= 5
      2485865.94     13764063.09        2485725.       13763975.
        2485325.       13763725.        2484625.       13763775.
      2484283.36      13763799.4
#Sta/Elev= 30
    4370  321.48  4556.4  318.99  4583.7  317.44  4601.7  315.33  4732.5  313.16
  4747.9  312.11  4753.8  314.76  4783.8  311.96  4790.3  314.19  4796.2  312.02
  4826.9   314.9  4848.1  312.31  4884.7  313.21  4890.6  309.92    4900  309.01
  4905.9  311.86  5000.2  310.95  5010.4  308.09  5012.7  303.11  5013.2  302.61
  5023.1  303.11    5028  309.49    5038  313.83  5177.6  313.05  5276.8  313.76
  5375.8  314.69  5474.7  315.81  5573.6  316.88  5771.4  319.89  6052.2  324.17
#Mann= 12 ,-1 , 0
    4370     .05       0  4556.4     .07       0  4583.7     .05       0
  4732.5      .1       0  5012.7     .05       0  5023.1      .1       0
  5177.6     .12       0  5276.8     .07       0  5375.8    .035       0
  5474.7     .07       0  5573.6    .035       0  5771.4     .05       0
Bank Sta=5012.7,5023.1
XS Rating Curve= 0 ,0
Exp/Cntr=0.3,0.1

Type RM Length L Ch R = 1 ,15689   ,461,461,461
BEGIN DESCRIPTION:
EAST TINSLEY CREEK 28.0
END DESCRIPTION:
XS GIS Cut Line= 5
      2485939.05     13763889.05        2485775.       13763725.
        2485375.       13763325.        2484725.       13763325.
      2484593.99       13763325.
#Sta/Elev= 30
  4201.5   321.8    4249  321.42  4292.1  321.12  4337.2  319.72    4430  318.61
  4461.8  318.93  4493.2   317.5  4546.6  317.23  4673.9  312.14  4716.3  311.44
  4815.3  311.11  4942.6  311.86  4970.9  311.19  5001.7  308.77  5003.9  303.33
  5004.4  302.83  5014.4  303.33  5019.2  303.58  5029.2   308.6  5039.2  312.24
  5059.3  312.59  5099.2  311.57  5119.2  313.09  5129.2  312.54  5169.2  313.61
  5289.2  314.26  5409.2  316.13  5539.2  316.67  5701.4  318.54  5780.2  320.27
#Mann= 8 ,-1 , 0
  4201.5     .05       0    4249     .12       0  4337.2     .05       0
  4493.2      .1       0  5003.9     .05       0  5014.4      .1       0
  5059.3     .07       0  5701.4    .035       0
Bank Sta=5003.9,5014.4
XS Rating Curve= 0 ,0
Exp/Cntr=0.3,0.1

Type RM Length L Ch R = 1 ,15228   ,440,440,440
BEGIN DESCRIPTION:
EAST TINSLEY CREEK 27.0
END DESCRIPTION:
XS GIS Cut Line= 5
      2486216.97     13763147.99        2485925.       13763075.
        2485525.       13762975.        2484975.       13763075.
      2484628.17     13763138.06
#Sta/Elev= 30
  4291.6  325.52  4499.8  322.18  4656.4  316.03  4829.6  308.45  4953.3  312.71
  4973.9  309.53  4986.8  305.68  4994.6   305.4  4996.8   300.8  4997.3   300.3
  5007.8   300.8    5015  309.37  5025.2  309.92    5076  308.21  5084.9  310.42
    5090  309.03  5106.5  310.17    5137  307.09  5143.4  309.17  5347.9  312.55
  5360.4   312.6  5402.5   313.2  5595.6  316.82    5635   316.7    5649  315.15
  5746.8  316.25  5767.2  314.84  5828.1  318.26    5895  319.83  5916.4  319.93
#Mann= 8 ,-1 , 0
  4291.6     .07       0  4656.4      .1       0  4996.8     .05       0
  5007.8      .1       0  5347.9     .07       0  5360.4     .05       0
  5402.5      .1       0    5895     .07       0
Bank Sta=4996.8,5007.8
XS Rating Curve= 0 ,0
Exp/Cntr=0.3,0.1

Type RM Length L Ch R = 1 ,14788   ,488,488,488
BEGIN DESCRIPTION:
EAST TINSLEY CREEK 26.0
END DESCRIPTION:
XS GIS Cut Line= 4
      2486174.98       13762575.        2485375.       13762625.
        2485075.       13762725.      2484674.91     13762858.36
#Sta/Elev= 30
    4214  322.78  4215.9  322.78  4429.6  315.89  4451.9  315.37    4457  316.22
  4514.6  314.53  4674.9  312.71  4777.6  309.17  4785.1  309.58    4804  309.03
  4845.2  308.16  4885.3  309.38  4905.3  309.27  4925.4  307.43  4945.4  309.33
  4995.5  307.42  5026.1  307.22  5052.1  299.55  5052.6  299.05  5062.8  299.05
  5063.3  299.55  5068.2   307.6  5078.8  308.81    5142  311.19    5231  313.09
  5279.1  313.42  5458.3  316.76  5484.3  316.52  5718.4  318.79  5753.5  319.63
#Mann= 9 ,-1 , 0
    4214     .05       0  4215.9    .035       0  4429.6     .07       0
    4804      .1       0  5052.1     .05       0  5063.3      .1       0
    5231     .07       0  5484.3     .05       0  5718.4     .07       0
Bank Sta=5052.1,5063.3
XS Rating Curve= 0 ,0
Exp/Cntr=0.3,0.1

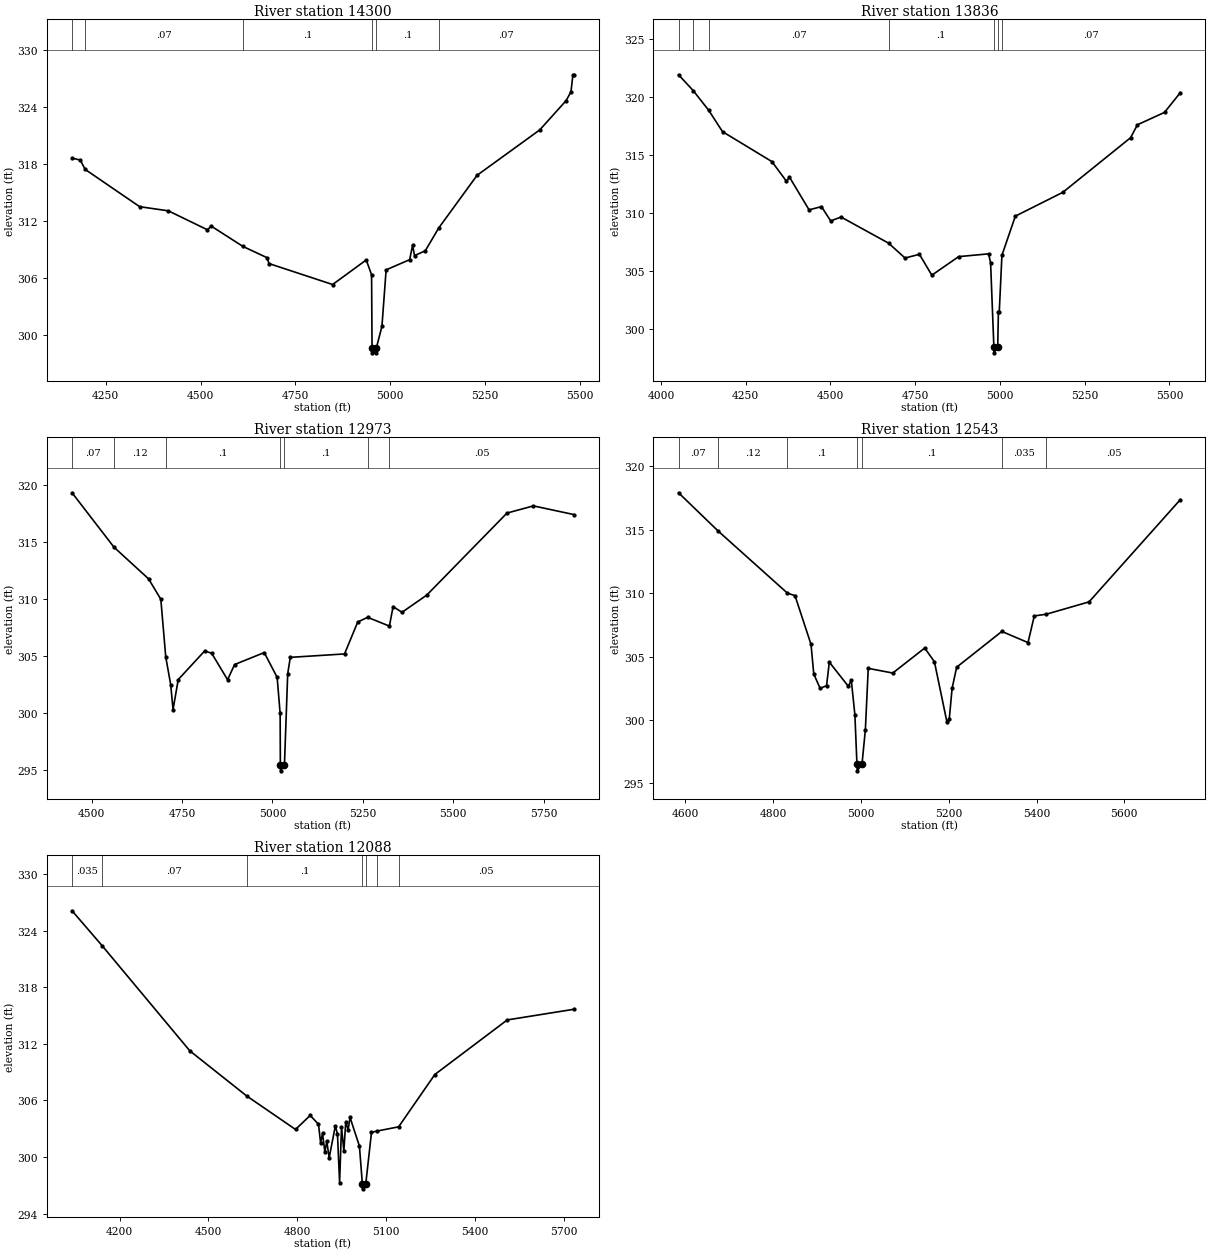
Type RM Length L Ch R = 1 ,14300   ,464,464,464
BEGIN DESCRIPTION:
EAST TINSLEY CREEK 25.0
END DESCRIPTION:
XS GIS Cut Line= 4
      2486074.98     13762474.99        2485275.       13762225.
        2485075.       13762175.      2484805.09     13762107.52
#Sta/Elev= 30
  4161.3   318.6  4182.8   318.4    4196  317.41  4339.4   313.5  4415.3  313.06
    4518  311.07    4528  311.46  4611.7  309.32  4674.6  308.15  4680.4  307.52
    4848  305.32  4936.6   307.9  4950.7  306.34  4951.9  298.64  4952.4  298.14
  4962.7  298.14  4963.2  298.64    4978  300.93    4989  306.86    5051  307.93
  5058.7  309.43  5063.9  308.36  5092.2  308.86  5127.3  311.24  5228.8   316.8
  5393.7  321.56  5463.3  324.64  5476.2  325.57  5481.3  327.36  5483.8  327.36
#Mann= 6 ,-1 , 0
  4161.3    .035       0    4196     .07       0  4611.7      .1       0
  4951.9     .05       0  4963.2      .1       0  5127.3     .07       0
Bank Sta=4951.9,4963.2
XS Rating Curve= 0 ,0
Exp/Cntr=0.3,0.1

Type RM Length L Ch R = 1 ,13836   ,863,863,863
BEGIN DESCRIPTION:
EAST TINSLEY CREEK 24.0
END DESCRIPTION:
XS GIS Cut Line= 4
        2486175.       13762425.        2485375.       13761925.
        2485075.       13761925.       2484838.4       13761925.
#Sta/Elev= 30
    4052   321.9  4095.5  320.53  4141.2  318.83  4181.7     317  4327.4  314.42
  4370.4  312.72  4379.2  313.08    4437  310.26  4473.6  310.54  4500.7  309.31
  4531.4  309.64  4671.6  307.39    4720  306.11  4762.5  306.43  4799.1  304.63
  4878.1  306.23  4966.5  306.47  4972.4   305.7  4982.1  298.44  4982.6  297.94
  4993.4  298.44  4995.4  301.42  4997.9  301.42  5005.8  306.34  5045.4  309.72
  5185.4  311.77  5385.4  316.48  5405.4  317.59  5485.4  318.66    5532  320.36
#Mann= 7 ,-1 , 0
    4052     .07       0  4095.5    .035       0  4141.2     .07       0
  4671.6      .1       0  4982.1     .05       0  4993.4      .1       0
  5005.8     .07       0
Bank Sta=4982.1,4993.4
XS Rating Curve= 0 ,0
Exp/Cntr=0.3,0.1

Type RM Length L Ch R = 1 ,12973   ,430,430,430
BEGIN DESCRIPTION:
EAST TINSLEY CREEK 23.0
END DESCRIPTION:
XS GIS Cut Line= 5
      2486257.34      13761827.1        2486075.       13761775.
        2485725.       13761675.      2485455.18     13761472.63
      2484992.94     13761290.08
#Sta/Elev= 30
  4445.8  319.34  4561.7  314.57  4657.5  311.79  4691.3     310  4704.9  304.95
  4718.6  302.52  4725.1  300.33  4739.4  302.96  4812.2  305.46  4831.7  305.28
  4875.9  302.95  4895.4  304.28  4977.3  305.33    5013  303.16  5021.3  299.99
  5021.9  295.46  5022.4  294.96  5033.2  295.46  5042.2  303.47  5049.4  304.91
  5199.4  305.21  5235.9  308.01  5263.4  308.42  5323.5  307.65  5333.7  309.36
  5358.4  308.86  5426.9  310.37  5648.7  317.56  5721.8  318.19  5833.7  317.43
#Mann= 7 ,-1 , 0
  4445.8     .07       0  4561.7     .12       0  4704.9      .1       0
  5021.9     .05       0  5033.2      .1       0  5263.4    .035       0
  5323.5     .05       0
Bank Sta=5021.9,5033.2
XS Rating Curve= 0 ,0
Exp/Cntr=0.3,0.1

Type RM Length L Ch R = 1 ,12543   ,455,455,455
BEGIN DESCRIPTION:
EAST TINSLEY CREEK 22.0
END DESCRIPTION:
XS GIS Cut Line= 4
      2486257.36     13761724.27        2486125.       13761625.
        2485925.       13761475.      2485224.96     13761274.99
#Sta/Elev= 30
  4584.2  317.91  4674.6  314.89  4832.3     310  4849.6   309.8  4886.1  305.96
  4892.4  303.62  4906.9  302.49  4921.5   302.7  4927.8  304.56  4971.5  302.64
  4977.8  303.17  4986.1   300.4  4990.8  296.49  4991.3  295.99  5002.2  296.49
    5010  299.24  5016.5  304.07  5072.4   303.7  5145.2  305.67  5167.3  304.59
    5196  299.81  5201.2  300.09  5207.6  302.49    5218  304.16    5321  306.98
  5380.6   306.1  5394.9   308.2  5422.6  308.34  5519.7  309.31  5727.7  317.37
#Mann= 7 ,-1 , 0
  4584.2     .07       0  4674.6     .12       0  4832.3      .1       0
  4990.8     .05       0  5002.2      .1       0    5321    .035       0
  5422.6     .05       0
Bank Sta=4990.8,5002.2
XS Rating Curve= 0 ,0
Exp/Cntr=0.3,0.1

Type RM Length L Ch R = 1 ,12088   ,427,427,427
BEGIN DESCRIPTION:
EAST TINSLEY CREEK 21.0
END DESCRIPTION:
XS GIS Cut Line= 3
      2486525.02     13761675.01        2485775.       13761075.
      2485054.14     13761215.95
#Sta/Elev= 30
  4039.2  326.12  4140.9  322.41    4437  311.26  4628.8  306.48    4794  302.92
  4843.6  304.41  4871.6  303.47  4878.8  301.48  4885.2   302.5  4893.2  300.52
  4899.6  301.68  4907.6   299.9  4928.5   303.3  4935.7  302.43  4942.9  297.29
  4949.3  303.16  4957.3  300.65  4963.7  303.75  4971.7  302.87  4978.1   304.2
  5009.9  301.15  5019.8  297.12  5020.3  296.62  5031.2  297.12  5050.6  302.61
  5067.9  302.74  5142.3   303.2  5264.6  308.75  5509.2  314.54  5734.2  315.67
#Mann= 7 ,-1 , 0
  4039.2    .035       0  4140.9     .07       0  4628.8      .1       0
  5019.8     .05       0  5031.2      .1       0  5067.9    .035       0
  5142.3     .05       0
Bank Sta=5019.8,5031.2
XS Rating Curve= 0 ,0
Exp/Cntr=0.3,0.1