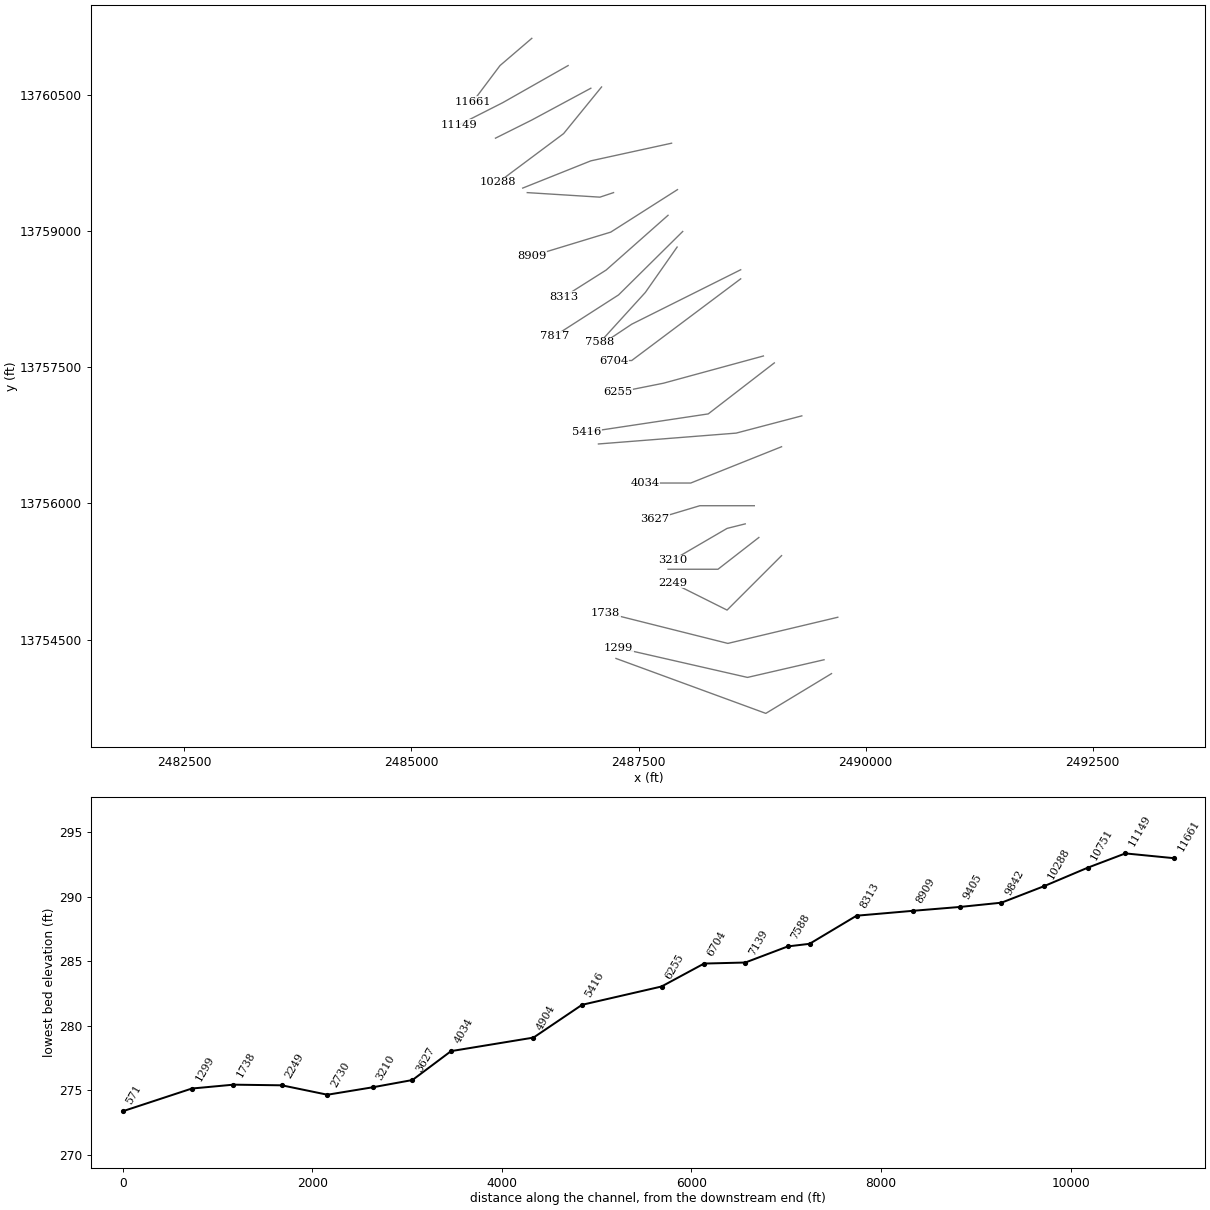
HEC-RAS study EAST TINSLEY CREEK.prj: EAST TINSLEY CREEK Base Level Engineering

--- EAST TINSLEY CREEK.g01 (geometry) --- (continued)

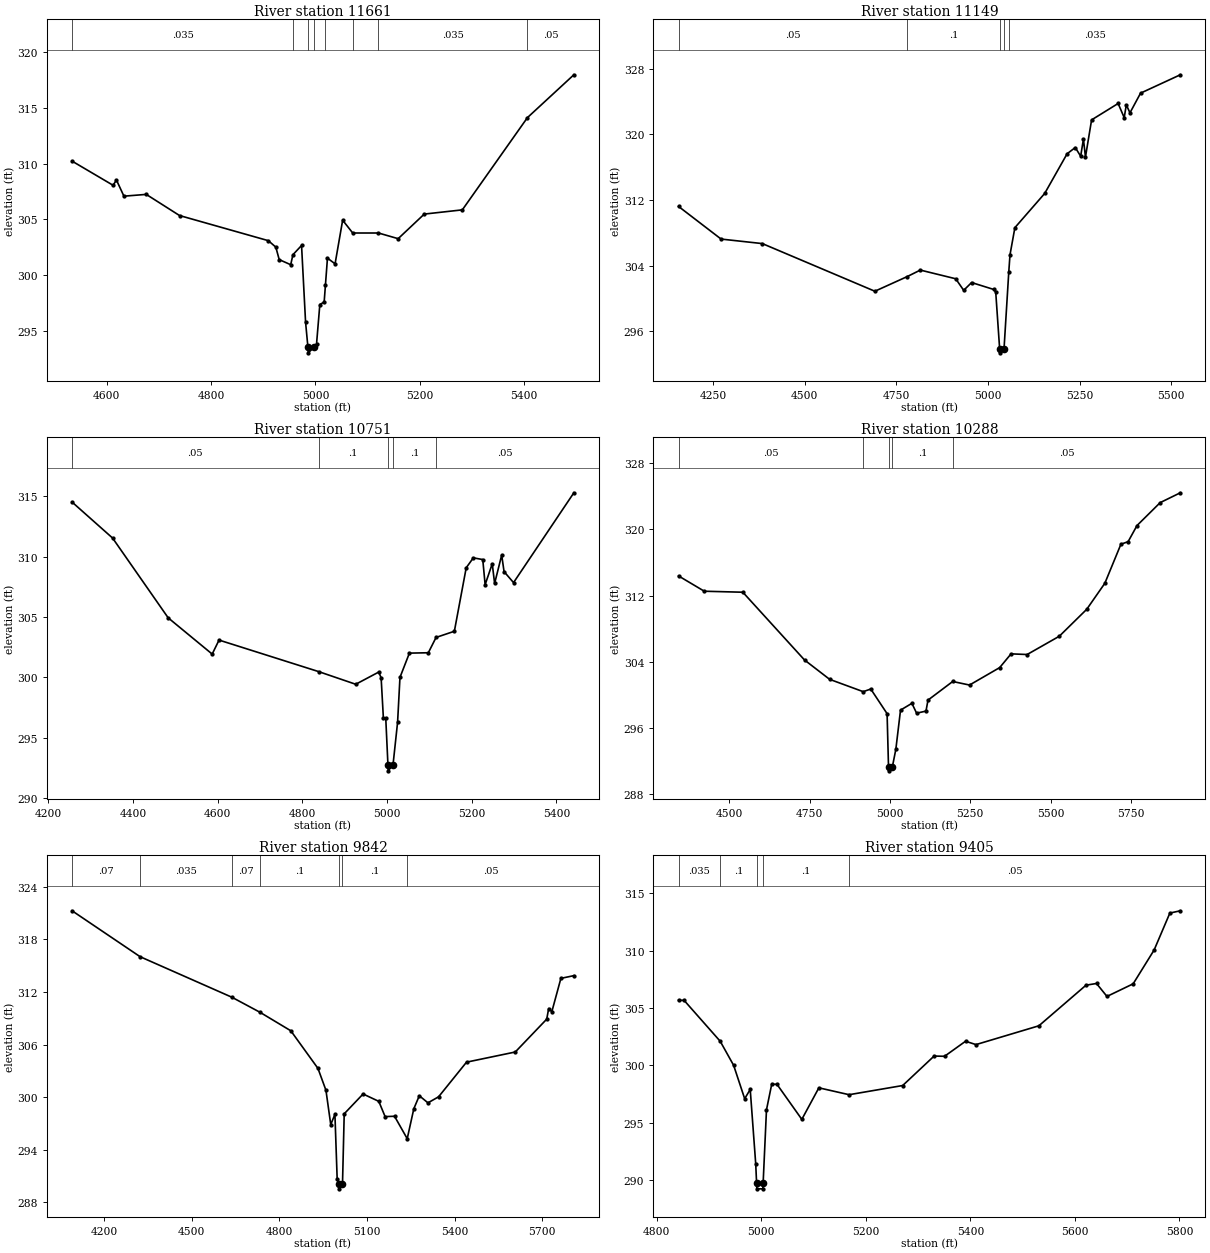
Type RM Length L Ch R = 1 ,11661   ,512,512,512
BEGIN DESCRIPTION:
EAST TINSLEY CREEK 20.0
END DESCRIPTION:
XS GIS Cut Line= 3
      2486324.98     13761124.98        2485975.       13760825.
      2485674.97     13760424.96
#Sta/Elev= 30
    4534  310.23  4612.5  308.06    4619  308.53  4633.3  307.08  4676.1  307.24
  4739.8  305.34  4909.9  303.08  4924.2   302.5  4930.7  301.38  4952.7  300.92
    4957  301.82  4973.5  302.65  4981.2  295.75  4985.7   293.5  4986.2     293
  4997.7   293.5  5002.2   293.8  5008.5  297.34  5016.8  297.57  5019.2  299.07
  5023.1  301.51  5037.7     301  5052.2  304.92  5071.5  303.77  5120.8  303.77
  5158.5  303.26  5208.5  305.47  5281.4  305.85  5406.1  314.14    5495  317.99
#Mann= 8 ,-1 , 0
    4534    .035       0    4957      .1       0  4985.7     .05       0
  4997.7      .1       0  5019.2    .035       0  5071.5      .1       0
  5120.8    .035       0  5406.1     .05       0
Bank Sta=4985.7,4997.7
XS Rating Curve= 0 ,0
Exp/Cntr=0.3,0.1

Type RM Length L Ch R = 1 ,11149   ,398,398,398
BEGIN DESCRIPTION:
EAST TINSLEY CREEK 19.0
END DESCRIPTION:
XS GIS Cut Line= 3
      2486725.02     13760825.01       2486005.2      13760416.2
       2485522.5     13760171.25
#Sta/Elev= 30
  4155.6  311.22  4271.7  307.24  4384.2  306.69  4691.3  300.88  4779.7  302.67
  4815.3  303.46  4911.9   302.4  4933.6  300.99  4955.2  301.94  5015.4   301.1
    5021   300.8  5031.7  293.87  5032.2  293.37  5043.7  293.87  5056.7  303.28
    5060  305.33  5073.3  308.63  5154.6   312.8  5215.8  317.64  5238.1   318.4
  5252.8  317.34  5260.3  319.42  5265.9  317.25  5282.6  321.77    5355  323.77
  5371.6  322.04  5377.3   323.6  5387.3  322.63  5416.2  325.03  5524.7  327.27
#Mann= 5 ,-1 , 0
  4155.6     .05       0  4779.7      .1       0  5031.7     .05       0
  5043.7      .1       0  5056.7    .035       0
Bank Sta=5031.7,5043.7
XS Rating Curve= 0 ,0
Exp/Cntr=0.3,0.1

Type RM Length L Ch R = 1 ,10751   ,463,463,463
BEGIN DESCRIPTION:
EAST TINSLEY CREEK 18.0
END DESCRIPTION:
XS GIS Cut Line= 3
      2486974.99     13760574.99        2486325.       13760225.
      2485925.04     13760025.02
#Sta/Elev= 30
  4255.7  314.52  4351.4  311.54  4482.8  304.93  4586.7  301.93  4602.9  303.09
  4838.1  300.48  4925.8  299.43  4980.1  300.44  4985.8  299.97  4991.1  296.65
  4996.7  296.65  5001.9  292.76  5002.4  292.26  5013.9  292.76  5024.7  296.29
  5030.3     300  5052.6  302.01  5097.3  302.04  5115.6  303.31  5158.8  303.82
  5186.8  309.08  5203.6   309.9  5225.9  309.76  5231.5  307.68  5248.3  309.41
  5253.9  307.78  5270.6  310.13  5276.2  308.76  5298.6  307.85  5441.1  315.29
#Mann= 5 ,-1 , 0
  4255.7     .05       0  4838.1      .1       0  5001.9     .05       0
  5013.9      .1       0  5115.6     .05       0
Bank Sta=5001.9,5013.9
XS Rating Curve= 0 ,0
Exp/Cntr=0.3,0.1

Type RM Length L Ch R = 1 ,10288   ,446,446,446
BEGIN DESCRIPTION:
EAST TINSLEY CREEK 17.0
END DESCRIPTION:
XS GIS Cut Line= 3
      2487093.12     13760589.11        2486675.       13760075.
      2485954.79     13759537.23
#Sta/Elev= 30
  4342.3  314.38  4422.5  312.53  4542.4  312.41  4734.3  304.22  4812.5  301.88
    4917  300.39  4940.5  300.71  4991.3  297.73  4995.7  291.32  4996.2  290.82
  5007.8  291.32  5018.5  293.42  5033.1  298.16  5068.5  298.98  5083.1  297.79
  5112.3  298.04  5118.6  299.37  5195.5  301.62  5247.8  301.19  5341.7   303.3
  5377.1  304.96  5427.1  304.88  5527.2  307.09  5612.6  310.35  5668.9  313.49
  5718.9  318.21  5741.3  318.52    5769  320.47  5841.1  323.24  5903.8  324.43
#Mann= 5 ,-1 , 0
  4342.3     .05       0    4917      .1       0  4995.7     .05       0
  5007.8      .1       0  5195.5     .05       0
Bank Sta=4995.7,5007.8
XS Rating Curve= 0 ,0
Exp/Cntr=0.3,0.1

Type RM Length L Ch R = 1 ,9842    ,437,437,437
BEGIN DESCRIPTION:
EAST TINSLEY CREEK 16.0
END DESCRIPTION:
XS GIS Cut Line= 3
       2487864.1     13759969.51        2486975.       13759775.
      2486225.01       13759475.
#Sta/Elev= 30
  4090.2  321.27  4323.2  316.03  4637.2  311.41  4733.6  309.69  4839.1  307.58
    4932  303.29  4959.4  300.79  4975.8  296.88  4990.1  298.05  4997.8  290.66
  5003.6  290.05  5004.1  289.55    5016  290.05  5021.9  298.11  5086.5  300.37
  5140.3  299.53  5161.9  297.79  5194.2  297.83  5237.6  295.27  5260.2  298.69
    5279  300.17  5308.6  299.36    5345  300.05  5440.6     304  5607.5  305.16
  5715.2  308.91  5721.9  310.12  5732.7  309.76  5763.7  313.56  5808.1  313.87
#Mann= 7 ,-1 , 0
  4090.2     .07       0  4323.2    .035       0  4637.2     .07       0
  4733.6      .1       0  5003.6     .05       0    5016      .1       0
  5237.6     .05       0
Bank Sta=5003.6,5016
XS Rating Curve= 0 ,0
Exp/Cntr=0.3,0.1

Type RM Length L Ch R = 1 ,9405    ,496,496,496
BEGIN DESCRIPTION:
EAST TINSLEY CREEK 15.0
END DESCRIPTION:
XS GIS Cut Line= 3
      2487225.02     13759425.01        2487075.       13759375.
        2486275.       13759425.
#Sta/Elev= 30
  4841.9  305.66  4852.5  305.66  4921.6  302.09  4947.3  299.99  4968.4  297.08
    4979  297.89  4989.5  291.41  4991.2  289.72  4991.7  289.22  5003.2  289.22
  5003.7  289.72  5010.1  296.11  5020.1  298.34  5030.1  298.34  5077.7  295.28
  5110.3  298.03  5168.1  297.43  5270.6  298.23  5330.7   300.8  5350.7  300.78
  5390.8  302.09  5410.8   301.8  5531.1  303.44  5621.2  306.98  5641.3  307.13
  5661.3     306  5711.4   307.1  5751.5  310.05  5781.6  313.27  5801.6  313.47
#Mann= 5 ,-1 , 0
  4841.9    .035       0  4921.6      .1       0  4991.2     .05       0
  5003.7      .1       0  5168.1     .05       0
Bank Sta=4991.2,5003.7
XS Rating Curve= 0 ,0
Exp/Cntr=0.3,0.1

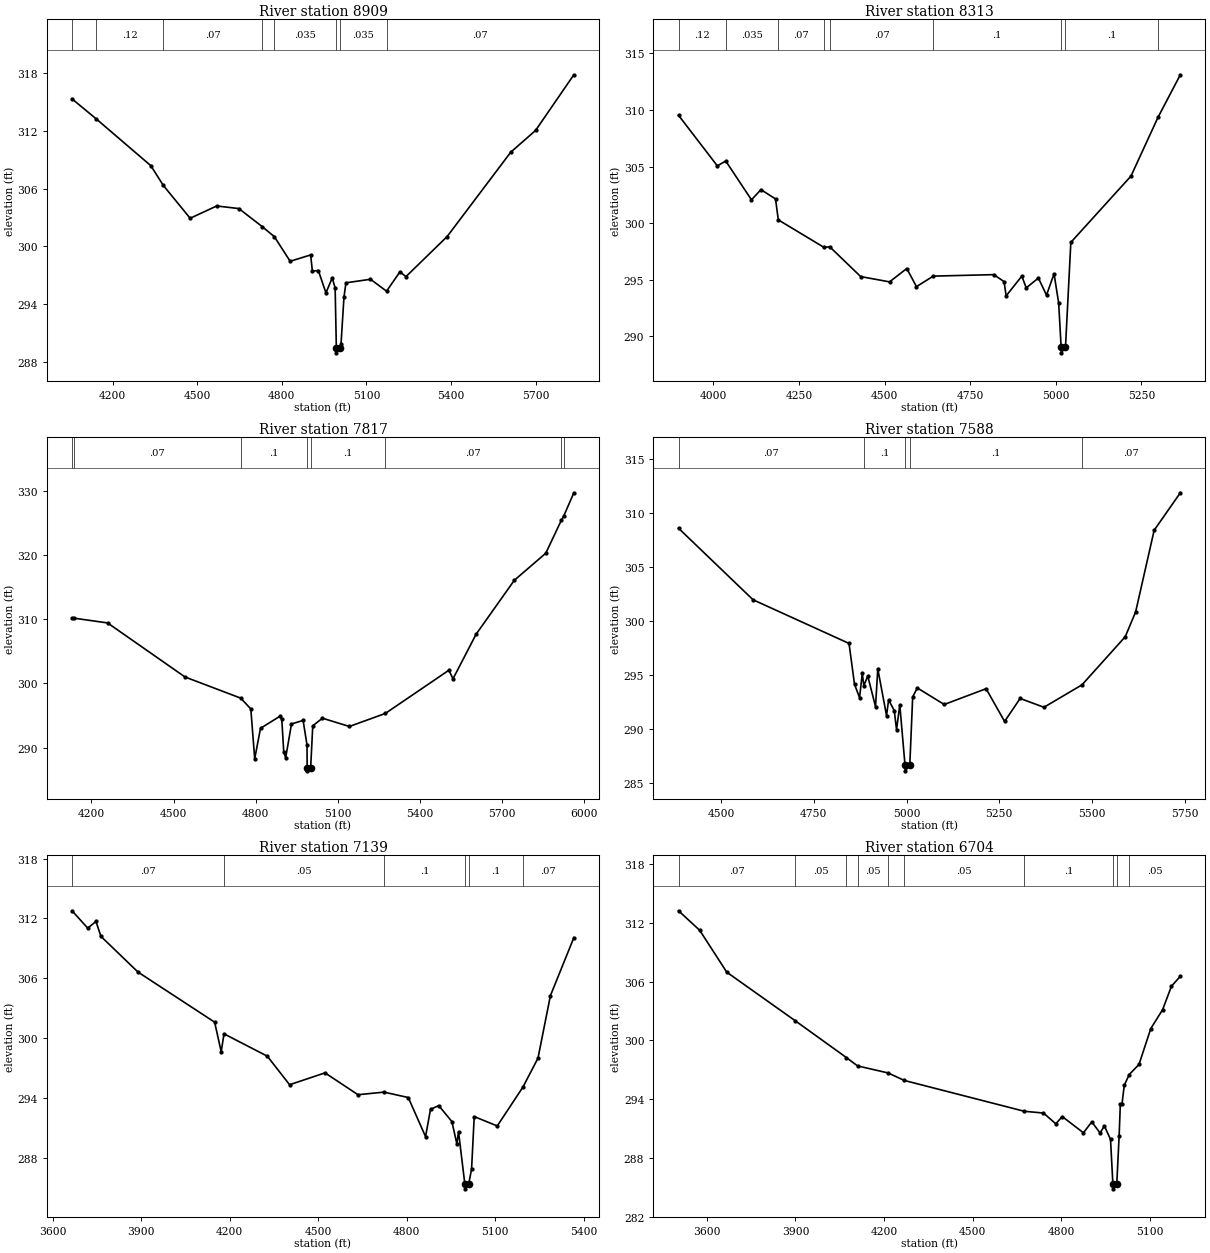
Type RM Length L Ch R = 1 ,8909    ,596,596,596
BEGIN DESCRIPTION:
EAST TINSLEY CREEK 14.0
END DESCRIPTION:
XS GIS Cut Line= 3
      2487928.87     13759457.94        2487194.     13758989.64
        2486325.       13758725.
#Sta/Elev= 30
  4056.1  315.32  4140.3  313.28  4335.4  308.38  4379.9  306.32    4475  302.91
    4569  304.19  4647.7  303.92  4730.2  302.05  4773.5     301  4829.7  298.44
  4902.4   299.1  4908.4  297.42  4929.6  297.48  4956.6  295.15  4978.7  296.71
  4989.2  295.67  4993.5  289.42    4994  288.92  5006.2  289.42  5010.1  289.86
  5020.5  294.71  5027.5   296.2  5114.6  296.57  5171.6  295.33  5219.2  297.35
  5240.2  296.84  5386.4  301.01    5612  309.78    5700  312.04  5835.9  317.83
#Mann= 8 ,-1 , 0
  4056.1     .07       0  4140.3     .12       0  4379.9     .07       0
  4730.2     .12       0  4773.5    .035       0  4993.5    .035       0
  5006.2    .035       0  5171.6     .07       0
Bank Sta=4993.5,5006.2
XS Rating Curve= 0 ,0
Exp/Cntr=0.3,0.1

Type RM Length L Ch R = 1 ,8313    ,496,496,496
BEGIN DESCRIPTION:
EAST TINSLEY CREEK 13.0
END DESCRIPTION:
XS GIS Cut Line= 3
        2487825.       13759175.      2487143.57     13758571.76
      2486675.02     13758275.01
#Sta/Elev= 30
  3898.8  309.53  4012.1  305.06  4036.6  305.49  4111.7  302.06  4139.3  302.96
  4181.9  302.14    4190  300.29  4323.3  297.86  4340.2  297.91  4430.4  295.28
  4514.8  294.81    4565  295.99  4593.3  294.39  4642.4  295.32    4819  295.45
  4849.1  294.83    4855  293.57  4900.8  295.32  4913.7  294.28  4949.2  295.15
  4972.9  293.64  4994.9  295.53  5008.4  292.94  5015.6  289.04  5016.1  288.54
  5028.3  289.04  5043.9   298.3  5219.5  304.16  5298.5  309.36  5363.5  313.11
#Mann= 9 ,-1 , 0
  3898.8     .12       0  4036.6    .035       0    4190     .07       0
  4323.3      .1       0  4340.2     .07       0  4642.4      .1       0
  5015.6     .05       0  5028.3      .1       0  5298.5     .12       0
Bank Sta=5015.6,5028.3
XS Rating Curve= 0 ,0
Exp/Cntr=0.3,0.1

Type RM Length L Ch R = 1 ,7817    ,229,229,229
BEGIN DESCRIPTION:
EAST TINSLEY CREEK 12.0
END DESCRIPTION:
XS GIS Cut Line= 3
      2487986.56     13758996.86      2487280.46     13758297.97
      2486574.37     13757844.05
#Sta/Elev= 30
  4129.1  310.21  4135.1  310.18  4258.8  309.43  4541.6     301  4745.1   297.7
    4782  296.02  4796.2  288.25  4817.4  292.99  4888.2  294.87  4895.2  294.37
  4902.3   289.3  4909.3  288.39  4930.6  293.67    4973  294.22  4987.2  290.41
  4987.8  286.86  4988.3  286.36  5000.6  286.86  5008.3  293.39  5043.7  294.57
  5142.1  293.28  5273.3  295.31  5505.4  302.05  5520.6  300.72  5605.1  307.68
  5744.5  316.08  5859.4   320.3  5916.5  325.46  5924.7  326.07    5962  329.73
#Mann= 8 ,-1 , 0
  4129.1    .035       0  4135.1     .07       0  4745.1      .1       0
  4987.8     .05       0  5000.6      .1       0  5273.3     .07       0
  5916.5     .12       0  5924.7     .07       0
Bank Sta=4987.8,5000.6
XS Rating Curve= 0 ,0
Exp/Cntr=0.3,0.1

Type RM Length L Ch R = 1 ,7588    ,449,449,449
BEGIN DESCRIPTION:
EAST TINSLEY CREEK 11.0
END DESCRIPTION:
XS GIS Cut Line= 3
        2487925.       13758825.        2487575.       13758325.
      2487075.02     13757775.02
#Sta/Elev= 30
    4385  308.61    4586  301.99  4844.9  297.95  4859.7  294.17  4873.3  292.93
  4880.7  295.18  4884.8  294.04  4895.5  294.93  4916.4   292.1  4922.5   295.6
  4946.1  291.27  4951.7  292.73    4967  291.73  4973.1  289.96  4981.8  292.27
    4996  286.66  4996.5  286.16  5008.8  286.66  5016.6     293  5029.1  293.83
  5101.8   292.3  5214.6  293.76  5264.6  290.73  5306.5  292.86  5370.7  292.04
  5473.4  294.12    5590  298.57    5618  300.86    5668  308.42  5738.6  311.89
#Mann= 5 ,-1 , 0
    4385     .07       0  4884.8      .1       0    4996     .05       0
  5008.8      .1       0  5473.4     .07       0
Bank Sta=4996,5008.8
XS Rating Curve= 0 ,0
Exp/Cntr=0.3,0.1

Type RM Length L Ch R = 1 ,7139    ,435,435,435
BEGIN DESCRIPTION:
EAST TINSLEY CREEK 10.0
END DESCRIPTION:
XS GIS Cut Line= 3
        2488625.       13758575.        2487425.       13757975.
        2487125.       13757775.
#Sta/Elev= 30
  3664.9  312.77    3718  311.03    3746   311.7  3762.7  310.21  3888.5  306.63
  4148.5  301.61  4170.8  298.65  4180.3  300.44  4327.3   298.2  4402.8  295.34
    4523  296.53  4634.8  294.34  4723.1   294.6  4805.3  294.06    4864  290.14
  4880.8  292.87  4908.7  293.25  4953.4  291.65  4970.2  289.41  4975.8  290.64
  4997.2  285.41  4997.7  284.91  5010.4  285.41  5020.1  286.88  5029.1  292.15
  5107.2  291.21  5194.2   295.1  5245.4     298  5287.5  304.26  5367.1  310.08
#Mann= 6 ,-1 , 0
  3664.9     .07       0  4180.3     .05       0  4723.1      .1       0
  4997.2     .05       0  5010.4      .1       0  5194.2     .07       0
Bank Sta=4997.2,5010.4
XS Rating Curve= 0 ,0
Exp/Cntr=0.3,0.1

Type RM Length L Ch R = 1 ,6704    ,449,449,449
BEGIN DESCRIPTION:
EAST TINSLEY CREEK 9.0
END DESCRIPTION:
XS GIS Cut Line= 3
      2488624.97     13758474.98        2487425.       13757575.
      2487224.96       13757575.
#Sta/Elev= 30
  3503.9  313.26  3575.7  311.26  3667.4  306.98  3899.5  302.01  4072.7  298.25
  4110.3   297.4  4213.7  296.68  4269.1  295.91  4675.3  292.76  4740.3  292.58
    4782  291.48  4803.9  292.22  4875.7  290.56  4903.9  291.68    4932  290.54
  4946.6  291.26  4967.4  289.89  4975.4  285.33  4975.9  284.83  4988.6  285.33
  4996.6  290.25  5000.7  293.52  5006.4  293.52  5013.9   295.4  5030.8  296.52
  5063.9  297.55  5103.9  301.22  5143.9  303.15  5173.9  305.55  5203.9  306.56
#Mann= 10 ,-1 , 0
  3503.9     .07       0  3899.5     .05       0  4072.7     .07       0
  4110.3     .05       0  4213.7     .07       0  4269.1     .05       0
  4675.3      .1       0  4975.4     .05       0  4988.6      .1       0
  5030.8     .05       0
Bank Sta=4975.4,4988.6
XS Rating Curve= 0 ,0
Exp/Cntr=0.3,0.1

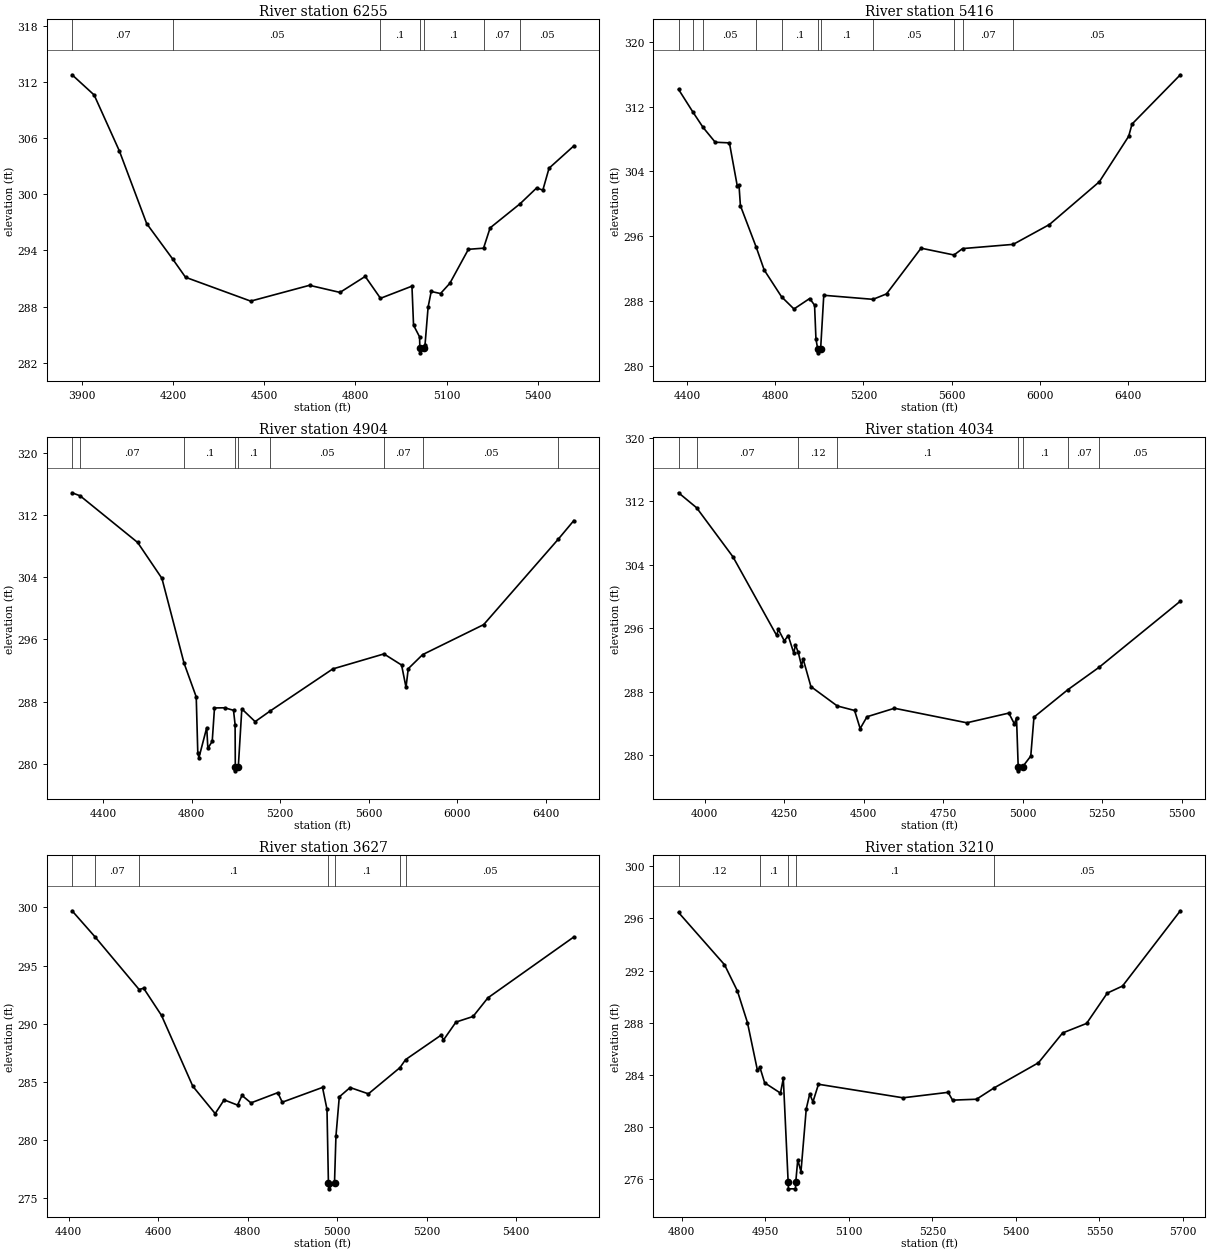
Type RM Length L Ch R = 1 ,6255    ,839,839,839
BEGIN DESCRIPTION:
EAST TINSLEY CREEK 8.0
END DESCRIPTION:
XS GIS Cut Line= 3
        2488875.       13757625.        2487775.       13757325.
      2487274.97     13757224.99
#Sta/Elev= 30
    3868  312.78  3940.6  310.62  4023.5  304.64  4113.3  296.87  4199.5  293.05
  4241.1  291.13  4455.4  288.58  4648.8  290.27    4749  289.51    4832  291.22
  4882.2  288.88  4985.7  290.18  4990.9  286.01  5010.7  284.76  5011.7  283.55
  5012.2  283.05    5025  283.55  5028.6  283.88  5038.8  287.94    5049  289.61
  5079.6  289.39  5110.2  290.48  5171.3  294.12  5221.1  294.24  5242.7  296.41
  5341.6     299  5395.7  300.68  5416.1  300.45  5436.5  302.79  5518.1  305.18
#Mann= 7 ,-1 , 0
    3868     .07       0  4199.5     .05       0  4882.2      .1       0
  5011.7     .05       0    5025      .1       0  5221.1     .07       0
  5341.6     .05       0
Bank Sta=5011.7,5025
XS Rating Curve= 0 ,0
Exp/Cntr=0.3,0.1

Type RM Length L Ch R = 1 ,5416    ,512,512,512
BEGIN DESCRIPTION:
X19088
END DESCRIPTION:
XS GIS Cut Line= 3
      2488995.24     13757548.68      2488267.53     13756986.68
      2486928.67     13756785.14
#Sta/Elev= 30
  4362.5  314.13    4427  311.36  4473.6  309.44  4528.7  307.61    4593  307.53
  4628.3  302.26  4636.5  302.29  4642.8  299.79  4714.6  294.65  4750.6  291.85
  4829.1  288.55  4885.5  287.04  4956.6  288.33  4978.8  287.51  4985.1  283.33
  4992.9  282.13  4993.4  281.63  5006.3  282.13  5020.5  288.73  5243.5  288.23
  5304.7   288.9  5461.3  294.54  5610.4   293.7  5649.4  294.49  5878.7  295.01
    6043  297.46  6268.9  302.73  6401.8  308.34  6417.1  309.85  6635.9  315.93
#Mann= 11 ,-1 , 0
  4362.5     .05       0    4427     .07       0  4473.6     .05       0
  4714.6     .07       0  4829.1      .1       0  4992.9     .05       0
  5006.3      .1       0  5243.5     .05       0  5610.4      .1       0
  5649.4     .07       0  5878.7     .05       0
Bank Sta=4992.9,5006.3
XS Rating Curve= 0 ,0
Exp/Cntr=0.3,0.1

Type RM Length L Ch R = 1 ,4904    ,870,870,870
BEGIN DESCRIPTION:
EAST TINSLEY CREEK 7.0
END DESCRIPTION:
XS GIS Cut Line= 3
      2489297.81     13756965.06        2488575.       13756775.
      2487058.59     13756655.38
#Sta/Elev= 30
  4258.6  314.86  4294.9  314.47    4555  308.47  4664.8  303.85  4764.9  292.94
  4819.9   288.6    4827  281.38  4832.2  280.79  4867.4  284.65  4872.5  281.98
  4892.2  282.89  4902.5  287.18  4948.1   287.2  4988.4  286.88  4995.6  285.05
  4996.6  279.59  4997.1  279.09  5010.1  279.59    5026  287.06  5086.2  285.42
  5154.3  286.79  5437.3   292.2  5668.5  294.13  5748.3   292.7  5768.3  289.83
  5778.4  292.23  5843.4  294.04  6119.4   297.9  6456.9   308.9  6527.1  311.29
#Mann= 9 ,-1 , 0
  4258.6     .05       0  4294.9     .07       0  4764.9      .1       0
  4996.6     .05       0  5010.1      .1       0  5154.3     .05       0
  5668.5     .07       0  5843.4     .05       0  6456.9    .035       0
Bank Sta=4996.6,5010.1
XS Rating Curve= 0 ,0
Exp/Cntr=0.3,0.1

Type RM Length L Ch R = 1 ,4034    ,407,407,407
BEGIN DESCRIPTION:
EAST TINSLEY CREEK 6.0
END DESCRIPTION:
XS GIS Cut Line= 3
      2489074.98     13756624.99        2488075.       13756225.
      2487575.01       13756225.
#Sta/Elev= 30
  3918.3  313.05    3975  311.17  4089.3  304.99  4226.6  295.09    4232  295.84
  4250.8   294.4  4262.9  295.07  4280.4  292.88  4285.8  293.88  4294.6  292.95
  4304.7  291.29    4310  292.11  4334.3  288.65  4417.1  286.21  4471.6  285.64
  4489.1  283.36  4510.6  284.85  4596.8  285.92  4824.3  284.09  4956.3  285.31
  4973.8  283.95  4980.5   284.7  4985.8  278.54  4986.3  278.04  4999.4  278.54
  5025.3   279.9  5035.3   284.8  5141.6  288.25  5240.1  291.08  5495.3   299.4
#Mann= 8 ,-1 , 0
  3918.3     .05       0    3975     .07       0  4294.6     .12       0
  4417.1      .1       0  4985.8     .05       0  4999.4      .1       0
  5141.6     .07       0  5240.1     .05       0
Bank Sta=4985.8,4999.4
XS Rating Curve= 0 ,0
Exp/Cntr=0.3,0.1

Type RM Length L Ch R = 1 ,3627    ,417,417,417
BEGIN DESCRIPTION:
EAST TINSLEY CREEK 5.0
END DESCRIPTION:
XS GIS Cut Line= 3
      2488774.96       13755975.        2488175.       13755975.
      2487674.98     13755824.99
#Sta/Elev= 30
  4407.4  299.71  4458.9  297.46  4557.3  292.94  4567.4  293.05  4607.4  290.71
  4677.4  284.62  4727.4  282.27  4747.4  283.45  4777.4     283  4787.4  283.83
  4807.4  283.19  4867.4  284.07  4877.4  283.25  4967.4  284.52  4977.4  282.64
  4980.6   276.3  4981.1   275.8  4994.2   276.3  4997.4  280.31  5004.9  283.71
  5029.1  284.51    5070  283.97  5140.5  286.22  5153.1  286.91  5232.7  289.02
  5237.9   288.6  5265.8  290.14    5304  290.62  5337.1  292.22  5529.4  297.46
#Mann= 7 ,-1 , 0
  4407.4     .12       0  4458.9     .07       0  4557.3      .1       0
  4980.6     .05       0  4994.2      .1       0  5140.5     .07       0
  5153.1     .05       0
Bank Sta=4980.6,4994.2
XS Rating Curve= 0 ,0
Exp/Cntr=0.3,0.1

Type RM Length L Ch R = 1 ,3210    ,480,480,480
BEGIN DESCRIPTION:
EAST TINSLEY CREEK 4.0
END DESCRIPTION:
XS GIS Cut Line= 3
      2488675.01       13755775.        2488475.       13755725.
      2487874.99     13755374.99
#Sta/Elev= 30
  4794.3  296.46  4876.8  292.45    4900  290.43    4918  288.01    4936  284.33
  4940.4  284.57  4948.9  283.38  4977.3  282.59  4982.4  283.72  4991.1  275.74
  4991.6  275.24  5004.2  275.24  5004.7  275.74  5008.3  277.47  5014.1  276.56
  5023.6  281.39  5029.8  282.52  5035.6  281.92  5045.5  283.27  5197.3  282.23
  5278.3  282.65  5286.2  282.05  5329.2  282.12    5360  282.97  5440.4  284.92
  5483.8  287.21  5526.8  287.94    5564  290.27  5591.3  290.81  5695.1  296.59
#Mann= 5 ,-1 , 0
  4794.3     .12       0  4940.4      .1       0  4991.1     .05       0
  5004.7      .1       0    5360     .05       0
Bank Sta=4991.1,5004.7
XS Rating Curve= 0 ,0
Exp/Cntr=0.3,0.1

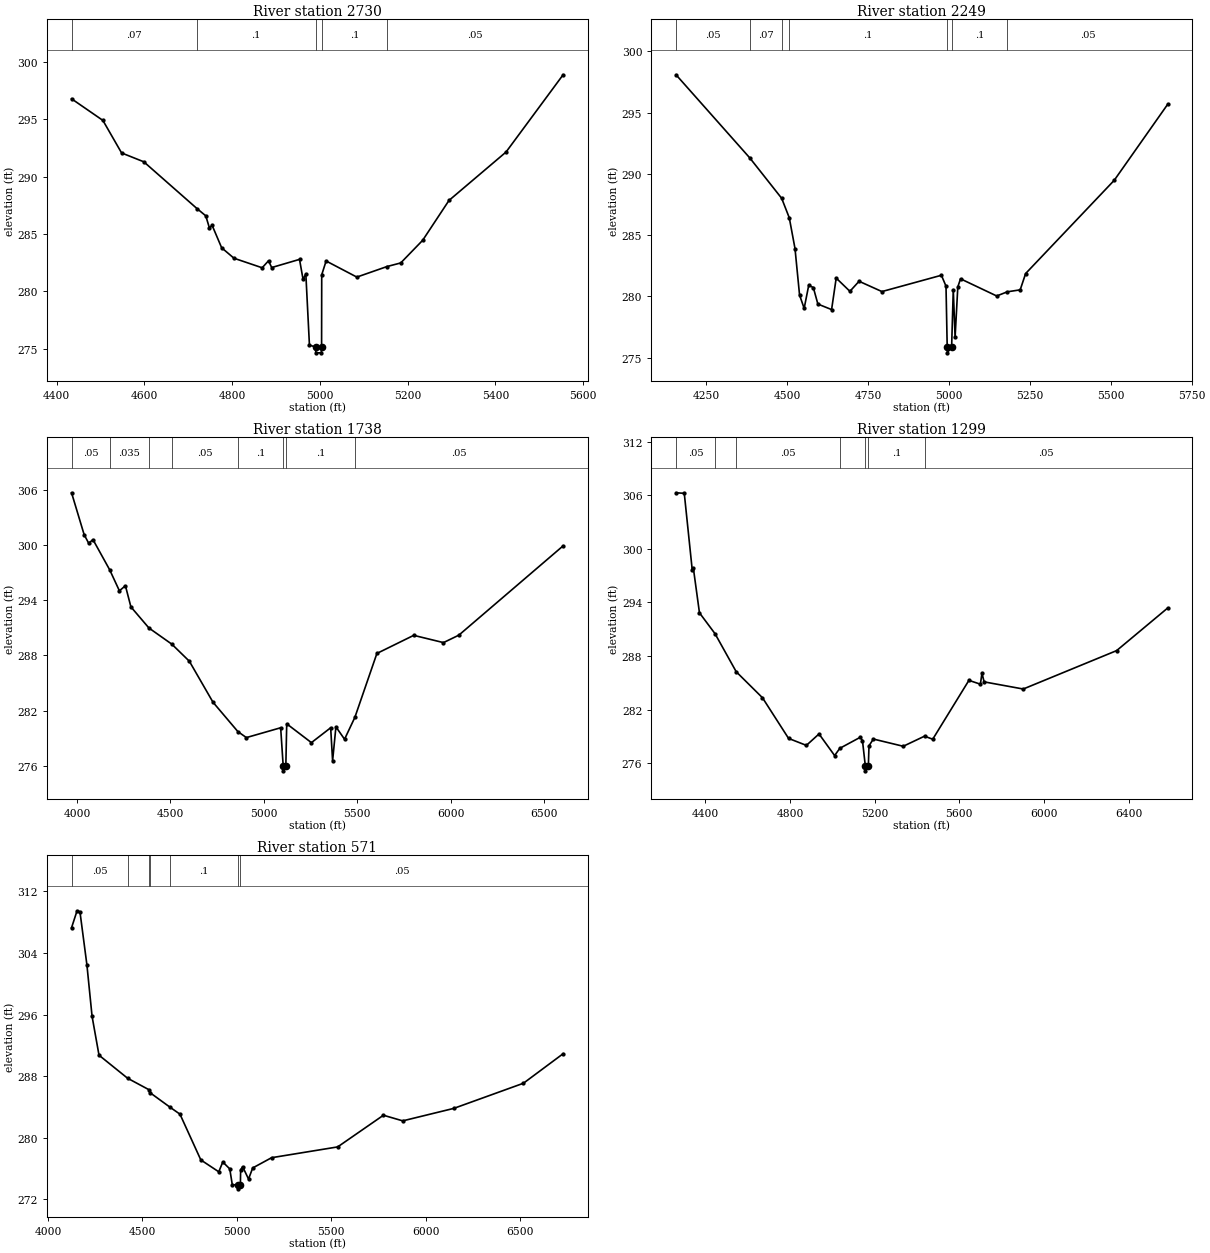
Type RM Length L Ch R = 1 ,2730    ,481,481,481
BEGIN DESCRIPTION:
EAST TINSLEY CREEK 3.0
END DESCRIPTION:
XS GIS Cut Line= 3
      2488824.97     13755624.97        2488375.       13755275.
      2487825.04       13755275.
#Sta/Elev= 30
  4434.2  296.76  4505.6  294.88  4548.2  292.05  4598.8  291.28    4720  287.21
    4740  286.58  4748.2  285.54  4754.5  285.75  4776.2   283.8  4804.3  282.89
  4868.5  282.06    4883  282.67  4890.2  282.08  4953.6  282.79  4961.7  281.05
    4968  281.53  4976.2  275.34  4990.2  275.16  4990.7  274.66  5003.4  274.66
  5003.9  275.16  5004.2  281.45  5014.2  282.65  5084.2  281.25  5153.2  282.17
  5184.2  282.48  5234.2  284.45  5294.2  287.92  5424.2  292.13  5554.2  298.85
#Mann= 5 ,-1 , 0
  4434.2     .07       0    4720      .1       0  4990.2     .05       0
  5003.9      .1       0  5153.2     .05       0
Bank Sta=4990.2,5003.9
XS Rating Curve= 0 ,0
Exp/Cntr=0.3,0.1

Type RM Length L Ch R = 1 ,2249    ,511,511,511
BEGIN DESCRIPTION:
EAST TINSLEY CREEK 2.0
END DESCRIPTION:
XS GIS Cut Line= 3
        2489075.       13755425.        2488475.       13754825.
      2487875.04     13755124.98
#Sta/Elev= 30
  4156.3  298.08  4384.1   291.3  4482.8     288  4506.3  286.41    4524   283.9
  4538.1   280.1  4552.3  279.02  4566.4   280.9  4580.6  280.72  4594.7  279.37
  4637.1  278.92  4651.3  281.49  4693.7  280.41    4722  281.23  4792.7  280.39
  4976.5  281.72  4990.7  280.83  4994.4  275.89  4994.9  275.39  5008.1  275.89
  5013.2  280.55  5018.8  276.66  5027.2  280.77  5035.6  281.43  5147.4  280.03
  5180.1  280.37    5220  280.53  5236.8  281.86  5510.7  289.47  5675.6  295.66
#Mann= 7 ,-1 , 0
  4156.3     .05       0  4384.1     .07       0  4482.8     .05       0
  4506.3      .1       0  4994.4     .05       0  5008.1      .1       0
  5180.1     .05       0
Bank Sta=4994.4,5008.1
XS Rating Curve= 0 ,0
Exp/Cntr=0.3,0.1

Type RM Length L Ch R = 1 ,1738    ,439,439,439
BEGIN DESCRIPTION:
X19087
END DESCRIPTION:
XS GIS Cut Line= 3
      2489694.09     13754745.97      2488483.67     13754457.77
      2487138.17     13754795.95
#Sta/Elev= 30
    3971  305.71  4038.4  301.15  4062.6  300.22  4085.7  300.61  4175.2  297.32
  4227.1  295.04  4259.4  295.59  4288.7  293.29  4385.2  290.99  4507.8  289.23
  4601.7  287.37  4728.2  282.91  4861.5  279.71    4907  279.06  5090.5  280.13
  5104.1  275.94  5104.6  275.44  5118.1  275.94  5122.9  280.56  5255.1  278.51
  5358.2  280.13  5368.5  276.53  5386.3  280.23  5432.5  278.88  5487.7  281.26
  5605.7  288.22  5802.8  290.19  5962.1   289.4  6044.4  290.21  6602.6  299.93
#Mann= 8 ,-1 , 0
    3971     .05       0  4175.2    .035       0  4385.2     .07       0
  4507.8     .05       0  4861.5      .1       0  5104.1     .05       0
  5118.1      .1       0  5487.7     .05       0
Bank Sta=5104.1,5118.1
XS Rating Curve= 0 ,0
Exp/Cntr=0.3,0.1

Type RM Length L Ch R = 1 ,1299    ,728,728,728
BEGIN DESCRIPTION:
X19086
END DESCRIPTION:
XS GIS Cut Line= 3
      2489542.77     13754277.64      2488699.82     13754083.12
      2487280.48     13754407.33
#Sta/Elev= 30
  4262.5  306.27  4301.4  306.21  4339.1   297.6  4344.2  297.85  4373.1  292.83
  4446.4   290.5  4546.8  286.23  4670.7  283.32  4793.9  278.77  4877.9  277.99
  4937.6  279.27  5011.3  276.85  5035.7  277.66  5132.6   278.9  5142.8  278.52
  5156.5  275.64    5157  275.14  5170.5  275.64  5173.6  277.94  5194.1   278.7
  5335.3  277.89  5435.7  279.02  5474.5  278.68  5645.4  285.27  5699.6  284.84
    5707  286.07  5717.2   285.1  5901.9   284.3  6342.9   288.6  6583.5  293.36
#Mann= 7 ,-1 , 0
  4262.5     .05       0  4446.4    .035       0  4546.8     .05       0
  5035.7      .1       0  5156.5     .05       0  5170.5      .1       0
  5435.7     .05       0
Bank Sta=5156.5,5170.5
XS Rating Curve= 0 ,0
Exp/Cntr=0.3,0.1

Type RM Length L Ch R = 1 ,571     ,0,0,0
BEGIN DESCRIPTION:
EAST TINSLEY CREEK 1.0
END DESCRIPTION:
XS GIS Cut Line= 3
      2489624.99     13754124.99      2488901.56     13753686.85
      2487251.62     13754292.07
#Sta/Elev= 30
  4125.4  307.26  4154.5  309.46    4170  309.31  4206.8  302.42    4234  295.77
  4270.8  290.72  4422.2  287.73  4535.4  286.24  4539.7  285.88  4648.6  283.94
  4699.5  283.07    4810  277.13    4905  275.59  4926.3  276.86  4963.2  275.97
  4976.6  273.92  5005.3  273.88  5005.8  273.38  5019.5  273.88  5020.8  275.85
  5031.4  276.25  5062.7  274.65  5084.7  276.09  5184.7  277.42  5534.7  278.82
    5777  282.93  5879.3   282.2  6149.8  283.82  6518.3  287.08  6728.6  290.91
#Mann= 7 ,-1 , 0
  4125.4     .05       0  4422.2    .035       0  4535.4     .05       0
  4539.7    .035       0  4648.6      .1       0  5005.3     .05       0
  5019.5     .05       0
Bank Sta=5005.3,5019.5
XS Rating Curve= 0 ,0
Exp/Cntr=0.3,0.1

Chan Stop Cuts=-1
Use User Specified Reach Order=0
Composite Channel Slope=5