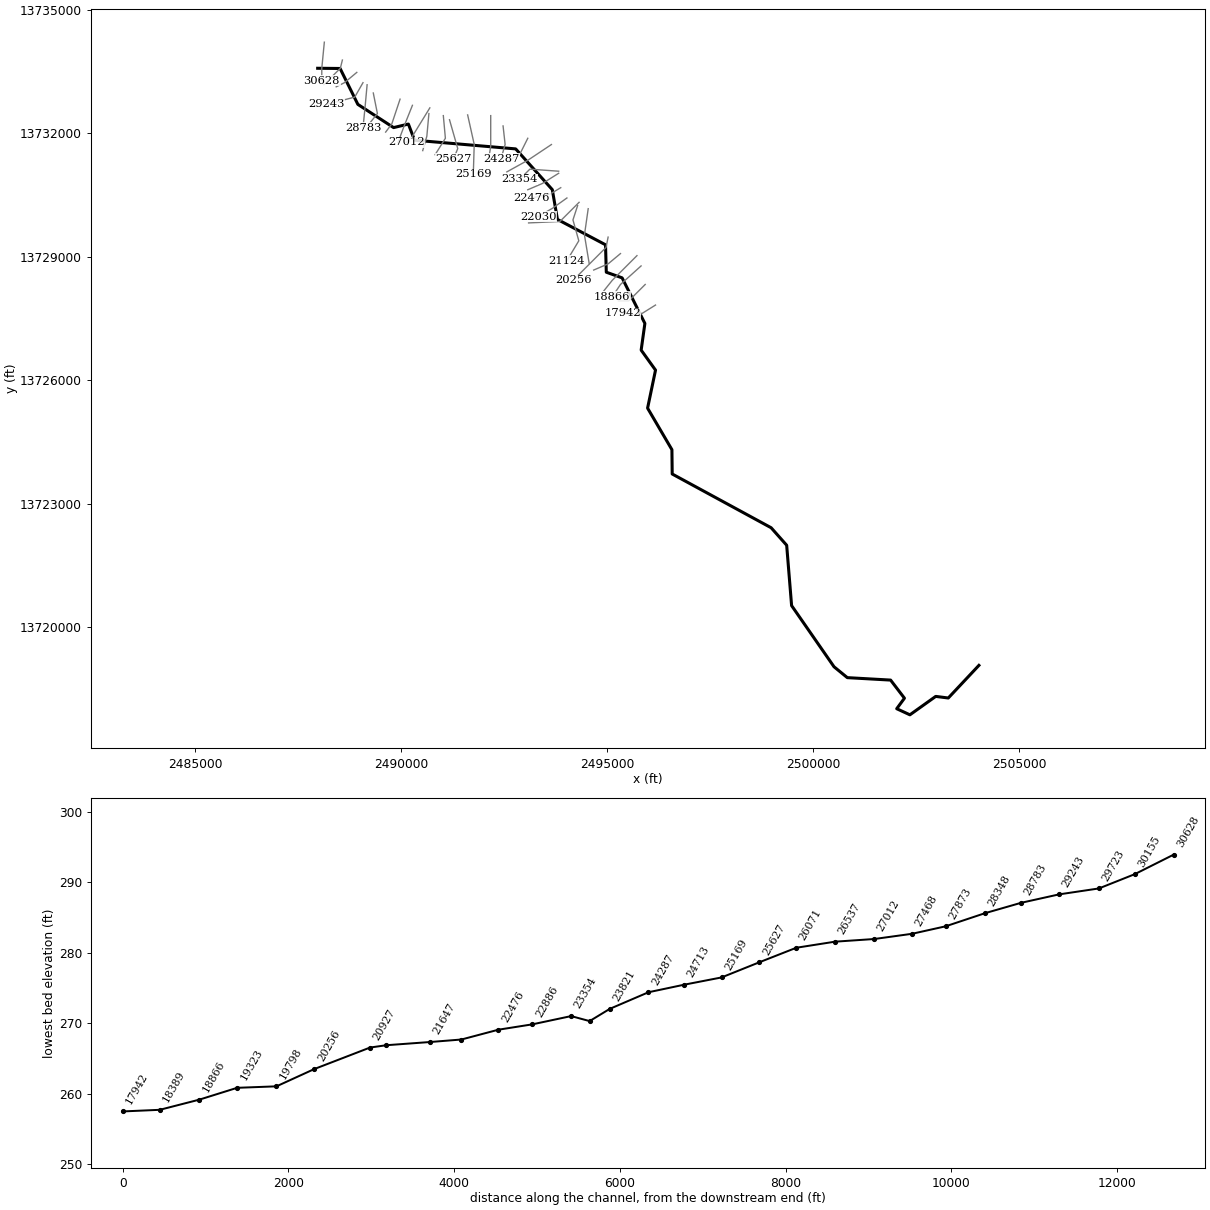
--- ELM SLOUGH.prj (project) ---

Proj Title=ELM SLOUGH Base Level Engineering
Current Plan=p01
Default Exp/Contr=0.3,0.1
English Units
Geom File=g01
Flow File=f01
Plan File=p01
Y Axis Title=Elevation
X Axis Title(PF)=Main Channel Distance
X Axis Title(XS)=Station
BEGIN DESCRIPTION:
ELM SLOUGH
END DESCRIPTION:
DSS Export Rating Curves= 0
DSS Export Rating Curve Sorted= 0
DSS Export Volume Flow Curves= 0
DXF OffsetX= 0
DXF OffsetY= 0
DXF ScaleX= 1
DXF ScaleY= 10

--- ELM SLOUGH.p01 (plan) ---

Plan Title=Multiple Run
Short Identifier=Multiple
Geom File=g01
Flow File=f01
Subcritical Flow
K Sum by GR= 0
Std Step Tol= 0.01
Critical Tol= 0.01
Num of Std Step Trials= 20
Max Error Tol= 0.3
Flow Tol Ratio= 0.001
Split Flow NTrial= 30
Split Flow Tol= 0.02
Split Flow Ratio= 0.02
Log Output Level= 0
Friction Slope Method= 1
Unsteady Friction Slope Method= 2
Unsteady Bridges Friction Slope Method= 1
Parabolic Critical Depth
Global Vel Dist=  1 , 1 , 1
Global Log Level= 0
CheckData=True
Encroach Param= -1, 0, 0, 0
BEGIN DESCRIPTION:
Multiple Run
END DESCRIPTION:

--- ELM SLOUGH.f01 (steady flow) ---

Flow Title=Multiple
Number of Profiles=7
Profile Names=10-year,25-year,50-year,1pct_min,100-year,1pct_plu,500-year
River Rch & RM= ELM SLOUGH,Reach-1,30628
     688    1105    1479     959    1913    3816    3167
River Rch & RM= ELM SLOUGH,Reach-1,28783
     923    1499    2022    1318    2630    5248    4409
River Rch & RM= ELM SLOUGH,Reach-1,23821
    1084    1773    2404    1574    3141    6267    5312
River Rch & RM= ELM SLOUGH,Reach-1,21124
    1290    2120    2882    1891    3773    7529    6409
River Rch & RM= ELM SLOUGH,Reach-1,16130
    1473    2431    3313    2178    4346    8672    7412
River Rch & RM= ELM SLOUGH,Reach-1,13096
    1685    2797    3826    2524    5035   10046    8644
River Rch & RM= ELM SLOUGH,Reach-1,4706
    1870    3098    4233    2787    5561   11095    9509
Boundary for River Rch & Prof#=ELM SLOUGH,Reach-1,1
Up Type=0
Dn Type=3
Dn Slope=0.005
Boundary for River Rch & Prof#=ELM SLOUGH,Reach-1,2
Up Type=0
Dn Type=3
Dn Slope=0.005
Boundary for River Rch & Prof#=ELM SLOUGH,Reach-1,3
Up Type=0
Dn Type=3
Dn Slope=0.005
Boundary for River Rch & Prof#=ELM SLOUGH,Reach-1,4
Up Type=0
Dn Type=3
Dn Slope=0.005
Boundary for River Rch & Prof#=ELM SLOUGH,Reach-1,5
Up Type=0
Dn Type=3
Dn Slope=0.005
Boundary for River Rch & Prof#=ELM SLOUGH,Reach-1,6
Up Type=0
Dn Type=3
Dn Slope=0.005
Boundary for River Rch & Prof#=ELM SLOUGH,Reach-1,7
Up Type=0
Dn Type=3
Dn Slope=0.005

--- ELM SLOUGH.g01 (geometry) ---

Geom Title=Existing Conditions
Program Version=4.10

River Reach=ELM SLOUGH      ,Reach-1
Reach XY= 30
        2487975.       13733575.      2488519.55     13733569.79
      2488950.59     13732697.99      2489818.05     13732134.18
       2490177.3     13732219.94      2490326.32     13731828.33
      2492781.34     13731616.98      2493670.01     13730627.55
      2493794.61      13729904.8       2494961.8     13729288.73
      2494980.47     13728622.56       2495364.7     13728485.22
       2495917.3     13727378.67      2495826.98     13726730.67
      2496175.67     13726245.08      2495982.79     13725321.57
       2496573.5     13724313.15      2496580.39     13723722.56
      2498981.48      13722417.3      2499358.86     13721992.09
      2499478.45     13720526.25      2500507.86     13719041.28
      2500830.84     13718777.05      2501881.33     13718717.66
      2502217.47     13718278.16      2502029.95     13718022.42
      2502349.91     13717874.37       2502976.5     13718321.54
      2503281.57     13718282.69        2504025.       13719075.

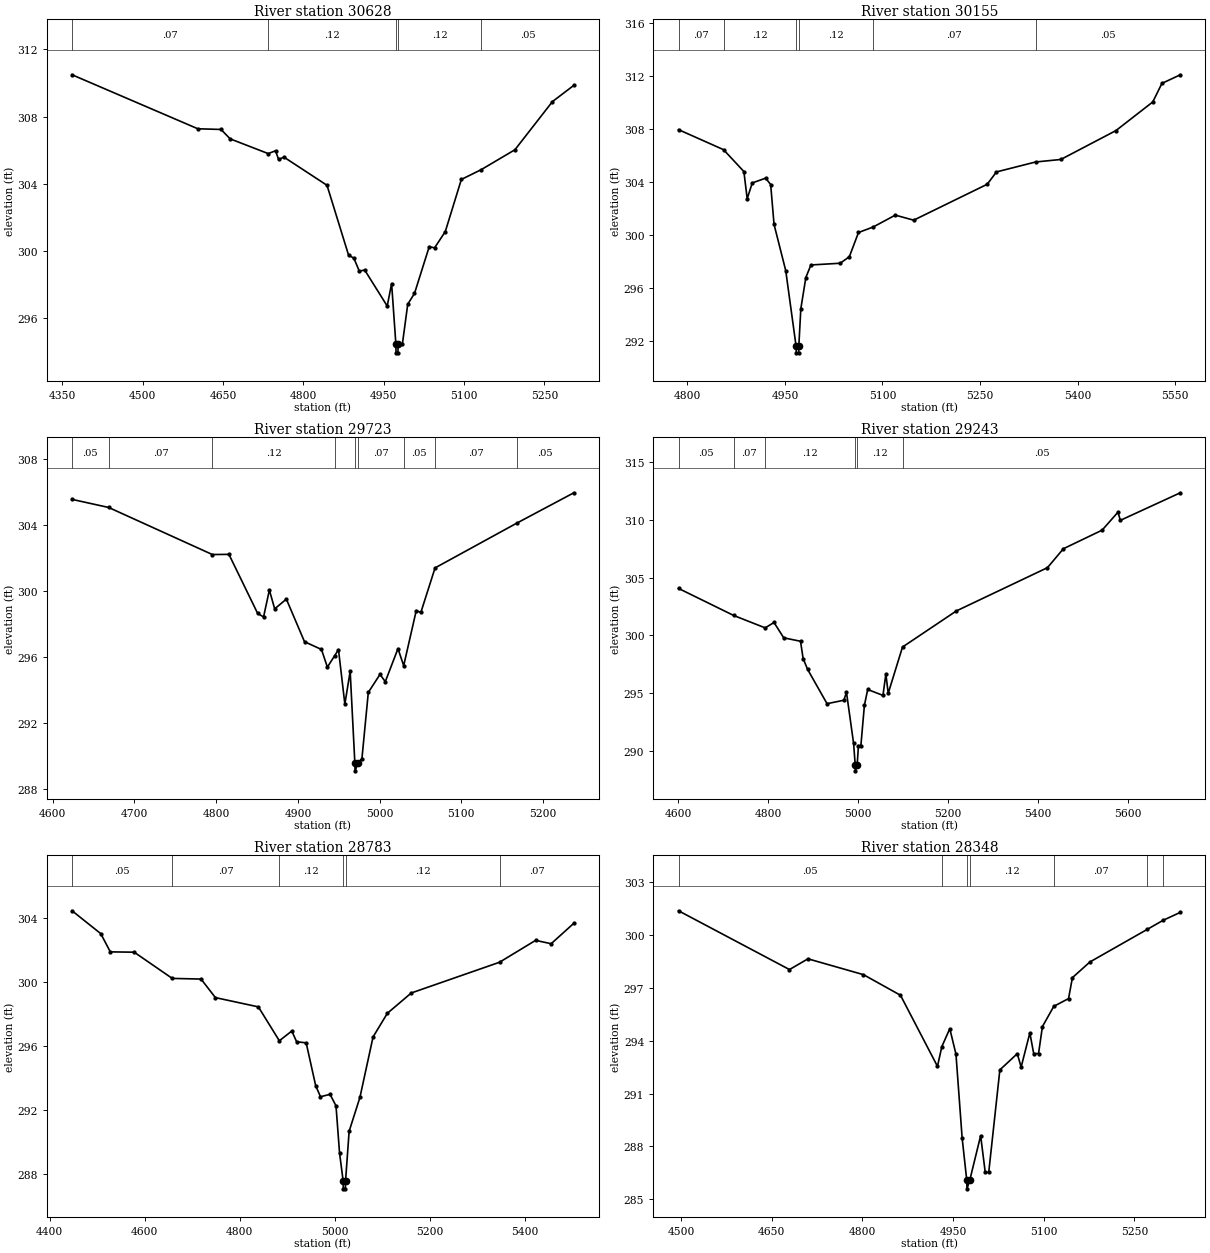
Type RM Length L Ch R = 1 ,30628   ,473,473,473
BEGIN DESCRIPTION:
ELM SLOUGH 62.0
END DESCRIPTION:
XS GIS Cut Line= 3
      2488136.81     13734208.65        2488075.       13733575.
        2488075.     13733274.96
#Sta/Elev= 30
  4368.3  310.49  4603.1  307.27  4646.4  307.23  4663.3  306.67  4734.5  305.79
  4748.1  305.96  4753.8  305.44  4763.8  305.58  4844.2   303.9  4884.4  299.74
  4894.4  299.55  4904.5  298.78  4914.5  298.85  4956.6   296.7  4964.8  298.04
  4972.8  294.41    4973  293.91  4976.6  293.91  4976.9  294.41  4984.9  294.43
  4994.9  296.81  5007.5  297.45    5035  300.24    5045  300.17    5065  301.14
    5095  304.25  5131.9  304.83    5195  306.02    5265  308.89    5305  309.86
#Mann= 5 ,-1 , 0
  4368.3     .07       0  4734.5     .12       0  4972.8     .05       0
  4976.9     .12       0  5131.9     .05       0
Bank Sta=4972.8,4976.9
XS Rating Curve= 0 ,0
Exp/Cntr=0.3,0.1

Type RM Length L Ch R = 1 ,30155   ,432,432,432
BEGIN DESCRIPTION:
ELM SLOUGH 61.0
END DESCRIPTION:
XS GIS Cut Line= 3
      2488574.99     13733774.98        2488525.       13733575.
      2488125.01     13733175.01
#Sta/Elev= 30
  4786.3  307.96  4855.5  306.45  4886.8   304.8  4891.9  302.75  4899.7  303.94
  4920.3   304.3    4928  303.82  4933.2  300.81  4951.2  297.32  4967.1  291.62
  4967.4  291.12  4971.1  291.12  4971.3  291.62  4974.4  294.45  4982.1   296.8
  4989.9  297.75  5034.9  297.88    5049  298.37  5063.1   300.2  5085.5  300.61
  5119.7  301.51    5148  301.13  5261.1  303.84  5275.3  304.77  5335.5  305.52
  5374.3  305.71  5459.1  307.89  5515.7  310.05  5529.8  311.45  5558.1   312.1
#Mann= 6 ,-1 , 0
  4786.3     .07       0  4855.5     .12       0  4967.1     .05       0
  4971.3     .12       0  5085.5     .07       0  5335.5     .05       0
Bank Sta=4967.1,4971.3
XS Rating Curve= 0 ,0
Exp/Cntr=0.3,0.1

Type RM Length L Ch R = 1 ,29723   ,480,480,480
BEGIN DESCRIPTION:
ELM SLOUGH 60.0
END DESCRIPTION:
XS GIS Cut Line= 3
      2488925.03     13733475.03        2488625.       13733225.
      2488424.97     13733124.98
#Sta/Elev= 30
  4623.6  305.54  4668.4  305.05  4795.3   302.2  4815.6  302.21  4850.8  298.63
    4858  298.42  4865.1  300.05  4871.6  298.91  4885.9   299.5  4908.1  296.92
  4928.9  296.45  4936.1  295.38  4945.1  296.08  4949.7  296.44  4957.5  293.14
    4964  295.13  4969.7   289.6    4970   289.1    4974   289.6  4978.4  289.84
  4986.2  293.85  5000.5  294.94    5007   294.5  5022.5   296.5  5029.5  295.47
  5044.9  298.81  5050.5  298.69  5067.9  301.39  5167.9   304.1  5237.8  305.94
#Mann= 9 ,-1 , 0
  4623.6     .05       0  4668.4     .07       0  4795.3     .12       0
  4945.1     .07       0  4969.7     .05       0    4974     .07       0
  5029.5     .05       0  5067.9     .07       0  5167.9     .05       0
Bank Sta=4969.7,4974
XS Rating Curve= 0 ,0
Exp/Cntr=0.3,0.1

Type RM Length L Ch R = 1 ,29243   ,460,460,460
BEGIN DESCRIPTION:
ELM SLOUGH 59.0
END DESCRIPTION:
XS GIS Cut Line= 3
      2489075.01     13733225.02        2488875.       13732875.
      2488184.73     13732695.35
#Sta/Elev= 30
  4601.1  304.07  4723.6  301.73  4793.9  300.65  4813.5  301.12  4835.1  299.79
  4872.5  299.49  4878.3  297.99  4888.3  297.05  4931.5  294.08    4969  294.38
  4974.7  295.08  4990.6  290.63  4994.2  288.76  4994.5  288.26  4998.5  288.76
  5001.4  290.45  5006.8  290.45  5014.6  293.93  5021.9  295.31  5055.9   294.8
  5062.4  296.65  5067.6  294.98  5099.4  298.99  5219.3  302.12  5421.9  305.87
  5457.3  307.51  5543.5  309.12  5578.8  310.68    5584  309.97  5717.5  312.36
#Mann= 6 ,-1 , 0
  4601.1     .05       0  4723.6     .07       0  4793.9     .12       0
  4994.2     .05       0  4998.5     .12       0  5099.4     .05       0
Bank Sta=4994.2,4998.5
XS Rating Curve= 0 ,0
Exp/Cntr=0.3,0.1

Type RM Length L Ch R = 1 ,28783   ,435,435,435
BEGIN DESCRIPTION:
ELM SLOUGH 58.0
END DESCRIPTION:
XS GIS Cut Line= 3
        2489175.     13733175.03        2489125.       13732625.
        2489075.     13732124.99
#Sta/Elev= 30
  4447.4  304.45  4507.7  303.02  4527.8  301.88    4578  301.86    4658  300.22
  4718.5  300.18  4748.7  299.02    4839  298.44  4883.1  296.32  4909.3  296.93
  4919.4  296.26  4939.5  296.19  4959.5  293.51  4969.6  292.82  4989.7  292.97
  5002.2  292.25  5009.7  289.29  5017.2  287.56  5017.6  287.06  5021.9  287.06
  5022.3  287.56  5029.8  290.66  5052.5  292.78  5080.1  296.56  5110.2  298.04
  5160.5  299.31  5345.9  301.23  5421.8   302.6  5454.5  302.39  5502.2  303.67
#Mann= 6 ,-1 , 0
  4447.4     .05       0    4658     .07       0  4883.1     .12       0
  5017.2     .05       0  5022.3     .12       0  5345.9     .07       0
Bank Sta=5017.2,5022.3
XS Rating Curve= 0 ,0
Exp/Cntr=0.3,0.1

Type RM Length L Ch R = 1 ,28348   ,475,475,475
BEGIN DESCRIPTION:
ELM SLOUGH 57.0
END DESCRIPTION:
XS GIS Cut Line= 3
      2489325.01     13732974.97        2489425.       13732475.
      2489225.02     13732225.02
#Sta/Elev= 30
  4496.1  301.39  4679.6  298.05  4710.2  298.66    4802  297.76  4863.2  296.59
  4924.4  292.55  4931.6  293.67  4944.8  294.69    4955  293.24  4965.2  288.48
  4972.8  286.09  4973.2  285.59  4977.9  286.09  4995.8  288.61  5003.4  286.53
  5009.2  286.53  5027.6  292.35  5056.4  293.27  5062.8  292.51  5077.2  294.45
  5083.6  293.27  5091.6  293.28    5098  294.81  5116.8  295.96  5141.2   296.4
  5147.6  297.59  5176.5  298.48  5271.2  300.33  5297.7  300.85  5326.1   301.3
#Mann= 7 ,-1 , 0
  4496.1     .05       0  4931.6     .12       0  4972.8     .05       0
  4977.9     .12       0  5116.8     .07       0  5271.2     .12       0
  5297.7     .07       0
Bank Sta=4972.8,4977.9
XS Rating Curve= 0 ,0
Exp/Cntr=0.3,0.1

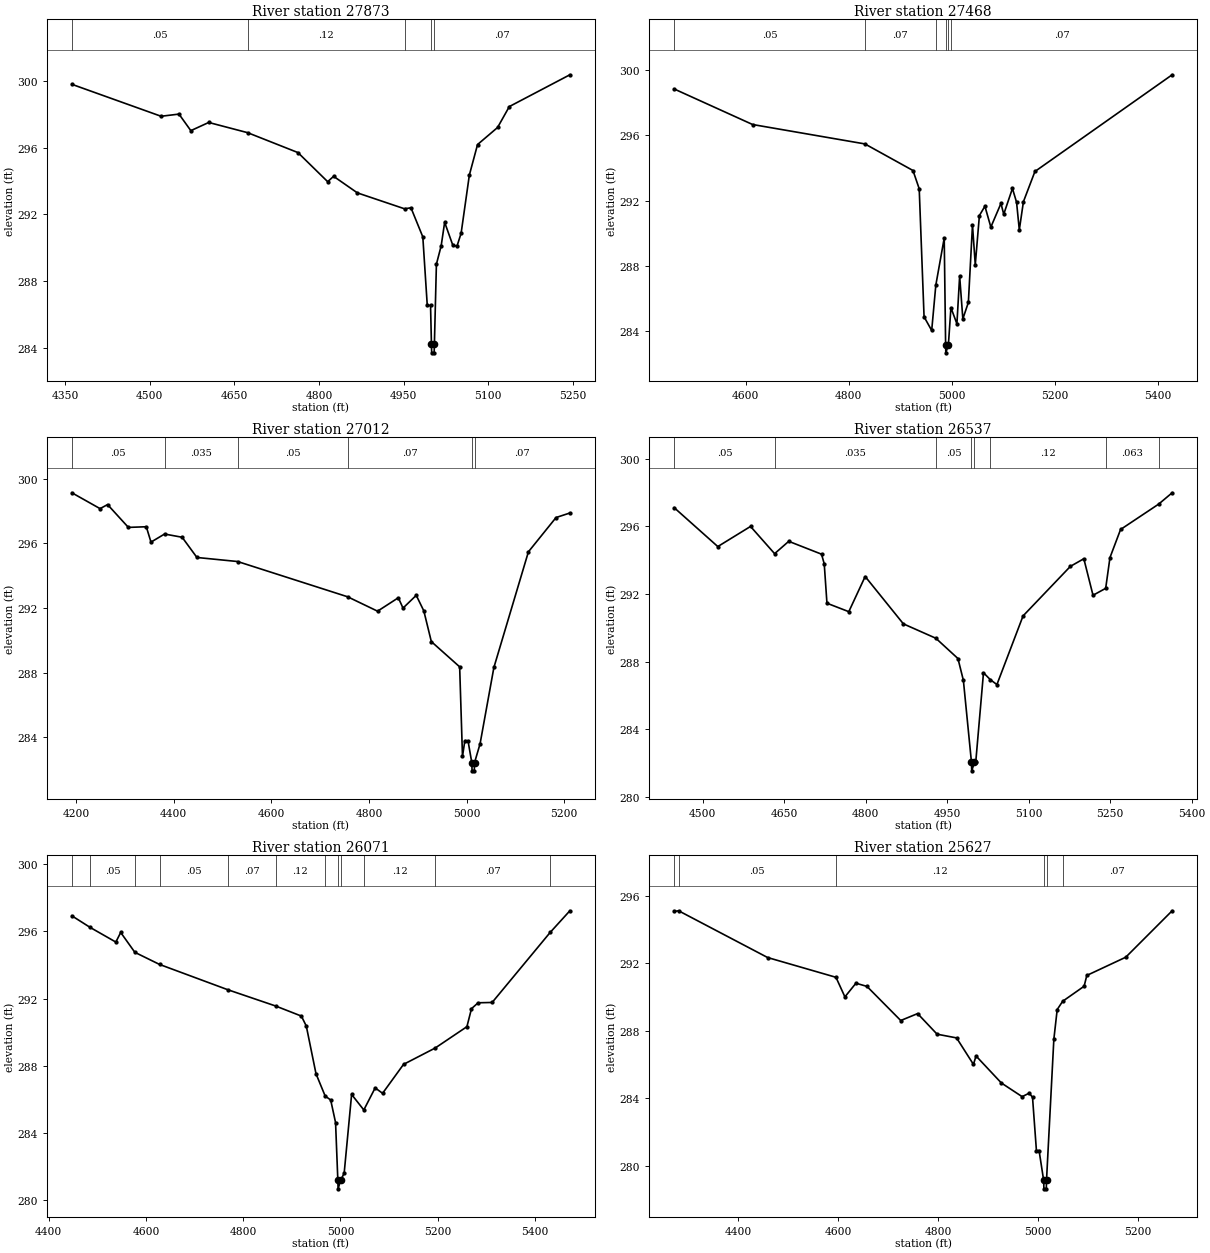
Type RM Length L Ch R = 1 ,27873   ,405,405,405
BEGIN DESCRIPTION:
ELM SLOUGH 56.0
END DESCRIPTION:
XS GIS Cut Line= 3
      2489975.01     13732825.02        2489775.       13732225.
      2489624.99     13732024.98
#Sta/Elev= 30
    4362  299.78  4520.1  297.87  4551.8     298  4572.8  297.01  4604.5   297.5
  4673.4  296.89  4762.6   295.7  4815.3  293.96  4825.8  294.28    4868  293.29
  4951.5  292.34  4962.9   292.4  4983.9  290.66  4991.8  286.56  4997.6  286.56
  4999.2  284.23  4999.6  283.73    5004  283.73  5004.4  284.23    5008  289.03
  5016.4  290.12  5022.6  291.53  5037.2  290.15  5044.5  290.11  5051.8  290.88
  5066.4  294.36  5080.9  296.18  5116.4   297.2  5137.2  298.45  5244.5  300.35
#Mann= 5 ,-1 , 0
    4362     .05       0  4673.4     .12       0  4951.5     .07       0
  4999.2     .05       0  5004.4     .07       0
Bank Sta=4999.2,5004.4
XS Rating Curve= 0 ,0
Exp/Cntr=0.3,0.1

Type RM Length L Ch R = 1 ,27468   ,456,456,456
BEGIN DESCRIPTION:
ELM SLOUGH 55.0
END DESCRIPTION:
XS GIS Cut Line= 3
      2490274.99     13732674.97        2490075.       13732175.
      2489924.99     13731774.98
#Sta/Elev= 30
  4461.6  298.85  4613.7  296.67  4831.5  295.48  4924.7  293.85  4936.8  292.73
  4946.2  284.88    4961  284.04    4969  286.82  4985.3  289.71    4988  283.17
  4988.4  282.67  4993.4  283.17  4998.3  285.44  5009.9  284.45  5015.2  287.38
  5021.4  284.75  5032.1  285.76  5040.1  290.51  5045.5  288.07  5053.5  291.09
  5064.2  291.66  5075.7  290.38  5095.3  291.83  5100.7  291.17  5117.6  292.75
  5125.6   291.9  5130.9  290.21  5138.9  291.94  5161.2  293.79  5427.3  299.72
#Mann= 6 ,-1 , 0
  4461.6     .05       0  4831.5     .07       0    4969     .12       0
    4988     .05       0  4993.4     .12       0  4998.3     .07       0
Bank Sta=4988,4993.4
XS Rating Curve= 0 ,0
Exp/Cntr=0.3,0.1

Type RM Length L Ch R = 1 ,27012   ,475,475,475
BEGIN DESCRIPTION:
ELM SLOUGH 54.0
END DESCRIPTION:
XS GIS Cut Line= 3
      2490697.75     13732613.18        2490275.       13731925.
      2490124.99     13731774.99
#Sta/Elev= 30
  4191.7  299.12  4249.4  298.14  4264.8  298.39  4307.4  296.98  4344.1  297.02
  4353.7  296.07  4381.5  296.57  4417.5  296.37  4447.8  295.12  4531.1  294.87
  4756.4  292.69  4817.7   291.8  4860.2  292.63  4869.8  291.99  4896.9  292.78
  4912.4  291.82  4927.8  289.92  4985.8  288.36  4991.6  282.82  4996.4  283.79
  5002.9  283.79  5010.7  282.43  5011.2  281.93  5015.8  281.93  5016.2  282.43
  5027.6   283.6  5055.9  288.32  5126.6  295.47  5183.2  297.59  5211.5  297.87
#Mann= 6 ,-1 , 0
  4191.7     .05       0  4381.5    .035       0  4531.1     .05       0
  4756.4     .07       0  5010.7     .05       0  5016.2     .07       0
Bank Sta=5010.7,5016.2
XS Rating Curve= 0 ,0
Exp/Cntr=0.3,0.1

Type RM Length L Ch R = 1 ,26537   ,466,466,466
BEGIN DESCRIPTION:
ELM SLOUGH 53.0
END DESCRIPTION:
XS GIS Cut Line= 3
        2490675.     13732474.96        2490625.       13731925.
      2490525.01     13731575.03
#Sta/Elev= 30
  4447.8  297.11  4528.1  294.81  4588.3     296  4632.6  294.39  4658.6  295.12
  4718.9  294.36  4723.9  293.79  4728.9  291.46  4769.1  290.96  4799.2  293.04
  4869.5  290.24  4929.2  289.39  4969.9  288.19  4979.9   286.9  4994.8  282.05
  4995.2  281.55  5000.3  282.05  5002.6  282.05  5016.9  287.35  5029.5  286.94
  5041.6  286.65  5089.7  290.71  5176.8  293.64  5201.5  294.09  5218.4  291.93
  5241.7  292.34  5249.6  294.16  5269.1  295.82  5339.2  297.32    5364  297.99
#Mann= 8 ,-1 , 0
  4447.8     .05       0  4632.6    .035       0  4929.2     .05       0
  4994.8     .05       0  5000.3     .05       0  5029.5     .12       0
  5241.7    .063       0  5339.2     .07       0
Bank Sta=4994.8,5000.3
XS Rating Curve= 0 ,0
Exp/Cntr=0.3,0.1

Type RM Length L Ch R = 1 ,26071   ,444,444,444
BEGIN DESCRIPTION:
ELM SLOUGH 52.0
END DESCRIPTION:
XS GIS Cut Line= 3
        2491025.     13732424.98        2491075.       13731875.
      2490824.97     13731474.96
#Sta/Elev= 30
  4447.8  296.92  4485.4  296.23  4538.2  295.36  4548.2  295.93  4577.3  294.75
  4628.1  294.03  4768.1  292.53  4866.7  291.56  4919.7  290.96  4929.8  290.37
  4949.8  287.53  4968.6  286.21    4980  285.97    4990  284.63  4994.7  281.19
  4995.2  280.69  5000.3  281.19  5007.7  281.62    5023   286.3  5048.1  285.38
  5071.4  286.69  5086.7  286.37  5129.8  288.09  5194.8  289.06  5260.1  290.33
  5269.5   291.4  5283.1  291.75    5312  291.77  5431.2  295.93  5471.8  297.22
#Mann= 12 ,-1 , 0
  4447.8     .07       0  4485.4     .05       0  4577.3     .07       0
  4628.1     .05       0  4768.1     .07       0  4866.7     .12       0
  4968.6     .15       0  4994.7     .05       0  5000.3     .15       0
  5048.1     .12       0  5194.8     .07       0  5431.2     .05       0
Bank Sta=4994.7,5000.3
XS Rating Curve= 0 ,0
Exp/Cntr=0.3,0.1

Type RM Length L Ch R = 1 ,25627   ,458,458,458
BEGIN DESCRIPTION:
ELM SLOUGH 51.0
END DESCRIPTION:
XS GIS Cut Line= 3
      2491175.01     13732324.98        2491375.       13731625.
      2491275.02     13731375.04
#Sta/Elev= 30
  4271.6  295.07  4280.5  295.11  4458.8  292.34  4595.6  291.17  4613.5  290.01
  4635.6  290.82  4657.7  290.63  4725.3  288.61  4759.1  289.02  4798.1   287.8
  4837.1  287.58  4870.9  286.01  4876.1  286.51  4926.8  284.91  4968.4   284.1
  4982.7  284.31  4989.2  284.06    4997  280.91  5002.3  280.91  5011.5  279.14
    5012  278.64  5016.8  278.64  5017.2  279.14  5031.9   287.5  5038.6  289.26
  5049.6  289.75  5092.5  290.64  5097.9  291.28  5175.9  292.36  5268.8  295.11
#Mann= 6 ,-1 , 0
  4271.6     .07       0  4280.5     .05       0  4595.6     .12       0
  5011.5     .05       0  5017.2     .12       0  5049.6     .07       0
Bank Sta=5011.5,5017.2
XS Rating Curve= 0 ,0
Exp/Cntr=0.3,0.1

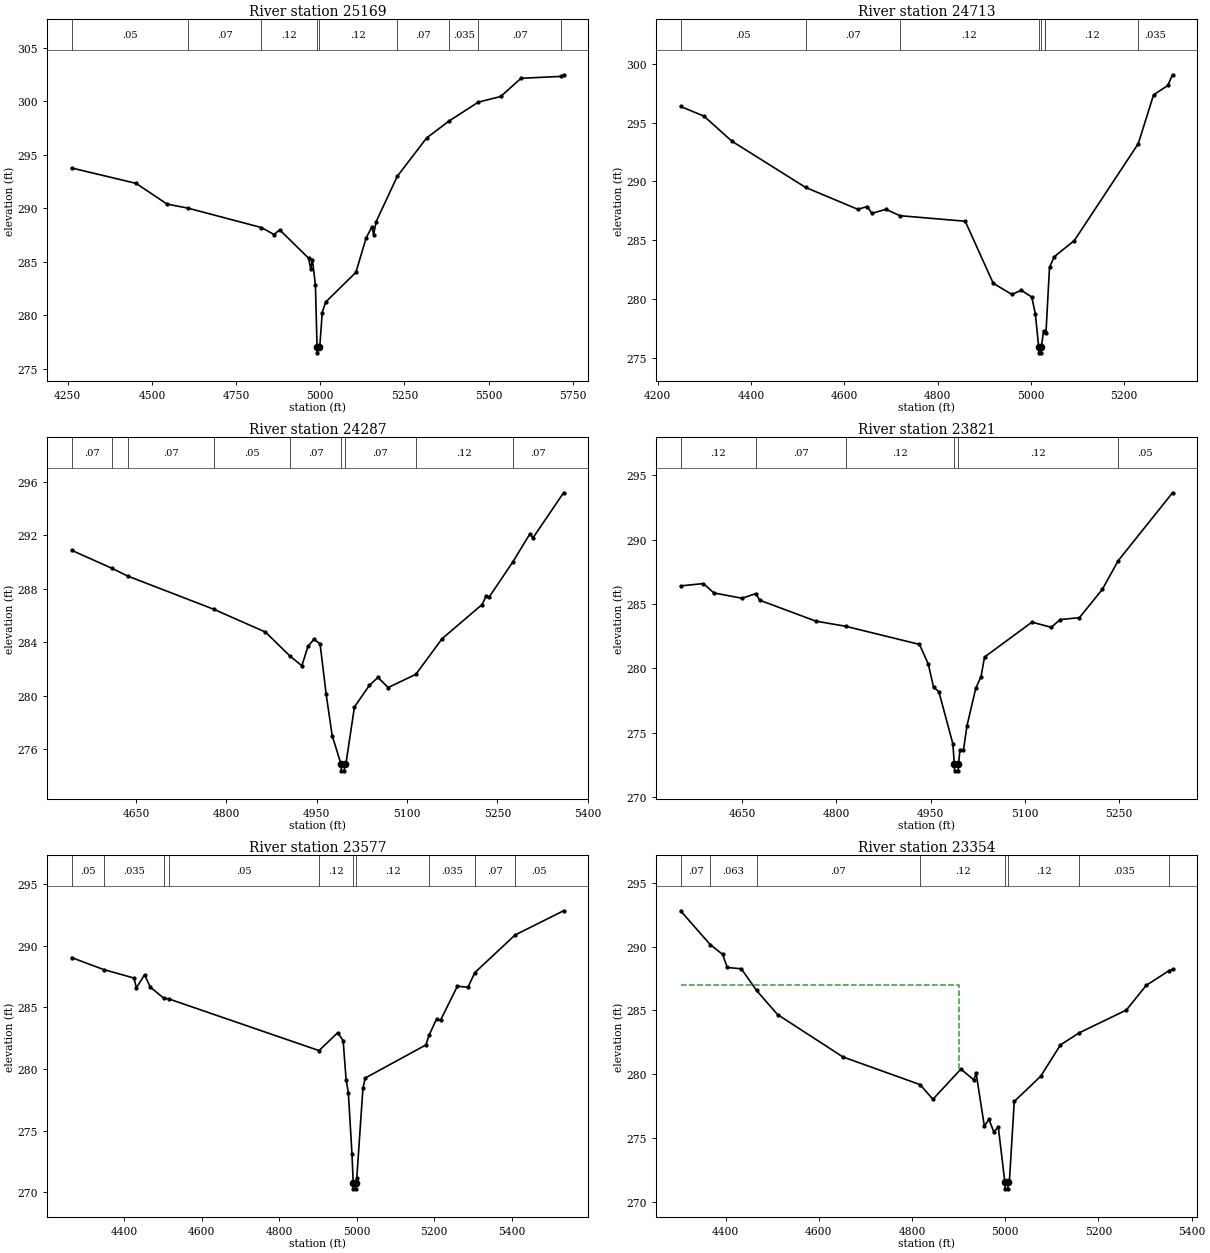
Type RM Length L Ch R = 1 ,25169   ,456,456,456
BEGIN DESCRIPTION:
ELM SLOUGH 50.0
END DESCRIPTION:
XS GIS Cut Line= 3
      2491615.31     13732442.03        2491775.       13731725.
       2491752.3     13730998.56
#Sta/Elev= 30
  4261.3  293.76  4452.9  292.32  4545.1  290.38  4606.3  290.01  4825.3  288.19
  4862.7  287.54  4879.5  287.98  4965.2  285.33  4971.6  284.35  4976.7   285.2
  4985.7   282.8  4990.5  276.98  4990.9  276.48  4996.2  276.98  4998.4  276.98
  5005.9  280.25  5015.9  281.22    5106  284.01    5136  287.19  5153.5  288.27
  5158.5  287.53    5166  288.74  5228.8  292.98  5316.1  296.57  5382.7  298.15
  5469.3  299.91  5536.2  300.44  5596.2  302.14  5715.4  302.32  5722.7  302.47
#Mann= 9 ,-1 , 0
  4261.3     .05       0  4606.3     .07       0  4825.3     .12       0
  4990.5     .05       0  4996.2     .12       0  5228.8     .07       0
  5382.7    .035       0  5469.3     .07       0  5715.4     .05       0
Bank Sta=4990.5,4996.2
XS Rating Curve= 0 ,0
Exp/Cntr=0.3,0.1

Type RM Length L Ch R = 1 ,24713   ,426,426,426
BEGIN DESCRIPTION:
ELM SLOUGH 49.0
END DESCRIPTION:
XS GIS Cut Line= 3
        2492175.     13732425.02        2492175.       13731675.
      2492124.99     13731374.96
#Sta/Elev= 30
  4249.2  296.37  4299.2  295.55  4359.2  293.42  4517.2  289.49  4629.2  287.63
  4649.2  287.87  4659.2  287.29  4689.2  287.63  4719.3  287.09  4859.2  286.62
  4919.2  281.35  4959.2   280.4  4979.2  280.76  5001.8  280.18  5009.4  278.76
  5016.6  275.94    5017  275.44  5021.9  275.44  5022.4  275.94  5027.1  277.32
  5029.3  277.23  5030.5  277.18  5032.2   277.1  5039.8   282.7  5049.9   283.6
    5093  284.98  5229.9   293.2  5262.8  297.35  5293.2  298.15  5303.4  299.06
#Mann= 8 ,-1 , 0
  4249.2     .05       0  4517.2     .07       0  4719.3     .12       0
  5016.6     .05       0  5022.4     .12       0  5029.3     .07       0
  5030.5     .12       0  5229.9    .035       0
Bank Sta=5016.6,5022.4
XS Rating Curve= 0 ,0
Exp/Cntr=0.3,0.1

Type RM Length L Ch R = 1 ,24287   ,466,466,466
BEGIN DESCRIPTION:
ELM SLOUGH 48.0
END DESCRIPTION:
XS GIS Cut Line= 3
        2492475.     13732174.97        2492525.       13731725.
      2492425.01     13731375.04
#Sta/Elev= 30
  4543.1  290.88  4610.6  289.52  4636.3  288.95  4778.9  286.47    4865  284.76
    4906  282.95  4925.4  282.24  4935.5  283.69  4945.5  284.22  4955.6  283.88
  4965.7  280.12  4975.7  277.02  4990.4  274.88  4990.9  274.38  4995.8  274.38
  4996.3  274.88  4998.4  274.88  5012.7  279.16  5037.4  280.77  5051.7  281.37
  5068.6  280.61  5114.6   281.6  5158.3  284.27  5224.6  286.82  5231.1  287.44
  5236.3  287.38  5275.3  289.99  5303.9   292.1  5309.1  291.81  5359.8  295.18
#Mann= 9 ,-1 , 0
  4543.1     .07       0  4610.6     .05       0  4636.3     .07       0
  4778.9     .05       0    4906     .07       0  4990.4     .05       0
  4996.3     .07       0  5114.6     .12       0  5275.3     .07       0
Bank Sta=4990.4,4996.3
XS Rating Curve= 0 ,0
Exp/Cntr=0.3,0.1

Type RM Length L Ch R = 1 ,23821   ,244,244,244
BEGIN DESCRIPTION:
ELM SLOUGH 47.0
END DESCRIPTION:
XS GIS Cut Line= 3
        2493075.       13731875.        2492875.       13731475.
      2492575.02     13731325.01
#Sta/Elev= 30
  4552.3  286.41  4588.6  286.59  4605.4  285.86  4650.1  285.45  4672.1  285.81
  4678.1   285.3  4767.5  283.67  4814.9  283.27  4932.4  281.86  4946.4  280.33
  4954.8  278.53  4963.2  278.19  4985.5  274.13  4987.8  272.53  4988.3  272.03
  4993.9  272.03  4994.4  272.53  4996.7  273.62  5002.3  273.62  5007.9  275.53
  5021.9  278.44  5030.3  279.36  5035.9  280.88  5111.3  283.59  5142.1  283.19
    5156  283.79  5186.8  283.94  5223.1  286.13  5248.5  288.37  5334.9  293.65
#Mann= 6 ,-1 , 0
  4552.3     .12       0  4672.1     .07       0  4814.9     .12       0
  4987.8     .05       0  4994.4     .12       0  5248.5     .05       0
Bank Sta=4987.8,4994.4
XS Rating Curve= 0 ,0
Exp/Cntr=0.3,0.1

Type RM Length L Ch R = 1 ,23577   ,223,223,223
BEGIN DESCRIPTION:
X19152
END DESCRIPTION:
XS GIS Cut Line= 3
        2493649.     13731723.01      2493073.82     13731339.56
      2492567.08      13731058.8
#Sta/Elev= 30
  4263.7  289.03  4346.4  288.06  4424.7  287.37  4431.1  286.58  4452.1  287.63
  4467.1  286.63  4501.4  285.75  4516.5  285.66  4902.9  281.49  4950.9  282.94
  4965.1   282.3  4972.7  279.13  4978.5  278.08  4987.9   273.1  4991.1  270.79
  4991.6  270.29  4997.3  270.29  4997.8  270.79  5000.2  271.13  5016.2  278.45
  5022.2  279.27  5178.8  281.95    5187  282.74  5206.3  284.05  5216.6  283.95
  5260.1  286.71  5287.5  286.62  5304.9   287.8  5408.7  290.85  5534.3  292.82
#Mann= 10 ,-1 , 0
  4263.7     .05       0  4346.4    .035       0  4501.4     .07       0
  4516.5     .05       0  4902.9     .12       0  4991.1     .05       0
  4997.8     .12       0    5187    .035       0  5304.9     .07       0
  5408.7     .05       0
Bank Sta=4991.1,4997.8
XS Rating Curve= 0 ,0
Exp/Cntr=0.3,0.1

Type RM Length L Ch R = 1 ,23354   ,468,468,468
BEGIN DESCRIPTION:
ELM SLOUGH 46.0
END DESCRIPTION:
XS GIS Cut Line= 3
      2493825.02       13731075.        2493125.       13731125.
      2492874.97     13730874.97
#Sta/Elev= 30
  4303.4  292.82  4367.5  290.15  4393.6   289.4  4403.7  288.37  4433.7  288.27
  4466.4  286.57  4511.4  284.68  4651.8  281.35  4817.2  279.18  4844.8  278.03
  4904.9   280.4  4932.5  279.55  4937.5  280.07  4955.1  275.93  4965.1  276.46
  4975.1  275.49  4985.1  275.83  4999.2   271.5  4999.7     271  5005.6     271
  5006.1   271.5  5008.7   271.5  5019.3  277.86  5075.9  279.83  5118.3  282.29
  5158.5  283.24  5259.8  285.03  5302.2  286.96  5350.8  288.11  5358.8  288.22
#Mann= 8 ,-1 , 0
  4303.4     .07       0  4367.5    .063       0  4466.4     .07       0
  4817.2     .12       0  4999.2     .05       0  5006.1     .12       0
  5158.5    .035       0  5350.8     .07       0
#XS Ineff= 2 , 0
       0    4900     287               0
Permanent Ineff=
       F       F
Bank Sta=4999.2,5006.1
XS Rating Curve= 0 ,0
Exp/Cntr=0.3,0.1

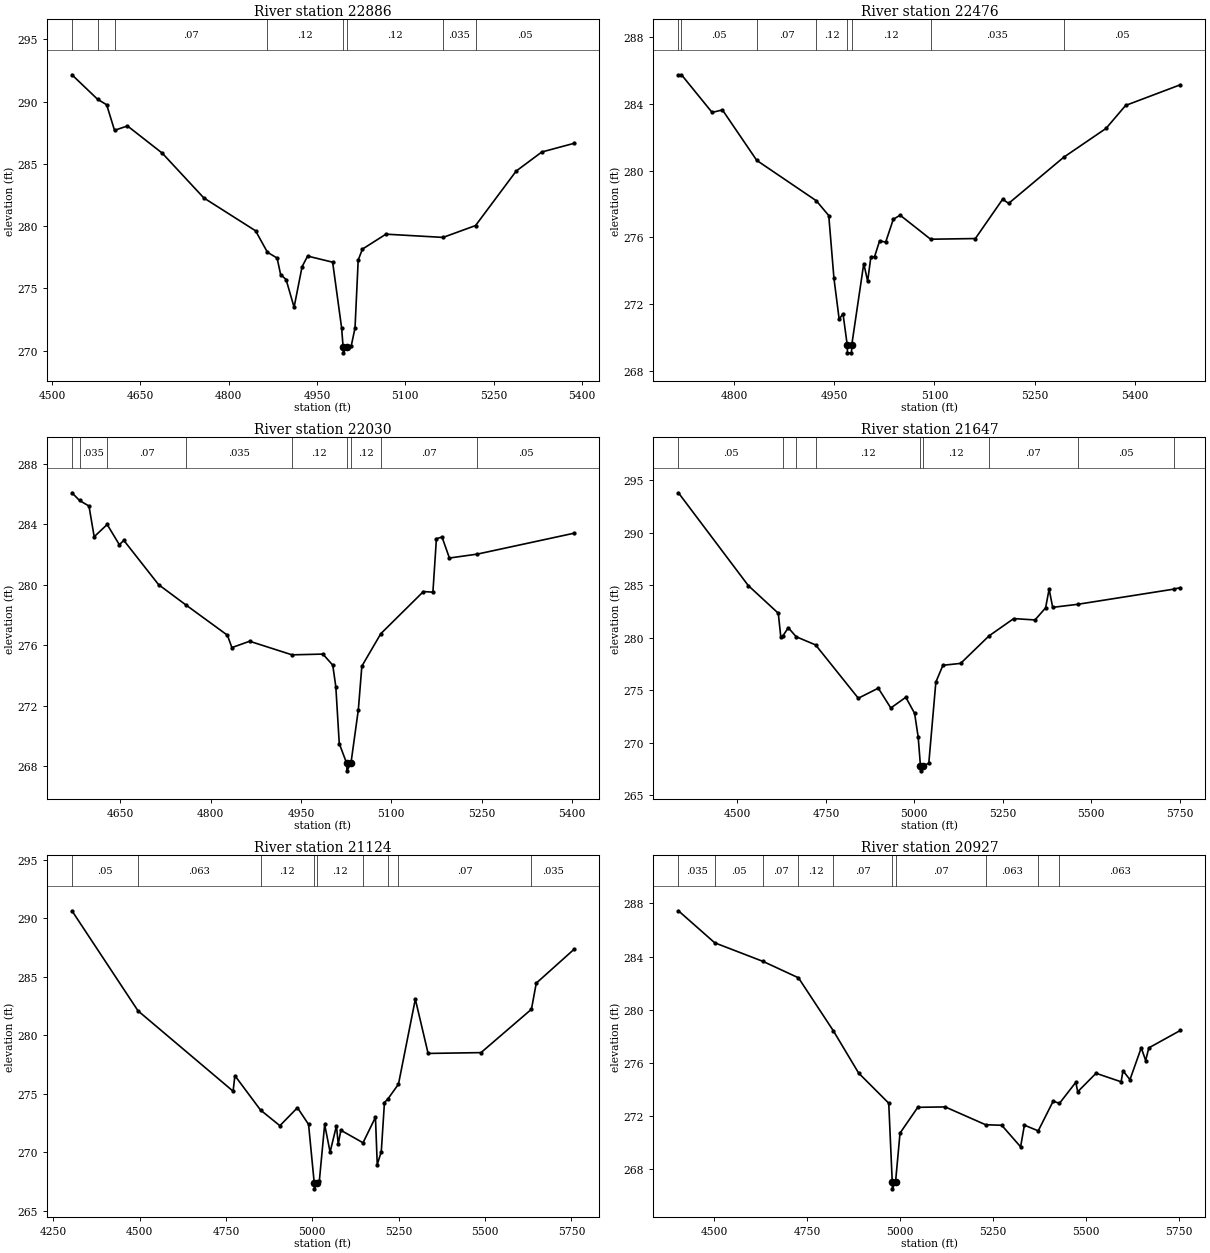
Type RM Length L Ch R = 1 ,22886   ,410,410,410
BEGIN DESCRIPTION:
ELM SLOUGH 45.0
END DESCRIPTION:
XS GIS Cut Line= 3
      2493824.99     13731024.99        2493425.       13730775.
      2493074.98     13730624.99
#Sta/Elev= 30
  4533.9  292.16  4577.3   290.2  4592.9  289.75  4606.2   287.7  4628.2  288.05
  4687.2  285.87  4757.9  282.27  4845.8  279.63  4865.9  277.91  4882.4  277.44
  4888.3  276.12  4897.7  275.71  4911.2  273.49  4924.8  276.75  4934.2   277.6
  4976.7  277.11    4992  271.81  4994.4  270.33  4994.9  269.83  5001.4  270.33
  5008.3  270.39  5014.7  271.83  5020.1  277.28  5027.3  278.16  5067.2  279.36
  5164.2   279.1  5219.4  280.05  5288.5  284.43    5332  285.96  5386.4  286.65
#Mann= 8 ,-1 , 0
  4533.9     .07       0  4577.3    .063       0  4606.2     .07       0
  4865.9     .12       0  4994.4     .05       0  5001.4     .12       0
  5164.2    .035       0  5219.4     .05       0
Bank Sta=4994.4,5001.4
XS Rating Curve= 0 ,0
Exp/Cntr=0.3,0.1

Type RM Length L Ch R = 1 ,22476   ,446,446,446
BEGIN DESCRIPTION:
ELM SLOUGH 44.0
END DESCRIPTION:
XS GIS Cut Line= 3
      2493874.96     13730674.98        2493625.       13730525.
      2493174.98       13730425.
#Sta/Elev= 30
  4716.1  285.73  4720.7  285.76  4766.6   283.5  4782.1  283.65  4833.6  280.62
  4922.8   278.2  4941.5  277.31  4949.3  273.54  4957.1  271.09  4962.9  271.41
  4969.1  269.57  4969.6  269.07  4975.6  269.07  4976.1  269.57    4994  274.43
  4999.8  273.37  5004.7  274.84  5010.2  274.84  5017.8   275.8  5026.8  275.71
  5038.3  277.09  5048.6  277.33  5094.2  275.89  5161.3  275.93  5202.2  278.29
  5211.2  278.04  5293.8  280.81  5357.2  282.54  5386.6  283.92  5468.6  285.16
#Mann= 8 ,-1 , 0
  4716.1    .063       0  4720.7     .05       0  4833.6     .07       0
  4922.8     .12       0  4969.1     .05       0  4976.1     .12       0
  5094.2    .035       0  5293.8     .05       0
Bank Sta=4969.1,4976.1
XS Rating Curve= 0 ,0
Exp/Cntr=0.3,0.1

Type RM Length L Ch R = 1 ,22030   ,383,383,383
BEGIN DESCRIPTION:
ELM SLOUGH 43.0
END DESCRIPTION:
XS GIS Cut Line= 3
      2494025.04     13730425.03        2493675.       13730175.
      2493324.98     13729974.99
#Sta/Elev= 30
  4569.7  286.09  4582.3  285.58    4598  285.21  4606.6  283.18  4628.2  283.99
  4648.4  282.65  4655.8  282.94  4713.5  280.01  4758.7  278.67  4827.8  276.66
  4835.2  275.84  4864.7  276.26  4935.1  275.36  4986.3  275.41  5002.7  274.68
  5007.8  273.25  5013.5  269.49  5025.8  268.18  5026.3  267.68  5032.9  268.18
  5045.2  271.73    5051  274.61  5082.5  276.76  5153.2  279.55    5169  279.51
  5174.8  283.05  5184.1  283.16  5196.4  281.77  5242.8  282.03    5403  283.41
#Mann= 9 ,-1 , 0
  4569.7     .05       0  4582.3    .035       0  4628.2     .07       0
  4758.7    .035       0  4935.1     .12       0  5025.8     .05       0
  5032.9     .12       0  5082.5     .07       0  5242.8     .05       0
Bank Sta=5025.8,5032.9
XS Rating Curve= 0 ,0
Exp/Cntr=0.3,0.1

Type RM Length L Ch R = 1 ,21647   ,523,523,523
BEGIN DESCRIPTION:
ELM SLOUGH 42.0
END DESCRIPTION:
XS GIS Cut Line= 3
      2494320.07      13730319.3      2493854.43     13729853.66
      2493094.41     13729819.43
#Sta/Elev= 30
    4333  293.82  4530.5  284.98  4615.4  282.34  4622.5  280.08  4627.5  280.13
  4643.7  280.96    4666   280.1    4721  279.32  4841.7  274.24  4898.2   275.2
  4933.6  273.31    4976  274.33  5000.9   272.8    5011  270.55  5017.4  267.82
  5017.9  267.32  5024.5  267.82    5041  268.03    5061  275.78    5081  277.38
  5131.1  277.56  5211.3  280.18  5281.2  281.83  5341.3   281.7  5371.3  282.85
  5381.3  284.64  5391.3   282.9  5461.9  283.19  5734.4  284.64  5752.3  284.78
#Mann= 9 ,-1 , 0
    4333     .05       0  4627.5    .063       0    4666    .035       0
    4721     .12       0  5017.4     .05       0  5024.5     .12       0
  5211.3     .07       0  5461.9     .05       0  5734.4     .07       0
Bank Sta=5017.4,5024.5
XS Rating Curve= 0 ,0
Exp/Cntr=0.3,0.1

Type RM Length L Ch R = 1 ,21124   ,197,197,197
BEGIN DESCRIPTION:
ELM SLOUGH 41.0
END DESCRIPTION:
XS GIS Cut Line= 4
      2494284.55     13730240.16       2494171.6     13729892.43
      2494313.35     13729385.21      2494025.39     13728904.54
#Sta/Elev= 30
  4304.3  290.65  4495.6  282.09  4770.7  275.22  4775.9  276.55    4850  273.61
  4906.1  272.27    4957  273.81  4989.1  272.38  5005.5  267.37    5006  266.87
  5014.3  267.37  5020.3  267.55  5035.7  272.38  5051.4  270.01  5069.8  272.26
    5075   270.7  5082.6  271.88  5146.7  270.81  5182.7  272.99  5187.9  268.94
  5199.6  270.06  5208.7  274.25    5219  274.57  5249.3  275.82  5298.1  283.09
  5335.1  278.45  5488.2  278.52  5634.2  282.23  5648.1  284.46  5756.9  287.34
#Mann= 9 ,-1 , 0
  4304.3     .05       0  4495.6    .063       0    4850     .12       0
  5005.5     .05       0  5014.3     .12       0  5146.7    .063       0
    5219     .12       0  5249.3     .07       0  5634.2    .035       0
Bank Sta=5005.5,5014.3
XS Rating Curve= 0 ,0
Exp/Cntr=0.3,0.1

Type RM Length L Ch R = 1 ,20927   ,671,671,671
BEGIN DESCRIPTION:
ELM SLOUGH 40.0
END DESCRIPTION:
XS GIS Cut Line= 3
      2494541.49     13730164.86      2494450.43     13729525.53
      2494565.86     13728831.44
#Sta/Elev= 30
  4403.9  287.45  4501.6  285.04  4631.6  283.64  4726.6  282.41  4820.3  278.43
  4888.6  275.24  4969.4  272.98  4978.8  267.04  4979.3  266.54  4987.6  267.04
  4999.7  270.73  5047.4  272.67  5121.2   272.7  5229.8  271.36  5273.2  271.32
  5323.9   269.7  5334.1  271.33  5371.3   270.9  5411.4  273.13  5428.4  272.97
  5472.3  274.55  5477.4  273.84  5526.7  275.23  5594.1  274.59  5599.2  275.42
  5617.9  274.75  5648.3  277.15  5660.1  276.19  5668.6  277.14  5753.3  278.45
#Mann= 10 ,-1 , 0
  4403.9    .035       0  4501.6     .05       0  4631.6     .07       0
  4726.6     .12       0  4820.3     .07       0  4978.8     .05       0
  4987.6     .07       0  5229.8    .063       0  5371.3    .035       0
  5428.4    .063       0
Bank Sta=4978.8,4987.6
XS Rating Curve= 0 ,0
Exp/Cntr=0.3,0.1

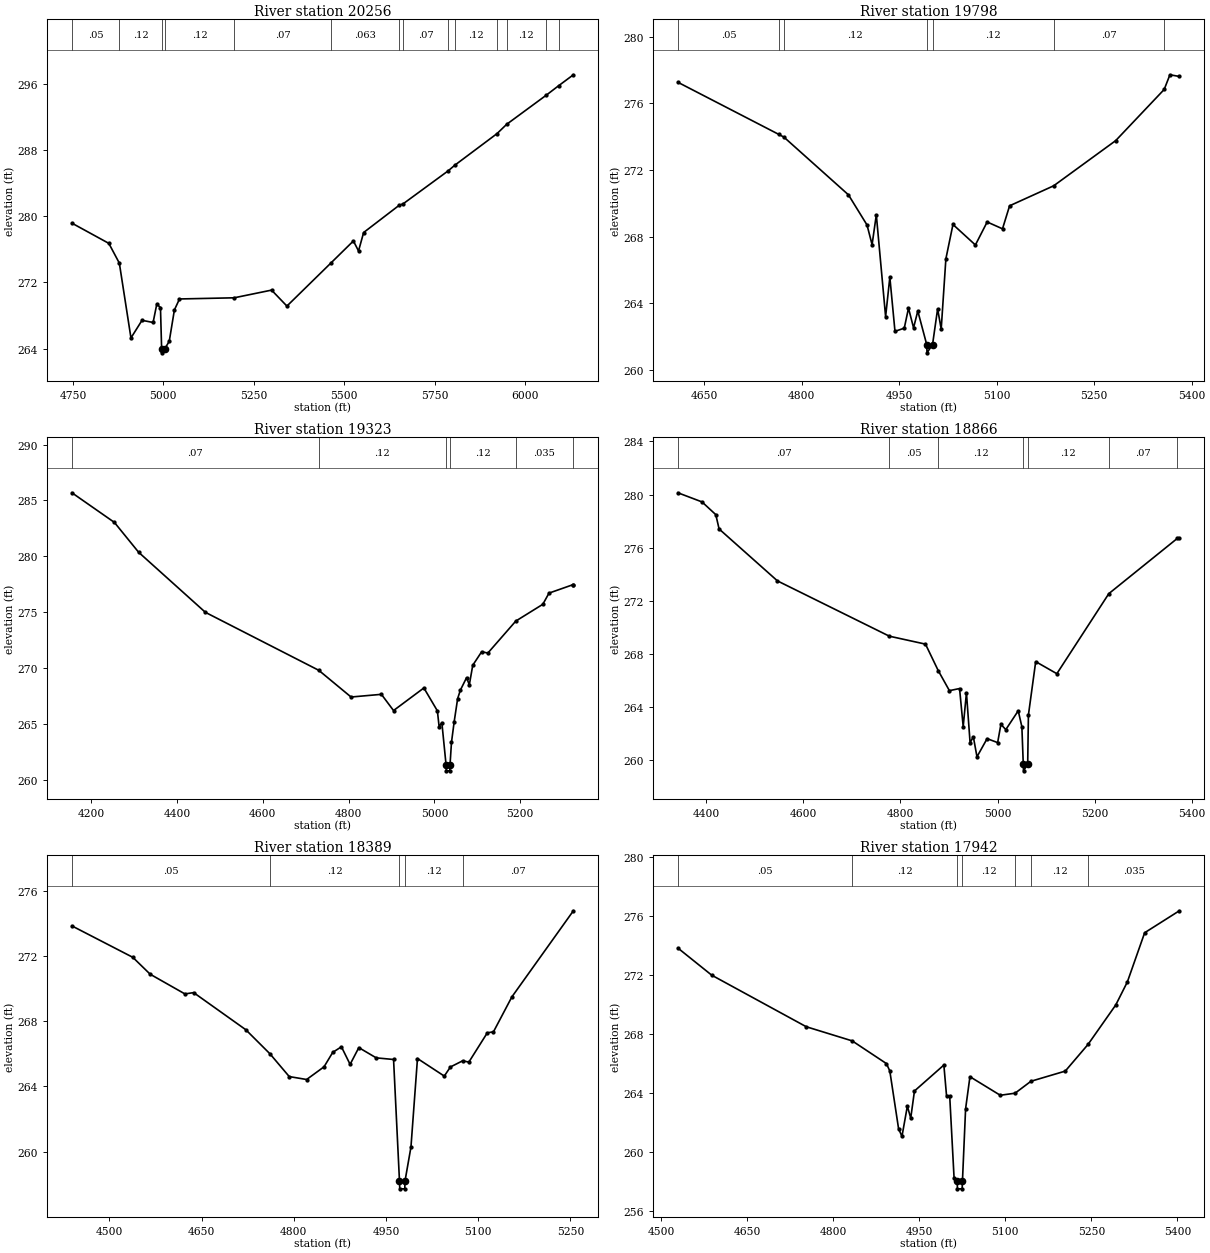
Type RM Length L Ch R = 1 ,20256   ,458,458,458
BEGIN DESCRIPTION:
ELM SLOUGH 39.0
END DESCRIPTION:
XS GIS Cut Line= 3
      2495025.01     13729475.03        2494975.       13729225.
      2494174.97     13728424.97
#Sta/Elev= 30
  4747.3  279.17  4849.3  276.73  4878.4  274.34  4910.5   265.3  4941.1  267.43
  4971.7  267.17  4981.9  269.38  4992.1  268.97  4995.3     264  4995.8   263.5
  5004.2     264  5016.4   264.9  5030.6  268.68  5044.7  270.01  5195.8  270.15
  5299.3  271.08  5341.7  269.15    5463  274.34  5525.5  277.02  5539.7  275.81
  5553.8  278.04  5651.8  281.32  5662.8   281.5  5787.2  285.48  5806.1  286.18
  5922.6  289.99  5949.4  291.12    6058  294.61  6092.7  295.77  6133.7   297.1
#Mann= 14 ,-1 , 0
  4747.3     .05       0  4878.4     .12       0  4995.3     .05       0
  5004.2     .12       0  5195.8     .07       0    5463    .063       0
  5651.8    .035       0  5662.8     .07       0  5787.2    .035       0
  5806.1     .12       0  5922.6     .07       0  5949.4     .12       0
    6058     .07       0  6092.7     .12       0
Bank Sta=4995.3,5004.2
XS Rating Curve= 0 ,0
Exp/Cntr=0.3,0.1

Type RM Length L Ch R = 1 ,19798   ,475,475,475
BEGIN DESCRIPTION:
ELM SLOUGH 38.0
END DESCRIPTION:
XS GIS Cut Line= 3
      2495324.98     13729074.98        2495025.       13728825.
      2494674.97     13728674.99
#Sta/Elev= 30
  4609.7  277.27  4765.1  274.14  4772.8  273.98    4872  270.52  4900.6  268.71
  4908.4  267.53  4914.9  269.32  4929.2  263.21  4935.7  265.58  4943.6  262.33
  4957.9  262.52  4964.4  263.72  4972.2  262.54  4978.7  263.55  4992.4  261.54
  4992.9  261.04  5001.4  261.54  5009.2  263.68  5014.7  262.46  5021.9  266.68
  5032.8  268.74  5067.3  267.51  5085.4  268.89    5109  268.48  5119.9  269.86
  5187.7  271.06  5283.1  273.77  5357.7  276.84  5366.5  277.72    5381  277.62
#Mann= 7 ,-1 , 0
  4609.7     .05       0  4765.1     .07       0  4772.8     .12       0
  4992.4     .05       0  5001.4     .12       0  5187.7     .07       0
  5357.7    .063       0
Bank Sta=4992.4,5001.4
XS Rating Curve= 0 ,0
Exp/Cntr=0.3,0.1

Type RM Length L Ch R = 1 ,19323   ,457,457,457
BEGIN DESCRIPTION:
ELM SLOUGH 37.0
END DESCRIPTION:
XS GIS Cut Line= 3
      2495724.97     13729024.97        2495125.       13728425.
      2494925.03     13728175.04
#Sta/Elev= 30
  4155.2  285.69  4254.2  283.04  4310.7  280.37  4466.3     275  4730.4  269.82
  4805.7  267.43  4876.4  267.67  4904.7  266.22  4975.4  268.24  5006.9  266.19
  5010.9  264.78  5017.3  265.14  5027.2  261.33  5027.7  260.83  5035.8  260.83
  5036.3  261.33  5039.7  263.37  5046.1  265.24  5054.1  267.29  5060.5  268.05
  5074.9  269.16  5081.3  268.52  5089.3  270.27  5110.1  271.48  5124.5  271.36
  5189.6  274.22  5252.6  275.72    5267  276.72  5321.9  277.46  5323.8  277.46
#Mann= 6 ,-1 , 0
  4155.2     .07       0  4730.4     .12       0  5027.2     .05       0
  5036.3     .12       0  5189.6    .035       0  5321.9    .063       0
Bank Sta=5027.2,5036.3
XS Rating Curve= 0 ,0
Exp/Cntr=0.3,0.1

Type RM Length L Ch R = 1 ,18866   ,477,477,477
BEGIN DESCRIPTION:
ELM SLOUGH 36.0
END DESCRIPTION:
XS GIS Cut Line= 3
      2495825.03     13728775.03        2495325.       13728325.
      2495124.99     13728024.98
#Sta/Elev= 30
  4341.4  280.13  4391.1  279.44  4419.5  278.48  4426.3   277.4  4546.6  273.48
  4777.1  269.31  4851.6  268.71  4877.9  266.71  4900.9   265.2  4921.8  265.36
  4929.3  262.49    4936  265.04  4943.5  261.27  4950.2  261.72  4957.7  260.21
  4978.6  261.58  5000.3  261.28    5007  262.66  5017.1  262.26  5042.7  263.68
  5050.2  262.48  5053.1  259.65  5053.6  259.15  5062.2  259.65  5063.7  263.36
  5078.7  267.39  5122.3  266.48  5229.4  272.52  5370.6  276.69  5374.7  276.72
#Mann= 7 ,-1 , 0
  4341.4     .07       0  4777.1     .05       0  4877.9     .12       0
  5053.1     .05       0  5062.2     .12       0  5229.4     .07       0
  5370.6    .035       0
Bank Sta=5053.1,5062.2
XS Rating Curve= 0 ,0
Exp/Cntr=0.3,0.1

Type RM Length L Ch R = 1 ,18389   ,447,447,447
BEGIN DESCRIPTION:
ELM SLOUGH 35.0
END DESCRIPTION:
XS GIS Cut Line= 3
      2495924.99     13728324.99        2495525.       13727925.
      2495274.97       13727925.
#Sta/Elev= 30
  4439.1  273.87  4538.1  271.94  4566.4   270.9  4622.9  269.69  4637.1  269.77
  4721.9  267.49  4761.2  266.01  4792.6  264.61  4820.9  264.43  4849.2  265.21
  4863.4   266.1  4877.5  266.44  4891.6  265.36  4905.8  266.39  4934.1  265.76
  4962.3  265.66  4971.9  258.21  4972.4  257.71  4980.5  257.71    4981  258.21
  4990.6  260.28  5001.2  265.72  5044.8  264.64  5054.8   265.2  5074.7  265.58
  5084.8   265.5  5114.8   267.3  5124.8  267.36  5154.8  269.51  5254.8   274.8
#Mann= 5 ,-1 , 0
  4439.1     .05       0  4761.2     .12       0  4971.9     .05       0
    4981     .12       0  5074.7     .07       0
Bank Sta=4971.9,4981
XS Rating Curve= 0 ,0
Exp/Cntr=0.3,0.1

Type RM Length L Ch R = 1 ,17942   ,447,447,447
BEGIN DESCRIPTION:
ELM SLOUGH 34.0
END DESCRIPTION:
XS GIS Cut Line= 3
      2496174.99       13727825.        2495775.       13727575.
        2495375.       13727625.
#Sta/Elev= 30
  4528.7  273.82  4587.7  271.98  4752.7  268.48  4832.8  267.52  4892.5  265.98
  4898.4  265.48  4913.7  261.56  4919.6  261.04    4929  263.09  4934.9  262.28
  4941.4  264.12  4992.7  265.88  4997.4  263.78  5002.9  263.78  5010.5  258.22
  5015.9  257.98  5016.4  257.48  5024.6  257.48  5025.1  257.98  5030.6  262.91
  5038.2  265.09  5091.1  263.83  5116.9  263.97  5144.6  264.78  5204.5  265.47
  5244.2  267.28  5292.6  269.96  5312.8  271.52    5343  274.86  5403.5  276.35
#Mann= 7 ,-1 , 0
  4528.7     .05       0  4832.8     .12       0  5015.9     .05       0
  5025.1     .12       0  5116.9    .035       0  5144.6     .12       0
  5244.2    .035       0
Bank Sta=5015.9,5025.1
XS Rating Curve= 0 ,0
Exp/Cntr=0.3,0.1