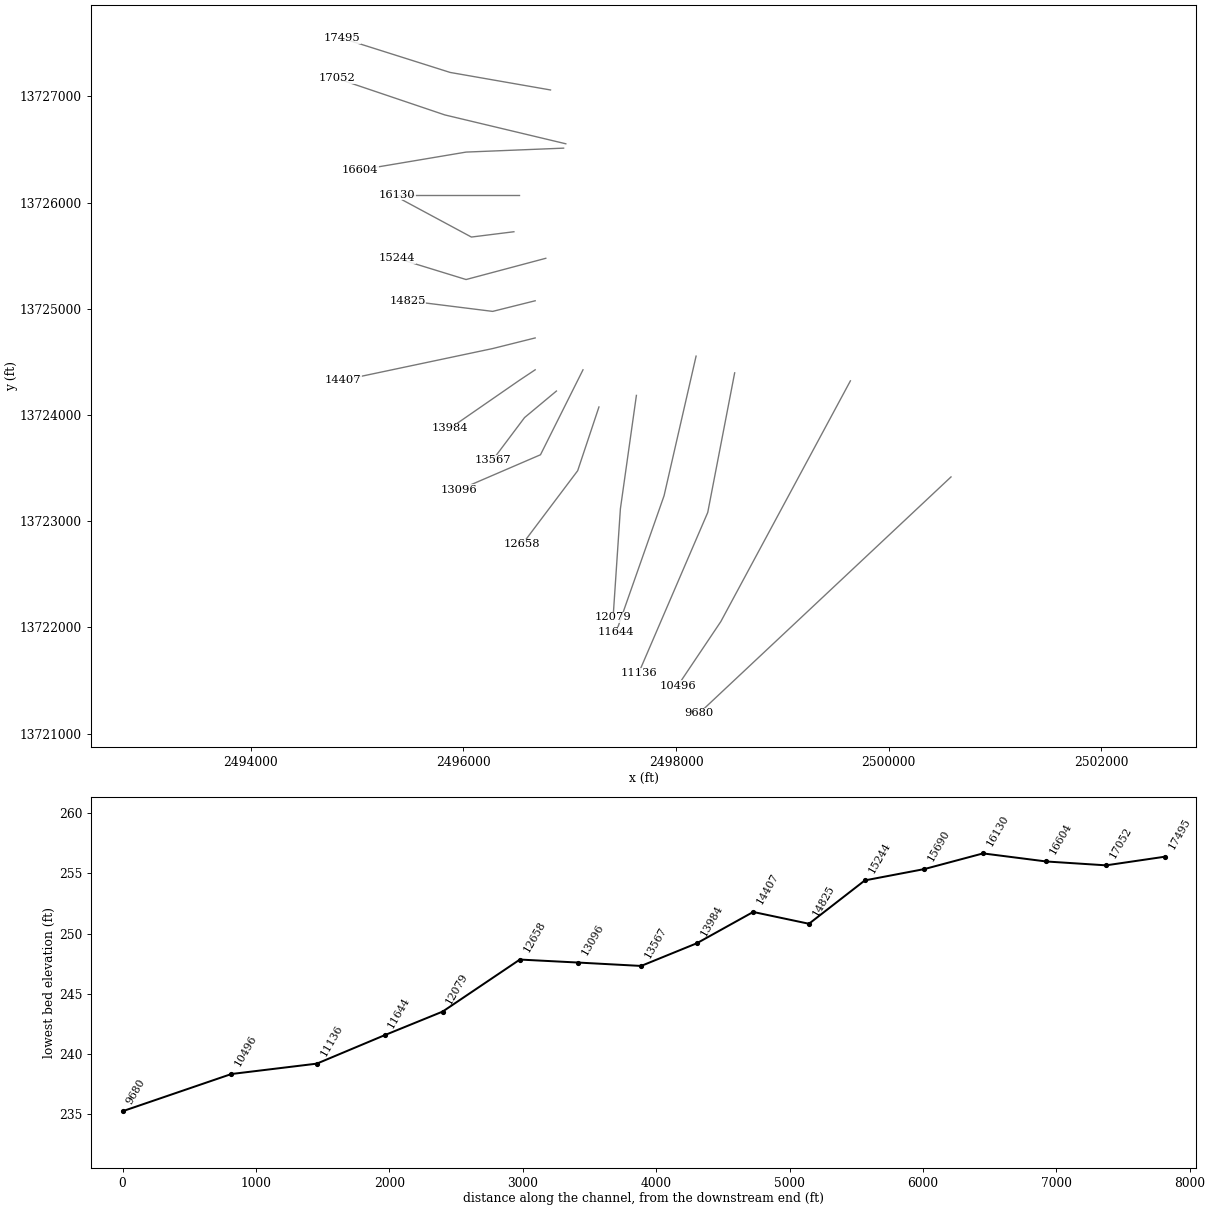
HEC-RAS study ELM SLOUGH.prj: ELM SLOUGH Base Level Engineering

--- ELM SLOUGH.g01 (geometry) --- (continued)

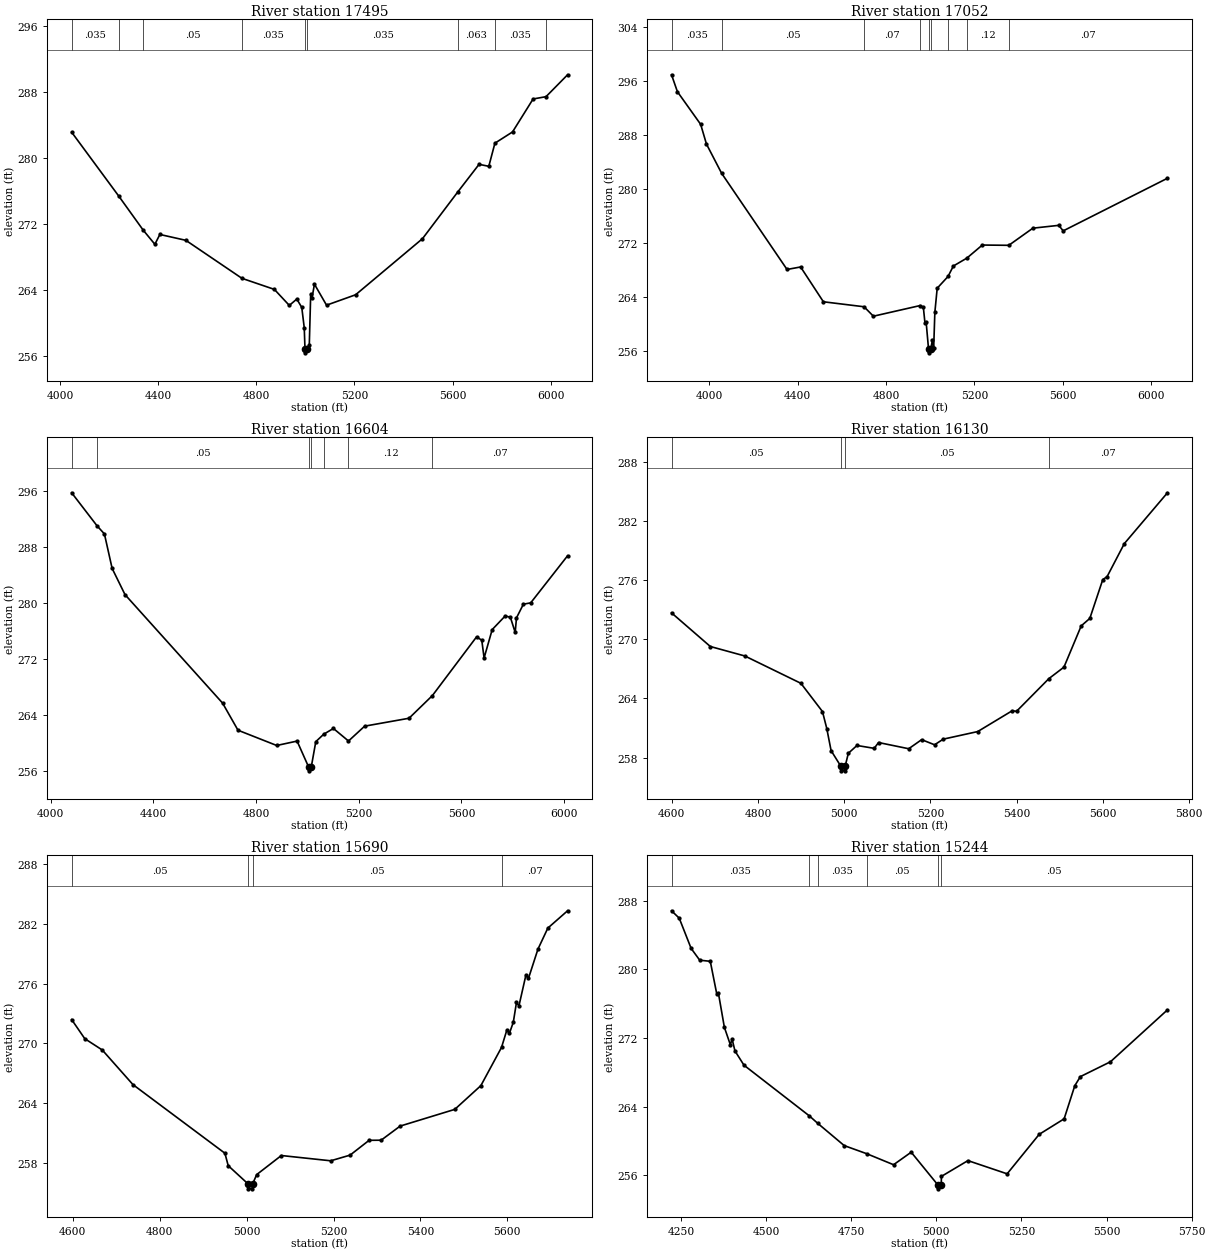
Type RM Length L Ch R = 1 ,17495   ,443,443,443
BEGIN DESCRIPTION:
ELM SLOUGH 33.0
END DESCRIPTION:
XS GIS Cut Line= 3
      2496819.34     13727059.91        2495875.       13727225.
      2494860.98     13727546.08
#Sta/Elev= 30
  4046.6   283.1  4238.3  275.38  4338.7  271.23    4386  269.53  4406.3  270.72
  4512.3  270.01    4741  265.41  4873.3  264.07  4934.2  262.13  4964.7   262.9
    4985  261.89  4995.1  259.43  4998.1  256.89  4998.6  256.39  5007.4  256.89
  5015.7  257.39  5021.4  263.48  5026.7  263.03  5036.7   264.7    5086  262.16
  5204.6  263.42  5477.3  270.21  5621.5  275.88    5708  279.21  5747.7  278.97
  5772.6  281.77  5844.4  283.13  5928.3  287.12    5981   287.4  6068.9  290.05
#Mann= 9 ,-1 , 0
  4046.6    .035       0  4238.3     .07       0  4338.7     .05       0
    4741    .035       0  4998.1    .035       0  5007.4    .035       0
  5621.5    .063       0  5772.6    .035       0    5981    .063       0
Bank Sta=4998.1,5007.4
XS Rating Curve= 0 ,0
Exp/Cntr=0.3,0.1

Type RM Length L Ch R = 1 ,17052   ,448,448,448
BEGIN DESCRIPTION:
ELM SLOUGH 32.0
END DESCRIPTION:
XS GIS Cut Line= 3
      2496963.18     13726553.19        2495825.       13726825.
      2494808.14     13727168.82
#Sta/Elev= 30
  3829.7  296.89  3856.3  294.38  3961.5  289.54  3987.7  286.62  4056.4  282.28
  4352.2  268.03  4413.7   268.4  4516.7  263.24  4700.7   262.5  4742.9   261.1
  4954.6  262.68    4969  262.41  4976.3  260.07  4981.4  260.29  4992.6  256.17
  4993.1  255.67    5002  256.17  5010.3  257.62  5015.6  256.32    5021  261.68
  5031.6  265.25  5080.6  266.99  5104.7  268.54  5165.7  269.71  5235.7  271.65
  5355.6  271.61  5464.4  274.15  5581.6  274.57  5601.6  273.75  6073.3  281.55
#Mann= 9 ,-1 , 0
  3829.7    .035       0  4056.4     .05       0  4700.7     .07       0
  4954.6     .12       0  4992.6     .05       0    5002     .12       0
  5080.6     .07       0  5165.7     .12       0  5355.6     .07       0
Bank Sta=4992.6,5002
XS Rating Curve= 0 ,0
Exp/Cntr=0.3,0.1

Type RM Length L Ch R = 1 ,16604   ,474,474,474
BEGIN DESCRIPTION:
ELM SLOUGH 31.0
END DESCRIPTION:
XS GIS Cut Line= 3
      2496942.61     13726512.11        2496025.       13726475.
      2495025.34     13726306.68
#Sta/Elev= 30
  4081.6   295.7  4180.4  290.99  4209.3  289.82  4239.3   284.9  4289.4  281.16
  4669.7  265.66  4729.7  261.79  4880.5  259.61  4959.9  260.24  5005.4  256.49
  5005.9  255.99  5014.9  256.49  5032.8  260.16    5064  261.23  5101.4  262.04
  5160.2  260.25  5223.1  262.37    5396   263.5  5487.1  266.74  5659.1  275.12
  5679.4  274.65  5688.5  272.11    5720  276.16  5770.7  278.11  5790.9  277.92
  5809.6  275.76  5814.7  277.84  5841.6  279.79  5870.1  279.98  6013.7   286.7
#Mann= 7 ,-1 , 0
  4081.6    .035       0  4180.4     .05       0  5005.4     .05       0
  5014.9     .05       0    5064     .07       0  5160.2     .12       0
  5487.1     .07       0
Bank Sta=5005.4,5014.9
XS Rating Curve= 0 ,0
Exp/Cntr=0.3,0.1

Type RM Length L Ch R = 1 ,16130   ,440,440,440
BEGIN DESCRIPTION:
ELM SLOUGH 30.0
END DESCRIPTION:
XS GIS Cut Line= 3
      2496524.97       13726075.        2496125.       13726075.
      2495374.97       13726075.
#Sta/Elev= 30
  4599.7  272.67  4689.7  269.26  4769.7   268.3  4899.7  265.53  4949.7  262.67
  4959.7  260.95  4969.7  258.71  4991.8  257.16  4992.3  256.66    5002  256.66
  5002.5  257.16  5009.7  258.44  5029.7  259.23  5069.7  258.94  5079.7  259.53
  5149.7   258.9  5179.7  259.82  5209.7   259.3  5229.7  259.87  5309.7  260.64
  5389.7  262.75  5399.7  262.69  5474.6     266  5509.7  267.17  5549.7  271.35
  5569.7  272.11  5599.7  276.04  5609.7  276.34  5649.7  279.69  5749.7  284.84
#Mann= 4 ,-1 , 0
  4599.7     .05       0  4991.8     .05       0  5002.5     .05       0
  5474.6     .07       0
Bank Sta=4991.8,5002.5
XS Rating Curve= 0 ,0
Exp/Cntr=0.3,0.1

Type RM Length L Ch R = 1 ,15690   ,446,446,446
BEGIN DESCRIPTION:
ELM SLOUGH 29.0
END DESCRIPTION:
XS GIS Cut Line= 3
      2496474.98       13725725.        2496075.       13725675.
      2495425.03     13726024.98
#Sta/Elev= 30
  4597.3  272.38  4627.5  270.46  4667.8  269.32  4738.4  265.84    4950  258.94
  4957.6  257.69  5003.2  255.86  5003.7  255.36  5013.4  255.36  5013.9  255.86
  5023.1  256.79  5079.9  258.71  5193.5  258.18  5238.1  258.75  5281.9  260.24
  5309.5  260.25  5353.3  261.67    5479  263.35  5539.1  265.74  5586.6  269.58
  5599.1  271.36  5604.8     271  5613.7  272.11    5621   274.1  5626.7  273.76
  5642.9  276.89  5648.6  276.52  5670.5  279.47  5693.2  281.58  5738.6  283.32
#Mann= 4 ,-1 , 0
  4597.3     .05       0  5003.2     .05       0  5013.9     .05       0
  5586.6     .07       0
Bank Sta=5003.2,5013.9
XS Rating Curve= 0 ,0
Exp/Cntr=0.3,0.1

Type RM Length L Ch R = 1 ,15244   ,419,419,419
BEGIN DESCRIPTION:
ELM SLOUGH 28.0
END DESCRIPTION:
XS GIS Cut Line= 3
      2496774.99       13725475.        2496025.       13725275.
      2495374.98     13725475.01
#Sta/Elev= 30
  4222.6  286.83  4245.2  285.97  4280.2  282.44  4305.4  281.07  4336.4  280.94
  4355.2  277.18  4360.4   277.2  4377.8  273.24  4395.3  271.22  4400.5  271.87
  4408.9  270.49  4435.4  268.83  4627.4  262.92  4651.5  262.07  4729.7  259.46
  4796.1  258.51  4874.6  257.23  4926.4  258.69  5003.8  254.92  5004.3  254.42
  5014.7  254.92  5015.1  255.87    5093  257.71  5208.1  256.17  5302.2  260.77
  5375.5  262.58  5406.8  266.44  5423.2   267.5  5511.5  269.23  5678.9  275.28
#Mann= 6 ,-1 , 0
  4222.6    .035       0  4627.4     .07       0  4651.5    .035       0
  4796.1     .05       0  5003.8     .05       0  5014.7     .05       0
Bank Sta=5003.8,5014.7
XS Rating Curve= 0 ,0
Exp/Cntr=0.3,0.1

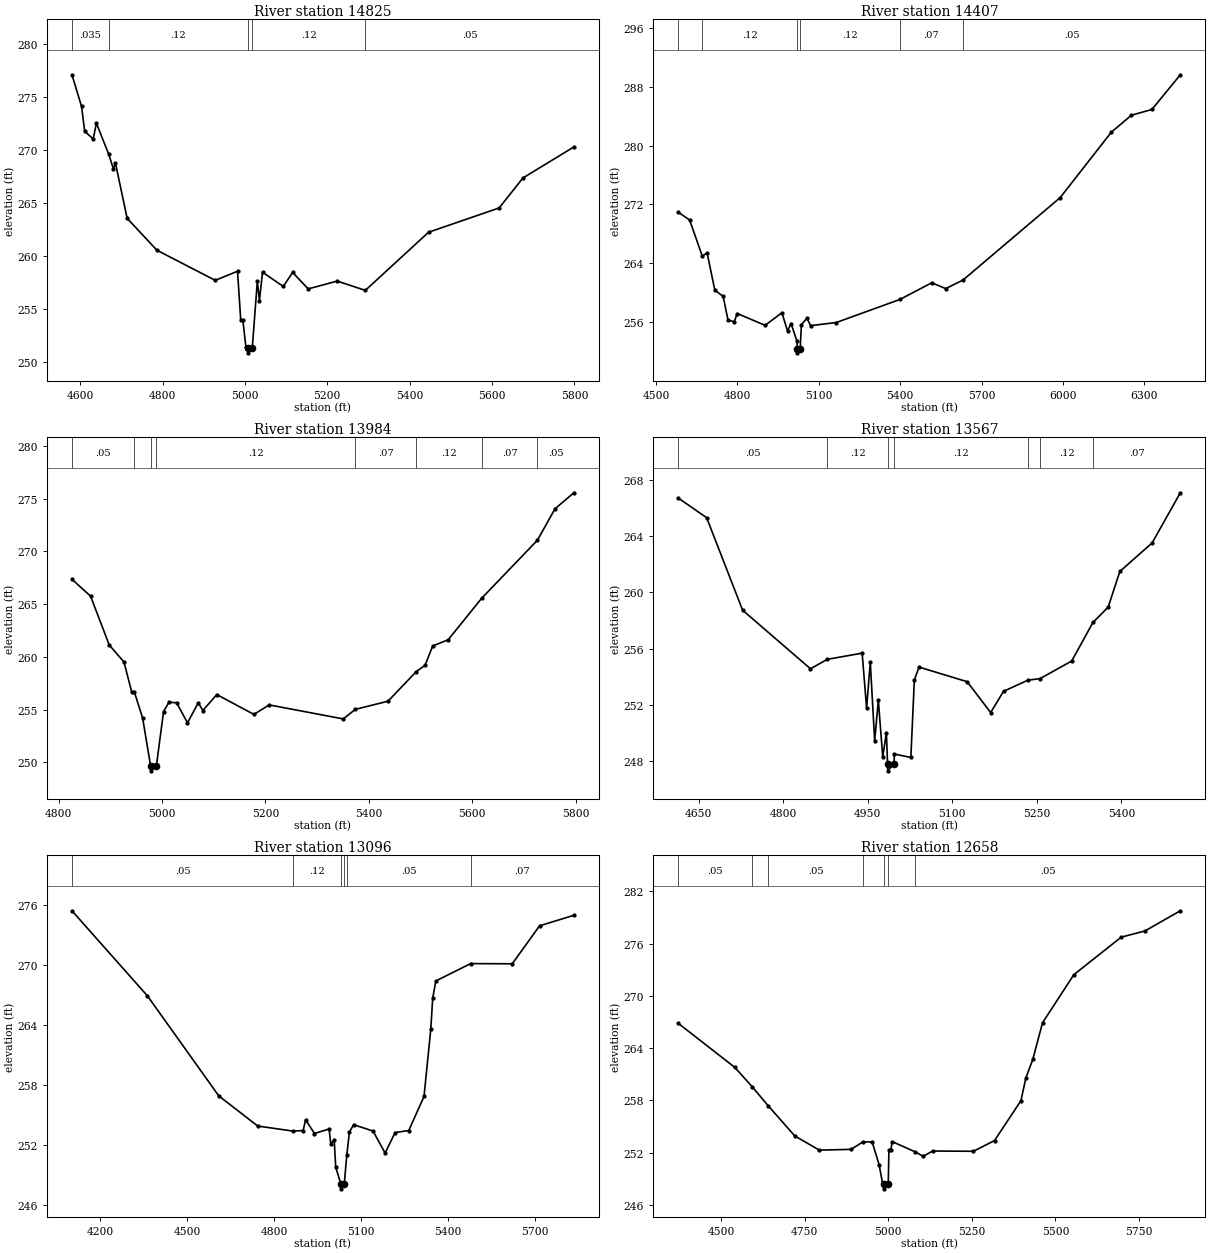
Type RM Length L Ch R = 1 ,14825   ,418,418,418
BEGIN DESCRIPTION:
ELM SLOUGH 27.0
END DESCRIPTION:
XS GIS Cut Line= 3
      2496675.03     13725075.01        2496275.       13724975.
      2495474.97       13725075.
#Sta/Elev= 30
  4580.1  277.13  4603.3  274.15  4611.1  271.78  4631.7  271.06  4639.4  272.55
  4669.4  269.61  4680.6  268.24  4685.8  268.76  4714.1  263.55  4786.3  260.53
    4928  257.68  4982.1  258.54  4989.9  253.93    4995  253.93  5002.5  251.36
  5007.1  251.32  5007.6  250.82    5018  251.32  5030.2   257.6  5035.3  255.77
  5042.8  258.45  5093.2   257.1  5115.9  258.43  5153.7  256.87  5224.2  257.61
  5292.4  256.73  5445.9  262.23  5617.3  264.53  5675.2  267.37  5798.7   270.3
#Mann= 5 ,-1 , 0
  4580.1    .035       0  4669.4     .12       0  5007.1     .05       0
    5018     .12       0  5292.4     .05       0
Bank Sta=5007.1,5018
XS Rating Curve= 0 ,0
Exp/Cntr=0.3,0.1

Type RM Length L Ch R = 1 ,14407   ,423,423,423
BEGIN DESCRIPTION:
ELM SLOUGH 26.0
END DESCRIPTION:
XS GIS Cut Line= 3
      2496675.02     13724725.01        2496275.       13724625.
      2494868.96     13724328.01
#Sta/Elev= 30
    4583  270.91  4624.3  269.87    4671  264.95  4688.7  265.41    4717  260.34
  4747.9  259.47    4766  256.21  4789.2  256.05  4799.5  257.15  4902.6  255.54
  4964.4  257.26    4985  254.78  4997.9  255.78  5020.2  253.36  5020.4   252.3
  5020.9   251.8  5031.6   252.3  5036.2  255.64  5056.7   256.5    5070   255.5
  5164.3  255.92    5399  259.06  5516.6  261.33  5567.7  260.54  5631.3  261.69
  5989.6  272.91  6178.3  281.82  6252.5  284.12  6327.6   284.9  6432.4  289.62
#Mann= 6 ,-1 , 0
    4583    .035       0    4671     .12       0  5020.4     .05       0
  5031.6     .12       0    5399     .07       0  5631.3     .05       0
Bank Sta=5020.4,5031.6
XS Rating Curve= 0 ,0
Exp/Cntr=0.3,0.1

Type RM Length L Ch R = 1 ,13984   ,417,417,417
BEGIN DESCRIPTION:
ELM SLOUGH 25.0
END DESCRIPTION:
XS GIS Cut Line= 3
      2496674.97     13724424.98        2496525.       13724325.
      2495875.01       13723875.
#Sta/Elev= 30
  4825.9  267.36  4861.9  265.76    4898  261.13  4926.5  259.52  4941.5  256.67
  4946.6  256.67  4962.6  254.21  4977.9   249.7  4978.4   249.2  4989.3   249.7
  5003.1  254.82  5013.6  255.71  5028.4  255.65  5049.4  253.75  5070.3  255.66
  5079.1  254.92  5106.1  256.43  5177.8  254.55  5207.5  255.45  5350.7  254.12
    5374  255.03  5437.2   255.8  5491.5  258.59  5508.9  259.21  5523.7  261.04
  5553.5  261.62  5618.4  265.56  5726.3  271.07  5760.2  274.04  5796.7  275.56
#Mann= 8 ,-1 , 0
  4825.9     .05       0  4946.6     .12       0  4977.9     .05       0
  4989.3     .12       0    5374     .07       0  5491.5     .12       0
  5618.4     .07       0  5726.3     .05       0
Bank Sta=4977.9,4989.3
XS Rating Curve= 0 ,0
Exp/Cntr=0.3,0.1

Type RM Length L Ch R = 1 ,13567   ,471,471,471
BEGIN DESCRIPTION:
ELM SLOUGH 24.0
END DESCRIPTION:
XS GIS Cut Line= 3
      2496874.98     13724224.98        2496575.       13723975.
      2496274.99     13723574.99
#Sta/Elev= 30
    4614  266.69  4664.1   265.3  4727.9  258.73  4848.3  254.57  4878.2  255.24
    4940  255.68  4947.9  251.77  4954.4  255.05  4962.2  249.45  4968.7  252.33
  4976.5  248.32    4983  250.02  4985.1  247.82  4985.6  247.32  4996.5  247.82
  4997.3  248.51  5026.4  248.27  5032.6  253.77  5040.9  254.69  5126.4  253.65
    5168  251.46  5190.9  252.97  5234.1  253.76  5255.6  253.87  5311.8  255.12
  5349.6  257.87  5376.4  258.94  5397.2  261.48  5454.5  263.51  5504.5  267.07
#Mann= 7 ,-1 , 0
    4614     .05       0  4878.2     .12       0  4985.1     .05       0
  4996.5     .12       0  5234.1     .07       0  5255.6     .12       0
  5349.6     .07       0
Bank Sta=4985.1,4996.5
XS Rating Curve= 0 ,0
Exp/Cntr=0.3,0.1

Type RM Length L Ch R = 1 ,13096   ,438,438,438
BEGIN DESCRIPTION:
ELM SLOUGH 23.0
END DESCRIPTION:
XS GIS Cut Line= 3
      2497125.01     13724425.01        2496725.       13723625.
      2495958.32     13723294.55
#Sta/Elev= 30
  4103.5  275.45  4363.5  266.93  4609.4  256.91  4743.6  253.89  4866.1  253.38
  4900.1  253.44  4908.5  254.52  4939.2  253.14  4989.6   253.6  4995.1  252.11
    5007  252.49  5012.4  249.76    5030   248.1  5030.5   247.6  5041.8   248.1
  5050.5  250.99  5059.5   253.3  5074.2  254.02  5140.9  253.39  5182.5  251.18
  5216.9  253.24    5264  253.44  5316.5  256.85    5340  263.62  5346.4  266.68
  5357.3  268.42  5477.3  270.16  5620.5  270.14  5714.6  273.94  5832.8     275
#Mann= 6 ,-1 , 0
  4103.5     .05       0  4866.1     .12       0    5030     .05       0
  5041.8     .12       0  5050.5     .05       0  5477.3     .07       0
Bank Sta=5030,5041.8
XS Rating Curve= 0 ,0
Exp/Cntr=0.3,0.1

Type RM Length L Ch R = 1 ,12658   ,579,579,579
BEGIN DESCRIPTION:
ELM SLOUGH 22.0
END DESCRIPTION:
XS GIS Cut Line= 3
      2497275.01     13724075.04        2497075.       13723475.
      2496552.33     13722780.25
#Sta/Elev= 30
  4371.8  266.83  4540.5  261.79  4592.3  259.58  4640.8  257.37  4719.7  253.93
  4793.5  252.29  4888.3  252.38  4923.3  253.22  4951.6  253.24  4972.7  250.56
  4983.2  248.37  4987.8  248.35  4988.3  247.85  4999.7  248.35  5001.7  252.31
  5007.4  252.31  5011.6  253.27  5079.3  252.11  5104.4  251.58  5132.4  252.19
  5254.6  252.16  5317.7  253.39  5396.8  257.97  5411.4  260.57  5432.2   262.7
  5461.4  266.91  5554.9  272.42  5696.7  276.73  5767.6  277.44  5873.7  279.76
#Mann= 7 ,-1 , 0
  4371.8     .05       0  4592.3     .12       0  4640.8     .05       0
  4923.3     .12       0  4987.8     .05       0  4999.7     .12       0
  5079.3     .05       0
Bank Sta=4987.8,4999.7
XS Rating Curve= 0 ,0
Exp/Cntr=0.3,0.1

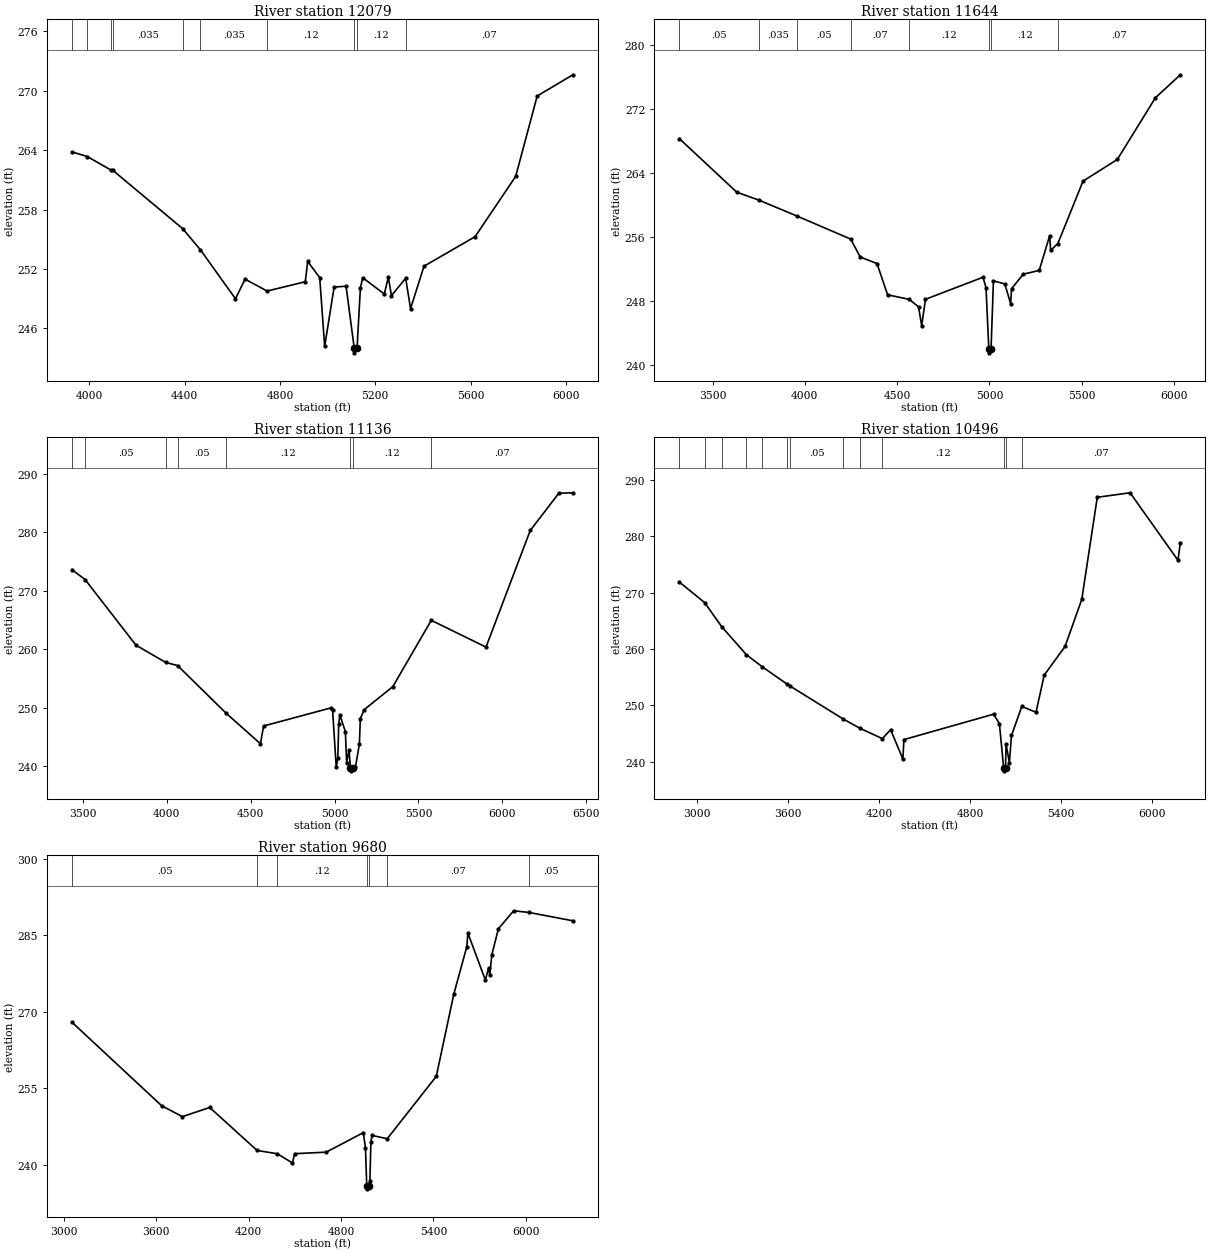
Type RM Length L Ch R = 1 ,12079   ,435,435,435
BEGIN DESCRIPTION:
ELM SLOUGH 21.0
END DESCRIPTION:
XS GIS Cut Line= 3
      2497627.38     13724183.99      2497476.73     13723115.77
      2497408.25     13722095.46
#Sta/Elev= 30
  3927.8  263.82  3992.3  263.35  4092.4  261.97  4098.1  261.98  4391.6  256.08
  4466.4  253.94  4613.5  248.99  4653.9  250.97  4746.2  249.77  4906.4  250.71
  4916.5  252.76    4967  251.12  4987.7  244.18  5027.4  250.17  5077.5  250.26
  5111.6  244.03  5112.1  243.53  5123.7  244.03  5137.7  250.12  5147.7  251.11
  5237.9  249.47  5254.7  251.17  5267.9  249.31  5327.5  251.06  5348.1     248
  5404.5  252.28  5618.7  255.26  5789.1  261.35  5879.3  269.47  6029.2  271.61
#Mann= 10 ,-1 , 0
  3927.8    .035       0  3992.3     .05       0  4092.4     .07       0
  4098.1    .035       0  4391.6     .07       0  4466.4    .035       0
  4746.2     .12       0  5111.6     .05       0  5123.7     .12       0
  5327.5     .07       0
Bank Sta=5111.6,5123.7
XS Rating Curve= 0 ,0
Exp/Cntr=0.3,0.1

Type RM Length L Ch R = 1 ,11644   ,508,508,508
BEGIN DESCRIPTION:
X19151
END DESCRIPTION:
XS GIS Cut Line= 3
      2498188.86     13724553.72      2497887.58     13723239.03
      2497435.65     13721951.72
#Sta/Elev= 30
    3321  268.28  3630.9  261.62  3751.4  260.62  3955.4  258.66  4248.5  255.76
  4300.1  253.52    4391  252.71  4448.2  248.81  4565.4  248.24  4615.8  247.31
  4632.9  244.95  4653.4  248.25  4964.9     251  4981.4   249.7  4996.5  242.07
    4997  241.57  5008.7  242.07  5021.6  250.56  5083.6  250.16  5114.6   247.7
  5119.9  249.57  5182.8  251.38  5269.5  251.85  5326.2  256.19  5331.5  254.35
  5370.5  255.21  5506.9  262.99  5692.8   265.7  5899.2   273.4  6034.1  276.26
#Mann= 8 ,-1 , 0
    3321     .05       0  3751.4    .035       0  3955.4     .05       0
  4248.5     .07       0  4565.4     .12       0  4996.5     .05       0
  5008.7     .12       0  5370.5     .07       0
Bank Sta=4996.5,5008.7
XS Rating Curve= 0 ,0
Exp/Cntr=0.3,0.1

Type RM Length L Ch R = 1 ,11136   ,640,640,640
BEGIN DESCRIPTION:
X19150
END DESCRIPTION:
XS GIS Cut Line= 3
      2498551.77      13724396.2      2498298.42     13723081.54
      2497648.28      13721569.1
#Sta/Elev= 30
  3435.3  273.56  3513.1  271.89  3816.5  260.67  3993.4  257.73  4064.1   257.2
  4354.9  249.02  4558.1  243.84  4577.1  246.87  4977.7  249.96  4988.1   249.6
  5009.8  239.85  5019.3  241.42  5024.8  247.23  5031.6  248.74  5064.3  245.91
  5071.9  240.54    5086   242.8  5094.8  239.71  5095.3  239.21    5107  239.71
  5124.4  239.85  5147.9  243.79  5153.4  248.13  5176.9  249.67  5347.2   253.6
  5576.2  264.92  5902.4  260.35    6166  280.27  6336.2  286.63  6420.4  286.71
#Mann= 8 ,-1 , 0
  3435.3    .035       0  3513.1     .05       0  3993.4    .035       0
  4064.1     .05       0  4354.9     .12       0  5094.8     .05       0
    5107     .12       0  5576.2     .07       0
Bank Sta=5094.8,5107
XS Rating Curve= 0 ,0
Exp/Cntr=0.3,0.1

Type RM Length L Ch R = 1 ,10496   ,816,816,816
BEGIN DESCRIPTION:
X19149
END DESCRIPTION:
XS GIS Cut Line= 3
      2499640.52     13724320.91      2498421.68     13722054.42
      2498017.68     13721451.85
#Sta/Elev= 30
  2886.8  271.86  3052.3  268.23  3165.8  263.92  3328.1  258.96  3432.8  256.81
  3592.2  253.81  3617.4  253.37  3960.5  247.63    4074  245.93  4223.4  244.06
  4277.2  245.67  4358.2  240.45  4364.9   243.9  4955.7  248.41  4993.8  246.74
    5022  238.85  5022.5  238.35  5034.2  238.85  5037.6  243.12  5059.6   239.8
  5073.5  244.63  5141.2  249.78  5234.8  248.76  5289.2  255.36  5426.4  260.45
  5536.4   268.8  5638.5  286.93  5854.6  287.73  6169.9  275.74  6185.7  278.88
#Mann= 13 ,-1 , 0
  2886.8     .05       0  3052.3    .035       0  3165.8     .05       0
  3328.1    .035       0  3432.8     .05       0  3592.2    .035       0
  3617.4     .05       0  3960.5    .035       0    4074     .05       0
  4223.4     .12       0    5022     .05       0  5034.2     .12       0
  5141.2     .07       0
Bank Sta=5022,5034.2
XS Rating Curve= 0 ,0
Exp/Cntr=0.3,0.1

Type RM Length L Ch R = 1 ,9680    ,1178,1178,1178
BEGIN DESCRIPTION:
X19148
END DESCRIPTION:
XS GIS Cut Line= 2
      2500587.07     13723416.34      2498216.32      13721189.9
#Sta/Elev= 30
  3053.4  267.95  3635.8  251.56  3770.1  249.43  3947.4  251.23    4255  242.79
  4386.6  242.15  4484.7  240.33  4498.9  242.16    4704  242.46  4944.8  246.29
  4958.9  243.24    4967  235.76  4967.5  235.26  4979.3  235.76  4987.3  236.76
  4994.1  244.47  5001.4  245.75  5099.8  245.09  5418.6  257.34  5531.9  273.43
  5616.9  282.81  5623.7  285.47    5737  276.25  5758.5  278.66  5765.4  277.21
  5779.5  281.24    5822  286.32  5921.1  289.84  6020.6  289.51  6305.7  287.87
#Mann= 7 ,-1 , 0
  3053.4     .05       0    4255    .035       0  4386.6     .12       0
    4967     .05       0  4979.3     .12       0  5099.8     .07       0
  6020.6     .05       0
Bank Sta=4967,4979.3
XS Rating Curve= 0 ,0
Exp/Cntr=0.3,0.1