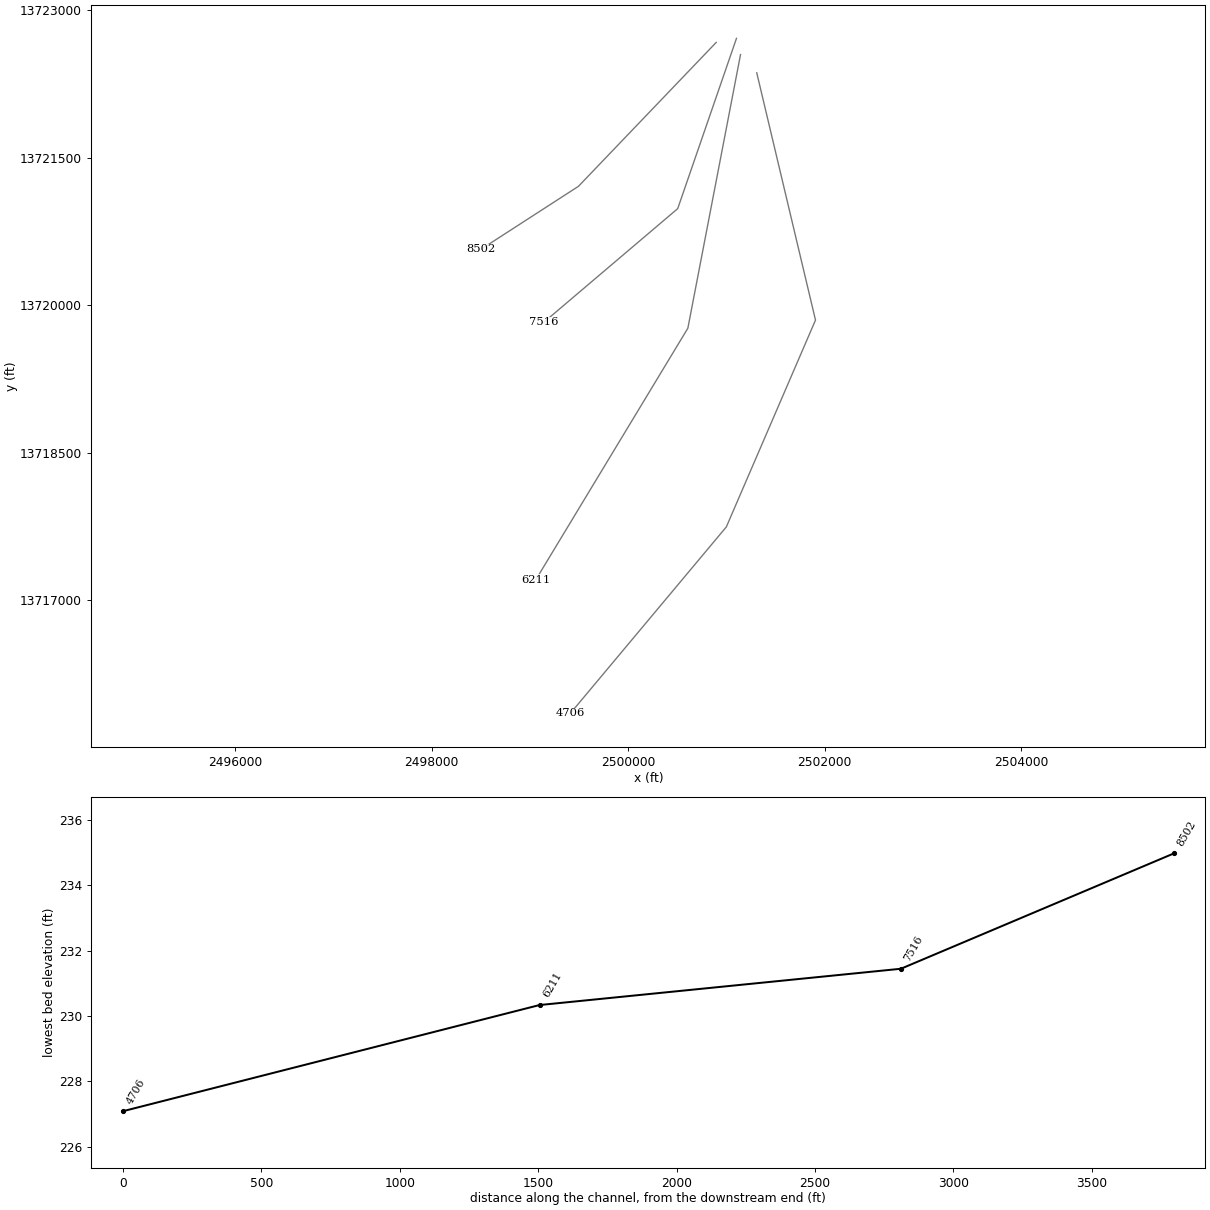
HEC-RAS study ELM SLOUGH.prj: ELM SLOUGH Base Level Engineering

--- ELM SLOUGH.g01 (geometry) --- (continued)

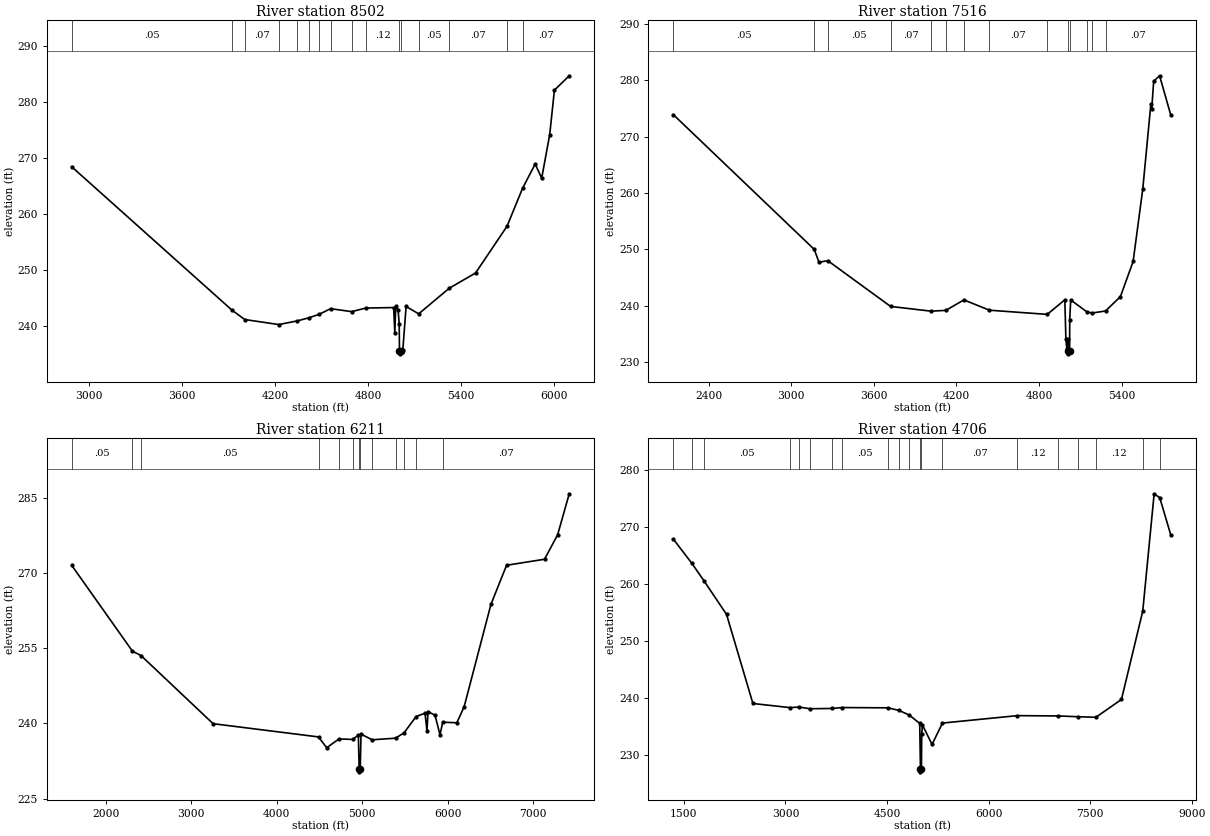
Type RM Length L Ch R = 1 ,8502    ,986,986,986
BEGIN DESCRIPTION:
X19147
END DESCRIPTION:
XS GIS Cut Line= 3
      2500896.28     13722674.13      2499494.41     13721210.41
      2498504.88     13720571.34
#Sta/Elev= 30
  2890.6   268.4  3923.5  242.77    4005  241.11  4224.6  240.21  4343.9  240.87
  4419.8  241.43    4484  242.04    4558  243.05  4693.8  242.52  4784.7  243.16
  4964.3  243.25  4971.8  238.74  4977.8  243.53  4992.9   242.8    5000  240.39
  5001.9  235.48  5002.4  234.98  5014.2  235.48  5023.3  235.66  5044.4  243.44
  5125.6  242.13  5322.3   246.7  5491.8  249.42  5694.8  257.79  5794.5  264.55
  5875.8  268.89    5918  266.37  5969.5  274.15  5999.8  282.09  6095.3  284.66
#Mann= 16 ,-1 , 0
  2890.6     .05       0  3923.5    .035       0    4005     .07       0
  4224.6     .12       0  4343.9    .035       0  4419.8     .12       0
    4484    .035       0    4558     .12       0  4693.8    .035       0
  4784.7     .12       0  5001.9     .05       0  5014.2     .12       0
  5125.6     .05       0  5322.3     .07       0  5694.8    .035       0
  5794.5     .07       0
Bank Sta=5001.9,5014.2
XS Rating Curve= 0 ,0
Exp/Cntr=0.3,0.1

Type RM Length L Ch R = 1 ,7516    ,1305,1305,1305
BEGIN DESCRIPTION:
X19146
END DESCRIPTION:
XS GIS Cut Line= 3
      2501102.46      13722715.4      2500504.59     13720983.64
      2499144.47      13719829.6
#Sta/Elev= 30
  2142.3  273.88  3165.9  249.99  3200.6  247.71  3265.1  247.97  3721.1  239.86
  4015.3  239.02  4122.4  239.16    4254  241.02  4439.5  239.19  4859.6  238.45
  4987.4  241.03  4995.2  234.05  5001.7  232.37  5009.4  234.11  5009.8  231.95
  5010.3  231.45  5022.2  231.95    5023  237.53  5030.3  241.01    5145  238.94
  5184.4  238.69  5283.3  239.05  5391.6  241.61  5483.9  247.84  5554.1  260.74
  5612.5  275.71    5619  274.91  5633.3  279.83  5676.2  280.78  5758.1  273.76
#Mann= 14 ,-1 , 0
  2142.3     .05       0  3165.9    .035       0  3265.1     .05       0
  3721.1     .07       0  4015.3     .05       0  4122.4     .07       0
    4254     .12       0  4439.5     .07       0  4859.6     .12       0
  5009.8     .05       0  5022.2     .12       0    5145     .07       0
  5184.4     .12       0  5283.3     .07       0
Bank Sta=5009.8,5022.2
XS Rating Curve= 0 ,0
Exp/Cntr=0.3,0.1

Type RM Length L Ch R = 1 ,6211    ,1505,1505,1505
BEGIN DESCRIPTION:
X19145
END DESCRIPTION:
XS GIS Cut Line= 3
      2501143.69     13722550.46      2500607.67      13719767.3
      2499061.49     13717210.93
#Sta/Elev= 30
    1600  271.56  2310.2  254.43    2411  253.55  3254.5  239.95  4487.9  237.31
  4583.7  235.15  4727.2  236.91  4889.7  236.81  4954.3  237.68  4963.5  230.84
    4964  230.34    4976  230.84  4985.3  237.86  5116.8  236.74  5389.3  237.06
  5488.3  238.12  5629.8  241.38  5734.2  242.05  5757.4   238.5  5769.3  242.37
  5851.1  241.64  5909.5  237.75  5941.6  240.24  6106.6  240.14    6192  243.33
  6505.6  263.77  6688.6  271.58  7132.9  272.78  7286.1  277.67  7421.9  285.85
#Mann= 13 ,-1 , 0
    1600     .05       0  2310.2    .035       0    2411     .05       0
  4487.9     .12       0  4727.2     .07       0  4889.7     .12       0
  4963.5     .05       0    4976     .12       0  5116.8     .07       0
  5389.3    .035       0  5488.3     .07       0  5629.8     .12       0
  5941.6     .07       0
Bank Sta=4963.5,4976
XS Rating Curve= 0 ,0
Exp/Cntr=0.3,0.1

Type RM Length L Ch R = 1 ,4706    ,0,0,0
BEGIN DESCRIPTION:
X19144
END DESCRIPTION:
XS GIS Cut Line= 4
      2501308.62     13722364.89      2501906.48     13719849.76
      2500999.37     13717746.93      2499411.92     13715850.23
#Sta/Elev= 30
  1344.1  267.88  1618.3  263.62  1795.5  260.59  2129.4  254.69  2519.2  239.07
  3064.3  238.35  3198.8  238.44  3365.9  238.15  3693.5   238.2  3833.7  238.36
    4515  238.31  4677.9  237.85  4829.6  237.04  4983.1  235.58  4993.9  227.59
  4994.4  227.09  5008.4  227.59  5012.7  233.76  5023.6  235.31  5165.2  231.89
  5319.1  235.64  6424.7  236.94  7020.8  236.89  7321.2  236.75  7585.1  236.65
  7963.2  239.78  8277.4  255.26  8445.9  275.83  8528.6  275.14  8692.8  268.57
#Mann= 20 ,-1 , 0
  1344.1     .05       0  1618.3    .035       0  1795.5     .05       0
  3064.3     .05       0  3198.8     .07       0  3365.9     .05       0
  3693.5     .07       0  3833.7     .05       0    4515     .07       0
  4677.9     .05       0  4829.6     .07       0  4993.9     .05       0
  5008.4     .12       0  5319.1     .07       0  6424.7     .12       0
  7020.8     .07       0  7321.2     .07       0  7585.1     .12       0
  8277.4     .05       0  8528.6     .05       0
Bank Sta=4993.9,5008.4
XS Rating Curve= 0 ,0
Exp/Cntr=0.3,0.1

Chan Stop Cuts=-1
Use User Specified Reach Order=0
Composite Channel Slope=5