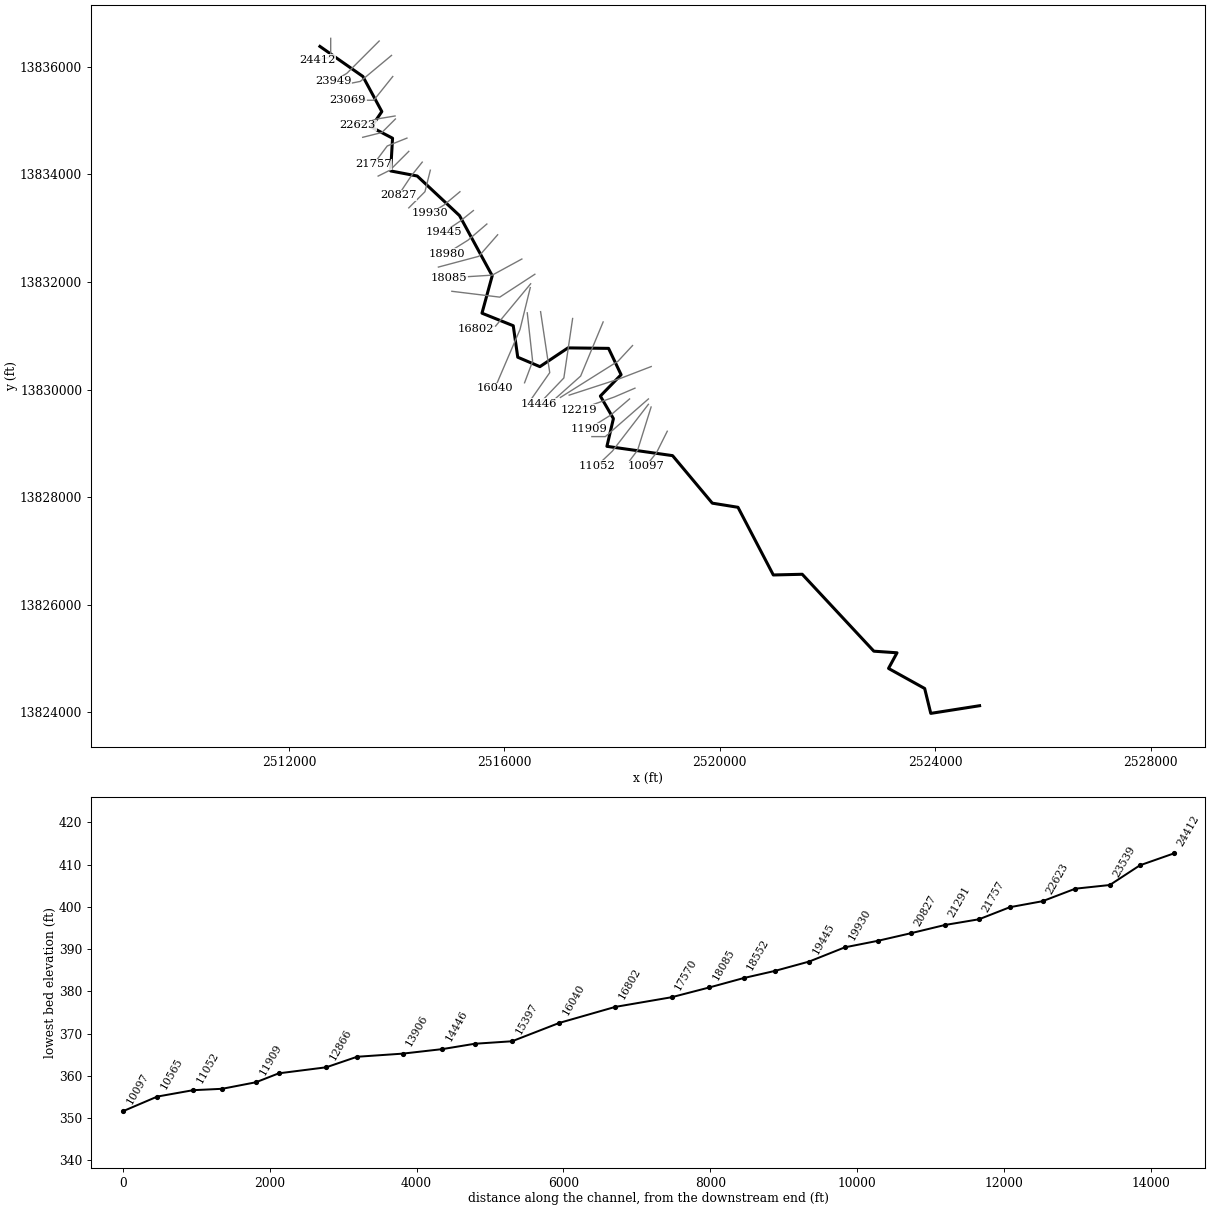
--- Elm Creek 3.prj (project) ---

Proj Title=Elm Creek 3 Base Level Engineering
Current Plan=p01
Default Exp/Contr=0.3,0.1
English Units
Geom File=g01
Flow File=f01
Plan File=p01
Y Axis Title=Elevation
X Axis Title(PF)=Main Channel Distance
X Axis Title(XS)=Station
BEGIN DESCRIPTION:
Elm Creek 3
END DESCRIPTION:
DSS Export Rating Curves= 0
DSS Export Rating Curve Sorted= 0
DSS Export Volume Flow Curves= 0
DXF OffsetX= 0
DXF OffsetY= 0
DXF ScaleX= 1
DXF ScaleY= 10

--- Elm Creek 3.p01 (plan) ---

Plan Title=Multiple Run
Short Identifier=Multiple
Geom File=g01
Flow File=f01
Subcritical Flow
K Sum by GR= 0
Std Step Tol= 0.01
Critical Tol= 0.01
Num of Std Step Trials= 20
Max Error Tol= 0.3
Flow Tol Ratio= 0.001
Split Flow NTrial= 30
Split Flow Tol= 0.02
Split Flow Ratio= 0.02
Log Output Level= 0
Friction Slope Method= 1
Unsteady Friction Slope Method= 2
Unsteady Bridges Friction Slope Method= 1
Parabolic Critical Depth
Global Vel Dist=  1 , 1 , 1
Global Log Level= 0
CheckData=True
Encroach Param= -1, 0, 0, 0
BEGIN DESCRIPTION:
Multiple Run
END DESCRIPTION:

--- Elm Creek 3.f01 (steady flow) ---

Flow Title=Multiple
Number of Profiles=7
Profile Names=10-year,25-year,50-year,1pct_min,100-year,1pct_plu,500-year
River Rch & RM= Elm Creek 3,Reach-1,24412
     556     884    1176     759    1515    3023    2486
River Rch & RM= Elm Creek 3,Reach-1,23069
     624     998    1332     862    1720    3432    2837
River Rch & RM= Elm Creek 3,Reach-1,20376
     746    1199    1608    1043    2082    4154    3455
River Rch & RM= Elm Creek 3,Reach-1,15397
    1386    2297    3143    2076    4143    8266    7132
River Rch & RM= Elm Creek 3,Reach-1,8261
    1653    2757    3788    2511    5009    9995    8682
River Rch & RM= Elm Creek 3,Reach-1,4537
    1671    2779    3809    2519    5025   10027    8667
Boundary for River Rch & Prof#=Elm Creek 3,Reach-1,1
Up Type=0
Dn Type=3
Dn Slope=0.005
Boundary for River Rch & Prof#=Elm Creek 3,Reach-1,2
Up Type=0
Dn Type=3
Dn Slope=0.005
Boundary for River Rch & Prof#=Elm Creek 3,Reach-1,3
Up Type=0
Dn Type=3
Dn Slope=0.005
Boundary for River Rch & Prof#=Elm Creek 3,Reach-1,4
Up Type=0
Dn Type=3
Dn Slope=0.005
Boundary for River Rch & Prof#=Elm Creek 3,Reach-1,5
Up Type=0
Dn Type=3
Dn Slope=0.005
Boundary for River Rch & Prof#=Elm Creek 3,Reach-1,6
Up Type=0
Dn Type=3
Dn Slope=0.005
Boundary for River Rch & Prof#=Elm Creek 3,Reach-1,7
Up Type=0
Dn Type=3
Dn Slope=0.005

--- Elm Creek 3.g01 (geometry) ---

Geom Title=Existing Conditions
Program Version=4.10

River Reach=Elm Creek 3     ,Reach-1
Reach XY= 30
        2512575.       13836375.      2513372.49     13835816.89
      2513724.45     13835164.36      2513528.33     13834876.33
      2513923.51     13834669.15      2513888.22     13834061.33
      2514381.19     13833967.19      2515167.24     13833231.17
      2515774.44     13832113.91      2515584.13     13831418.26
      2516164.93       13831185.      2516248.47     13830600.05
      2516659.92     13830424.89      2517181.05     13830773.41
       2517934.8     13830764.52       2518167.8      13830275.3
       2517782.6     13829878.37      2518024.97     13829459.58
      2517904.42     13828944.23      2519123.55     13828771.47
      2519861.31     13827888.47       2520338.3      13827811.6
      2520994.47     13826554.25      2521531.48     13826567.31
      2522861.27     13825138.16      2523291.71     13825108.37
      2523133.82     13824818.01      2523805.21     13824445.09
      2523918.47     13823982.68        2524825.       13824125.

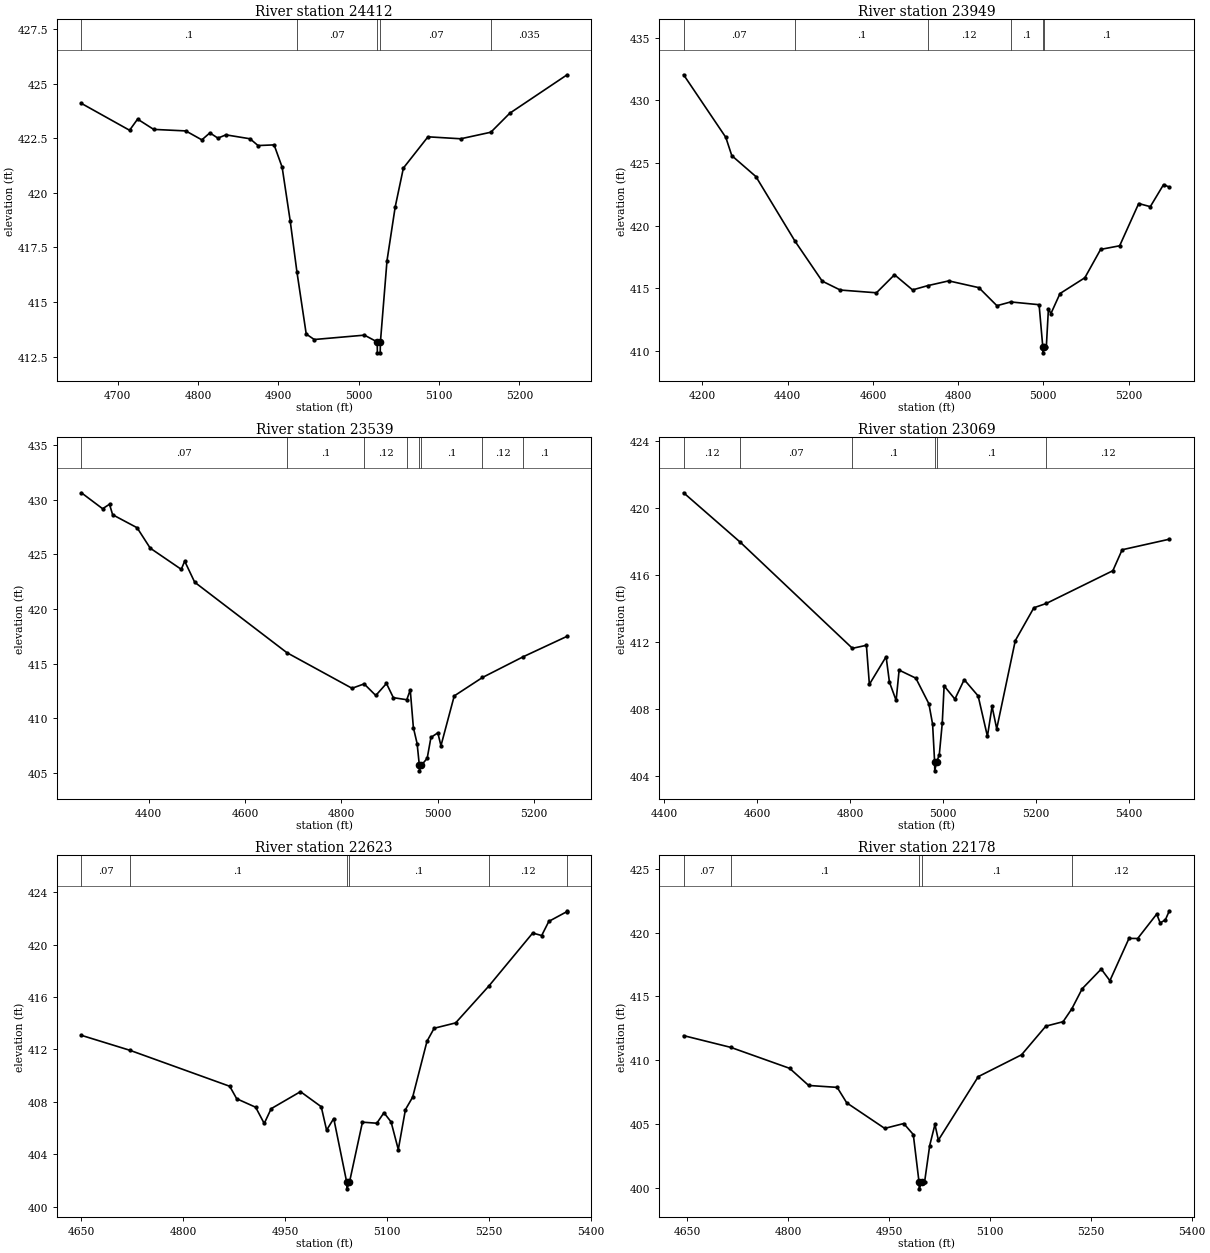
Type RM Length L Ch R = 1 ,24412   ,463,463,463
BEGIN DESCRIPTION:
Elm Creek 3 43.0
END DESCRIPTION:
XS GIS Cut Line= 3
        2512775.     13836524.98        2512775.       13836175.
      2512525.04     13836125.01
#Sta/Elev= 30
  4654.6  424.09  4714.6  422.86  4724.6  423.37  4744.6   422.9  4784.6  422.83
  4804.6  422.42  4814.6  422.74  4824.6   422.5  4834.6  422.65  4864.6  422.47
  4874.6  422.16  4894.6  422.19  4904.6  421.17  4914.6  418.72    4923  416.38
  4934.6  413.53  4944.6  413.28  5007.1  413.48    5023  413.17  5023.2  412.67
  5026.7  412.67    5027  413.17  5035.2  416.89  5045.4  419.35  5055.6  421.13
  5086.2  422.56    5127  422.47  5164.5  422.77  5188.1  423.64  5259.5   425.4
#Mann= 5 ,-1 , 0
  4654.6      .1       0    4923     .07       0    5023     .05       0
    5027     .07       0  5164.5    .035       0
Bank Sta=5023,5027
XS Rating Curve= 0 ,0
Exp/Cntr=0.3,0.1

Type RM Length L Ch R = 1 ,23949   ,410,410,410
BEGIN DESCRIPTION:
Elm Creek 3 42.0
END DESCRIPTION:
XS GIS Cut Line= 3
        2513675.       13836475.        2513075.       13835875.
      2512824.98     13835724.99
#Sta/Elev= 30
  4155.7  432.03  4254.7  427.04  4268.8  425.58  4325.4  423.91  4417.3  418.75
    4481  415.57  4523.4  414.86  4608.3  414.64  4650.7  416.08  4693.1  414.87
  4728.8  415.21    4778  415.59  4848.7  415.05  4891.1  413.61  4923.4  413.91
  4990.1  413.69  4998.7  410.35  4998.9  409.85  5002.7  410.35  5007.1  410.35
    5012  413.36  5017.8  412.98  5039.2  414.58  5097.5  415.84  5134.5   418.1
  5179.2  418.39  5223.9  421.76  5251.1  421.51  5282.2  423.27  5295.8  423.07
#Mann= 6 ,-1 , 0
  4155.7     .07       0  4417.3      .1       0  4728.8     .12       0
  4923.4      .1       0  4998.7     .05       0  5002.7      .1       0
Bank Sta=4998.7,5002.7
XS Rating Curve= 0 ,0
Exp/Cntr=0.3,0.1

Type RM Length L Ch R = 1 ,23539   ,470,470,470
BEGIN DESCRIPTION:
Elm Creek 3 41.0
END DESCRIPTION:
XS GIS Cut Line= 4
      2513904.37     13836207.81        2513625.       13835975.
        2513325.       13835725.      2513075.02       13835675.
#Sta/Elev= 30
  4260.1  430.65  4304.2  429.19  4318.5   429.6    4325  428.64  4375.8  427.45
  4403.1  425.58  4467.6  423.64  4474.7  424.39  4495.5  422.46    4687  416.01
  4822.3  412.75  4847.5  413.15  4871.7  412.09  4893.9  413.19  4908.2  411.89
  4936.1   411.7  4943.3   412.6  4949.8  409.15  4957.6  407.68  4962.2  405.69
  4962.4  405.19  4966.2  405.69  4978.5  406.34  4986.3  408.25  5000.6  408.67
  5007.1  407.49  5034.7  412.05  5093.4  413.74  5177.7  415.63  5269.2  417.51
#Mann= 8 ,-1 , 0
  4260.1     .07       0    4687      .1       0  4847.5     .12       0
  4936.1      .1       0  4962.2     .05       0  4966.2      .1       0
  5093.4     .12       0  5177.7      .1       0
Bank Sta=4962.2,4966.2
XS Rating Curve= 0 ,0
Exp/Cntr=0.3,0.1

Type RM Length L Ch R = 1 ,23069   ,446,446,446
BEGIN DESCRIPTION:
Elm Creek 3 40.0
END DESCRIPTION:
XS GIS Cut Line= 5
      2513927.32     13835815.39        2513775.       13835625.
        2513575.       13835375.        2513325.       13835375.
      2513093.38       13835375.
#Sta/Elev= 30
  4441.4  420.91  4563.4  417.96  4804.8  411.63  4834.9  411.81  4841.3  409.48
  4877.3  411.13  4884.5  409.61  4898.9  408.52  4905.3  410.33  4941.3  409.85
  4969.4  408.32  4977.4   407.1  4981.8  404.82    4982  404.32  4985.8  404.82
  4991.8  405.28  4998.2  407.17  5002.2  409.39  5025.4   408.6  5045.4  409.76
  5075.4  408.79  5095.4  406.38  5105.4  408.16  5115.4  406.83  5155.4  412.09
  5195.4  414.05  5222.4  414.31  5365.4  416.26  5385.4  417.51    5487  418.14
#Mann= 6 ,-1 , 0
  4441.4     .12       0  4563.4     .07       0  4804.8      .1       0
  4981.8     .05       0  4985.8      .1       0  5222.4     .12       0
Bank Sta=4981.8,4985.8
XS Rating Curve= 0 ,0
Exp/Cntr=0.3,0.1

Type RM Length L Ch R = 1 ,22623   ,445,445,445
BEGIN DESCRIPTION:
Elm Creek 3 39.0
END DESCRIPTION:
XS GIS Cut Line= 5
      2513970.18     13835082.53        2513925.       13835075.
        2513625.       13835025.        2513325.       13834925.
      2513279.53     13834909.84
#Sta/Elev= 30
  4650.4  413.08  4721.6  411.94  4868.5  409.19  4878.7  408.24  4906.6  407.59
  4919.2  406.35  4929.4  407.48  4972.5  408.78    5003  407.63  5010.9  405.84
  5021.4  406.73  5040.5  401.86  5040.8  401.36  5044.5  401.86  5063.6  406.45
  5084.7  406.37  5095.2  407.17  5105.7  406.47  5116.3  404.36  5126.8  407.41
  5137.4  408.36  5158.5  412.63    5169  413.62  5200.6  414.03  5249.7  416.86
  5313.9  420.89  5327.1   420.7  5337.6  421.78  5363.6  422.51  5364.5  422.59
#Mann= 6 ,-1 , 0
  4650.4     .07       0  4721.6      .1       0  5040.5     .05       0
  5044.5      .1       0  5249.7     .12       0  5363.6     .07       0
Bank Sta=5040.5,5044.5
XS Rating Curve= 0 ,0
Exp/Cntr=0.3,0.1

Type RM Length L Ch R = 1 ,22178   ,421,421,421
BEGIN DESCRIPTION:
Elm Creek 3 38.0
END DESCRIPTION:
XS GIS Cut Line= 5
      2513976.53     13835026.53        2513925.       13834975.
        2513725.       13834775.        2513525.       13834725.
      2513369.26     13834686.07
#Sta/Elev= 30
  4644.3  411.93  4714.5  411.01    4802  409.37  4830.3  408.03  4872.7  407.88
  4886.9  406.67  4943.4  404.67  4971.7  405.05  4985.9  404.19  4994.5  400.44
  4994.7  399.94  4998.5  400.44  5002.6  400.44  5010.3  403.33  5018.1  404.98
  5023.2  403.75  5082.5  408.72  5146.9  410.43    5183  412.67  5208.7  413.02
  5221.7  414.03  5237.1   415.6  5265.4  417.14  5278.3  416.23  5306.7  419.54
  5319.6  419.53  5347.9  421.44  5353.1  420.75  5360.8  420.99  5366.7   421.7
#Mann= 5 ,-1 , 0
  4644.3     .07       0  4714.5      .1       0  4994.5     .05       0
  4998.5      .1       0  5221.7     .12       0
Bank Sta=4994.5,4998.5
XS Rating Curve= 0 ,0
Exp/Cntr=0.3,0.1

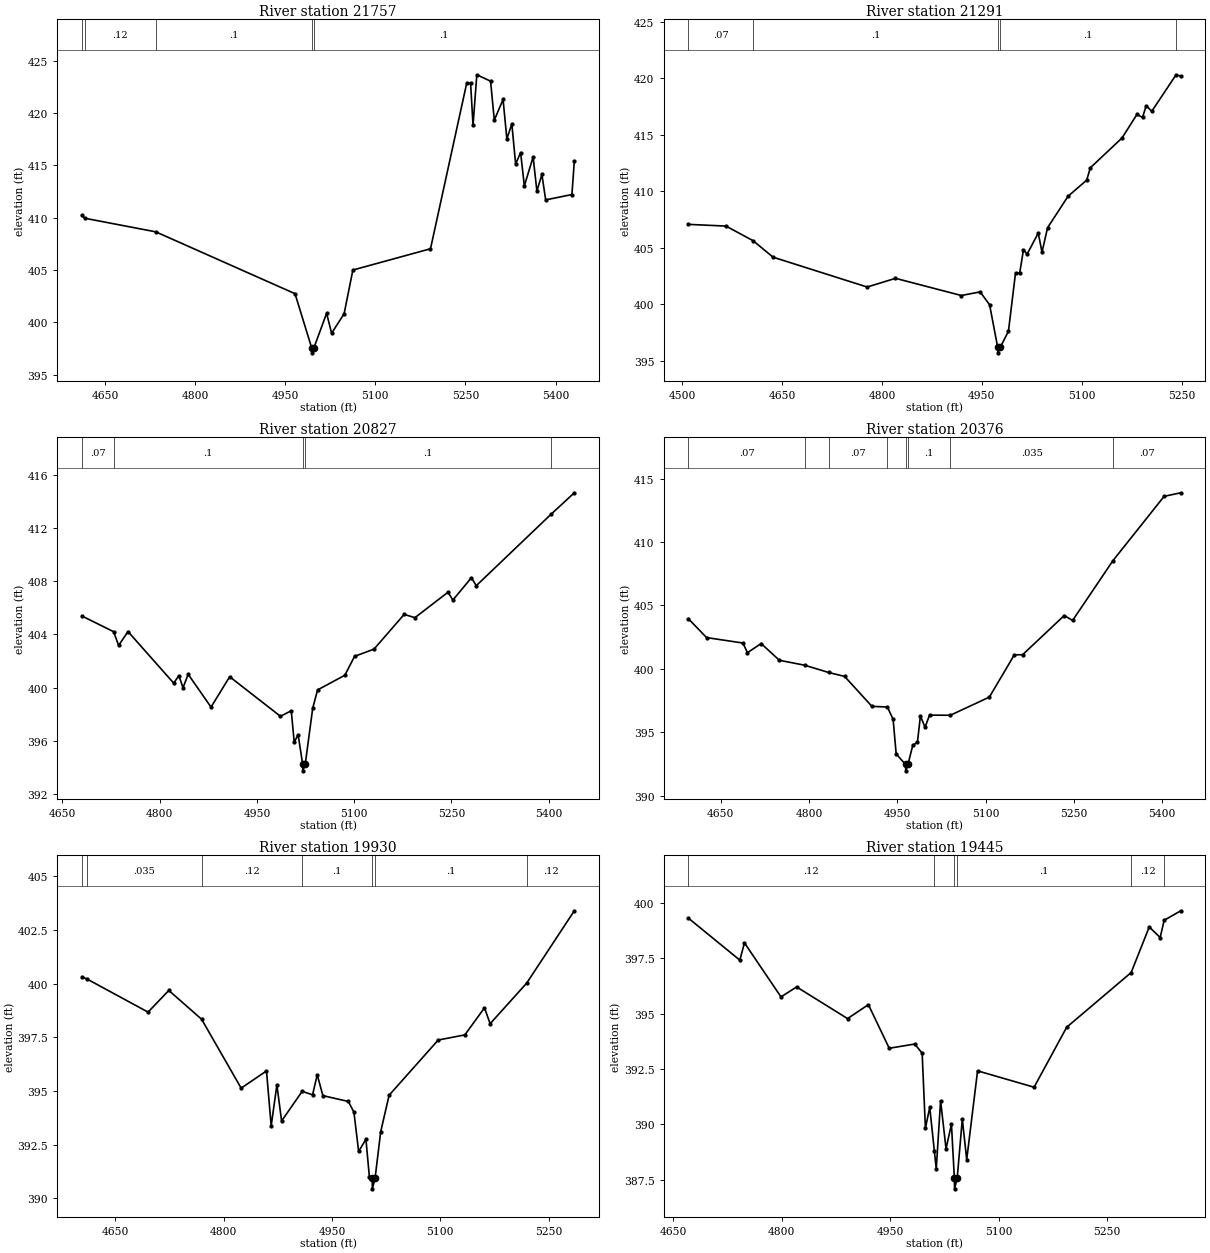
Type RM Length L Ch R = 1 ,21757   ,466,466,466
BEGIN DESCRIPTION:
Elm Creek 3 37.0
END DESCRIPTION:
XS GIS Cut Line= 5
      2514190.66     13834671.26        2514075.       13834625.
        2513825.       13834525.        2513675.       13834325.
      2513569.48      13834184.3
#Sta/Elev= 30
  4611.5   410.2    4616  409.94  4734.4  408.64  4966.3  402.73  4993.9  397.58
  4994.2  397.08  4997.9  397.58  5018.9  400.86  5027.2  398.95    5048  400.81
  5062.6  404.99  5191.8  407.02  5252.2  422.87  5258.5  422.87  5262.6  418.82
  5268.9  423.64  5291.8  423.03    5298  419.31  5312.6  421.28  5318.9  417.52
  5327.2  418.94  5333.5  415.12  5341.8  416.21    5348  413.03  5362.6  415.78
  5368.9  412.54  5377.2  414.12  5383.5  411.69  5427.2   412.2  5431.2  415.39
#Mann= 5 ,-1 , 0
  4611.5     .07       0    4616     .12       0  4734.4      .1       0
  4993.9     .05       0  4997.9      .1       0
Bank Sta=4993.9,4997.9
XS Rating Curve= 0 ,0
Exp/Cntr=0.3,0.1

Type RM Length L Ch R = 1 ,21291   ,464,464,464
BEGIN DESCRIPTION:
Elm Creek 3 36.0
END DESCRIPTION:
XS GIS Cut Line= 4
      2514225.02     13834425.02        2513875.       13834075.
        2513775.       13834025.      2513656.04     13833965.52
#Sta/Elev= 30
  4509.1  407.08  4565.7  406.93  4606.3  405.64  4636.4  404.18  4777.8  401.54
  4820.3  402.31  4919.2  400.79  4947.5  401.11  4961.7  399.97  4973.8  396.22
  4974.1  395.72  4977.8  396.22    4990  397.63  5000.6  402.77  5006.9  402.77
  5012.5  404.82  5018.1  404.46  5034.8  406.31  5040.4  404.62  5048.8  406.79
  5079.6  409.57  5107.5  410.99  5113.1  412.09  5160.6  414.72    5183   416.8
  5191.4  416.54    5197  417.58  5205.3  417.08  5241.8  420.31  5248.9  420.18
#Mann= 5 ,-1 , 0
  4509.1     .07       0  4606.3      .1       0  4973.8     .05       0
  4977.8      .1       0  5241.8     .12       0
Bank Sta=4973.8,4977.8
XS Rating Curve= 0 ,0
Exp/Cntr=0.3,0.1

Type RM Length L Ch R = 1 ,20827   ,451,451,451
BEGIN DESCRIPTION:
Elm Creek 3 35.0
END DESCRIPTION:
XS GIS Cut Line= 4
      2514474.99     13834224.99        2514275.       13833975.
        2514175.       13833825.      2514031.07      13833609.1
#Sta/Elev= 30
  4679.9  405.39  4728.8  404.21  4736.7  403.18  4751.1  404.22  4821.6  400.35
  4829.6  400.91    4836  400.01    4844  401.01  4879.2  398.55    4908  400.83
  4986.4  397.86    5003  398.28  5007.6  395.91  5013.6  396.49  5020.6  394.27
  5020.8  393.77  5024.6  394.27  5036.1  398.46  5043.6  399.84  5085.7  400.94
  5100.7  402.36  5130.7   402.9  5177.3  405.51  5193.8  405.26  5244.9  407.17
  5252.4  406.58    5281  408.26  5288.5  407.66  5403.7  413.01  5439.8  414.63
#Mann= 5 ,-1 , 0
  4679.9     .07       0  4728.8      .1       0  5020.6     .05       0
  5024.6      .1       0  5403.7    .035       0
Bank Sta=5020.6,5024.6
XS Rating Curve= 0 ,0
Exp/Cntr=0.3,0.1

Type RM Length L Ch R = 1 ,20376   ,446,446,446
BEGIN DESCRIPTION:
Elm Creek 3 34.0
END DESCRIPTION:
XS GIS Cut Line= 3
      2514625.01     13834075.05        2514525.       13833675.
      2514225.02     13833375.02
#Sta/Elev= 30
    4595  403.96    4626  402.47  4687.8  402.04  4695.5  401.28  4718.7     402
  4749.7  400.68  4792.9  400.29  4833.4  399.72  4860.5  399.41  4906.9  397.05
  4933.2     397  4942.9  396.03  4948.1   393.3  4964.1  392.47  4964.4  391.97
  4968.1  392.47  4976.4     394  4984.2  394.22  4989.3   396.3  4997.1   395.4
  5004.8  396.36  5040.1  396.35  5106.4  397.78  5148.8  401.11  5162.9  401.12
  5233.6  404.21  5247.8  403.82  5316.3  408.53  5403.3   413.6  5431.6  413.88
#Mann= 8 ,-1 , 0
    4595     .07       0  4792.9      .1       0  4833.4     .07       0
  4933.2      .1       0  4964.1     .05       0  4968.1      .1       0
  5040.1    .035       0  5316.3     .07       0
Bank Sta=4964.1,4968.1
XS Rating Curve= 0 ,0
Exp/Cntr=0.3,0.1

Type RM Length L Ch R = 1 ,19930   ,485,485,485
BEGIN DESCRIPTION:
Elm Creek 3 33.0
END DESCRIPTION:
XS GIS Cut Line= 3
      2515174.97     13833674.97        2514875.       13833425.
      2514625.01     13833275.01
#Sta/Elev= 30
  4603.6  400.31  4610.3  400.22  4695.3  398.67    4724  399.68  4769.4  398.34
  4824.2  395.13  4859.3  395.93  4865.8  393.37  4873.7  395.28  4880.2   393.6
  4908.7  394.98  4923.1  394.82  4929.6  395.75  4937.4  394.78  4972.6  394.51
  4980.4  394.01  4986.9  392.18    4997  392.75  5001.8  390.99  5005.7  390.94
  5005.9  390.44  5009.7  390.94  5017.4  393.09  5029.1   394.8  5097.1  397.37
    5134  397.61  5161.2  398.87    5169  398.13  5219.6  400.02  5285.6  403.39
#Mann= 7 ,-1 , 0
  4603.6     .07       0  4610.3    .035       0  4769.4     .12       0
  4908.7      .1       0  5005.7     .05       0  5009.7      .1       0
  5219.6     .12       0
Bank Sta=5005.7,5009.7
XS Rating Curve= 0 ,0
Exp/Cntr=0.3,0.1

Type RM Length L Ch R = 1 ,19445   ,465,465,465
BEGIN DESCRIPTION:
Elm Creek 3 32.0
END DESCRIPTION:
XS GIS Cut Line= 3
        2515425.       13833325.        2515175.       13833125.
      2514875.01       13832925.
#Sta/Elev= 30
    4671  399.31  4742.2  397.41  4748.6  398.19  4799.1  395.75  4820.7   396.2
  4891.1  394.77  4919.9   395.4  4948.7  393.43  4983.9  393.62  4994.2  393.21
  4998.7  389.82  5004.7  390.76  5011.1  388.78  5013.7  387.98  5019.7  391.06
  5027.2  388.89  5034.7     390  5038.7  387.58    5039  387.08  5042.7  387.58
  5049.7  390.23  5055.8   388.4  5070.8  392.41  5148.9  391.67    5194  394.38
  5283.1  396.85  5308.1  398.91  5323.2  398.43  5328.7  399.21  5351.7  399.64
#Mann= 6 ,-1 , 0
    4671     .12       0  5011.1      .1       0  5038.7     .05       0
  5042.7      .1       0  5283.1     .12       0  5328.7     .07       0
Bank Sta=5038.7,5042.7
XS Rating Curve= 0 ,0
Exp/Cntr=0.3,0.1

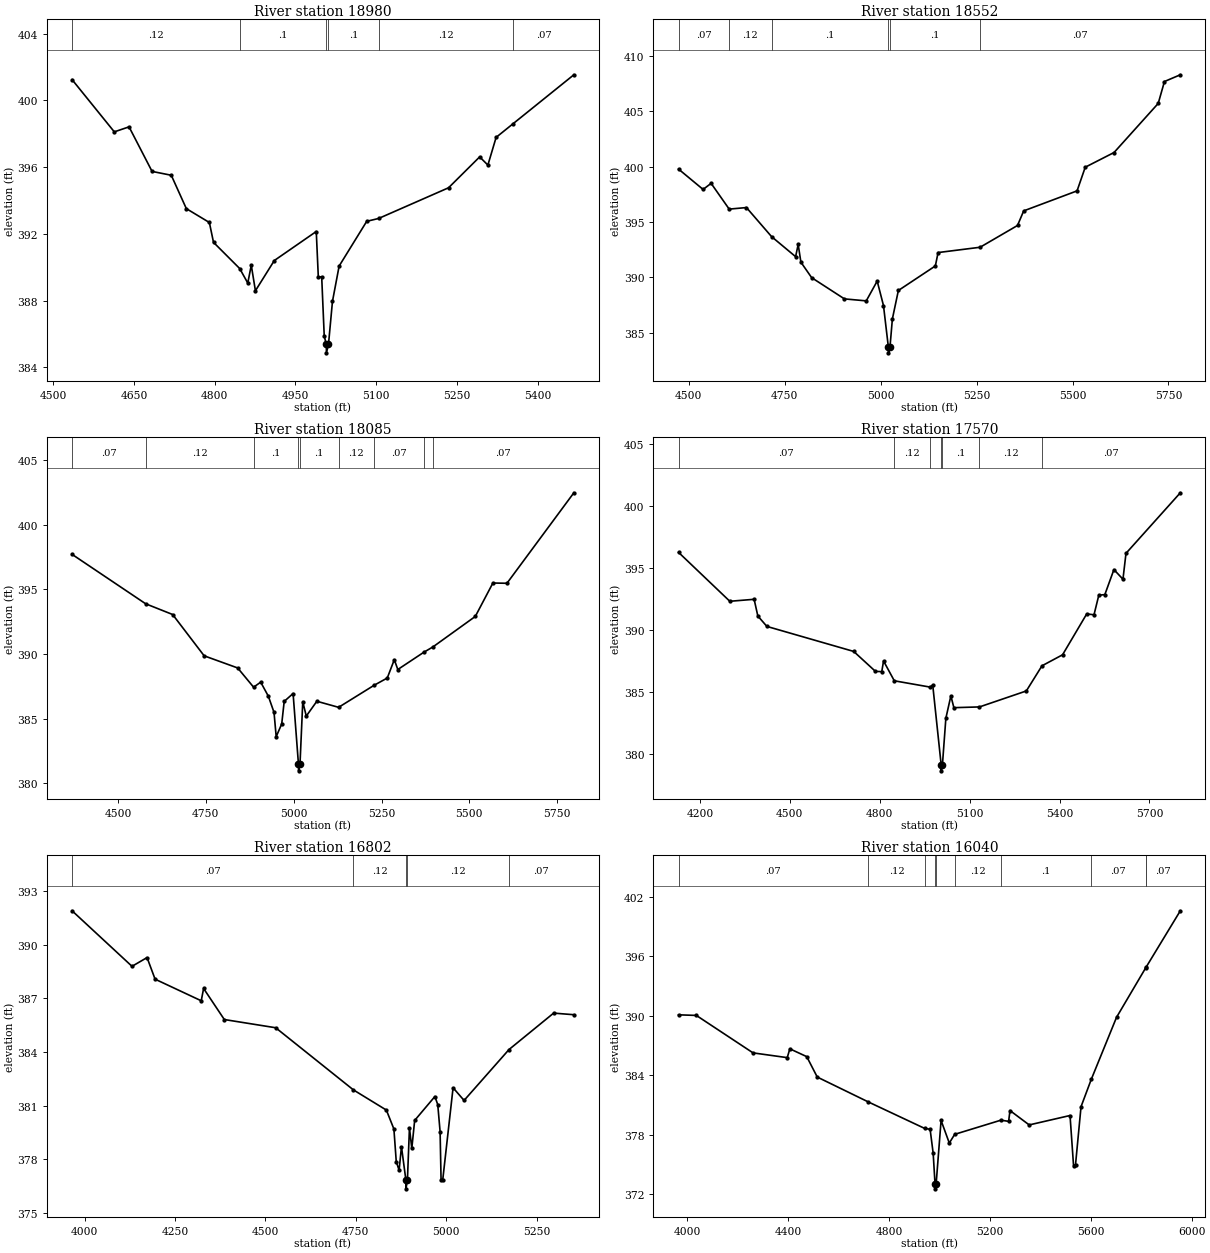
Type RM Length L Ch R = 1 ,18980   ,428,428,428
BEGIN DESCRIPTION:
Elm Creek 3 31.0
END DESCRIPTION:
XS GIS Cut Line= 3
      2515675.02     13833075.02        2515325.       13832775.
      2514925.01       13832525.
#Sta/Elev= 30
  4534.7  401.24  4613.2  398.11  4640.6  398.41  4683.4  395.74  4719.1  395.51
  4747.1  393.51  4789.9  392.68  4797.6  391.49  4846.3  389.92  4861.3  389.05
  4867.8  390.12  4875.5  388.59  4910.6   390.4  4988.6  392.14  4992.4  389.42
  4998.7  389.42  5003.4  385.88  5007.3  385.37  5007.5  384.87  5011.3  385.37
  5018.7  387.95  5031.1  390.07  5082.4  392.75  5104.4  392.92  5234.5  394.76
  5292.3  396.61  5307.6  396.12  5322.9  397.78  5354.9  398.61  5467.4  401.53
#Mann= 6 ,-1 , 0
  4534.7     .12       0  4846.3      .1       0  5007.3     .05       0
  5011.3      .1       0  5104.4     .12       0  5354.9     .07       0
Bank Sta=5007.3,5011.3
XS Rating Curve= 0 ,0
Exp/Cntr=0.3,0.1

Type RM Length L Ch R = 1 ,18552   ,467,467,467
BEGIN DESCRIPTION:
Elm Creek 3 30.0
END DESCRIPTION:
XS GIS Cut Line= 3
      2515874.98     13832874.98        2515525.       13832475.
      2514774.99       13832275.
#Sta/Elev= 30
  4473.2  399.79  4537.2  397.95  4558.1   398.5  4605.2  396.17  4650.2  396.31
  4715.7  393.68  4778.3  391.87    4785  392.97  4792.1  391.37  4820.1  389.97
  4905.5  388.05  4962.4  387.87  4990.9  389.66  5007.3  387.45  5020.1  383.67
  5020.3  383.17  5024.2  383.67  5030.5  386.24  5046.1  388.81  5142.5  391.03
  5149.6  392.24  5259.1  392.72  5356.6  394.69  5372.7  396.01  5511.8  397.82
  5533.1  399.96  5608.2  401.29  5723.3  405.73  5739.5  407.71  5780.9  408.32
#Mann= 6 ,-1 , 0
  4473.2     .07       0  4605.2     .12       0  4715.7      .1       0
  5020.1     .05       0  5024.2      .1       0  5259.1     .07       0
Bank Sta=5020.1,5024.2
XS Rating Curve= 0 ,0
Exp/Cntr=0.3,0.1

Type RM Length L Ch R = 1 ,18085   ,515,515,515
BEGIN DESCRIPTION:
Elm Creek 3 29.0
END DESCRIPTION:
XS GIS Cut Line= 3
      2516324.96     13832424.98        2515775.       13832125.
      2514975.02       13832075.
#Sta/Elev= 30
  4369.4  397.72  4578.9  393.89  4655.6  393.06  4745.3  389.86  4840.7  388.92
    4886  387.43  4906.2  387.82    4928  386.73  4944.1  385.48  4950.3   383.6
    4966  384.58  4973.1  386.33  4998.4  386.94  5013.7  381.45    5014  380.95
    5018  381.45  5025.9  386.31  5035.9  385.19    5066  386.34  5127.9  385.87
  5229.1  387.58  5266.4  388.14  5286.4  389.56  5296.4   388.8  5371.2  390.15
  5396.4  390.55  5516.9  392.91    5567   395.5    5607  395.48  5797.4  402.49
#Mann= 9 ,-1 , 0
  4369.4     .07       0  4578.9     .12       0    4886      .1       0
  5013.7     .05       0    5018      .1       0  5127.9     .12       0
  5229.1     .07       0  5371.2      .1       0  5396.4     .07       0
Bank Sta=5013.7,5018
XS Rating Curve= 0 ,0
Exp/Cntr=0.3,0.1

Type RM Length L Ch R = 1 ,17570   ,768,768,768
BEGIN DESCRIPTION:
Elm Creek 3 28.0
END DESCRIPTION:
XS GIS Cut Line= 3
      2516566.25     13832141.52      2515914.43     13831716.42
      2515025.02       13831825.
#Sta/Elev= 30
  4128.8  396.27  4299.9  392.32    4381  392.48  4393.4  391.13  4423.6  390.29
  4713.3  388.27  4785.8  386.66  4806.9  386.64  4812.8   387.5  4848.7   385.9
  4968.5  385.39  4976.9  385.56    5005  379.13  5005.3  378.63  5009.3  379.13
  5020.7  382.87  5037.4  384.68  5047.5  383.73  5132.9  383.79  5289.2  385.08
  5341.4  387.11  5410.1     388  5490.7   391.3    5515  391.23    5531  392.81
  5551.2  392.86  5581.4  394.88  5611.6   394.1  5621.7  396.19    5803  401.08
#Mann= 7 ,-1 , 0
  4128.8     .07       0  4848.7     .12       0  4968.5      .1       0
    5005     .05       0  5009.3      .1       0  5132.9     .12       0
  5341.4     .07       0
Bank Sta=5005,5009.3
XS Rating Curve= 0 ,0
Exp/Cntr=0.3,0.1

Type RM Length L Ch R = 1 ,16802   ,762,762,762
BEGIN DESCRIPTION:
Elm Creek 3 27.0
END DESCRIPTION:
XS GIS Cut Line= 3
      2516488.31      13831964.4       2515836.5     13831177.97
      2515475.15     13831121.29
#Sta/Elev= 30
  3965.5  391.91  4131.2   388.8  4172.8  389.29    4195  388.08  4322.6  386.87
  4329.1  387.56  4386.4  385.82  4528.4  385.36  4743.3  381.88  4834.4  380.75
  4855.2  379.69  4861.7  377.87  4869.6  377.38  4876.1   378.7  4888.3  376.84
  4888.5  376.34  4892.6  376.84  4898.2  379.75  4904.7   378.6  4912.6  380.17
  4968.5  381.51  4976.4  381.06  4982.9  379.55  4985.6  376.84  4990.2  376.84
  5018.8     382  5049.2  381.29  5173.4  384.14  5296.8  386.18  5352.7  386.09
#Mann= 5 ,-1 , 0
  3965.5     .07       0  4743.3     .12       0  4888.3     .05       0
  4892.6     .12       0  5173.4     .07       0
Bank Sta=4888.3,4892.6
XS Rating Curve= 0 ,0
Exp/Cntr=0.3,0.1

Type RM Length L Ch R = 1 ,16040   ,643,643,643
BEGIN DESCRIPTION:
Elm Creek 3 26.0
END DESCRIPTION:
XS GIS Cut Line= 3
      2516481.23     13831893.58      2516289.93     13831114.21
      2515822.31     13830023.09
#Sta/Elev= 30
  3965.9  390.11  4036.5  390.05  4261.3  386.27  4396.9  385.79  4407.2  386.68
  4474.3  385.89  4515.9  383.83  4718.4  381.32  4941.6  378.65  4963.4  378.56
  4975.5  376.15  4982.9  373.05  4983.2  372.55  4987.3  373.05  5006.9  379.45
  5039.5  377.17  5060.8  378.05  5244.2  379.48  5274.7  379.36  5280.1  380.45
  5356.3     379  5518.2  379.95  5532.2  374.86    5540     375  5561.8  380.84
  5602.6  383.61  5702.6  389.86  5817.5  394.82  5819.1  394.89  5955.5  400.61
#Mann= 10 ,-1 , 0
  3965.9     .07       0  4718.4     .12       0  4941.6      .1       0
  4982.9     .05       0  4987.3      .1       0  5060.8     .12       0
  5244.2      .1       0  5602.6     .07       0  5817.5     .05       0
  5819.1     .07       0
Bank Sta=4982.9,4987.3
XS Rating Curve= 0 ,0
Exp/Cntr=0.3,0.1

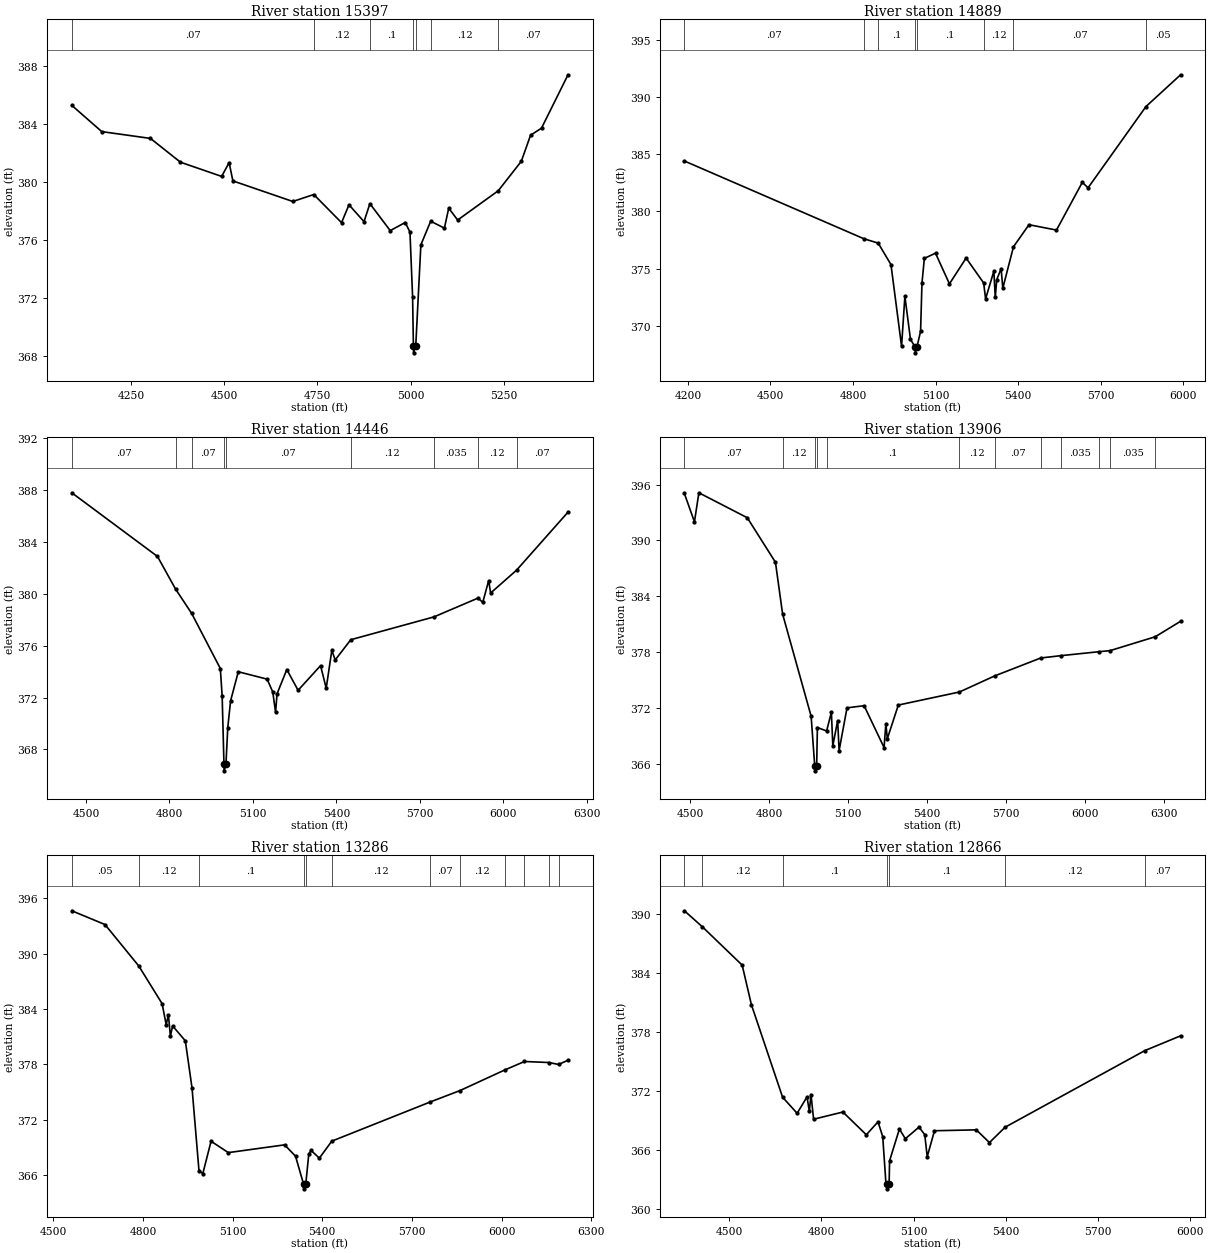
Type RM Length L Ch R = 1 ,15397   ,508,508,508
BEGIN DESCRIPTION:
Elm Creek 3 25.0
END DESCRIPTION:
XS GIS Cut Line= 3
        2516425.     13831424.97        2516525.       13830525.
        2516375.     13830125.01
#Sta/Elev= 30
  4090.2  385.28  4170.7  383.47  4301.5     383    4382  381.36  4492.6  380.38
  4512.8  381.33  4522.8  380.07  4683.8  378.65  4740.1  379.13  4814.6  377.19
  4834.7  378.42    4875  377.26  4890.8   378.5  4945.4  376.64  4985.6   377.2
  4998.4  376.54  5005.5  372.06  5007.6  368.71  5008.1  368.21    5014  368.71
  5027.7  375.66  5054.1  377.29  5090.9  376.81  5102.5  378.19  5126.5  377.37
  5235.5  379.39  5297.4  381.42  5322.3  383.22  5351.7  383.71  5422.9  387.39
#Mann= 7 ,-1 , 0
  4090.2     .07       0  4740.1     .12       0  4890.8      .1       0
  5007.6     .05       0    5014      .1       0  5054.1     .12       0
  5235.5     .07       0
Bank Sta=5007.6,5014
XS Rating Curve= 0 ,0
Exp/Cntr=0.3,0.1

Type RM Length L Ch R = 1 ,14889   ,443,443,443
BEGIN DESCRIPTION:
X19139
END DESCRIPTION:
XS GIS Cut Line= 3
      2516672.51      13831447.2      2516842.55     13830313.62
      2516467.06     13829775.18
#Sta/Elev= 30
  4187.4  384.42  4839.7  377.61  4891.4  377.23  4937.9  375.35  4976.4   368.2
  4988.5  372.57  5008.7  368.81  5025.7  368.12  5026.2  367.62  5032.2  368.12
  5045.5  369.51  5050.5  373.71  5059.2  375.89  5099.7  376.35  5150.3  373.66
  5210.9  375.92  5274.6  373.74  5281.7  372.35  5311.7  374.77  5316.8  372.47
  5322.2  374.03  5338.1  374.99  5344.2  373.28    5383  376.91  5439.3  378.84
  5539.2  378.37    5633  382.55  5653.9  382.07  5864.3  389.19  5990.1  391.97
#Mann= 8 ,-1 , 0
  4187.4     .07       0  4839.7     .12       0  4891.4      .1       0
  5025.7     .05       0  5032.2      .1       0  5274.6     .12       0
    5383     .07       0  5864.3     .05       0
Bank Sta=5025.7,5032.2
XS Rating Curve= 0 ,0
Exp/Cntr=0.3,0.1

Type RM Length L Ch R = 1 ,14446   ,540,540,540
BEGIN DESCRIPTION:
X19138
END DESCRIPTION:
XS GIS Cut Line= 3
      2517267.64     13831319.68      2517104.69     13830214.43
      2516644.15     13829732.63
#Sta/Elev= 30
  4449.1  387.79  4757.1  382.88    4822  380.37  4879.9  378.49    4983  374.24
  4989.6  372.11  4996.1  366.85  4996.6  366.35  5003.2  366.85  5009.8  369.69
  5019.9  371.75  5047.6  373.99  5151.3  373.42  5171.5  372.43  5181.6  370.87
  5186.9  372.29    5222  374.16  5262.5  372.56  5343.3  374.46  5363.6  372.72
  5383.8  375.64  5395.9   374.9  5451.9  376.46    5751  378.22  5909.3  379.67
  5926.3  379.34  5947.6  381.02  5954.6  380.06  6047.7  381.82  6232.8   386.3
#Mann= 9 ,-1 , 0
  4449.1     .07       0    4822     .12       0  4879.9     .07       0
  4996.1     .05       0  5003.2     .07       0  5451.9     .12       0
    5751    .035       0  5909.3     .12       0  6047.7     .07       0
Bank Sta=4996.1,5003.2
XS Rating Curve= 0 ,0
Exp/Cntr=0.3,0.1

Type RM Length L Ch R = 1 ,13906   ,620,620,620
BEGIN DESCRIPTION:
X19137
END DESCRIPTION:
XS GIS Cut Line= 3
      2517834.44     13831255.92      2517416.42     13830249.85
      2516822.17     13829719.27
#Sta/Elev= 30
  4477.5  395.05  4515.8     392  4532.6  395.12  4716.7  392.44  4823.7  387.66
  4850.9   382.1  4959.3  371.14    4973  365.78  4973.5  365.28  4980.3  365.78
  4983.1  369.93  5018.1  369.56  5036.3  371.56  5041.7  367.96  5060.1  370.68
  5065.6  367.45  5095.7  372.04  5160.7  372.27  5236.5  367.78  5243.4  370.34
  5248.8  368.72  5290.7  372.34  5522.9  373.74  5657.2  375.47    5832  377.39
  5908.5  377.64  6052.1  378.06  6095.5  378.18  6267.3  379.67  6363.6  381.33
#Mann= 12 ,-1 , 0
  4477.5     .07       0  4850.9     .12       0    4973     .05       0
  4980.3     .12       0  5018.1      .1       0  5522.9     .12       0
  5657.2     .07       0    5832     .12       0  5908.5    .035       0
  6052.1     .07       0  6095.5    .035       0  6267.3     .12       0
Bank Sta=4973,4980.3
XS Rating Curve= 0 ,0
Exp/Cntr=0.3,0.1

Type RM Length L Ch R = 1 ,13286   ,420,420,420
BEGIN DESCRIPTION:
Elm Creek 3 24.0
END DESCRIPTION:
XS GIS Cut Line= 3
      2518379.96     13830816.63      2518110.74     13830526.16
      2517040.91     13829853.09
#Sta/Elev= 30
  4562.1  394.63  4673.2  393.14  4786.3  388.65  4864.2  384.58  4877.9   382.3
  4885.2  383.37    4892  381.06  4899.4  382.17  4941.9  380.56  4964.4  375.43
  4987.6   366.5  5000.4  366.19    5028  369.69  5085.7  368.46  5274.1   369.3
  5310.6  368.07  5337.5  365.04    5338  364.54  5344.8  365.04  5354.8  368.29
  5362.4   368.7  5390.3  367.86  5431.8   369.7  5761.2  373.94  5860.4  375.17
  6009.6  377.39  6076.4  378.32  6157.6  378.21  6190.7     378  6222.1  378.46
#Mann= 12 ,-1 , 0
  4562.1     .05       0  4786.3     .12       0  4987.6      .1       0
  5337.5     .05       0  5344.8      .1       0  5431.8     .12       0
  5761.2     .07       0  5860.4     .12       0  6009.6     .07       0
  6076.4    .035       0  6157.6     .07       0  6190.7    .035       0
Bank Sta=5337.5,5344.8
XS Rating Curve= 0 ,0
Exp/Cntr=0.3,0.1

Type RM Length L Ch R = 1 ,12866   ,647,647,647
BEGIN DESCRIPTION:
Elm Creek 3 23.0
END DESCRIPTION:
XS GIS Cut Line= 3
      2518727.17     13830426.99      2518139.08     13830200.26
      2517203.83     13829895.59
#Sta/Elev= 30
  4354.7  390.29    4413  388.67  4542.7  384.77  4572.7  380.75  4674.1  371.36
  4721.4  369.72  4753.6  371.39  4761.1  369.92  4766.5  371.63    4775  369.12
  4870.3  369.85  4946.5  367.54  4984.5  368.86  4999.8  367.35  5010.3  362.58
  5013.1  362.55  5013.6  362.05  5020.6  362.55  5022.1   364.9    5054  368.12
  5073.4  367.14  5117.8  368.32  5136.5  367.55  5144.5  365.31  5168.1  367.95
  5304.1  368.04  5346.9  366.75  5397.9  368.31  5852.3  376.09  5968.6  377.59
#Mann= 7 ,-1 , 0
  4354.7     .07       0    4413     .12       0  4674.1      .1       0
  5013.1     .05       0  5020.6      .1       0  5397.9     .12       0
  5852.3     .07       0
Bank Sta=5013.1,5020.6
XS Rating Curve= 0 ,0
Exp/Cntr=0.3,0.1

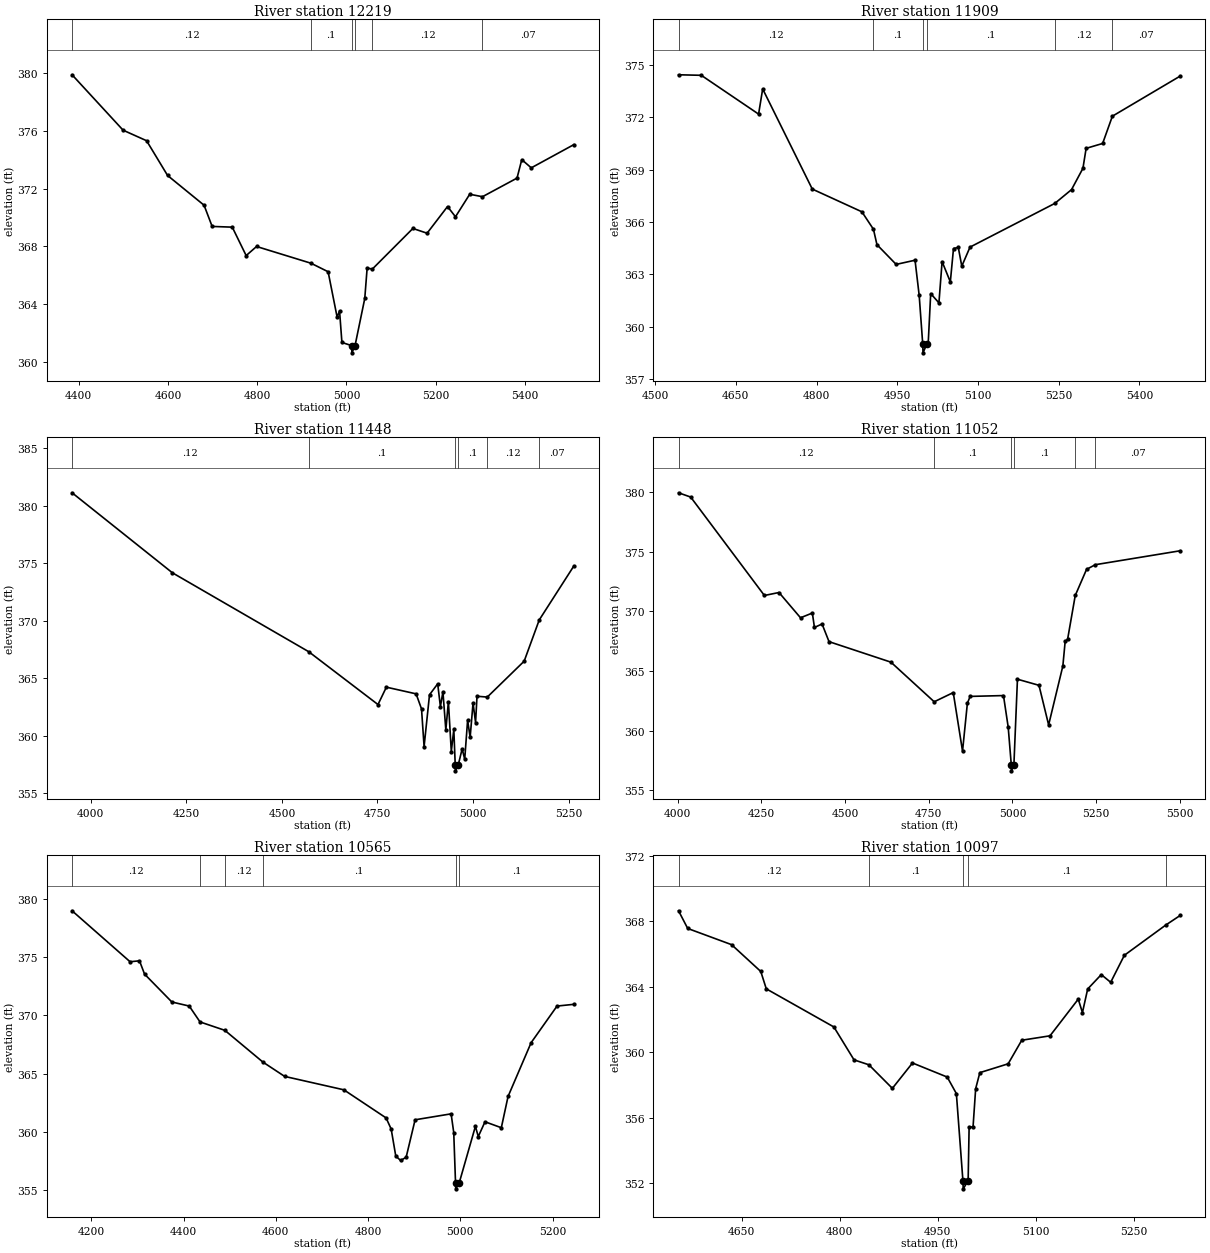
Type RM Length L Ch R = 1 ,12219   ,310,310,310
BEGIN DESCRIPTION:
Elm Creek 3 22.0
END DESCRIPTION:
XS GIS Cut Line= 3
      2518424.96     13830024.99      2518039.89     13829860.18
      2517375.02     13829625.01
#Sta/Elev= 30
  4385.3  379.89  4499.6  376.05  4552.2  375.32  4599.3  372.91    4681  370.85
  4699.1  369.38  4744.2  369.33  4775.3  367.36  4798.6  367.99  4920.5  366.83
  4958.9  366.24  4979.1  363.09  4984.5  363.53  4989.8  361.34  5011.6  361.12
  5012.1  360.62  5019.2  361.12    5041  364.39  5046.3  366.49  5058.1  366.43
  5148.8  369.24  5180.6  368.91  5226.4  370.76  5244.2  370.05  5276.1  371.61
  5304.7  371.44  5382.1  372.73  5392.7  374.01    5414  373.44  5509.4  375.05
#Mann= 6 ,-1 , 0
  4385.3     .12       0  4920.5      .1       0  5011.6     .05       0
  5019.2      .1       0  5058.1     .12       0  5304.7     .07       0
Bank Sta=5011.6,5019.2
XS Rating Curve= 0 ,0
Exp/Cntr=0.3,0.1

Type RM Length L Ch R = 1 ,11909   ,461,461,461
BEGIN DESCRIPTION:
Elm Creek 3 21.0
END DESCRIPTION:
XS GIS Cut Line= 3
      2518325.03     13829825.02        2517975.       13829525.
      2517575.01     13829275.01
#Sta/Elev= 30
  4543.5  374.42  4585.8  374.39  4692.3  372.17  4699.9  373.61  4792.1  367.88
  4884.3  366.58  4905.8  365.58  4912.3   364.7    4948  363.57  4983.1  363.81
  4990.8   361.8  4997.4  359.01  4997.9  358.51    5005  359.01  5007.5  359.01
  5012.2   361.9  5027.5  361.37  5033.4  363.73  5048.7  362.57  5054.6  364.48
  5063.5  364.54    5070  363.47  5085.3  364.56  5242.9  367.06    5274  367.85
  5295.2  369.07  5301.1  370.21  5331.8  370.49  5349.9  372.05  5476.2  374.35
#Mann= 6 ,-1 , 0
  4543.5     .12       0  4905.8      .1       0  4997.4     .05       0
    5005      .1       0  5242.9     .12       0  5349.9     .07       0
Bank Sta=4997.4,5005
XS Rating Curve= 0 ,0
Exp/Cntr=0.3,0.1

Type RM Length L Ch R = 1 ,11448   ,396,396,396
BEGIN DESCRIPTION:
Elm Creek 3 20.0
END DESCRIPTION:
XS GIS Cut Line= 3
      2518674.96     13829824.97        2517875.       13829125.
      2517624.97       13829125.
#Sta/Elev= 30
    3951  381.12  4213.4  374.17  4570.3  367.31  4751.5  362.72  4773.4  364.23
  4851.2  363.65  4865.4  362.34  4872.1  359.07  4886.3  363.57  4907.7  364.52
  4914.8  362.54  4921.4  363.83    4929  360.51  4935.7  362.97  4943.3  358.64
  4949.9  360.56  4953.6  357.46  4954.1  356.96  4961.4  357.46  4971.7  358.87
  4978.4  357.97    4986  361.36  4992.6  359.87  5000.2  362.86  5006.8  361.16
  5010.6  363.44  5037.5  363.37    5134  366.49  5173.4  370.07    5264  374.76
#Mann= 6 ,-1 , 0
    3951     .12       0  4570.3      .1       0  4953.6     .05       0
  4961.4      .1       0  5037.5     .12       0  5173.4     .07       0
Bank Sta=4953.6,4961.4
XS Rating Curve= 0 ,0
Exp/Cntr=0.3,0.1

Type RM Length L Ch R = 1 ,11052   ,487,487,487
BEGIN DESCRIPTION:
Elm Creek 3 19.0
END DESCRIPTION:
XS GIS Cut Line= 3
      2518675.03     13829725.04      2518004.47     13828854.13
      2517715.11     13828578.89
#Sta/Elev= 30
  4002.8  379.94  4039.1  379.58  4259.2  371.33  4302.8  371.58  4367.1  369.46
  4402.4  369.86  4408.7  368.65  4431.4  368.94  4452.2  367.46  4637.1  365.74
  4766.3  362.42  4823.2  363.19  4850.9  358.28  4865.4   362.3  4873.6  362.87
  4973.2  362.94  4987.3  360.29  4996.5  357.13    4997  356.63  5004.3  357.13
  5014.9  364.31  5079.2   363.8    5108  360.48  5150.5  365.42  5157.4  367.48
  5164.7  367.66  5187.5  371.33  5221.3  373.52  5247.3  373.91  5501.3  375.08
#Mann= 6 ,-1 , 0
  4002.8     .12       0  4766.3      .1       0  4996.5     .05       0
  5004.3      .1       0  5187.5     .12       0  5247.3     .07       0
Bank Sta=4996.5,5004.3
XS Rating Curve= 0 ,0
Exp/Cntr=0.3,0.1

Type RM Length L Ch R = 1 ,10565   ,468,468,468
BEGIN DESCRIPTION:
Elm Creek 3 18.0
END DESCRIPTION:
XS GIS Cut Line= 3
      2518725.01     13829675.04        2518475.       13828875.
        2518325.       13828675.
#Sta/Elev= 30
  4158.1  378.96  4283.9  374.59  4304.3  374.67  4315.3  373.53  4374.5  371.14
  4412.2  370.79  4435.6  369.43  4489.4  368.71  4571.9  365.99  4619.1  364.76
  4747.5  363.61  4839.1   361.2  4850.1  360.25  4860.1  357.93  4870.6  357.55
  4882.6  357.83    4902  361.04  4980.1  361.55  4985.8  359.95  4989.7  355.62
  4990.2  355.12  4997.6  355.62  5032.8  360.48    5039   359.6  5053.6  360.87
    5089  360.36  5103.6  363.04  5153.6  367.65  5209.8  370.79  5246.3  370.94
#Mann= 6 ,-1 , 0
  4158.1     .12       0  4435.6      .1       0  4489.4     .12       0
  4571.9      .1       0  4989.7     .05       0  4997.6      .1       0
Bank Sta=4989.7,4997.6
XS Rating Curve= 0 ,0
Exp/Cntr=0.3,0.1

Type RM Length L Ch R = 1 ,10097   ,454,454,454
BEGIN DESCRIPTION:
Elm Creek 3 17.0
END DESCRIPTION:
XS GIS Cut Line= 3
      2519025.01     13829225.02        2518825.       13828825.
        2518625.       13828575.
#Sta/Elev= 30
  4553.7  368.64  4567.7  367.56  4634.8  366.57  4679.5  364.93  4687.9  363.87
  4791.3  361.54  4822.1  359.53  4844.8  359.23  4880.7  357.79  4911.5  359.34
  4964.6  358.48  4978.6  357.47  4988.6  352.15  4989.1  351.65  4996.6  352.15
  4998.1  355.43  5004.1  355.43  5008.1  357.77  5014.5  358.75  5057.8  359.29
  5078.6  360.73  5121.8     361    5165  363.24  5171.4  362.42  5179.4  363.86
  5200.2  364.74  5214.6  364.27  5235.5  365.92  5298.9  367.77  5321.1  368.36
#Mann= 5 ,-1 , 0
  4553.7     .12       0  4844.8      .1       0  4988.6     .05       0
  4996.6      .1       0  5298.9     .07       0
Bank Sta=4988.6,4996.6
XS Rating Curve= 0 ,0
Exp/Cntr=0.3,0.1