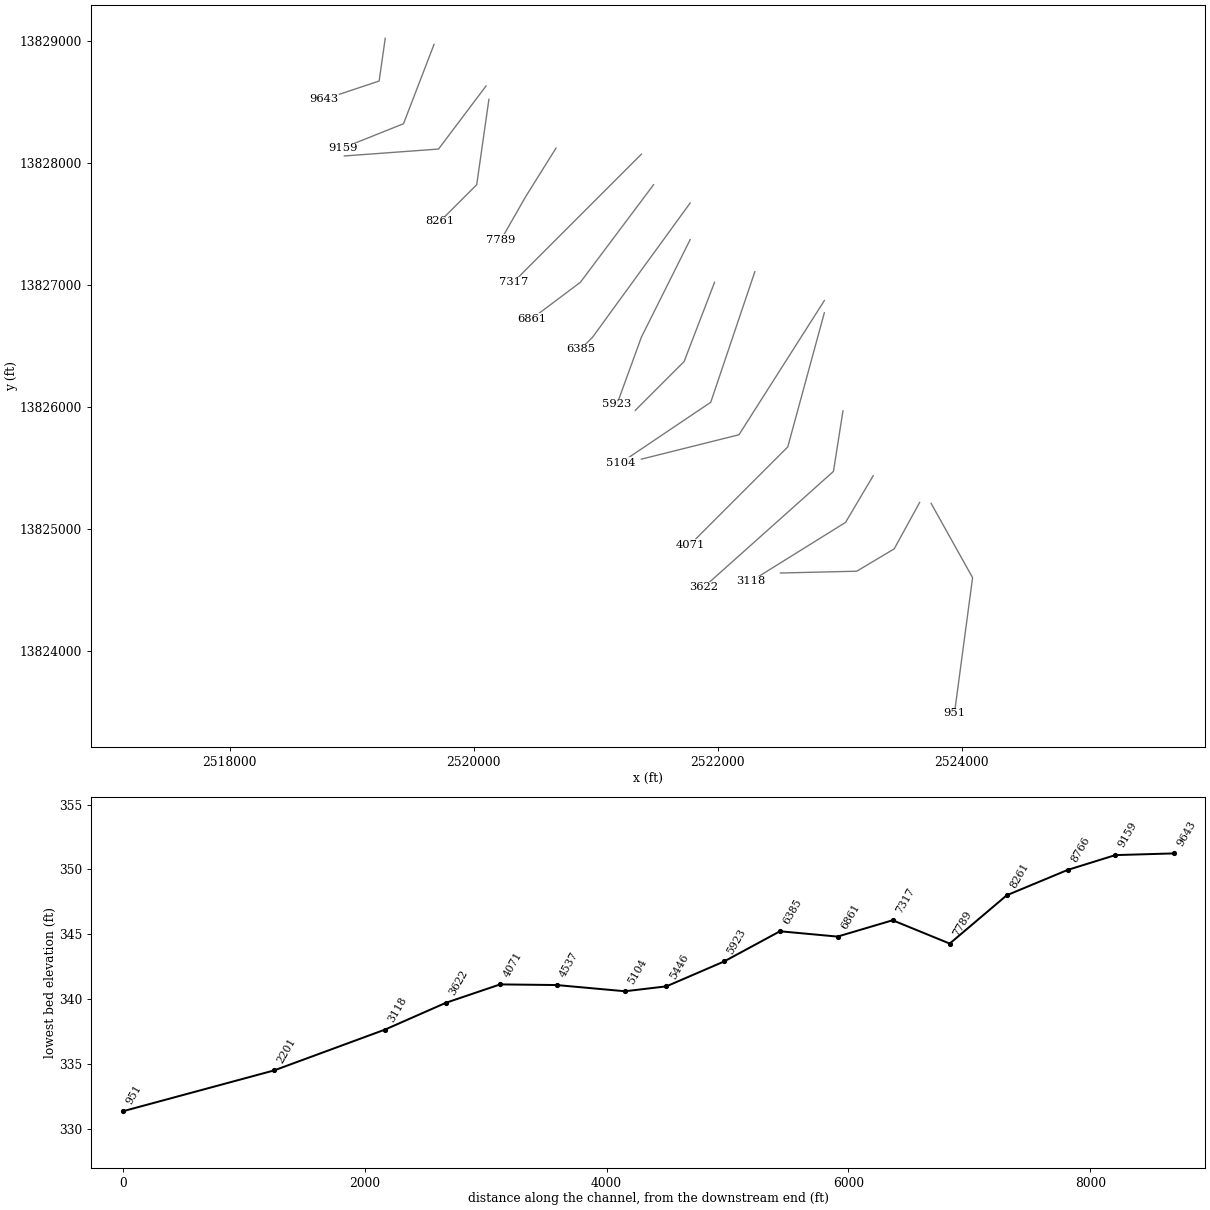
HEC-RAS study Elm Creek 3.prj: Elm Creek 3 Base Level Engineering

--- Elm Creek 3.g01 (geometry) --- (continued)

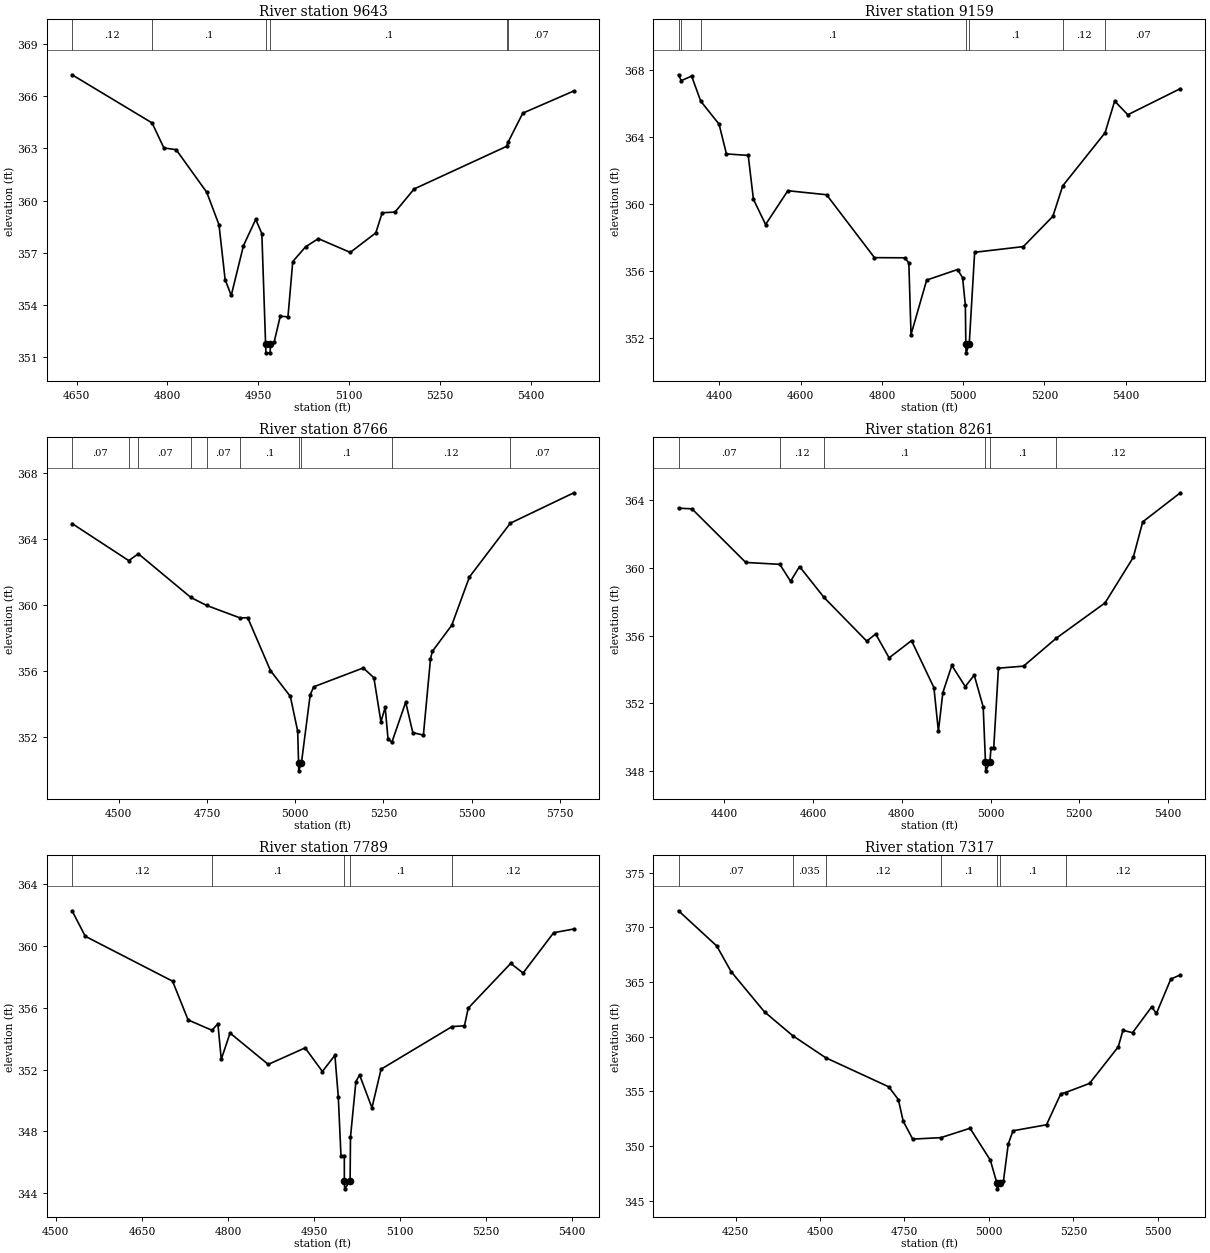
Type RM Length L Ch R = 1 ,9643    ,484,484,484
BEGIN DESCRIPTION:
Elm Creek 3 16.0
END DESCRIPTION:
XS GIS Cut Line= 3
        2519275.       13829025.        2519225.       13828675.
        2518775.       13828525.
#Sta/Elev= 30
  4642.6  367.24  4774.6  364.47  4794.1  363.03  4814.3  362.93  4864.8  360.48
    4885  358.61  4895.1  355.46  4905.2  354.54  4925.4  357.41  4945.6  358.92
  4955.7   358.1  4961.9  351.74  4962.4  351.24  4969.4  351.24  4969.9  351.74
    4976  351.86  4986.1  353.35  4998.8  353.31  5006.7  356.49  5027.8  357.34
  5048.9  357.81  5101.6  357.02  5143.7  358.14  5154.3   359.3  5175.4  359.34
    5207  360.67  5359.4  363.12  5362.4  363.39  5386.2  365.03  5470.5  366.31
#Mann= 6 ,-1 , 0
  4642.6     .12       0  4774.6      .1       0  4961.9     .05       0
  4969.9      .1       0  5359.4     .12       0  5362.4     .07       0
Bank Sta=4961.9,4969.9
XS Rating Curve= 0 ,0
Exp/Cntr=0.3,0.1

Type RM Length L Ch R = 1 ,9159    ,393,393,393
BEGIN DESCRIPTION:
Elm Creek 3 15.0
END DESCRIPTION:
XS GIS Cut Line= 3
      2519675.01     13828975.03        2519425.       13828325.
      2518924.97     13828124.99
#Sta/Elev= 30
  4299.4  367.73  4306.1  367.38  4331.6  367.65  4354.1  366.15  4399.1  364.78
  4417.3     363  4470.9  362.91  4483.7  360.29  4513.7  358.78  4568.4   360.8
  4663.7  360.56  4781.6   356.8  4856.6  356.79  4866.2  356.48  4871.6   352.2
  4910.1  355.46  4986.2  356.09  4998.5   355.6  5005.3  353.96  5006.5  351.61
    5007  351.11  5014.8  351.61  5028.2  357.12    5148  357.46  5220.7  359.27
  5244.9  361.09  5349.1  364.26  5372.8  366.16  5405.1  365.34  5534.4   366.9
#Mann= 7 ,-1 , 0
  4299.4     .07       0  4306.1     .12       0  4354.1      .1       0
  5006.5     .05       0  5014.8      .1       0  5244.9     .12       0
  5349.1     .07       0
Bank Sta=5006.5,5014.8
XS Rating Curve= 0 ,0
Exp/Cntr=0.3,0.1

Type RM Length L Ch R = 1 ,8766    ,505,505,505
BEGIN DESCRIPTION:
Elm Creek 3 14.0
END DESCRIPTION:
XS GIS Cut Line= 3
       2520101.6     13828634.52      2519711.92      13828117.3
      2518939.88     13828060.64
#Sta/Elev= 30
  4367.7  364.92  4528.2  362.68  4555.6  363.09  4704.4  360.45  4748.9  359.97
  4844.2  359.21  4865.3  359.23  4929.8  356.03  4986.1  354.47  5006.9  352.37
  5009.4  350.47  5009.9  349.97  5017.7  350.47  5042.3  354.56  5052.3  355.05
  5192.7  356.19  5222.8   355.6  5242.8  352.93  5254.8  353.81  5262.9  351.89
  5273.8   351.7    5313  354.12  5333.1  352.28  5363.1  352.13  5383.2  356.73
  5388.3  357.19  5443.4  358.77  5493.5  361.69  5609.3  364.94  5789.4  366.78
#Mann= 10 ,-1 , 0
  4367.7     .07       0  4528.2     .12       0  4555.6     .07       0
  4704.4     .12       0  4748.9     .07       0  4844.2      .1       0
  5009.4     .05       0  5017.7      .1       0  5273.8     .12       0
  5609.3     .07       0
Bank Sta=5009.4,5017.7
XS Rating Curve= 0 ,0
Exp/Cntr=0.3,0.1

Type RM Length L Ch R = 1 ,8261    ,472,472,472
BEGIN DESCRIPTION:
Elm Creek 3 13.0
END DESCRIPTION:
XS GIS Cut Line= 3
      2520125.01     13828525.04        2520025.       13827825.
      2519725.01     13827525.01
#Sta/Elev= 30
  4296.6  363.54  4326.9   363.5  4448.2  360.33  4524.9  360.22  4549.2  359.22
  4569.4  360.09  4624.7  358.26  4720.9  355.68  4741.1   356.1  4771.4  354.69
  4821.9  355.71  4872.4  352.93  4882.5  350.36  4892.6  352.64  4912.8  354.24
  4943.1  352.99  4963.3  353.67  4983.5  351.79  4988.7  348.51  4989.2  348.01
  4998.5  348.51  5001.2  349.37  5007.3  349.37  5017.9  354.08  5074.5   354.2
  5148.7  355.86  5258.3  357.94  5321.9  360.63  5343.2  362.73    5428  364.45
#Mann= 6 ,-1 , 0
  4296.6     .07       0  4524.9     .12       0  4624.7      .1       0
  4988.7     .05       0  4998.5      .1       0  5148.7     .12       0
Bank Sta=4988.7,4998.5
XS Rating Curve= 0 ,0
Exp/Cntr=0.3,0.1

Type RM Length L Ch R = 1 ,7789    ,472,472,472
BEGIN DESCRIPTION:
Elm Creek 3 12.0
END DESCRIPTION:
XS GIS Cut Line= 3
      2520675.02     13828125.03        2520425.       13827725.
      2520225.02     13827375.04
#Sta/Elev= 30
  4528.3  362.29  4551.3  360.64  4703.5  357.73  4730.6  355.22  4772.2  354.55
  4782.5  354.97  4788.4  352.67  4803.7  354.37  4870.3  352.34  4934.6  353.41
  4964.7  351.88  4986.5  352.93  4992.4  350.25  4997.1  346.43  5002.9  346.43
    5003  344.78  5003.5  344.28    5013  344.78  5013.7  347.64  5023.1  351.22
  5029.5  351.66  5051.1  349.53    5067  352.03  5190.8  354.79  5212.4  354.84
  5218.9  355.98    5293  358.88  5314.6  358.26  5367.9  360.87  5403.1  361.11
#Mann= 5 ,-1 , 0
  4528.3     .12       0  4772.2      .1       0    5003     .05       0
    5013      .1       0  5190.8     .12       0
Bank Sta=5003,5013
XS Rating Curve= 0 ,0
Exp/Cntr=0.3,0.1

Type RM Length L Ch R = 1 ,7317    ,456,456,456
BEGIN DESCRIPTION:
Elm Creek 3 11.0
END DESCRIPTION:
XS GIS Cut Line= 3
      2521374.98     13828074.98        2520725.       13827425.
        2520325.       13827025.
#Sta/Elev= 30
  4081.4  371.51  4194.5  368.29  4236.9  365.95  4335.9  362.26  4418.8   360.1
  4516.9  358.07  4703.6  355.41  4731.9  354.24  4746.1  352.28  4774.3  350.63
  4857.6  350.76    4944  351.62  5004.1   348.7  5023.7  346.58  5024.2  346.08
    5034  346.58    5043  346.83  5057.2   350.2  5071.3  351.39  5170.3  351.94
  5212.7  354.78  5226.8  354.89  5297.6  355.72  5382.5  359.06  5396.6  360.58
  5424.9  360.36  5481.4  362.72  5495.6  362.12    5538  365.26  5566.3  365.65
#Mann= 7 ,-1 , 0
  4081.4     .07       0  4418.8    .035       0  4516.9     .12       0
  4857.6      .1       0  5023.7     .05       0    5034      .1       0
  5226.8     .12       0
Bank Sta=5023.7,5034
XS Rating Curve= 0 ,0
Exp/Cntr=0.3,0.1

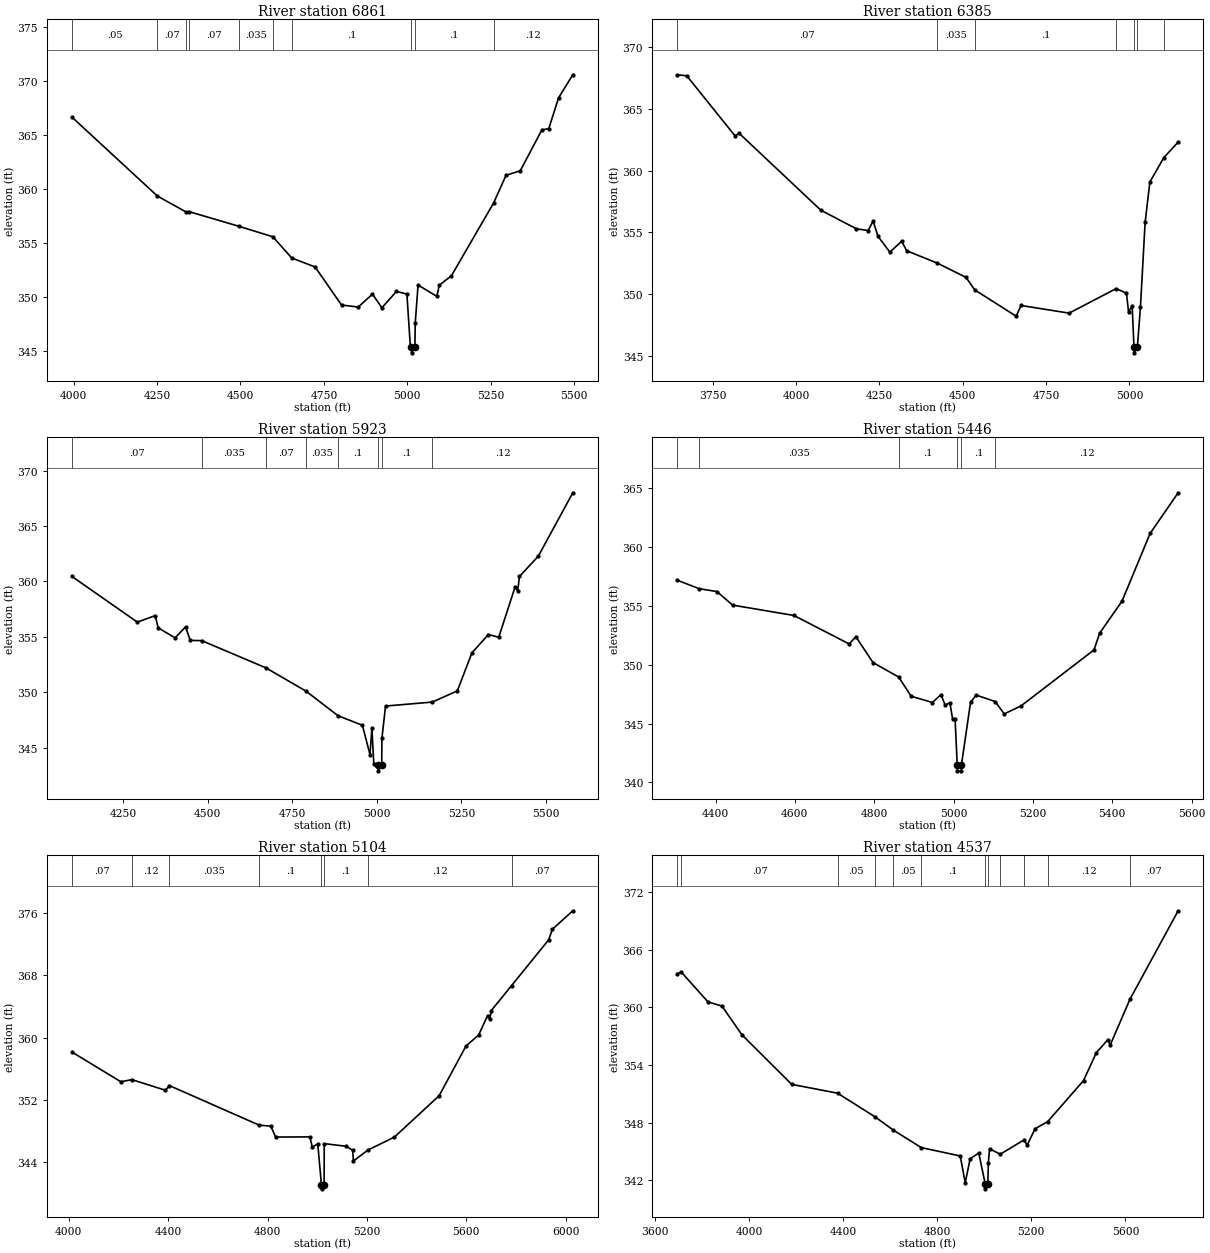
Type RM Length L Ch R = 1 ,6861    ,476,476,476
BEGIN DESCRIPTION:
Elm Creek 3 10.0
END DESCRIPTION:
XS GIS Cut Line= 3
        2521475.       13827825.        2520875.       13827025.
        2520475.       13826725.
#Sta/Elev= 30
  3995.5  366.64  4251.2  359.34  4336.9  357.87  4345.7   357.9  4495.2  356.54
    4597  355.57  4653.4  353.61  4723.6  352.77  4802.8  349.25  4852.8  349.06
  4895.5  350.26  4923.6  348.99  4967.4  350.51  4998.6  350.26    5009  345.39
  5012.2  345.32  5012.7  344.82  5022.5  345.32  5023.6  347.57    5032   351.1
  5088.2  350.05  5095.5  351.08    5132  351.96  5258.5  358.71  5295.5  361.26
  5338.2  361.68  5402.8  365.46  5423.6  365.59  5452.8  368.43  5495.5  370.57
#Mann= 10 ,-1 , 0
  3995.5     .05       0  4251.2     .07       0  4336.9     .05       0
  4345.7     .07       0  4495.2    .035       0    4597     .07       0
  4653.4      .1       0  5012.2     .05       0  5022.5      .1       0
  5258.5     .12       0
Bank Sta=5012.2,5022.5
XS Rating Curve= 0 ,0
Exp/Cntr=0.3,0.1

Type RM Length L Ch R = 1 ,6385    ,462,462,462
BEGIN DESCRIPTION:
Elm Creek 3 9.0
END DESCRIPTION:
XS GIS Cut Line= 3
      2521774.97     13827674.96        2520975.       13826575.
      2520875.02     13826475.02
#Sta/Elev= 30
  3644.5  367.78  3672.7   367.7  3817.2  362.83  3829.9  363.03  4074.5   356.8
  4181.2  355.29  4216.7  355.15  4231.4  355.92  4246.1  354.68  4281.6   353.4
  4317.2  354.28  4331.9  353.51  4423.6  352.51    4510  351.35  4535.9  350.34
  4660.3   348.2    4675  349.07  4819.1  348.45  4960.2  350.44  4991.1  350.06
  4997.3  348.53  5008.1  349.06  5013.5  345.73    5014  345.23  5023.9  345.73
  5032.9  348.92    5047  355.81  5061.2  359.08  5102.8  361.05    5146  362.32
#Mann= 7 ,-1 , 0
  3644.5     .07       0  4423.6    .035       0  4535.9      .1       0
  4960.2     .12       0  5013.5     .05       0  5023.9     .12       0
  5102.8     .07       0
Bank Sta=5013.5,5023.9
XS Rating Curve= 0 ,0
Exp/Cntr=0.3,0.1

Type RM Length L Ch R = 1 ,5923    ,477,477,477
BEGIN DESCRIPTION:
Elm Creek 3 8.0
END DESCRIPTION:
XS GIS Cut Line= 3
      2521775.01     13827375.02        2521375.       13826575.
        2521175.     13826024.99
#Sta/Elev= 30
  4099.6  360.45  4292.5  356.33  4345.6  356.92    4354  355.81  4404.3  354.91
    4435   355.9    4449  354.68  4482.7  354.66  4671.8  352.21  4790.4  350.11
  4885.5  347.88  4957.7  347.01  4980.1  344.36  4985.7  346.77  4991.3  343.54
    5004   343.4  5004.5   342.9  5014.6   343.4  5015.3  345.83    5026  348.75
  5164.1  349.11  5238.1  350.12  5281.3  353.56  5329.9  355.21  5360.5  354.96
    5409  359.53  5416.4  359.13  5421.7  360.45  5477.5  362.29  5579.3  368.01
#Mann= 8 ,-1 , 0
  4099.6     .07       0  4482.7    .035       0  4671.8     .07       0
  4790.4    .035       0  4885.5      .1       0    5004     .05       0
  5014.6      .1       0  5164.1     .12       0
Bank Sta=5004,5014.6
XS Rating Curve= 0 ,0
Exp/Cntr=0.3,0.1

Type RM Length L Ch R = 1 ,5446    ,342,342,342
BEGIN DESCRIPTION:
Elm Creek 3 7.0
END DESCRIPTION:
XS GIS Cut Line= 3
        2521975.     13827025.01        2521725.       13826375.
      2521325.01     13825975.01
#Sta/Elev= 30
  4303.9  357.18  4358.7  356.47  4403.6  356.22  4443.2  355.07  4597.5  354.19
  4736.8  351.77  4753.9  352.38  4796.8  350.19  4861.8  348.95  4893.2  347.32
  4946.8  346.79  4968.2  347.46  4978.9  346.56  4990.7  346.78  4997.7  345.36
  5003.9  345.36  5009.2  341.48  5009.7  340.98  5019.3  340.98  5019.8  341.48
  5042.8  346.81  5056.9  347.42    5105  346.87  5127.6  345.82    5170   346.5
  5353.9  351.26    5368  352.67  5424.6  355.41  5495.3  361.16    5566  364.62
#Mann= 6 ,-1 , 0
  4303.9     .07       0  4358.7    .035       0  4861.8      .1       0
  5009.2     .05       0  5019.8      .1       0    5105     .12       0
Bank Sta=5009.2,5019.8
XS Rating Curve= 0 ,0
Exp/Cntr=0.3,0.1

Type RM Length L Ch R = 1 ,5104    ,567,567,567
BEGIN DESCRIPTION:
Elm Creek 3 6.0
END DESCRIPTION:
XS GIS Cut Line= 3
        2522305.     13827111.28      2521943.66     13826041.44
      2521208.41     13825546.56
#Sta/Elev= 30
  4012.9  358.13  4209.5  354.33  4253.7   354.6    4389  353.24  4404.8  353.84
  4766.5  348.76  4813.1  348.64  4832.3  347.24  4970.4  347.26    4980  345.96
  5001.9  346.37  5016.8   341.1  5017.3   340.6  5027.6   341.1    5028   346.4
  5117.1  346.05  5142.1  345.55  5145.6  344.18  5204.5  345.58  5310.6  347.24
  5490.5  352.54  5598.6  358.91  5649.5  360.33  5685.5  362.81  5694.4  362.43
  5700.4  363.46    5782  366.66  5931.4  372.53  5946.3  373.88  6028.4  376.25
#Mann= 8 ,-1 , 0
  4012.9     .07       0  4253.7     .12       0  4404.8    .035       0
  4766.5      .1       0  5016.8     .05       0  5027.6      .1       0
  5204.5     .12       0    5782     .07       0
Bank Sta=5016.8,5027.6
XS Rating Curve= 0 ,0
Exp/Cntr=0.3,0.1

Type RM Length L Ch R = 1 ,4537    ,466,466,466
BEGIN DESCRIPTION:
Elm Creek 3 5.0
END DESCRIPTION:
XS GIS Cut Line= 3
      2522874.97     13826874.96        2522175.       13825775.
      2521375.01       13825575.
#Sta/Elev= 30
  3695.8  363.53    3713  363.68  3826.1  360.58  3885.4  360.15  3970.1  357.15
  4181.7  351.98  4376.5  351.06  4535.5   348.6    4614   347.2  4732.8  345.38
    4898  344.51  4919.2  341.72  4940.3  344.22  4976.7  344.82  5004.4  341.58
  5004.9  341.08  5015.3  341.58  5017.6  343.82  5022.8  345.26  5067.9  344.69
  5168.8  346.18  5182.6  345.64  5216.1  347.35  5269.6  348.09  5422.2  352.38
  5476.3  355.28  5525.3  356.64  5535.6  356.09  5619.4  360.86  5824.2  370.09
#Mann= 12 ,-1 , 0
  3695.8    .035       0    3713     .07       0  4376.5     .05       0
  4535.5     .07       0    4614     .05       0  4732.8      .1       0
  5004.4     .05       0  5015.3      .1       0  5067.9     .12       0
  5168.8    .035       0  5269.6     .12       0  5619.4     .07       0
Bank Sta=5004.4,5015.3
XS Rating Curve= 0 ,0
Exp/Cntr=0.3,0.1

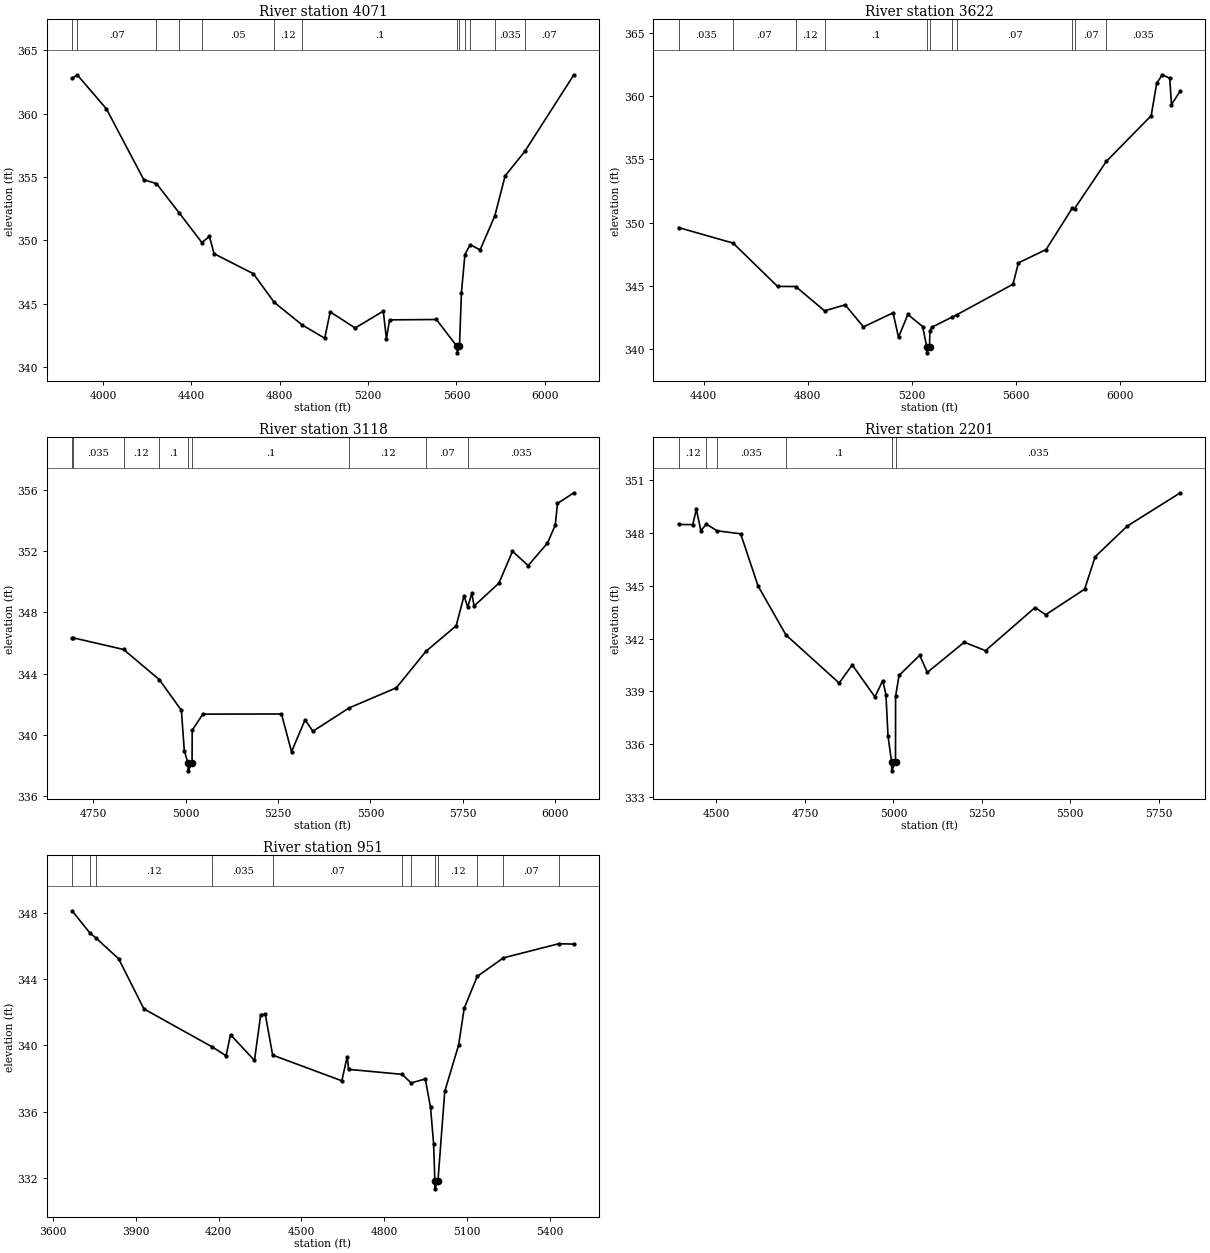
Type RM Length L Ch R = 1 ,4071    ,449,449,449
BEGIN DESCRIPTION:
Elm Creek 3 4.0
END DESCRIPTION:
XS GIS Cut Line= 3
      2522875.01     13826775.04        2522575.       13825675.
      2521774.99     13824874.99
#Sta/Elev= 30
  3860.1  362.77  3883.7  363.05  4015.6  360.37  4184.9  354.78  4242.1  354.48
  4344.9  352.17  4447.7  349.83  4482.1  350.31  4502.8  348.95  4680.7  347.37
  4775.4  345.11  4901.8  343.33  5003.9  342.28  5028.6  344.36  5141.7  343.09
    5269  344.42  5283.2  342.23  5297.3  343.73  5509.4  343.76    5603  341.63
  5603.5  341.13  5613.9  341.63  5622.6  345.85  5638.5  348.88  5662.2  349.66
  5707.4  349.25    5774  351.94  5820.6  355.09  5909.5  357.01  6131.7  363.06
#Mann= 13 ,-1 , 0
  3860.1    .035       0  3883.7     .07       0  4242.1     .05       0
  4344.9     .07       0  4447.7     .05       0  4775.4     .12       0
  4901.8      .1       0    5603     .05       0  5613.9      .1       0
  5638.5     .12       0  5662.2     .07       0    5774    .035       0
  5909.5     .07       0
Bank Sta=5603,5613.9
XS Rating Curve= 0 ,0
Exp/Cntr=0.3,0.1

Type RM Length L Ch R = 1 ,3622    ,504,504,504
BEGIN DESCRIPTION:
X19136
END DESCRIPTION:
XS GIS Cut Line= 3
      2523027.65     13825970.61      2522949.71     13825474.65
      2521886.97     13824525.26
#Sta/Elev= 30
    4304  349.61  4513.5  348.38  4684.2  344.96    4754  344.95  4864.9  343.03
  4943.9   343.5  5014.2  341.76  5127.9  342.87  5148.8  340.94  5184.7  342.74
  5241.5  341.79    5257  340.21  5257.5  339.71    5268  340.21  5269.2  341.46
  5276.7  341.73    5353  342.52  5372.7  342.72  5588.5  345.13  5609.4  346.82
  5715.6  347.87  5815.4  351.12  5825.2  351.11  5946.7  354.83  6119.3  358.45
  6140.3  361.01    6162  361.68  6190.4  361.41  6197.1  359.32  6231.1  360.41
#Mann= 11 ,-1 , 0
    4304    .035       0  4513.5     .07       0    4754     .12       0
  4864.9      .1       0    5257     .05       0    5268      .1       0
    5353     .12       0  5372.7     .07       0  5815.4      .1       0
  5825.2     .07       0  5946.7    .035       0
Bank Sta=5257,5268
XS Rating Curve= 0 ,0
Exp/Cntr=0.3,0.1

Type RM Length L Ch R = 1 ,3118    ,917,917,917
BEGIN DESCRIPTION:
Elm Creek 3 3.0
END DESCRIPTION:
XS GIS Cut Line= 3
      2523275.62     13825439.22       2523048.9     13825056.64
      2522274.96     13824574.98
#Sta/Elev= 30
  4693.4  346.34  4696.5  346.34  4832.6  345.58  4929.1  343.61  4988.9   341.6
  4996.7  338.97  5006.6  338.14  5007.1  337.64  5017.7  338.14  5018.1   340.3
    5047  341.35  5259.4  341.36  5286.6  338.89  5323.1  340.98  5344.4  340.23
  5442.5  341.76  5569.8  343.07    5650  345.46  5731.6  347.13  5752.8  349.08
  5762.9  348.36    5774  349.26  5779.9  348.42  5847.2  349.92  5883.8     352
  5926.3  351.07  5978.3  352.54  5999.5  353.72  6005.4  355.13  6049.7  355.83
#Mann= 9 ,-1 , 0
  4693.4     .07       0  4696.5    .035       0  4832.6     .12       0
  4929.1      .1       0  5006.6     .05       0  5017.7      .1       0
  5442.5     .12       0    5650     .07       0  5762.9    .035       0
Bank Sta=5006.6,5017.7
XS Rating Curve= 0 ,0
Exp/Cntr=0.3,0.1

Type RM Length L Ch R = 1 ,2201    ,1250,1250,1250
BEGIN DESCRIPTION:
Elm Creek 3 2.0
END DESCRIPTION:
XS GIS Cut Line= 4
      2523656.35     13825220.25      2523447.81     13824839.65
       2523140.7     13824656.35      2522514.61     13824641.54
#Sta/Elev= 30
  4392.8  348.49    4433  348.48  4443.2  349.35  4455.8  348.14  4471.7  348.51
  4501.5  348.13  4568.3  347.96  4617.6  344.99  4696.4  342.21  4846.6  339.48
  4883.6  340.51  4947.8  338.69  4969.8  339.62  4978.9  338.81  4984.7  336.47
  4994.8  334.99  4995.3  334.49  5005.9  334.99  5006.1  338.72  5015.9  339.91
  5074.3  341.06  5095.7  340.08  5200.1   341.8  5260.2  341.32  5400.2  343.77
  5430.2  343.36  5540.2  344.81  5570.2  346.66  5660.3  348.39  5810.7  350.29
#Mann= 6 ,-1 , 0
  4392.8     .12       0  4471.7     .07       0  4501.5    .035       0
  4696.4      .1       0  4994.8     .05       0  5005.9    .035       0
Bank Sta=4994.8,5005.9
XS Rating Curve= 0 ,0
Exp/Cntr=0.3,0.1

Type RM Length L Ch R = 1 ,951     ,0,0,0
BEGIN DESCRIPTION:
Elm Creek 3 1.0
END DESCRIPTION:
XS GIS Cut Line= 3
      2523750.28     13825212.55      2524090.38     13824603.21
      2523941.59     13823490.84
#Sta/Elev= 30
  3668.2  348.12  3733.4  346.77  3753.4   346.5  3837.3  345.22  3928.7   342.2
  4177.1   339.9  4226.9  339.37  4242.9  340.64  4329.8  339.09  4352.5  341.86
  4369.1  341.87  4395.7  339.41  4646.7  337.86  4666.2  339.32  4671.3  338.55
  4865.3  338.25  4897.9  337.73  4949.4  337.97  4968.4  336.26  4979.6  334.06
    4984  331.84  4984.5  331.34  4995.4  331.84    5020  337.22  5070.5  340.03
  5090.6  342.24  5137.8  344.16  5232.9  345.28  5433.4  346.13  5488.3  346.11
#Mann= 12 ,-1 , 0
  3668.2     .12       0  3733.4     .07       0  3753.4     .12       0
  4177.1    .035       0  4395.7     .07       0  4865.3      .1       0
  4897.9     .12       0    4984     .05       0  4995.4     .12       0
  5137.8     .05       0  5232.9     .07       0  5433.4     .05       0
Bank Sta=4984,4995.4
XS Rating Curve= 0 ,0
Exp/Cntr=0.3,0.1

Chan Stop Cuts=-1
Use User Specified Reach Order=0
Composite Channel Slope=5