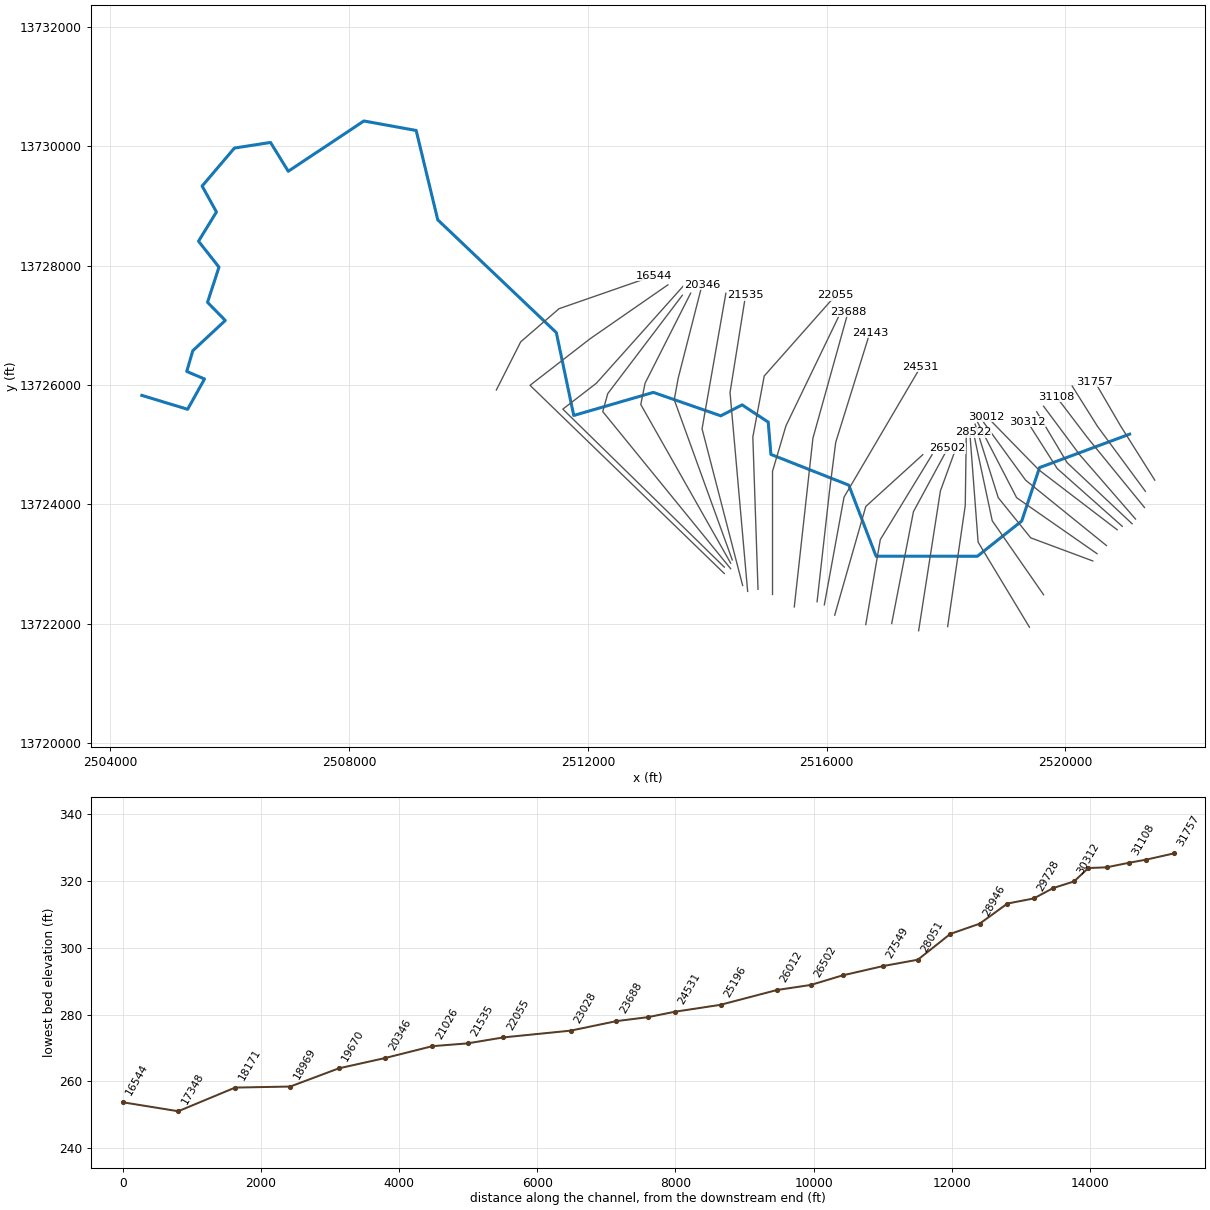
--- GELHORN CREEK.prj (project) ---

Proj Title=GELHORN CREEK Base Level Engineering
Current Plan=p01
Default Exp/Contr=0.3,0.1
English Units
Geom File=g01
Flow File=f01
Plan File=p01
Y Axis Title=Elevation
X Axis Title(PF)=Main Channel Distance
X Axis Title(XS)=Station
BEGIN DESCRIPTION:
GELHORN CREEK
END DESCRIPTION:
DSS Export Rating Curves= 0
DSS Export Rating Curve Sorted= 0
DSS Export Volume Flow Curves= 0
DXF OffsetX= 0
DXF OffsetY= 0
DXF ScaleX= 1
DXF ScaleY= 10

--- GELHORN CREEK.p01 (plan) ---

Plan Title=Multiple Run
Short Identifier=Multiple
Geom File=g01
Flow File=f01
Subcritical Flow
K Sum by GR= 0
Std Step Tol= 0.01
Critical Tol= 0.01
Num of Std Step Trials= 20
Max Error Tol= 0.3
Flow Tol Ratio= 0.001
Split Flow NTrial= 30
Split Flow Tol= 0.02
Split Flow Ratio= 0.02
Log Output Level= 0
Friction Slope Method= 1
Unsteady Friction Slope Method= 2
Unsteady Bridges Friction Slope Method= 1
Parabolic Critical Depth
Global Vel Dist=  1 , 1 , 1
Global Log Level= 0
CheckData=True
Encroach Param= -1, 0, 0, 0
BEGIN DESCRIPTION:
Multiple Run
END DESCRIPTION:

--- GELHORN CREEK.f01 (steady flow) ---

Flow Title=Multiple
Number of Profiles=7
Profile Names=10-year,25-year,50-year,1pct_min,100-year,1pct_plu,500-year
River Rch & RM= GELHORN CREEK,Reach-1,31757
    1019    1691    2318    1539    3070    6125    5329
River Rch & RM= GELHORN CREEK,Reach-1,28051
    1868    3197    4471    3022    6031   12033   10867
River Rch & RM= GELHORN CREEK,Reach-1,23028
    1959    3331    4635    3115    6215   12400   11068
River Rch & RM= GELHORN CREEK,Reach-1,15183
    2194    3744    5224    3518    7019   14005   12554
River Rch & RM= GELHORN CREEK,Reach-1,13142
    2757    4730    6623    4470    8919   17797   16031
Boundary for River Rch & Prof#=GELHORN CREEK,Reach-1,1
Up Type=0
Dn Type=3
Dn Slope=0.005
Boundary for River Rch & Prof#=GELHORN CREEK,Reach-1,2
Up Type=0
Dn Type=3
Dn Slope=0.005
Boundary for River Rch & Prof#=GELHORN CREEK,Reach-1,3
Up Type=0
Dn Type=3
Dn Slope=0.005
Boundary for River Rch & Prof#=GELHORN CREEK,Reach-1,4
Up Type=0
Dn Type=3
Dn Slope=0.005
Boundary for River Rch & Prof#=GELHORN CREEK,Reach-1,5
Up Type=0
Dn Type=3
Dn Slope=0.005
Boundary for River Rch & Prof#=GELHORN CREEK,Reach-1,6
Up Type=0
Dn Type=3
Dn Slope=0.005
Boundary for River Rch & Prof#=GELHORN CREEK,Reach-1,7
Up Type=0
Dn Type=3
Dn Slope=0.005

--- GELHORN CREEK.g01 (geometry) ---

Geom Title=Existing Conditions
Program Version=4.10

River Reach=GELHORN CREEK   ,Reach-1
Reach XY= 30
        2521075.       13725175.      2519565.32     13724614.24
      2519266.98     13723718.62      2518523.58     13723128.04
      2516826.48     13723128.46      2516369.56     13724319.75
      2515064.82     13724835.33      2515019.17     13725377.31
      2514581.55     13725665.76       2514224.9     13725482.32
      2513095.05     13725875.21      2511761.68     13725488.37
      2511469.54     13726877.45      2509482.86     13728768.79
      2509121.45      13730266.5      2508245.58     13730425.63
      2506978.61     13729582.46      2506681.67     13730065.71
      2506076.46     13729971.48      2505535.52     13729334.79
       2505775.5     13728900.04      2505475.25     13728409.78
      2505817.93     13727974.99      2505625.86     13727385.31
      2505923.47     13727080.83      2505378.52     13726573.54
      2505277.99      13726226.4      2505575.55     13726099.89
      2505292.56     13725591.62        2504525.       13725825.

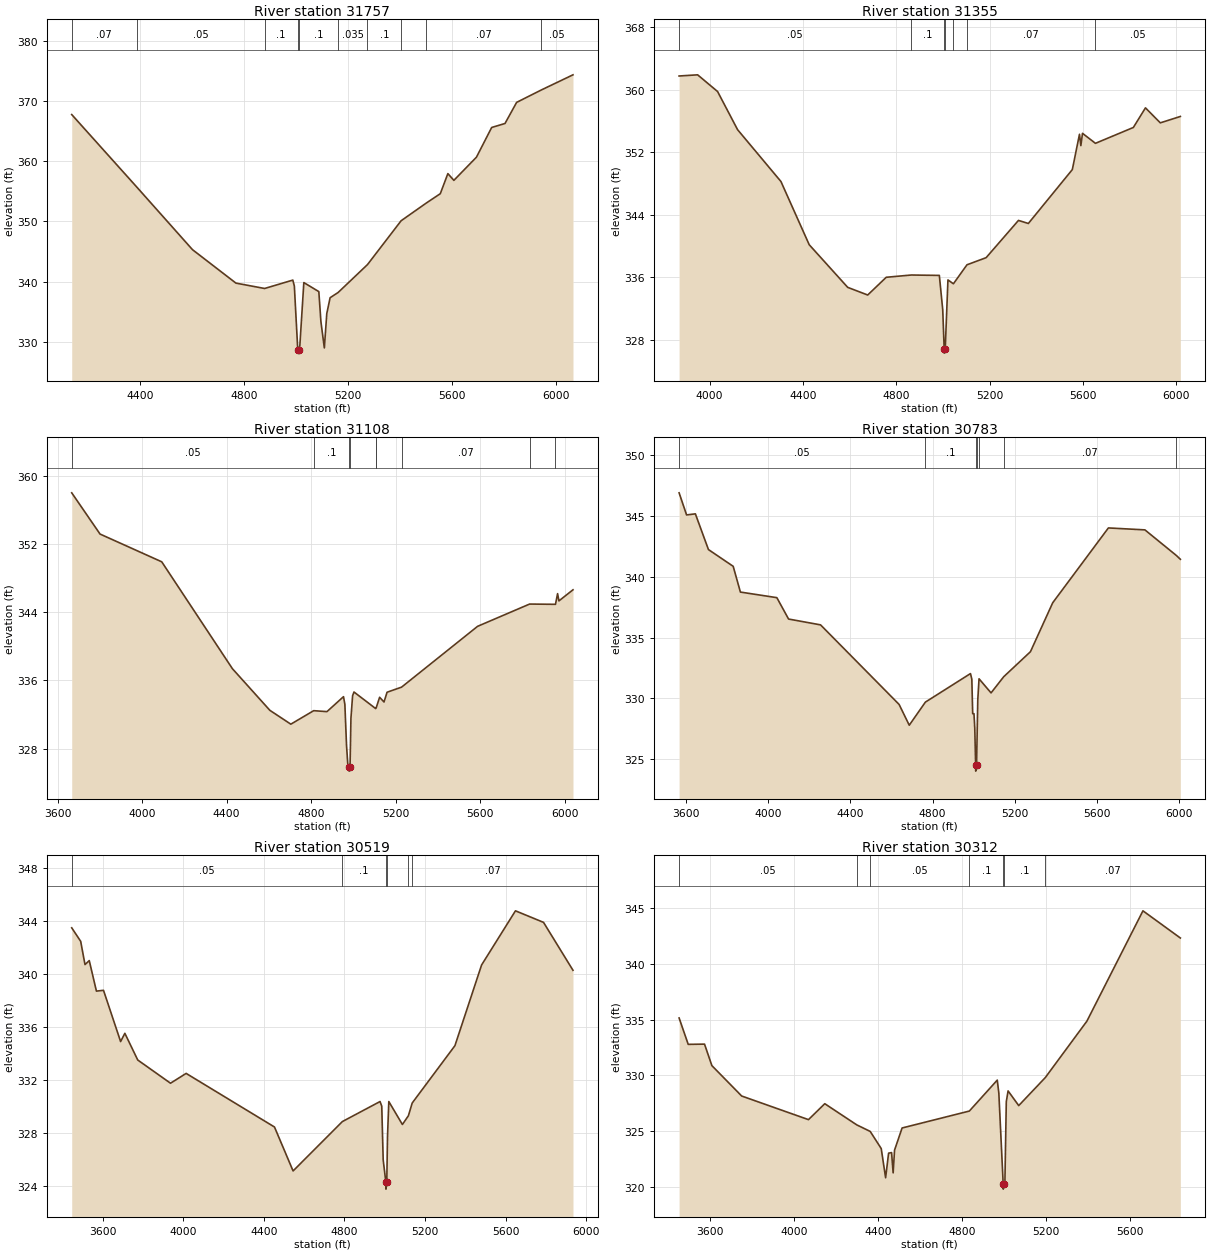
Type RM Length L Ch R = 1 ,31757   ,402,402,402
BEGIN DESCRIPTION:
A18951
END DESCRIPTION:
XS GIS Cut Line= 3
      2521495.69     13724403.76      2520922.42     13725313.84
        2520493.       13726051.
#Sta/Elev= 30
  4135.9  367.73  4386.6  355.69  4600.5  345.33  4767.7  339.78  4878.2  338.89
  4986.6  340.28  4992.5  339.29  5005.7  328.67  5005.9  328.17    5010  328.67
  5013.7  329.46    5029  339.87  5086.7  338.37  5094.7   333.4  5107.9  329.03
  5117.3  334.73  5130.1  337.36  5160.8  338.22  5273.9  342.85  5403.3  350.12
  5500.6  353.07  5554.1  354.61  5583.2  357.94  5606.3  356.82  5693.1  360.66
  5751.8  365.59    5803  366.25  5847.8  369.75  5941.9  371.79  6064.6  374.32
#Mann= 10 ,-1 , 0
  4135.9     .07       0  4386.6     .05       0  4878.2      .1       0
  5005.7     .05       0    5010      .1       0  5160.8    .035       0
  5273.9      .1       0  5403.3     .05       0  5500.6     .07       0
  5941.9     .05       0
Bank Sta=5005.7,5010
XS Rating Curve= 0 ,0
Exp/Cntr=0.3,0.1

Type RM Length L Ch R = 1 ,31355   ,247,247,247
BEGIN DESCRIPTION:
A18950
END DESCRIPTION:
XS GIS Cut Line= 3
      2521338.06      13724217.4      2520535.44     13725306.67
      2520112.72     13725980.16
#Sta/Elev= 30
  3869.6  361.78    3949  361.93  4034.6  359.79  4120.2  354.91  4306.1  348.27
  4427.2  340.18  4592.2  334.72  4677.9  333.74  4757.3  336.01  4864.9   336.3
  4984.9  336.25  4999.5  331.84  5005.7   326.8    5006   326.3  5010.1   326.8
  5021.8  335.67  5045.2  335.18  5103.4  337.61  5185.4  338.52    5324  343.29
  5366.4   342.9  5554.9   349.8  5585.5  354.32  5591.4  352.87  5598.5  354.44
  5653.9  353.16  5816.4  355.19  5868.3   357.7  5931.9  355.78  6017.8   356.6
#Mann= 7 ,-1 , 0
  3869.6     .05       0  4864.9      .1       0  5005.7     .05       0
  5010.1      .1       0  5045.2    .035       0  5103.4     .07       0
  5653.9     .05       0
Bank Sta=5005.7,5010.1
XS Rating Curve= 0 ,0
Exp/Cntr=0.3,0.1

Type RM Length L Ch R = 1 ,31108   ,325,325,325
BEGIN DESCRIPTION:
A18949
END DESCRIPTION:
XS GIS Cut Line= 3
      2521323.75     13723945.06      2520370.62     13725113.18
      2519847.91     13725800.58
#Sta/Elev= 30
  3667.2  357.98  3801.2  353.15    4093   349.9  4427.3  337.38  4604.6   332.5
  4703.7  330.88  4811.8  332.46  4874.6  332.35  4952.8   334.1  4959.3  333.21
  4967.2  328.38  4973.7  325.97  4979.4  325.88  4979.7  325.38  4983.8  325.88
    4988  331.58  4995.9  334.21  5002.4  334.65  5104.9  332.71    5107  332.76
  5123.7  334.03  5144.5  333.48  5158.9  334.62  5227.7  335.22  5587.1  342.34
  5833.2  344.95  5955.6  344.92  5965.6  346.17  5971.9  345.32  6038.4  346.62
#Mann= 9 ,-1 , 0
  3667.2     .05       0  4811.8      .1       0  4979.4     .05       0
  4983.8      .1       0  5104.9    .035       0    5107      .1       0
  5227.7     .07       0  5833.2     .12       0  5955.6     .07       0
Bank Sta=4979.4,4983.8
XS Rating Curve= 0 ,0
Exp/Cntr=0.3,0.1

Type RM Length L Ch R = 1 ,30783   ,264,264,264
BEGIN DESCRIPTION:
A18948
END DESCRIPTION:
XS GIS Cut Line= 3
      2521173.24     13723751.59      2520234.46      13724833.7
      2519632.49     13725643.49
#Sta/Elev= 30
  3565.5  346.92    3602   345.1  3644.8  345.19  3708.4  342.25    3829  340.87
  3864.1  338.75  4041.7  338.29  4098.7  336.53  4254.5  336.05  4637.2   329.5
  4686.6  327.79  4765.1  329.69  4984.8  332.04  4991.4  331.58  4995.6  328.74
  5001.8  328.74  5005.7  327.56    5010  324.51  5010.3  324.01  5014.4  324.51
  5020.4  329.89  5026.5  331.61    5085  330.45  5146.7  331.78  5276.9  333.84
  5385.4  337.87  5656.6  344.03  5834.5  343.87  5987.8  341.76  6007.1  341.45
#Mann= 7 ,-1 , 0
  3565.5     .05       0  4765.1      .1       0    5010     .05       0
  5014.4      .1       0  5026.5    .035       0  5146.7     .07       0
  5987.8     .12       0
Bank Sta=5010,5014.4
XS Rating Curve= 0 ,0
Exp/Cntr=0.3,0.1

Type RM Length L Ch R = 1 ,30519   ,207,207,207
BEGIN DESCRIPTION:
A18947
END DESCRIPTION:
XS GIS Cut Line= 3
      2521115.88     13723672.79      2520026.64     13724697.54
      2519517.91      13725550.2
#Sta/Elev= 30
  3446.6  343.49  3491.1  342.47  3512.5  340.72  3533.6  341.02  3569.2  338.72
  3604.4  338.78  3689.3  334.92  3710.4  335.54  3774.3  333.53    3937  331.78
  4014.6  332.52  4453.2  328.48  4545.5  325.17  4790.1  328.89  4977.2   330.4
  4985.7  330.05  4992.8  326.01  5006.2   324.3  5006.5   323.8  5010.6   324.3
  5014.2  327.73  5020.7   330.4  5088.2  328.67    5118  329.33  5136.9  330.29
    5349  334.61  5481.3  340.69  5649.5  344.77  5788.8   343.9    5935  340.29
#Mann= 6 ,-1 , 0
  3446.6     .05       0  4790.1      .1       0  5006.2     .05       0
  5010.6      .1       0    5118    .035       0  5136.9     .07       0
Bank Sta=5006.2,5010.6
XS Rating Curve= 0 ,0
Exp/Cntr=0.3,0.1

Type RM Length L Ch R = 1 ,30312   ,300,300,300
BEGIN DESCRIPTION:
A18946
END DESCRIPTION:
XS GIS Cut Line= 3
      2520951.07     13723629.78      2519861.81     13724597.21
      2519360.18     13725385.49
#Sta/Elev= 30
  3451.3  335.16  3494.8  332.79  3572.6  332.81  3607.7  330.88  3749.9  328.15
  4068.5  326.03  4146.3  327.46  4298.8  325.56  4363.1  324.97  4415.6  323.43
  4436.5  320.81  4450.7  323.02  4464.9  323.07  4472.4  321.25  4479.1  323.29
  4515.1  325.28  4835.9   326.8  4969.1  329.58  4976.6  328.41  4997.3  320.29
  4997.6  319.79  5001.7  320.29  5005.5  320.39  5012.2  327.64  5020.7  328.61
  5071.5  327.29  5198.4  329.81  5396.6  334.87  5664.1  344.78  5842.5  342.34
#Mann= 7 ,-1 , 0
  3451.3     .05       0  4298.8     .07       0  4363.1     .05       0
  4835.9      .1       0  4997.3     .05       0  5001.7      .1       0
  5198.4     .07       0
Bank Sta=4997.3,5001.7
XS Rating Curve= 0 ,0
Exp/Cntr=0.3,0.1

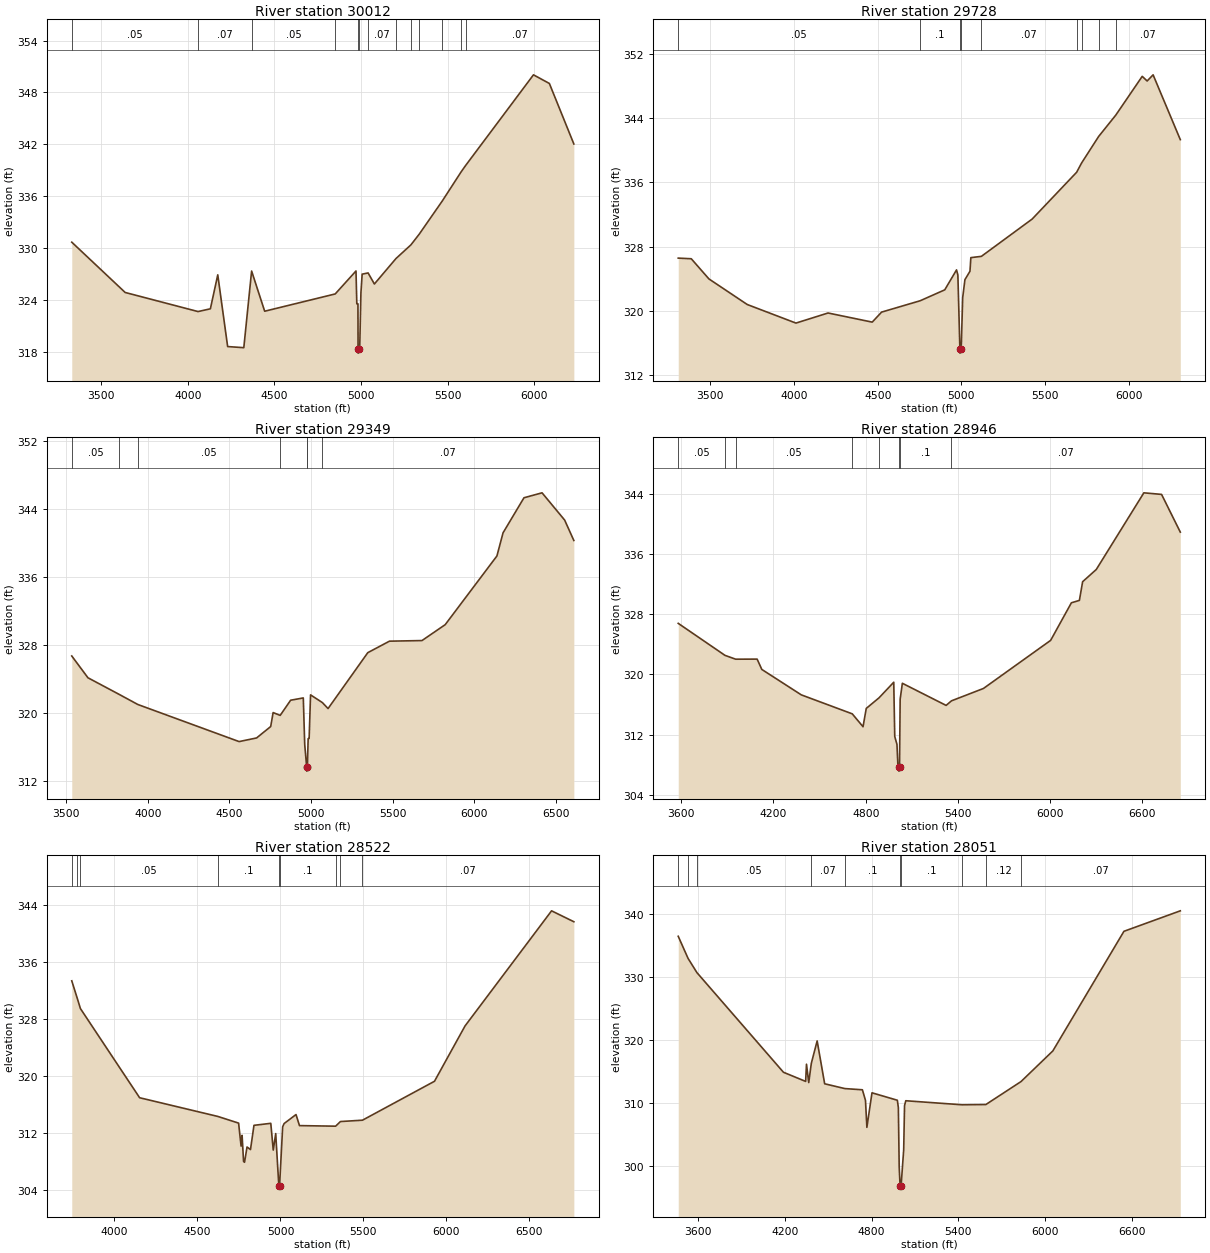
Type RM Length L Ch R = 1 ,30012   ,284,284,284
BEGIN DESCRIPTION:
A18945
END DESCRIPTION:
XS GIS Cut Line= 3
      2520865.09     13723572.44      2519553.66     13724575.71
      2518680.42     13725470.43
#Sta/Elev= 30
  3328.7  330.67  3637.3  324.85  4058.5  322.64  4129.7  322.96  4172.4  326.89
  4229.5  318.59  4322.9  318.46    4368  327.33  4443.5  322.68  4851.2  324.68
  4971.2  327.34  4975.9  323.54  4982.5  323.54  4983.2  318.33  4983.5  317.83
  4987.7  318.33  4992.7  318.44  4999.6  324.78  5006.8  326.97  5041.2  327.11
  5077.4  325.83  5202.4  328.78  5288.6  330.36  5336.3  331.59  5470.2  335.45
  5578.8  338.81  5604.1  339.53  5996.8  350.04  6088.7  349.04  6230.1  342.04
#Mann= 13 ,-1 , 0
  3328.7     .05       0  4058.5     .07       0    4368     .05       0
  4851.2      .1       0  4983.2     .05       0  4987.7      .1       0
  5041.2     .07       0  5202.4    .035       0  5288.6     .07       0
  5336.3    .035       0  5470.2     .07       0  5578.8    .035       0
  5604.1     .07       0
Bank Sta=4983.2,4987.7
XS Rating Curve= 0 ,0
Exp/Cntr=0.3,0.1

Type RM Length L Ch R = 1 ,29728   ,379,379,379
BEGIN DESCRIPTION:
A18944
END DESCRIPTION:
XS GIS Cut Line= 3
      2520685.97     13723307.25      2519331.51     13724403.72
      2518593.89     13725420.63
#Sta/Elev= 30
  3308.6  326.56  3386.5  326.48  3492.1  323.96  3720.7  320.77  4011.7  318.45
  4203.5  319.71  4467.3  318.57  4523.3  319.82    4754  321.24  4900.5   322.6
  4970.9  325.09  4978.9  324.45    4991   315.2  4991.3   314.7  4995.5   315.2
  4999.7  315.82  5007.6  321.61    5021  323.87  5051.2  324.92  5056.4  326.62
  5119.4  326.78  5422.9  331.44  5688.4  337.28  5717.8  338.43  5819.9  341.75
  5922.1  344.41    6080  349.25  6109.4  348.67    6145  349.44  6307.5  341.35
#Mann= 9 ,-1 , 0
  3308.6     .05       0    4754      .1       0    4991     .05       0
  4995.5      .1       0  5119.4     .07       0  5688.4    .035       0
  5717.8     .07       0  5819.9    .035       0  5922.1     .07       0
Bank Sta=4991,4995.5
XS Rating Curve= 0 ,0
Exp/Cntr=0.3,0.1

Type RM Length L Ch R = 1 ,29349   ,403,403,403
BEGIN DESCRIPTION:
A18943
END DESCRIPTION:
XS GIS Cut Line= 3
      2520528.28     13723171.13      2519181.02     13724109.91
      2518521.71     13725385.52
#Sta/Elev= 30
  3533.2  326.72  3632.4  324.16  3825.4  322.19  3938.1  321.02  4559.1  316.66
  4666.4  317.09  4752.8  318.43  4767.6  320.07    4811  319.74  4874.9  321.52
  4952.6  321.79  4961.3  316.33  4973.2  313.69  4973.5  313.19  4977.7  313.69
  4982.3     317  4988.4  317.03  4997.1  322.15  5069.9  321.24  5104.4  320.54
    5348  327.11  5480.9  328.46  5680.2  328.53  5822.6   330.4  6139.6  338.47
  6177.2  341.19  6305.5  345.31  6416.3  345.89  6554.8  342.69  6611.2  340.29
#Mann= 7 ,-1 , 0
  3533.2     .05       0  3825.4    .035       0  3938.1     .05       0
    4811      .1       0  4973.2     .05       0  4977.7      .1       0
  5069.9     .07       0
Bank Sta=4973.2,4977.7
XS Rating Curve= 0 ,0
Exp/Cntr=0.3,0.1

Type RM Length L Ch R = 1 ,28946   ,424,424,424
BEGIN DESCRIPTION:
A18942
END DESCRIPTION:
XS GIS Cut Line= 4
      2520456.65     13723049.29      2519417.51     13723436.28
      2518872.87     13724109.91      2518486.29     13725341.22
#Sta/Elev= 30
  3580.4  326.79  3884.3  322.54  3953.9  322.03  4093.6  322.04    4124  320.67
  4380.9  317.29  4712.3  314.77  4782.4  313.06  4803.4  315.49  4886.6   316.9
  4982.2  318.97  4988.7  311.76    5003  310.72  5009.5  307.79  5015.2  307.66
  5015.5  307.16  5019.7  307.66  5023.9  316.71  5038.2  318.83  5322.8  315.89
  5357.8   316.5  5565.6  318.14  6002.7  324.53  6137.6  329.52  6189.7  329.84
  6210.7  332.32  6299.7  333.95    6609  344.13  6724.3  343.92  6846.1  338.91
#Mann= 8 ,-1 , 0
  3580.4     .05       0  3884.3    .035       0  3953.9     .05       0
  4712.3     .12       0  4886.6      .1       0  5015.2     .05       0
  5019.7      .1       0  5357.8     .07       0
Bank Sta=5015.2,5019.7
XS Rating Curve= 0 ,0
Exp/Cntr=0.3,0.1

Type RM Length L Ch R = 1 ,28522   ,471,471,471
BEGIN DESCRIPTION:
A18941
END DESCRIPTION:
XS GIS Cut Line= 3
      2519632.47     13722483.19      2518772.54     13723722.93
      2518457.24      13725206.3
#Sta/Elev= 30
  3742.6  333.33  3776.5  330.82  3794.7  329.44  4151.5  316.93  4622.2  314.31
  4747.9  313.37  4762.8  310.15  4768.9  311.66  4777.7     308  4783.7  307.88
  4798.6  310.02  4819.5  309.66  4840.5  313.06  4941.8  313.34  4956.7  309.59
  4971.5   311.9  4990.2  304.61  4990.5  304.11  4994.7  304.61  5013.4  312.86
  5022.2  313.31  5093.8  314.57  5114.7  313.02  5332.5  312.94  5361.5  313.59
  5494.4  313.78  5928.2  319.24  6112.3     327  6633.7  343.15  6767.9  341.62
#Mann= 9 ,-1 , 0
  3742.6     .05       0  3776.5     .07       0  3794.7     .05       0
  4622.2      .1       0  4990.2     .05       0  4994.7      .1       0
  5332.5     .07       0  5361.5     .12       0  5494.4     .07       0
Bank Sta=4990.2,4994.7
XS Rating Curve= 0 ,0
Exp/Cntr=0.3,0.1

Type RM Length L Ch R = 1 ,28051   ,502,502,502
BEGIN DESCRIPTION:
A18940
END DESCRIPTION:
XS GIS Cut Line= 3
      2519396.02     13721938.51      2518536.06     13723364.62
       2518399.9     13725163.34
#Sta/Elev= 30
  3464.6   336.5  3532.4     333  3593.7  330.74  4191.6  314.93  4344.9  313.48
  4350.8  316.21  4366.3  313.29  4384.3  316.36  4424.5   319.9  4476.4   313.1
  4616.1  312.34  4737.1  312.15  4758.4  310.47  4768.1  306.19  4803.4  311.67
  4978.6  310.49  4985.6  309.32  4991.4  299.89  4997.7  296.89  4998.2  296.39
  5004.4  296.89  5022.5  302.66  5028.3  309.65    5037  310.41  5426.1  309.77
  5590.2  309.81    5833  313.45  6052.9  318.31  6544.3  337.29  6933.8  340.54
#Mann= 10 ,-1 , 0
  3464.6     .05       0  3532.4     .07       0  3593.7     .05       0
  4384.3     .07       0  4616.1      .1       0  4997.7     .05       0
  5004.4      .1       0  5426.1     .07       0  5590.2     .12       0
    5833     .07       0
Bank Sta=4997.7,5004.4
XS Rating Curve= 0 ,0
Exp/Cntr=0.3,0.1

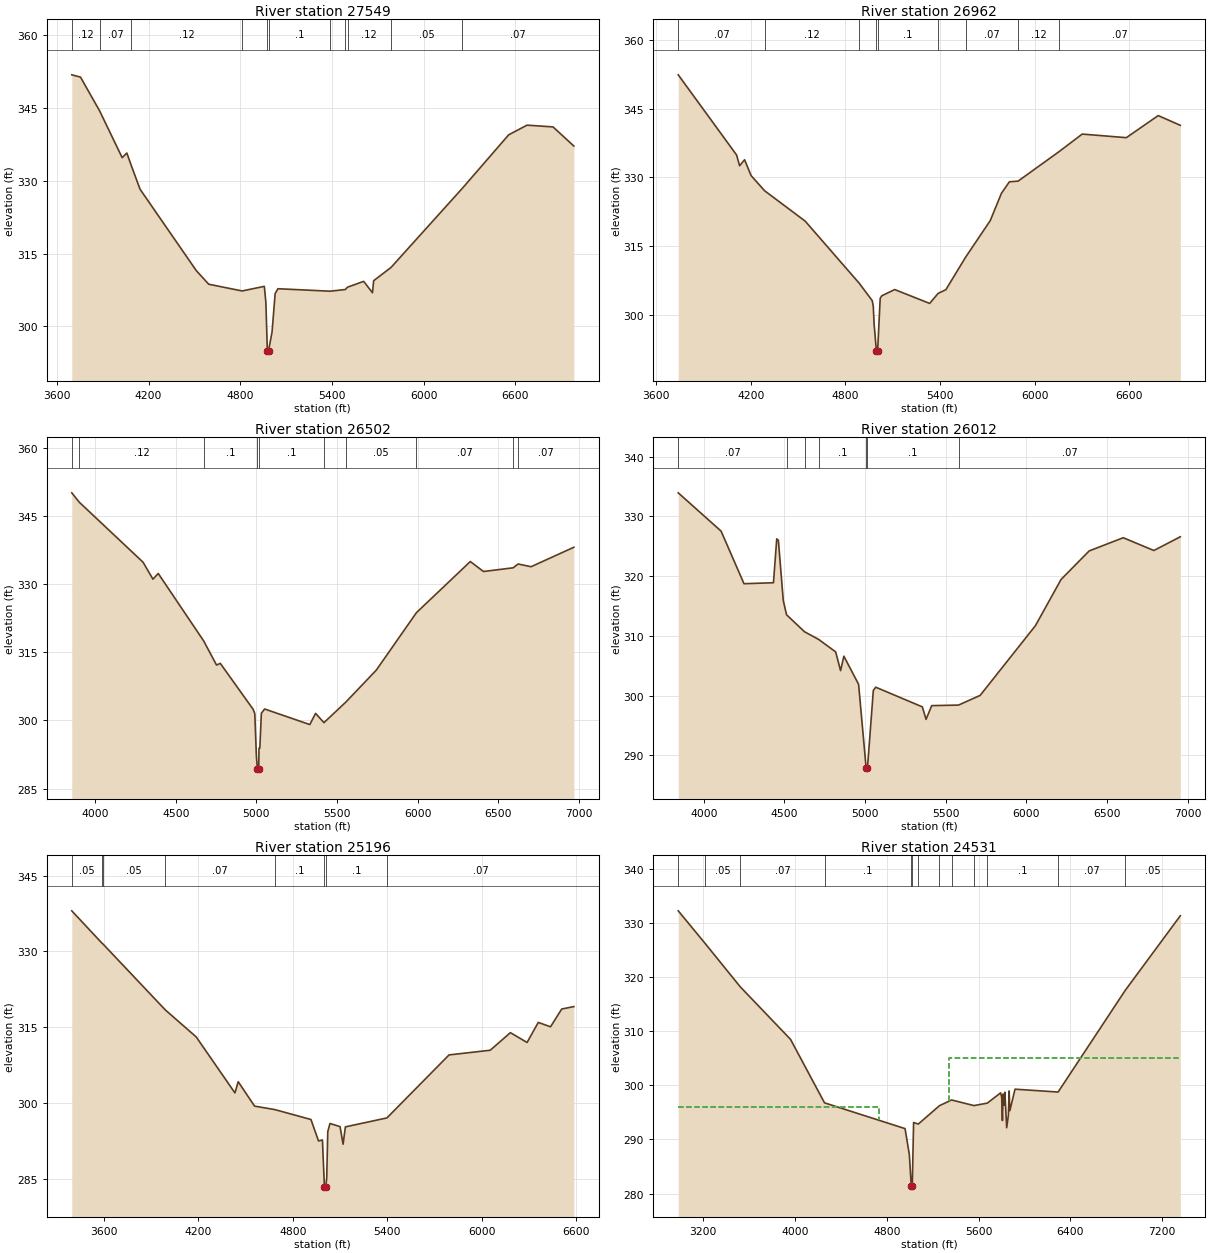
Type RM Length L Ch R = 1 ,27549   ,587,587,587
BEGIN DESCRIPTION:
A18939
END DESCRIPTION:
XS GIS Cut Line= 3
      2518025.69     13721948.54      2518320.83      13723979.8
      2518338.18     13725211.18
#Sta/Elev= 30
  3697.6  351.89  3754.7  351.42  3879.6  344.47  4027.5   334.8  4057.8  335.77
  4088.1  333.08  4144.3   328.3  4512.5   311.5  4593.4  308.71  4811.9  307.32
  4957.2  308.27  4967.3  304.93    4977     295  4977.5   294.5  4984.8     295
  5007.7  298.88  5027.9  306.78    5046  307.78  5386.8  307.27  5486.7  307.61
  5501.6   308.1  5607.1   309.3  5664.5  306.96  5672.2  309.43  5785.9  312.17
  6251.9  328.47  6555.5  339.52  6675.5  341.51  6845.5  341.15  6981.7  337.21
#Mann= 11 ,-1 , 0
  3697.6     .12       0  3879.6     .07       0  4088.1     .12       0
  4811.9      .1       0    4977     .05       0  4984.8      .1       0
  5386.8     .12       0  5486.7     .07       0  5501.6     .12       0
  5785.9     .05       0  6251.9     .07       0
Bank Sta=4977,4984.8
XS Rating Curve= 0 ,0
Exp/Cntr=0.3,0.1

Type RM Length L Ch R = 1 ,26962   ,460,460,460
BEGIN DESCRIPTION:
A18938
END DESCRIPTION:
XS GIS Cut Line= 3
      2517539.58     13721879.11      2517904.17     13724222.86
      2518181.96     13724986.78
#Sta/Elev= 30
  3739.3  352.34  4109.6  334.87  4128.6  332.53  4160.2  333.84  4201.6  330.38
  4287.2  327.09  4544.8  320.46  4887.7  306.92  4969.8  303.15  4976.5  301.92
  4981.6  298.13  4996.2  292.21  4996.7  291.71  5004.1  292.21  5020.4  303.65
  5030.5   304.2  5112.4  305.56  5334.1  302.54  5388.1  304.73    5437  305.53
  5562.4  312.62  5718.7  320.59  5789.6  326.54  5840.2  329.04    5895  329.18
  6154.7   335.6  6301.8  339.43  6581.7  338.65  6783.9  343.46  6924.1  341.34
#Mann= 9 ,-1 , 0
  3739.3     .07       0  4287.2     .12       0  4887.7      .1       0
  4996.2     .05       0  5004.1      .1       0  5388.1     .05       0
  5562.4     .07       0    5895     .12       0  6154.7     .07       0
Bank Sta=4996.2,5004.1
XS Rating Curve= 0 ,0
Exp/Cntr=0.3,0.1

Type RM Length L Ch R = 1 ,26502   ,490,490,490
BEGIN DESCRIPTION:
A18937
END DESCRIPTION:
XS GIS Cut Line= 3
      2517088.19     13722000.62      2517452.78     13723875.64
      2518025.69     13724934.66
#Sta/Elev= 30
  3854.6  350.05  3901.1  347.99  4297.1  334.78  4358.2  331.06  4390.9  332.32
  4672.7  317.49  4752.6  312.18  4775.9  312.55  4979.7  302.44  4989.9  301.48
    5000  291.98  5006.3  289.35  5006.8  288.85  5014.2  289.35    5016  293.91
  5021.1  293.91  5030.6  301.59    5051  302.51  5331.1  299.09  5366.8  301.55
  5418.8  299.51  5554.5  304.03  5743.7  311.07  5992.5   323.7  6326.6  334.94
  6408.4  332.75  6592.3  333.56  6623.1   334.4  6703.3   333.8  6968.8  338.08
#Mann= 10 ,-1 , 0
  3854.6     .07       0  3901.1     .12       0  4672.7      .1       0
  5006.3     .05       0  5014.2      .1       0  5418.8     .07       0
  5554.5     .05       0  5992.5     .07       0  6592.3     .12       0
  6623.1     .07       0
Bank Sta=5006.3,5014.2
XS Rating Curve= 0 ,0
Exp/Cntr=0.3,0.1

Type RM Length L Ch R = 1 ,26012   ,816,816,816
BEGIN DESCRIPTION:
A18936
END DESCRIPTION:
XS GIS Cut Line= 3
      2516654.17     13721983.27      2516897.22     13723406.89
      2517765.12     13724830.24
#Sta/Elev= 30
  3842.2  333.95  4107.7  327.54  4249.7  318.73  4432.3  318.89  4452.6  326.24
  4462.8  325.99  4493.2   315.9  4513.4  313.53  4624.9  310.68  4712.4   309.4
  4817.8  307.31  4848.3  304.17  4868.6  306.59  4959.9  301.88  5006.7  287.84
  5007.2  287.34  5014.7  287.84  5051.2  300.85  5065.8   301.4  5354.9   298.1
  5377.9  296.01    5413  298.31    5579   298.4    5713  300.02  6055.7   311.7
  6214.5  319.44  6388.8  324.22  6599.9  326.43  6789.6  324.29  6953.5  326.59
#Mann= 7 ,-1 , 0
  3842.2     .07       0  4513.4     .12       0  4624.9     .07       0
  4712.4      .1       0  5006.7     .05       0  5014.7      .1       0
    5579     .07       0
Bank Sta=5006.7,5014.7
XS Rating Curve= 0 ,0
Exp/Cntr=0.3,0.1

Type RM Length L Ch R = 1 ,25196   ,665,665,665
BEGIN DESCRIPTION:
A18935
END DESCRIPTION:
XS GIS Cut Line= 3
      2516133.34     13722139.56      2516654.17     13723962.44
      2517608.74     13724830.24
#Sta/Elev= 30
  3397.8  338.04  3589.4  331.64  3596.5  331.45  3991.6  318.41  4187.6  313.06
  4433.1  301.98  4453.9  304.19  4557.9  299.36  4686.5  298.67  4915.6  296.71
  4963.5  292.46  4988.4  292.66  5000.9  283.42  5001.4  282.92  5009.2  283.42
  5015.5  285.05  5022.2  294.29  5036.3  295.92  5100.2   295.3  5119.5  291.82
    5134  295.25  5397.5  297.02  5791.7   309.5  6053.2  310.43    6181  313.91
    6287  311.97    6358  315.94  6435.7  315.07  6506.7  318.59  6583.7  319.07
#Mann= 8 ,-1 , 0
  3397.8     .05       0  3589.4     .07       0  3596.5     .05       0
  3991.6     .07       0  4686.5      .1       0  5000.9     .05       0
  5009.2      .1       0  5397.5     .07       0
Bank Sta=5000.9,5009.2
XS Rating Curve= 0 ,0
Exp/Cntr=0.3,0.1

Type RM Length L Ch R = 1 ,24531   ,388,388,388
BEGIN DESCRIPTION:
A18934
END DESCRIPTION:
XS GIS Cut Line= 3
      2515959.72     13722313.13      2516289.58     13724118.69
       2517574.3     13726306.19
#Sta/Elev= 30
  2984.3   332.2  3218.5  326.18  3523.8  318.19  3962.1  308.48  4258.2  296.76
  4959.6     292  4996.8  287.22    5014  281.33  5014.5  280.83  5022.4  281.33
  5033.9  293.12  5074.9  292.84  5259.1  296.23  5364.8  297.29  5559.3  296.25
  5675.4   296.7  5791.8   298.6  5801.2  297.78  5807.4  293.49  5813.2   298.4
  5823.1  296.32  5828.9  298.72  5844.6  292.16  5859.2  294.45  5866.1  298.96
  5871.9   295.3  5917.2  299.28  6292.4  298.75  6877.7  317.54  7356.6  331.29
#Mann= 13 ,-1 , 0
  2984.3     .07       0  3218.5     .05       0  3523.8     .07       0
  4258.2      .1       0    5014     .05       0  5022.4      .1       0
  5074.9     .07       0  5259.1     .12       0  5364.8     .07       0
  5559.3     .12       0  5675.4      .1       0  6292.4     .07       0
  6877.7     .05       0
#XS Ineff= 2 , 0
       0    4730     296    5340       0     305
Permanent Ineff=
       F       F
Bank Sta=5014,5022.4
XS Rating Curve= 0 ,0
Exp/Cntr=0.3,0.1

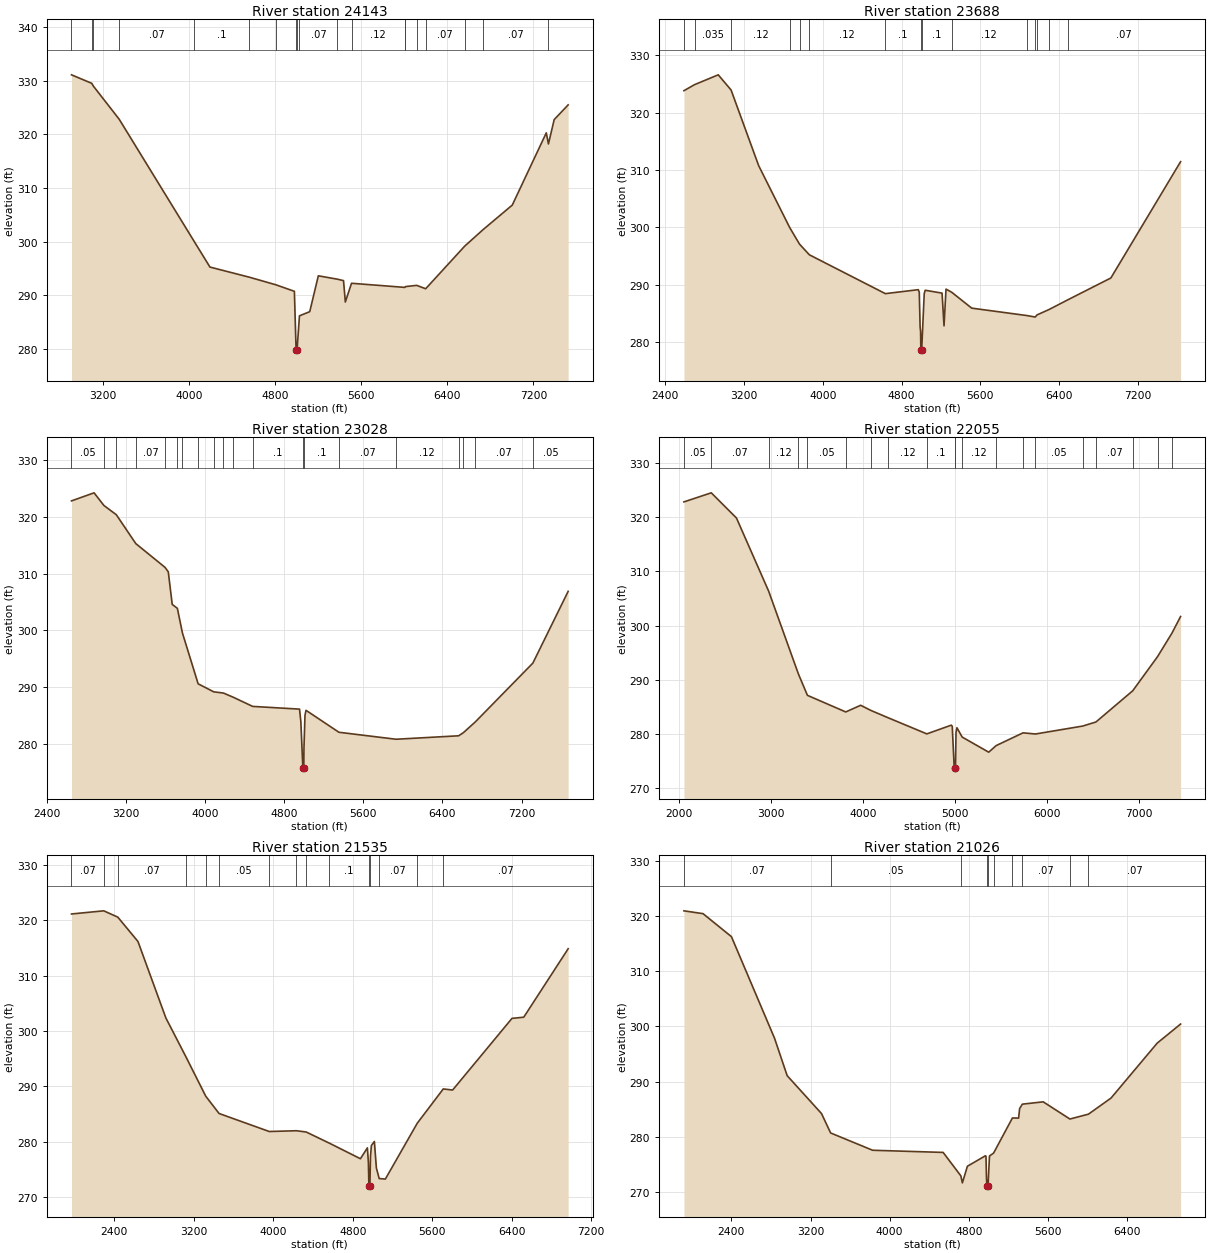
Type RM Length L Ch R = 1 ,24143   ,455,455,455
BEGIN DESCRIPTION:
A18933
END DESCRIPTION:
XS GIS Cut Line= 4
       2515838.2     13722365.24      2516046.53     13724222.86
      2516150.69     13725038.83      2516723.62     13726879.15
#Sta/Elev= 30
  2904.1  331.09  3092.2  329.51  3107.1     329  3347.8  322.81  4045.5  300.03
  4191.9  295.26  4556.6  293.38  4807.6  291.94  4977.2  290.74  4993.1  279.72
  4993.6  279.22  5001.5  279.72  5024.4  286.17    5120  286.95  5199.8  293.63
  5377.3     293  5434.2  292.73    5451  288.75  5508.6  292.24    6005  291.47
  6010.5  291.62  6114.5  291.85  6198.3  291.22  6561.7  299.17  6733.5  302.26
  7003.6  306.81  7320.1  320.28    7340  318.21  7393.4  322.74  7523.4  325.49
#Mann= 19 ,-1 , 0
  2904.1     .05       0  3092.2     .07       0  3107.1     .05       0
  3347.8     .07       0  4045.5      .1       0  4556.6     .12       0
  4807.6      .1       0  4993.1     .05       0  5001.5      .1       0
  5024.4     .07       0  5377.3      .1       0  5508.6     .12       0
    6005      .1       0  6010.5     .07       0  6114.5     .12       0
  6198.3     .07       0  6561.7     .05       0  6733.5     .07       0
    7340     .12       0
Bank Sta=4993.1,5001.5
XS Rating Curve= 0 ,0
Exp/Cntr=0.3,0.1

Type RM Length L Ch R = 1 ,23688   ,660,660,660
BEGIN DESCRIPTION:
A18932
END DESCRIPTION:
XS GIS Cut Line= 3
      2515456.25     13722278.39      2515768.75     13725108.28
      2516359.04     13727226.37
#Sta/Elev= 30
  2589.2  323.83  2697.7  324.89  2937.9   326.6  3068.4  323.95  3348.8  310.74
  3664.6  299.93    3764  297.05  3863.4   295.2  4635.6  288.42  4970.2  289.11
  4980.3  288.66  4988.7  282.64  4993.8  281.78  4996.2  278.54  4996.7  278.04
  5004.6  278.54  5030.6  288.42  5040.6  289.01  5211.7  288.51  5231.8   282.8
  5251.9  289.21  5309.2  288.67  5513.1  285.89  6071.9   284.6  6158.1  284.34
  6176.2   284.7  6302.4  285.68  6489.2  287.34  6926.8  291.15  7635.1  311.44
#Mann= 15 ,-1 , 0
  2589.2     .05       0  2697.7    .035       0  3068.4     .12       0
  3664.6     .07       0    3764    .035       0  3863.4     .12       0
  4635.6      .1       0  4996.2     .05       0  5004.6      .1       0
  5309.2     .12       0  6071.9     .07       0  6158.1     .12       0
  6176.2     .07       0  6302.4     .12       0  6489.2     .07       0
Bank Sta=4996.2,5004.6
XS Rating Curve= 0 ,0
Exp/Cntr=0.3,0.1

Type RM Length L Ch R = 1 ,23028   ,973,973,973
BEGIN DESCRIPTION:
A18931
END DESCRIPTION:
XS GIS Cut Line= 4
      2515091.67     13722486.75      2515091.67     13724552.72
      2515317.36     13725316.61      2516254.62     13727260.55
#Sta/Elev= 30
  2649.8  322.84  2878.1  324.26  2977.5  322.03  3102.9   320.4  3299.8  315.31
  3595.2  311.12  3628.1  310.33  3668.1  304.59  3719.9   303.9  3771.6  299.53
  3930.1  290.59  4087.5  289.18    4186  288.96  4284.4  288.23  4481.3  286.61
  4954.9  286.13  4968.4  283.89  4988.7   275.7  4989.2   275.2  4998.1   275.7
  4999.7  279.27  5010.1  285.04  5020.5  285.92  5353.3  282.05  5930.6  280.82
  6563.7  281.43    6612  281.99  6731.5  283.87  7313.6  294.24  7670.4  306.89
#Mann= 20 ,-1 , 0
  2649.8     .05       0  2977.5     .05       0  3102.9     .12       0
  3299.8     .07       0  3595.2     .12       0  3719.9     .07       0
  3771.6     .12       0  3930.1     .07       0  4087.5     .05       0
    4186    .035       0  4284.4     .05       0  4481.3      .1       0
  4988.7     .05       0  4998.1      .1       0  5353.3     .07       0
  5930.6     .12       0  6563.7     .07       0    6612     .12       0
  6731.5     .07       0  7313.6     .05       0
Bank Sta=4988.7,4998.1
XS Rating Curve= 0 ,0
Exp/Cntr=0.3,0.1

Type RM Length L Ch R = 1 ,22055   ,520,520,520
BEGIN DESCRIPTION:
A18930
END DESCRIPTION:
XS GIS Cut Line= 4
      2514848.61      13722573.6      2514761.81     13725125.64
      2514952.78     13726149.94      2516150.33      13727503.7
#Sta/Elev= 30
  2051.3  322.77  2348.7  324.44    2623   319.8  2973.3  306.32  3296.4  291.09
  3394.8  287.14  3811.8  284.08  3973.8  285.31  4083.7  284.37  4275.7  282.99
  4693.8  280.04  4960.2  281.65  4970.4  281.43  4990.7  274.13  4996.2  273.68
  4996.7  273.18  5005.6  273.68  5011.1  280.31  5021.2  281.17  5078.5  279.45
  5367.1  276.67  5447.6  277.88  5740.3  280.23  5875.9  280.02  6389.4  281.48
  6533.4  282.23  6933.7  287.98  7204.5  294.29  7360.8  298.61  7454.2  301.66
#Mann= 20 ,-1 , 0
  2051.3     .05       0  2348.7     .07       0  2973.3     .12       0
  3296.4     .07       0  3394.8     .05       0  3811.8    .035       0
  4083.7     .12       0  4275.7     .12       0  4693.8      .1       0
  4996.2     .05       0  5005.6      .1       0  5078.5     .12       0
  5447.6     .05       0  5740.3     .07       0  5875.9     .05       0
  6389.4     .07       0  6533.4     .07       0  6933.7     .05       0
  7204.5     .07       0  7360.8     .05       0
Bank Sta=4996.2,5005.6
XS Rating Curve= 0 ,0
Exp/Cntr=0.3,0.1

Type RM Length L Ch R = 1 ,21535   ,509,509,509
BEGIN DESCRIPTION:
A18929
END DESCRIPTION:
XS GIS Cut Line= 3
        2514675.     13722538.79      2514379.86     13725872.17
      2514640.13     13727503.21
#Sta/Elev= 30
  1969.8  321.15  2294.4  321.72  2435.8  320.58  2638.6  316.18  2919.7  302.34
  3124.5  295.21  3320.8   288.2  3454.9  285.07  3959.8  281.81    4233  281.95
  4331.6  281.72  4562.8  279.72  4877.3  276.89  4947.6  278.85  4957.7  276.18
  4962.7  271.89  4963.2  271.39  4972.7  271.89  4978.6  277.33  4987.8  279.28
  5017.9  280.01    5038  275.21  5066.5   273.3  5128.3  273.21  5449.1   283.3
  5711.2  289.51  5805.2  289.31  6402.6  302.27    6521  302.48  6967.9  314.86
#Mann= 15 ,-1 , 0
  1969.8     .07       0  2294.4     .12       0  2435.8     .07       0
  3124.5     .12       0  3320.8     .07       0  3454.9     .05       0
  3959.8    .035       0    4233     .05       0  4331.6     .12       0
  4562.8      .1       0  4962.7     .05       0  4972.7      .1       0
  5066.5     .07       0  5449.1     .05       0  5711.2     .07       0
Bank Sta=4962.7,4972.7
XS Rating Curve= 0 ,0
Exp/Cntr=0.3,0.1

Type RM Length L Ch R = 1 ,21026   ,680,680,680
BEGIN DESCRIPTION:
A18928
END DESCRIPTION:
XS GIS Cut Line= 3
       2514591.1     13722638.02      2513911.11     13725264.53
      2514310.21     13727537.65
#Sta/Elev= 30
  1920.1   320.9  2113.2  320.39  2400.3  316.23  2836.3  297.85  2963.7  291.09
  3311.5  284.22  3403.2  280.72    3828  277.59  4540.7   277.2  4719.8  272.96
  4735.2  271.69    4786   274.7  4968.7   276.6  4973.8  276.49  4978.9  272.52
  4983.9  271.06  4984.4  270.56  4994.2  271.06  5009.3  276.55  5050.7  277.08
  5241.1  283.43  5303.8  283.41  5313.9  285.13  5341.5  285.93  5552.3  286.35
  5822.5  283.24  6009.8  284.12  6237.9  287.03  6704.2  296.96  6941.1  300.42
#Mann= 10 ,-1 , 0
  1920.1     .07       0  3403.2     .05       0  4719.8      .1       0
  4983.9     .05       0  4994.2      .1       0  5050.7     .07       0
  5241.1    .035       0  5341.5     .07       0  5822.5     .12       0
  6009.8     .07       0
Bank Sta=4983.9,4994.2
XS Rating Curve= 0 ,0
Exp/Cntr=0.3,0.1

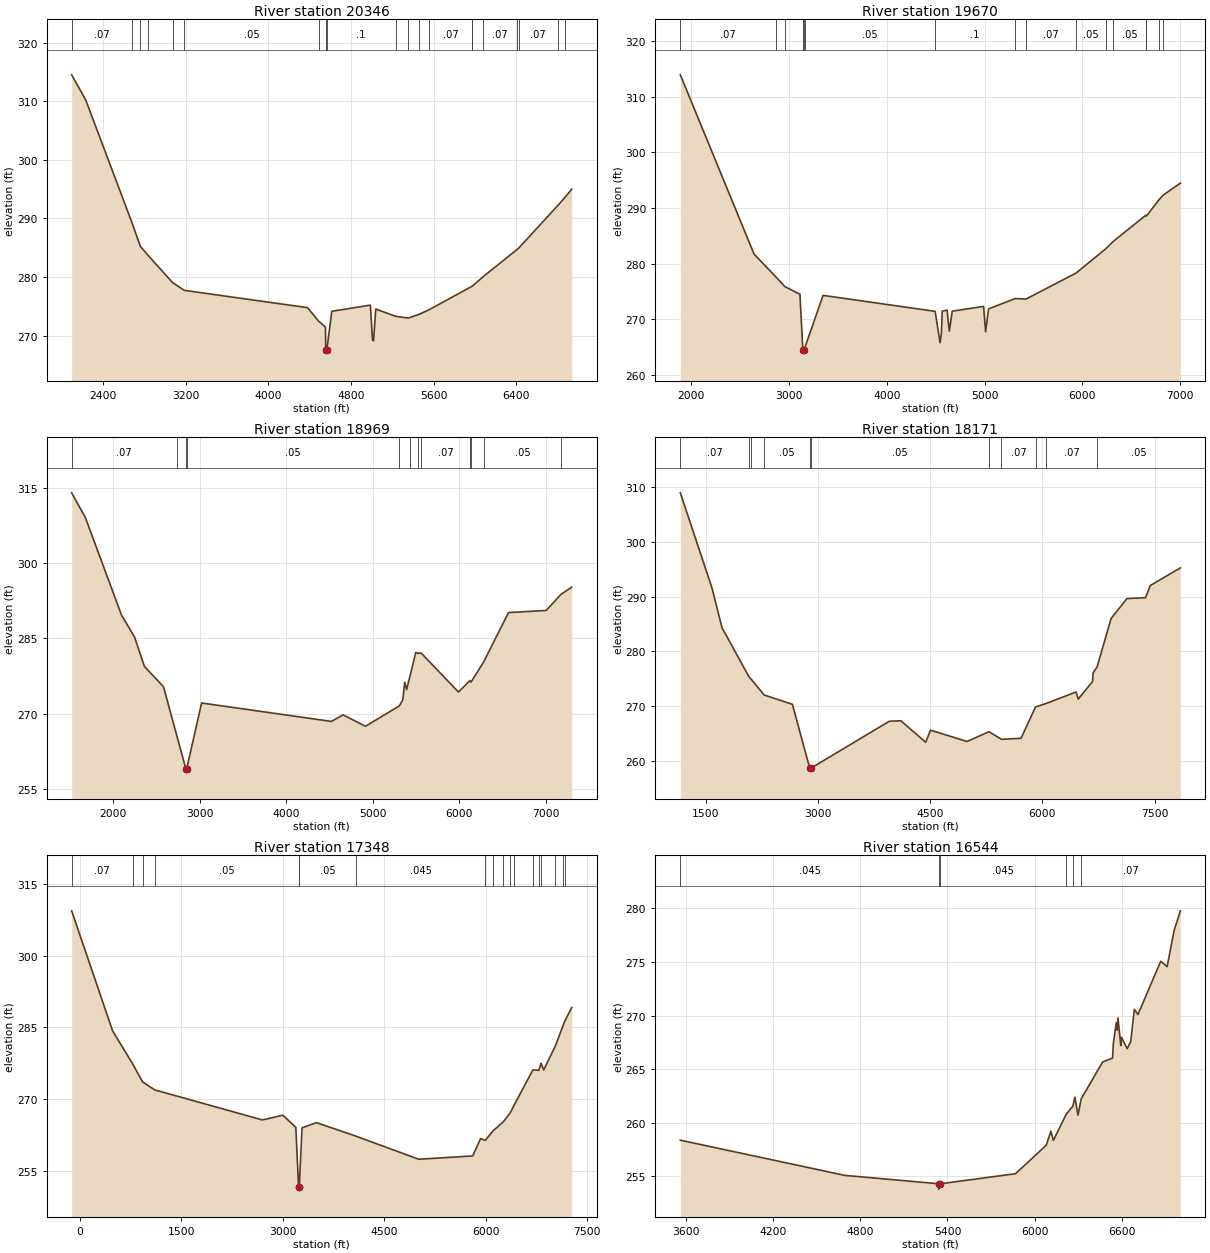
Type RM Length L Ch R = 1 ,20346   ,676,676,676
BEGIN DESCRIPTION:
A18927
END DESCRIPTION:
XS GIS Cut Line= 4
      2514417.35     13723065.73      2513445.28     13725751.74
      2513511.81     13726115.22       2513911.1     13727677.69
#Sta/Elev= 30
  2098.6  314.51  2234.2  310.24  2681.9   289.3  2763.6  285.23  2841.2  283.64
  3075.8  279.05  3188.6  277.74  4380.9  274.79  4486.9  272.51  4554.2  271.46
  4556.8  267.53  4557.3  267.03  4567.1  267.53  4615.4  274.17  4988.9  275.22
  5009.2  269.34  5019.4  269.13  5040.8  274.55  5232.1  273.32  5354.9  273.01
  5457.3  273.63  5559.7  274.46  5969.1   278.4  5970.9  278.39    6079  280.06
  6409.1  284.73  6425.3  284.97  6800.6  292.18  6869.9  293.57  6937.3     295
#Mann= 20 ,-1 , 0
  2098.6     .07       0  2681.9     .12       0  2763.6     .07       0
  2841.2     .12       0  3075.8     .07       0  3188.6     .05       0
  4486.9      .1       0  4556.8     .05       0  4567.1      .1       0
  5232.1     .12       0  5354.9    .035       0  5457.3     .12       0
  5559.7     .07       0  5969.1     .05       0  5970.9     .12       0
    6079     .07       0  6409.1     .05       0  6425.3     .07       0
  6800.6     .05       0  6869.9     .07       0
Bank Sta=4556.8,4567.1
XS Rating Curve= 0 ,0
Exp/Cntr=0.3,0.1

Type RM Length L Ch R = 1 ,19670   ,701,701,701
BEGIN DESCRIPTION:
A18926
END DESCRIPTION:
XS GIS Cut Line= 4
      2514390.61     13723012.29       2512884.5     13725671.35
      2512956.25     13726028.42      2513720.06     13727538.67
#Sta/Elev= 30
  1889.7  313.94  2643.6  281.72  2870.6  277.55  2959.2  275.87  3112.6  274.51
  3142.4  264.42  3142.9  263.92    3153  264.42  3160.7  264.81  3349.2   274.3
    4495  271.43  4545.4  265.78  4559.1  267.53  4567.1  271.45  4616.6  271.66
  4639.6  267.85  4669.5  271.46  4990.2  272.32  5010.6  267.76  5041.2  271.87
    5312  273.72  5423.9  273.64  5936.5  278.32  6238.2  282.66  6313.1  283.96
  6647.3  288.69  6655.1  288.56  6786.9  291.56  6829.2  292.36  7002.3  294.48
#Mann= 16 ,-1 , 0
  1889.7     .07       0  2870.6     .12       0  2959.2     .07       0
  3142.4     .05       0    3153     .07       0  3160.7     .05       0
    4495      .1       0    5312    .035       0  5423.9     .07       0
  5936.5     .05       0  6238.2     .07       0  6313.1     .05       0
  6647.3     .07       0  6655.1     .05       0  6786.9     .07       0
  6829.2     .05       0
Bank Sta=3142.4,3153
XS Rating Curve= 0 ,0
Exp/Cntr=0.3,0.1

Type RM Length L Ch R = 1 ,18969   ,798,798,798
BEGIN DESCRIPTION:
A18925
END DESCRIPTION:
XS GIS Cut Line= 4
      2514390.57     13722918.78      2512247.21     13725553.25
      2512331.25      13725854.8      2513580.61     13727503.27
#Sta/Elev= 30
  1522.8  314.08  1680.6  309.16  2099.3  289.63  2249.4  285.26  2362.9  279.41
  2583.4  275.36  2734.9  265.74  2841.3  258.99  2841.8  258.49  2851.9  258.99
  3024.4   272.1  4523.3  268.42  4659.1  269.73  4916.9  267.45  5308.2  271.51
  5348.7  272.73  5370.4  276.24  5392.4  274.77  5434.5   277.7  5498.5  282.19
  5526.1  282.02  5560.7  282.08  5991.5  274.29  6124.4  276.58  6137.1  276.27
  6284.6  280.36  6569.8  290.16  7004.6  290.58  7178.3  293.83  7300.5  295.24
#Mann= 12 ,-1 , 0
  1522.8     .07       0  2734.9     .05       0  2841.3     .05       0
  2851.9     .05       0  5308.2    .035       0  5434.5     .07       0
  5526.1     .12       0  5560.7     .07       0  6124.4     .05       0
  6137.1     .07       0  6284.6     .05       0  7178.3     .07       0
Bank Sta=2841.3,2851.9
XS Rating Curve= 0 ,0
Exp/Cntr=0.3,0.1

Type RM Length L Ch R = 1 ,18171   ,823,823,823
BEGIN DESCRIPTION:
A18924
END DESCRIPTION:
XS GIS Cut Line= 4
      2514283.64     13722945.51      2511578.72     13725594.48
      2512140.28     13726028.42      2513598.43     13727660.16
#Sta/Elev= 30
  1159.3  308.94  1582.2   291.6  1716.7  284.34  2077.3  275.38  2106.6  274.94
  2279.3  272.07  2657.1  270.37  2889.9  258.68  2890.4  258.18  2900.5  258.68
  3951.2  267.27  4106.8  267.37  4439.1  263.45  4502.7  265.65  4992.2  263.59
  5284.8  265.37  5451.9  263.98  5712.7  264.16  5907.2  269.89  6050.4  270.53
  6449.1  272.61  6477.6  271.32    6669  274.52  6675.7  276.08  6730.5  277.21
  6916.5  286.01  7128.8  289.65  7377.1  289.81  7440.6  292.03  7843.3  295.25
#Mann= 11 ,-1 , 0
  1159.3     .07       0  2077.3     .12       0  2106.6     .07       0
  2279.3     .05       0  2889.9     .05       0  2900.5     .05       0
  5284.8    .035       0  5451.9     .07       0  5907.2    .035       0
  6050.4     .07       0  6730.5     .05       0
Bank Sta=2889.9,2900.5
XS Rating Curve= 0 ,0
Exp/Cntr=0.3,0.1

Type RM Length L Ch R = 1 ,17348   ,804,804,804
BEGIN DESCRIPTION:
A18923
END DESCRIPTION:
XS GIS Cut Line= 4
      2514283.66     13722838.55      2511029.17     13725993.69
      2512036.11     13726774.94      2513338.23     13727677.75
#Sta/Elev= 30
  -122.5  309.39   482.2  284.26   778.8  277.35   925.5  273.56  1106.2  271.89
  2695.7   265.6  2999.8  266.59  3190.7  264.04  3231.3  251.61  3231.8  251.11
  3241.9  251.61  3282.7  263.94  3494.9  265.04  4078.3  262.21  5007.1  257.37
  5805.2  258.06  5921.3  261.69    5991  261.33  6108.5  263.35  6256.3  265.19
    6363  267.13  6420.1  268.78  6695.8   276.1    6784  275.99  6815.8  277.48
  6854.9  276.06    7027   281.1  7139.7  285.32  7163.8  286.24  7269.3  289.15
#Mann= 18 ,-1 , 0
  -122.5     .07       0   778.8     .12       0   925.5     .07       0
  1106.2     .05       0  3231.3    .045       0  3241.9     .05       0
  4078.3    .045       0    5991     .07       0  6108.5    .035       0
  6256.3     .07       0    6363    .035       0  6420.1     .07       0
  6695.8     .05       0    6784     .07       0  6815.8     .05       0
    7027     .07       0  7139.7     .05       0  7163.8     .07       0
Bank Sta=3231.3,3241.9
XS Rating Curve= 0 ,0
Exp/Cntr=0.3,0.1

Type RM Length L Ch R = 1 ,16544   ,639,639,639
BEGIN DESCRIPTION:
A18922
END DESCRIPTION:
XS GIS Cut Line= 4
      2510464.65     13725915.21      2510872.92     13726722.86
      2511515.28     13727278.42      2513111.24     13727833.53
#Sta/Elev= 30
  3560.3  258.36  4694.8  255.07    5340  254.29  5340.5  253.79  5350.6  254.29
  5868.7  255.23  6081.1   257.9  6112.2   259.2  6129.5  258.34  6217.9  260.79
  6263.6  261.53  6277.7  262.37  6298.9   260.7  6321.1  262.22  6468.3  265.66
    6537  266.03  6542.4  267.41  6562.8  269.33  6568.1  268.64  6574.2  269.78
  6593.9  267.19  6597.8  267.98  6637.7  266.91  6661.4  267.53  6687.3  270.59
  6711.8  270.09  6868.6  275.07    6913  274.57  6961.9     278  7004.3  279.78
#Mann= 6 ,-1 , 0
  3560.3    .045       0    5340    .045       0  5350.6    .045       0
  6217.9     .07       0  6263.6     .12       0  6321.1     .07       0
Bank Sta=5340,5350.6
XS Rating Curve= 0 ,0
Exp/Cntr=0.3,0.1