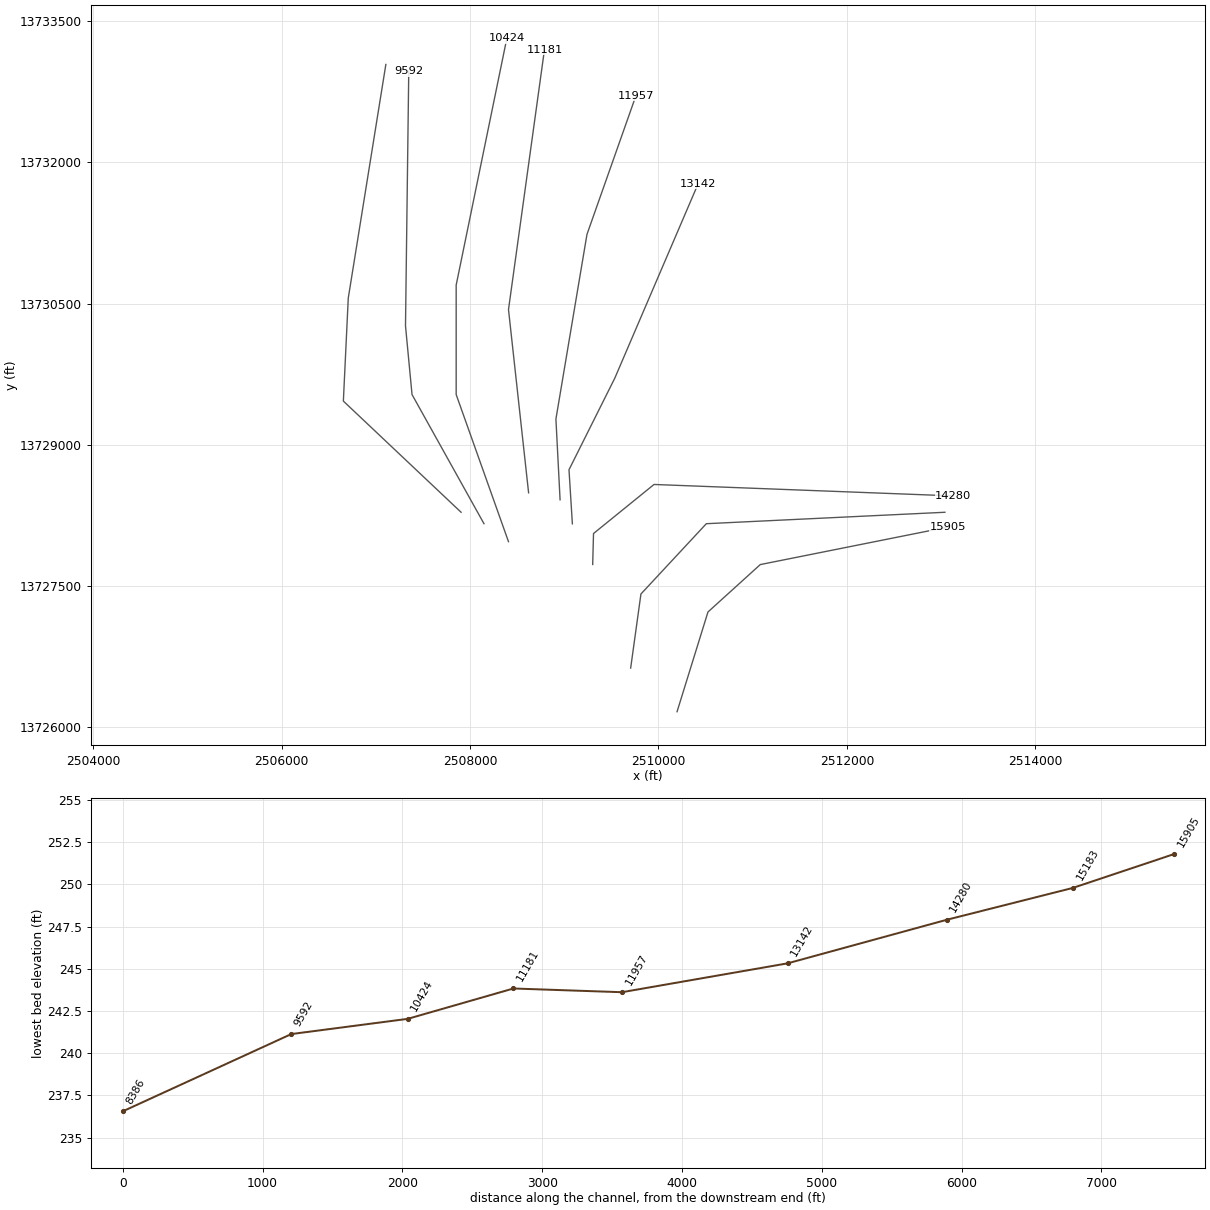
HEC-RAS study GELHORN CREEK.prj: GELHORN CREEK Base Level Engineering

--- GELHORN CREEK.g01 (geometry) --- (continued)

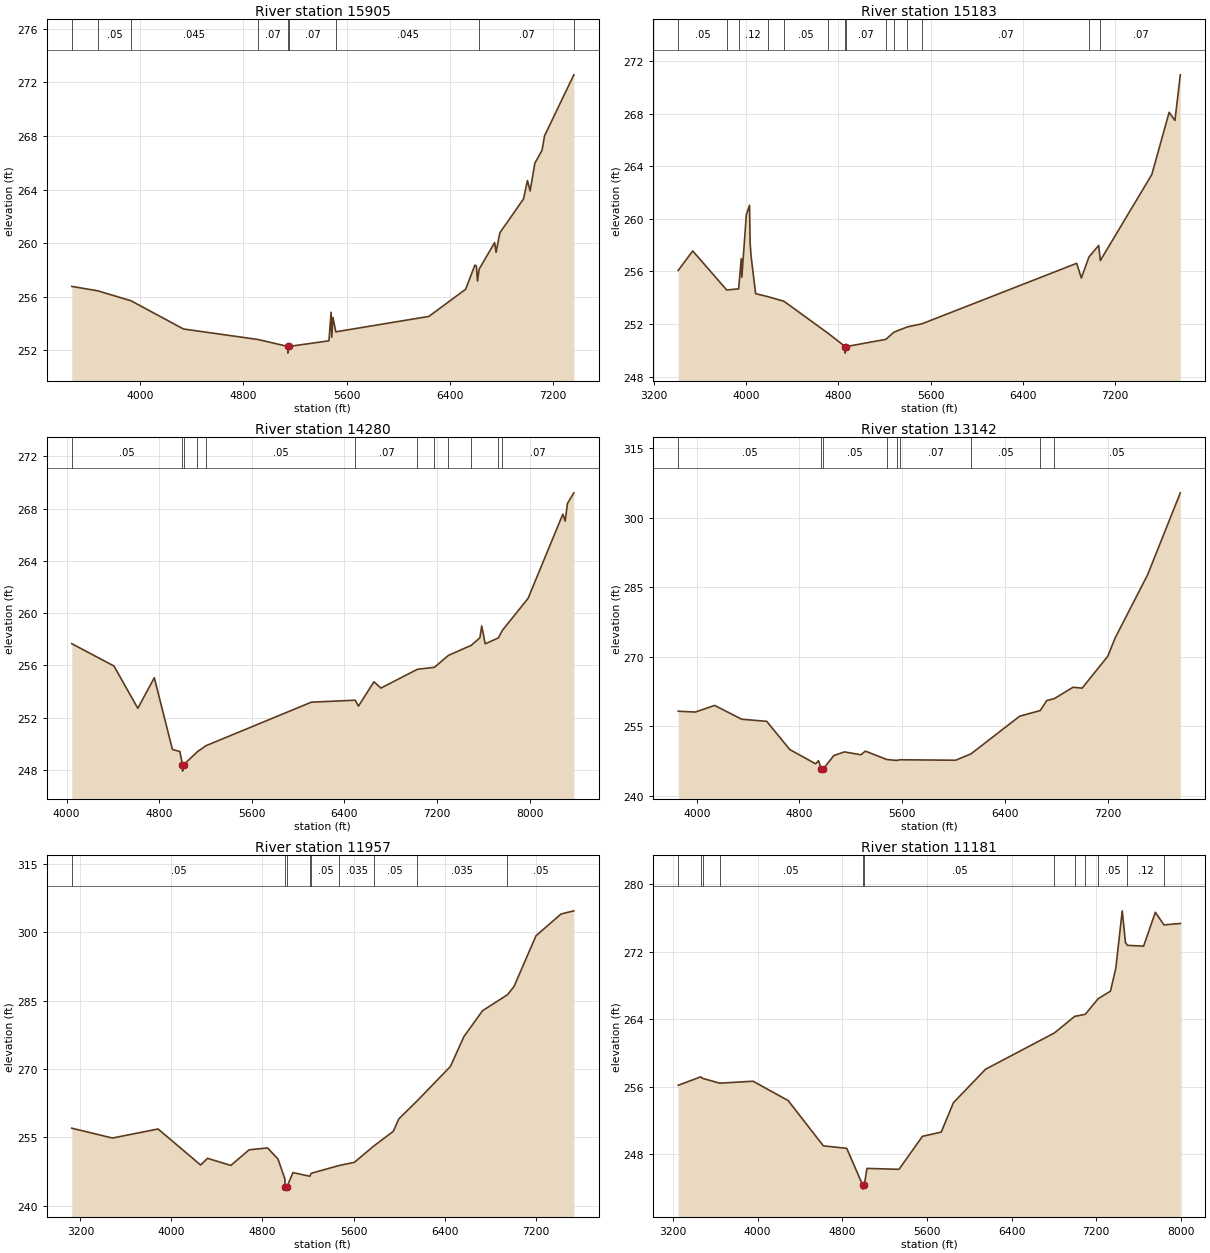
Type RM Length L Ch R = 1 ,15905   ,722,722,722
BEGIN DESCRIPTION:
A18921
END DESCRIPTION:
XS GIS Cut Line= 4
      2510197.29     13726166.95      2510525.69     13727226.33
      2511081.25      13727729.8      2513077.74      13728129.1
#Sta/Elev= 30
    3468  256.77  3669.4  256.44  3927.3   255.7  4334.9  253.59  4911.7  252.81
  5143.7  252.29  5144.2  251.79  5154.4  252.29  5463.3  252.71  5479.7  254.84
  5484.8  252.98  5493.9  254.46  5516.4  253.38  6238.3  254.53  6523.9  256.56
  6595.2  258.36  6606.6   258.3  6615.6  257.17  6627.8  258.05  6748.2  260.04
  6759.6  259.31    6789  260.77  6972.6   263.3  7003.2  264.67  7023.6  263.89
  7060.4  265.96  7116.5  266.94  7135.7  268.01  7362.8  272.56  7362.9  272.56
#Mann= 9 ,-1 , 0
    3468    .045       0  3669.4     .05       0  3927.3    .045       0
  4911.7     .07       0  5143.7     .05       0  5154.4     .07       0
  5516.4    .045       0  6627.8     .07       0  7362.8     .05       0
Bank Sta=5143.7,5154.4
XS Rating Curve= 0 ,0
Exp/Cntr=0.3,0.1

Type RM Length L Ch R = 1 ,15183   ,903,903,903
BEGIN DESCRIPTION:
A18920
END DESCRIPTION:
XS GIS Cut Line= 4
      2509704.85     13726630.63      2509813.89      13727417.3
      2510508.33     13728163.83      2513041.54     13728285.29
#Sta/Elev= 30
  3413.8  256.08  3539.4  257.56  3833.9  254.59  3937.3  254.68  3959.7  256.98
  3964.8  255.56  4003.8  260.31  4031.5  261.03  4036.5  258.21  4044.1  257.23
  4084.5  254.31  4188.5  254.09  4330.5  253.73    4715  251.28  4859.6  250.29
  4860.1  249.79  4870.6  250.29  5213.2  250.84    5282  251.38  5397.5  251.78
  5528.7  252.03  6866.1  256.62  6906.2   255.5  6972.3   257.1  7056.3  257.98
  7070.8  256.83  7516.9  263.37    7667   268.1  7717.1  267.48  7763.7  270.95
#Mann= 14 ,-1 , 0
  3413.8     .05       0  3833.9     .07       0  3937.3     .12       0
  4188.5     .07       0  4330.5     .05       0    4715     .07       0
  4859.6     .05       0  4870.6     .07       0  5213.2     .05       0
    5282     .07       0  5397.5     .05       0  5528.7     .07       0
  6972.3     .12       0  7070.8     .07       0
Bank Sta=4859.6,4870.6
XS Rating Curve= 0 ,0
Exp/Cntr=0.3,0.1

Type RM Length L Ch R = 1 ,14280   ,1138,1138,1138
BEGIN DESCRIPTION:
A18919
END DESCRIPTION:
XS GIS Cut Line= 4
      2509301.61     13727730.73      2509310.42     13728059.67
      2509952.78      13728580.5      2513129.82     13728458.97
#Sta/Elev= 30
  4045.4  257.66  4409.6  255.95  4615.8  252.71  4758.1  255.05  4914.7  249.56
  4978.7   249.4  5001.4   248.4  5001.9   247.9  5013.4   248.4  5130.3  249.39
  5205.2  249.85  6114.3  253.18  6492.9  253.33  6521.1  252.88  6654.7  254.74
  6714.8  254.26  7030.6   255.7  7177.1  255.85  7297.2  256.76  7494.5  257.53
  7569.7  258.11  7585.4  259.02  7615.4  257.65  7729.3   258.1  7763.6  258.68
  7985.7  261.13  8285.9  267.58  8305.9  267.05  8325.9   268.4  8380.8  269.21
#Mann= 12 ,-1 , 0
  4045.4     .05       0  5001.4     .05       0  5013.4     .05       0
  5130.3     .07       0  5205.2     .05       0  6492.9     .07       0
  7030.6     .12       0  7177.1      .1       0  7297.2     .12       0
  7494.5     .07       0  7729.3     .12       0  7763.6     .07       0
Bank Sta=5001.4,5013.4
XS Rating Curve= 0 ,0
Exp/Cntr=0.3,0.1

Type RM Length L Ch R = 1 ,13142   ,1185,1185,1185
BEGIN DESCRIPTION:
A18918
END DESCRIPTION:
XS GIS Cut Line= 4
      2509085.91     13728162.23        2509050.     13728736.75
      2509536.11     13729708.97      2510420.77     13731773.17
#Sta/Elev= 30
  3856.1  258.24  3989.1  258.06  4139.4  259.49  4349.8  256.52  4545.4  256.05
  4724.2  249.98  4925.5   246.9  4947.9  247.57  4969.9  245.82  4970.4  245.32
  4985.4  245.82  5067.1  248.67  5149.1  249.47  5277.7  248.85    5313  249.63
  5480.2  247.82  5555.9  247.63  5583.4  247.77  6015.6  247.67  6134.9  249.04
  6514.3  257.17    6674  258.38  6724.6  260.55  6782.5  260.94  6929.5  263.41
  7000.2  263.22  7199.7  270.09  7257.7  274.07  7509.8  287.66  7764.5  305.34
#Mann= 9 ,-1 , 0
  3856.1     .05       0  4969.9     .05       0  4985.4     .05       0
  5480.2     .07       0  5555.9     .05       0  5583.4     .07       0
  6134.9     .05       0    6674    .035       0  6782.5     .05       0
Bank Sta=4969.9,4985.4
XS Rating Curve= 0 ,0
Exp/Cntr=0.3,0.1

Type RM Length L Ch R = 1 ,11957   ,776,776,776
BEGIN DESCRIPTION:
A18917
END DESCRIPTION:
XS GIS Cut Line= 4
       2508955.3     13728417.75      2508911.11     13729274.94
      2509240.97     13731236.75      2509761.38     13732711.24
#Sta/Elev= 30
  3124.3  256.98    3482  254.82  3882.6  256.81  4256.5   248.9  4317.3  250.37
    4522  248.81  4682.4  252.24  4844.6  252.65  4935.8  250.23  4996.4  245.89
  4999.1  244.11  4999.6  243.61  5014.7  244.11  5067.7  247.24  5215.4  246.44
  5228.6  247.09  5475.7  248.81  5607.2  249.49  5776.7  253.04  5949.9  256.31
  5997.9  259.03  6156.9  262.93  6451.2  270.53  6569.6  277.07  6733.6  282.77
  6952.6  286.27  7009.4  288.05  7203.2  299.21  7422.9  303.98  7535.6  304.68
#Mann= 9 ,-1 , 0
  3124.3     .05       0  4999.1     .05       0  5014.7     .05       0
  5215.4     .07       0  5228.6     .05       0  5475.7    .035       0
  5776.7     .05       0  6156.9    .035       0  6952.6     .05       0
Bank Sta=4999.1,5014.7
XS Rating Curve= 0 ,0
Exp/Cntr=0.3,0.1

Type RM Length L Ch R = 1 ,11181   ,757,757,757
BEGIN DESCRIPTION:
A18916
END DESCRIPTION:
XS GIS Cut Line= 3
      2508621.08      13728492.1      2508407.64     13730438.14
      2508789.58     13733198.53
#Sta/Elev= 30
  3249.3  256.16  3461.8  257.16  3482.3  256.97  3641.7  256.41  3956.4  256.64
  4288.4  254.34  4620.4  248.97  4841.7  248.67  4991.8  244.33  4992.3  243.83
  5007.8  244.33  5032.8  246.29  5335.1  246.18  5557.2   250.1  5734.4   250.6
  5849.9  254.09  6152.8  258.06  6803.9  262.37  6995.6  264.34  7095.4  264.58
  7216.7  266.43  7333.9  267.34  7384.4  270.07    7445  276.87  7475.3  273.11
  7494.5  272.77  7646.9  272.68  7757.9   276.7  7839.3   275.2  7993.7  275.37
#Mann= 12 ,-1 , 0
  3249.3     .07       0  3461.8     .05       0  3482.3     .07       0
  3641.7     .05       0  4991.8     .05       0  5007.8     .05       0
  6803.9     .07       0  6995.6     .05       0  7095.4    .045       0
  7216.7     .05       0  7494.5     .12       0  7839.3     .05       0
Bank Sta=4991.8,5007.8
XS Rating Curve= 0 ,0
Exp/Cntr=0.3,0.1

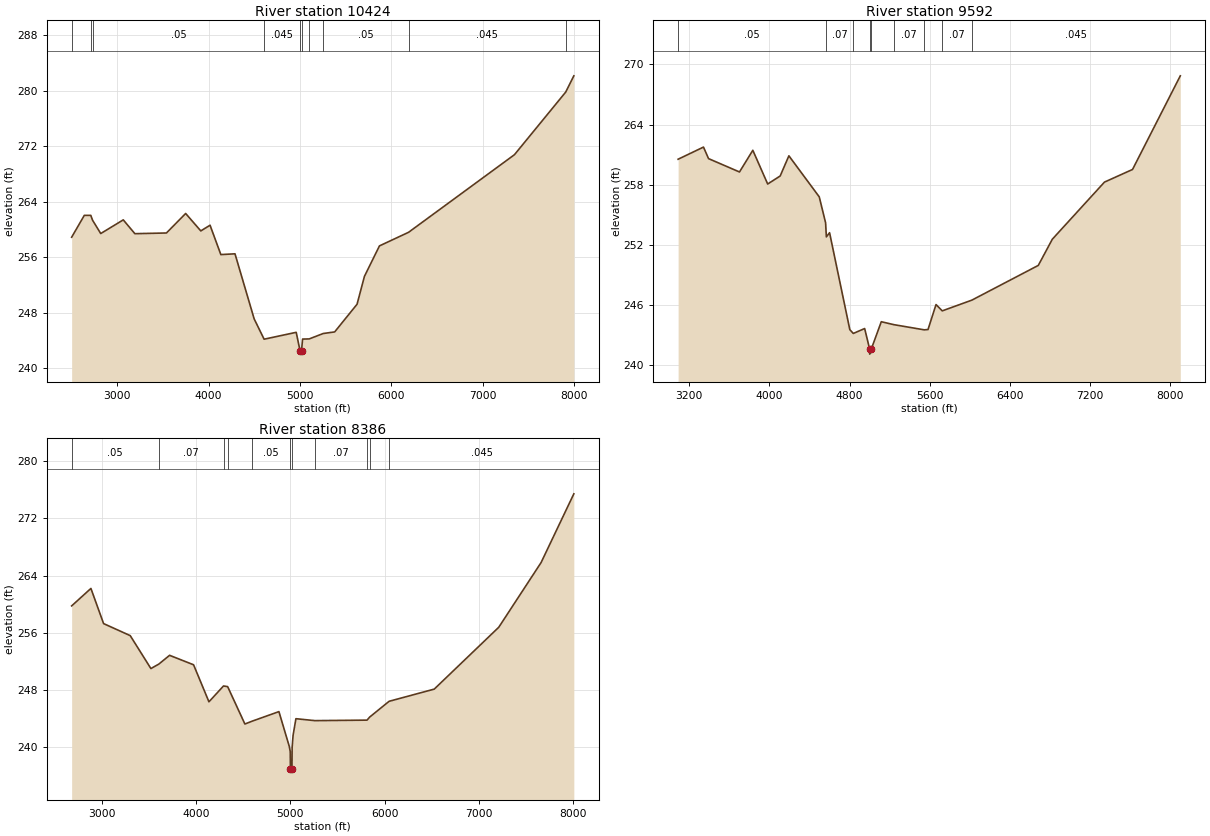
Type RM Length L Ch R = 1 ,10424   ,832,832,832
BEGIN DESCRIPTION:
A18915
END DESCRIPTION:
XS GIS Cut Line= 4
      2508407.64     13727972.85      2507852.08     13729535.36
      2507852.08     13730698.55      2508390.13     13733319.37
#Sta/Elev= 30
  2501.6  258.87  2640.2  262.02  2711.1  262.02  2730.6  261.32  2819.9   259.4
  3066.7  261.37  3193.7  259.38    3539  259.48  3749.6  262.29  3915.4  259.78
  4016.6   260.6  4134.7  256.37  4289.6  256.48  4499.6   247.1  4608.3  244.18
  4959.6  245.17  5001.5  242.53    5002  242.03  5017.7  242.53  5029.6   244.2
  5101.5  244.22  5255.3     245  5380.7  245.23  5625.8  249.22  5706.4  253.23
  5870.8  257.62  6189.7  259.58  7348.7  270.76  7909.7  279.78  7998.6  282.12
#Mann= 10 ,-1 , 0
  2501.6     .05       0  2711.1     .07       0  2730.6     .05       0
  4608.3    .045       0  5001.5    .045       0  5017.7    .045       0
  5101.5     .07       0  5255.3     .05       0  6189.7    .045       0
  7909.7     .05       0
Bank Sta=5001.5,5017.7
XS Rating Curve= 0 ,0
Exp/Cntr=0.3,0.1

Type RM Length L Ch R = 1 ,9592    ,1206,1206,1206
BEGIN DESCRIPTION:
A18914
END DESCRIPTION:
XS GIS Cut Line= 4
      2508147.21     13728163.86      2507383.33     13729535.36
      2507313.89     13730264.53      2507348.59     13732971.46
#Sta/Elev= 30
    3089  260.55  3342.1  261.76  3392.6  260.61  3701.3  259.28  3834.3  261.44
  3982.5  258.08  4107.1  258.88    4194  260.89  4496.9   256.8  4560.3  254.21
  4567.8  252.81  4599.8  253.23  4801.8  243.57  4836.6  243.19  4949.8  243.68
  4999.6  241.63  5000.1  241.13  5015.9  241.63  5115.8  244.36    5239  244.07
  5544.6  243.55  5581.8  243.58  5661.8  246.07  5723.8  245.44  6019.3  246.51
  6681.9  249.97  6821.9  252.58    7342  258.27    7622  259.53  8098.5  268.86
#Mann= 9 ,-1 , 0
    3089     .05       0  4560.3     .07       0  4836.6     .05       0
  4999.6     .05       0  5015.9     .05       0    5239     .07       0
  5544.6     .12       0  5723.8     .07       0  6019.3    .045       0
Bank Sta=4999.6,5015.9
XS Rating Curve= 0 ,0
Exp/Cntr=0.3,0.1

Type RM Length L Ch R = 1 ,8386    ,0,0,0
BEGIN DESCRIPTION:
A18913
END DESCRIPTION:
XS GIS Cut Line= 4
      2507904.14     13728285.38      2506654.17     13729465.92
      2506706.25     13730559.67      2507105.37     13733041.15
#Sta/Elev= 30
  2680.8  259.76  2885.2   262.2  3019.6  257.29  3302.3  255.61  3521.6  251.01
  3606.2  251.64  3719.8  252.86  3974.3  251.54  4137.3  246.37    4292  248.58
  4335.8  248.49  4518.6  243.27  4594.6  243.66  4879.8     245  4989.9  240.13
  4999.9  239.43  5001.7  237.05  5002.2  236.55  5018.1  237.05  5019.9  240.01
  5029.9  241.68    5060  244.01  5260.9  243.74  5814.5  243.81  5842.8  244.24
  6048.8  246.44  6527.4  248.14  7212.2  256.78  7661.4  265.82  8008.5  275.41
#Mann= 11 ,-1 , 0
  2680.8     .05       0  3606.2     .07       0    4292     .05       0
  4335.8     .07       0  4594.6     .05       0  5001.7     .05       0
  5018.1     .05       0  5260.9     .07       0  5814.5     .12       0
  5842.8     .07       0  6048.8    .045       0
Bank Sta=5001.7,5018.1
XS Rating Curve= 0 ,0
Exp/Cntr=0.3,0.1

Chan Stop Cuts=-1
Use User Specified Reach Order=0
Composite Channel Slope=5