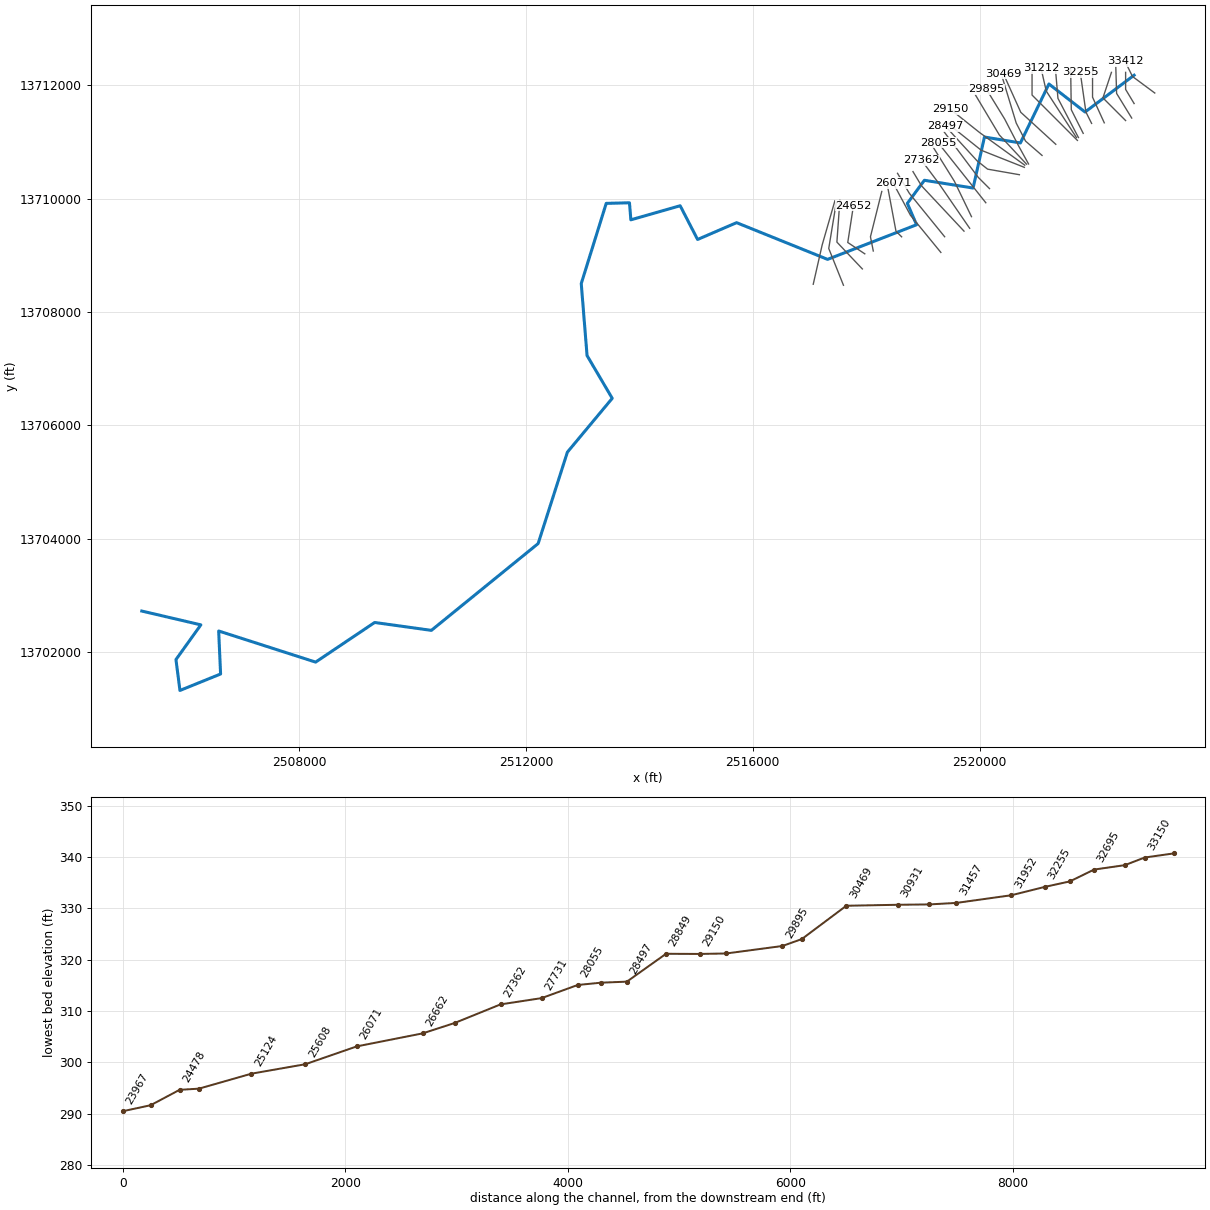
--- KOKERNOT BRANCH.prj (project) ---

Proj Title=KOKERNOT BRANCH Base Level Engineering
Current Plan=p01
Default Exp/Contr=0.3,0.1
English Units
Geom File=g01
Flow File=f01
Plan File=p01
Y Axis Title=Elevation
X Axis Title(PF)=Main Channel Distance
X Axis Title(XS)=Station
BEGIN DESCRIPTION:
KOKERNOT BRANCH
END DESCRIPTION:
DSS Export Rating Curves= 0
DSS Export Rating Curve Sorted= 0
DSS Export Volume Flow Curves= 0
DXF OffsetX= 0
DXF OffsetY= 0
DXF ScaleX= 1
DXF ScaleY= 10

--- KOKERNOT BRANCH.p01 (plan) ---

Plan Title=Multiple Run
Short Identifier=Multiple
Geom File=g01
Flow File=f01
Subcritical Flow
K Sum by GR= 0
Std Step Tol= 0.01
Critical Tol= 0.01
Num of Std Step Trials= 20
Max Error Tol= 0.3
Flow Tol Ratio= 0.001
Split Flow NTrial= 30
Split Flow Tol= 0.02
Split Flow Ratio= 0.02
Log Output Level= 0
Friction Slope Method= 1
Unsteady Friction Slope Method= 2
Unsteady Bridges Friction Slope Method= 1
Parabolic Critical Depth
Global Vel Dist=  1 , 1 , 1
Global Log Level= 0
CheckData=True
Encroach Param= -1, 0, 0, 0
BEGIN DESCRIPTION:
Multiple Run
END DESCRIPTION:

--- KOKERNOT BRANCH.f01 (steady flow) ---

Flow Title=Multiple
Number of Profiles=7
Profile Names=10-year,25-year,50-year,1pct_min,100-year,1pct_plu,500-year
River Rch & RM= KOKERNOT BRANCH,Reach-1,33412
    1019    1694    2324    1545    3084    6153    5371
River Rch & RM= KOKERNOT BRANCH,Reach-1,31457
    1267    2114    2908    1934    3859    7700    6732
River Rch & RM= KOKERNOT BRANCH,Reach-1,24218
    1367    2285    3146    2094    4178    8336    7296
River Rch & RM= KOKERNOT BRANCH,Reach-1,19871
    2213    3773    5260    3539    7061   14089   12607
River Rch & RM= KOKERNOT BRANCH,Reach-1,10182
    2288    3898    5433    3652    7287   14540   12990
Boundary for River Rch & Prof#=KOKERNOT BRANCH,Reach-1,1
Up Type=0
Dn Type=3
Dn Slope=0.005
Boundary for River Rch & Prof#=KOKERNOT BRANCH,Reach-1,2
Up Type=0
Dn Type=3
Dn Slope=0.005
Boundary for River Rch & Prof#=KOKERNOT BRANCH,Reach-1,3
Up Type=0
Dn Type=3
Dn Slope=0.005
Boundary for River Rch & Prof#=KOKERNOT BRANCH,Reach-1,4
Up Type=0
Dn Type=3
Dn Slope=0.005
Boundary for River Rch & Prof#=KOKERNOT BRANCH,Reach-1,5
Up Type=0
Dn Type=3
Dn Slope=0.005
Boundary for River Rch & Prof#=KOKERNOT BRANCH,Reach-1,6
Up Type=0
Dn Type=3
Dn Slope=0.005
Boundary for River Rch & Prof#=KOKERNOT BRANCH,Reach-1,7
Up Type=0
Dn Type=3
Dn Slope=0.005

--- KOKERNOT BRANCH.g01 (geometry) ---

Geom Title=Existing Conditions
Program Version=4.10

River Reach=KOKERNOT BRANCH ,Reach-1
Reach XY= 30
        2522725.       13712175.      2521859.78     13711525.49
      2521222.71      13712019.9      2520719.53      13710980.1
      2520085.63       13711085.      2519885.17     13710185.32
      2519026.39     13710321.98      2518725.48     13709914.51
      2518888.71     13709537.98      2517319.15     13708927.04
      2515714.38      13709574.4      2515026.43     13709278.07
      2514719.16     13709872.95      2513849.88     13709624.68
        2513825.       13709925.      2513415.17     13709914.53
       2512974.8     13708499.92      2513077.17     13707230.44
      2513521.18     13706476.58      2512730.45     13705527.47
      2512214.37       13703915.      2510331.67      13702384.3
      2509331.04     13702523.38       2508290.2     13701824.51
      2506580.61     13702373.27      2506614.18     13701614.68
      2505897.62     13701324.57      2505827.24     13701869.07
      2506266.05     13702481.67        2505225.       13702725.

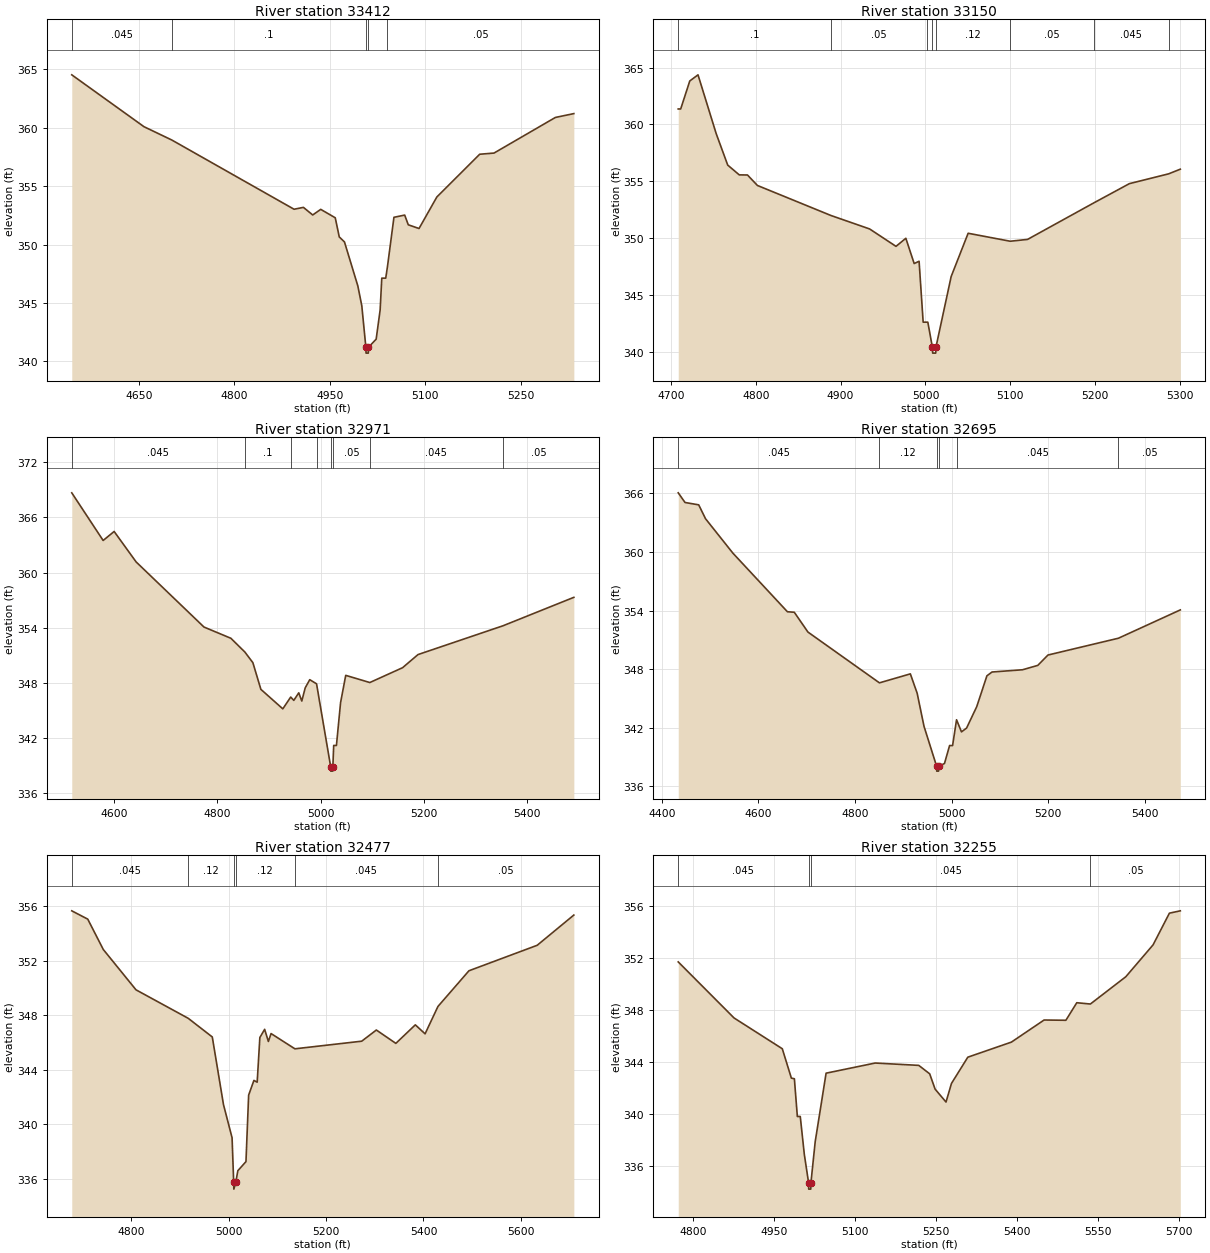
Type RM Length L Ch R = 1 ,33412   ,262,262,262
BEGIN DESCRIPTION:
A19558
END DESCRIPTION:
XS GIS Cut Line= 3
      2523089.21     13711861.05      2522696.54     13712152.05
      2522563.79     13712421.03
#Sta/Elev= 30
  4544.5  364.54  4657.9   360.1  4701.9  358.95  4893.7  353.03  4908.4  353.19
    4923  352.54  4935.6  353.02  4958.4   352.3  4964.7  350.66  4972.9  350.23
  4993.9  346.46  5000.1  344.77  5006.5  341.21  5006.8  340.71  5010.3  340.71
  5010.6  341.21  5022.7  341.91  5028.9   344.4  5031.5  347.13  5037.7  347.13
  5040.4  348.11  5050.6  352.34  5067.5  352.53  5073.1   351.7    5090  351.38
    5118  354.08  5185.3  357.74  5207.8  357.84  5304.2  360.89  5333.2  361.22
#Mann= 5 ,-1 , 0
  4544.5    .045       0  4701.9      .1       0  5006.5     .05       0
  5010.6      .1       0  5040.4     .05       0
Bank Sta=5006.5,5010.6
XS Rating Curve= 0 ,0
Exp/Cntr=0.3,0.1

Type RM Length L Ch R = 1 ,33150   ,179,179,179
BEGIN DESCRIPTION:
KOKERNOT BRANCH 46.0
END DESCRIPTION:
XS GIS Cut Line= 3
      2522725.01     13711674.99        2522575.       13711925.
        2522575.     13712225.04
#Sta/Elev= 30
  4708.7  361.36  4711.6  361.36  4722.3  363.82    4732  364.36  4753.4   359.2
    4767  356.43  4780.6  355.57  4790.3  355.56    4802  354.64  4888.7     352
  4934.2  350.82  4965.3  349.29  4976.9     350  4986.7  347.78  4992.5  347.98
  4997.3  342.63  5001.4  342.63  5002.8  342.63  5008.2  340.41  5008.5  339.91
  5012.1  339.91  5012.3  340.41  5030.3  346.64  5050.3  350.44  5099.9  349.74
  5120.3   349.9  5198.4  353.11  5240.3   354.8  5286.5  355.66  5300.3  356.07
#Mann= 8 ,-1 , 0
  4708.7      .1       0  4888.7     .05       0  5001.4     .12       0
  5008.2     .05       0  5012.3     .12       0  5099.9     .05       0
  5198.4    .045       0  5286.5     .05       0
Bank Sta=5008.2,5012.3
XS Rating Curve= 0 ,0
Exp/Cntr=0.3,0.1

Type RM Length L Ch R = 1 ,32971   ,276,276,276
BEGIN DESCRIPTION:
A19559
END DESCRIPTION:
XS GIS Cut Line= 3
      2522682.49     13711419.36      2522416.07     13711854.05
      2522402.04      13712316.8
#Sta/Elev= 30
  4517.7  368.67  4578.5  363.49  4599.8  364.47  4642.4  361.16  4773.9  354.08
    4826  352.86    4853  351.37  4868.6  350.21  4884.1  347.31  4926.6  345.19
  4941.9  346.47  4947.9  346.11  4957.5  346.93  4963.4  346.04    4970  347.47
  4978.8  348.36    4992  347.91  5019.3  338.92  5019.6  338.42  5023.3  338.42
  5023.6  338.92  5025.2  341.21  5030.5  341.21  5038.5  345.85  5048.5  348.83
  5095.2  348.05  5158.6  349.66  5188.6  351.09  5353.3  354.22  5490.5  357.31
#Mann= 8 ,-1 , 0
  4517.7    .045       0    4853      .1       0  4941.9     .12       0
    4992     .05       0  5019.3     .05       0  5023.6     .05       0
  5095.2    .045       0  5353.3     .05       0
Bank Sta=5019.3,5023.6
XS Rating Curve= 0 ,0
Exp/Cntr=0.3,0.1

Type RM Length L Ch R = 1 ,32695   ,218,218,218
BEGIN DESCRIPTION:
KOKERNOT BRANCH 45.0
END DESCRIPTION:
XS GIS Cut Line= 3
      2522574.97     13711375.03        2522175.       13711775.
        2522325.     13712225.01
#Sta/Elev= 30
  4433.9  366.06    4448  365.07  4476.3  364.83  4490.4  363.41    4547  359.89
  4660.1  353.88  4674.3  353.83  4702.6   351.8  4850.7   346.6  4914.7  347.52
  4928.8  345.54    4943  342.15  4969.1  338.06  4969.4  337.56  4973.1  337.56
  4973.4  338.06  4985.4  338.34    4996  340.18  5002.2  340.18  5010.4  342.82
  5020.6  341.58  5031.2  341.97  5052.2  344.16  5073.3  347.32  5083.9  347.71
  5147.1  347.94  5178.7  348.39  5199.8  349.45  5345.7  351.17  5473.9  354.07
#Mann= 6 ,-1 , 0
  4433.9    .045       0  4850.7     .12       0  4969.1     .05       0
  4973.4     .12       0  5010.4    .045       0  5345.7     .05       0
Bank Sta=4969.1,4973.4
XS Rating Curve= 0 ,0
Exp/Cntr=0.3,0.1

Type RM Length L Ch R = 1 ,32477   ,222,222,222
BEGIN DESCRIPTION:
A19557
END DESCRIPTION:
XS GIS Cut Line= 3
      2522198.71     13711335.16      2521991.86     13711787.44
      2521991.86      13712320.2
#Sta/Elev= 30
  4678.4  355.68  4711.2  355.07  4743.1  352.84  4810.2  349.88  4917.3  347.79
  4966.7  346.42  4989.7  341.45  5007.3  339.02  5010.6  335.75  5010.9  335.25
  5014.9  335.75  5019.1   336.6  5035.8  337.27  5041.3  342.15  5052.1  343.23
  5058.8   343.1  5064.3  346.38  5074.1  346.98  5081.8  346.09  5087.3  346.67
  5136.2  345.55  5273.3  346.11  5303.3  346.93  5343.3  345.95  5383.3  347.31
  5403.3  346.65  5429.7  348.66  5493.3  351.28  5633.3  353.15  5708.5  355.37
#Mann= 6 ,-1 , 0
  4678.4    .045       0  4917.3     .12       0  5010.6     .05       0
  5014.9     .12       0  5136.2    .045       0  5429.7     .05       0
Bank Sta=5010.6,5014.9
XS Rating Curve= 0 ,0
Exp/Cntr=0.3,0.1

Type RM Length L Ch R = 1 ,32255   ,303,303,303
BEGIN DESCRIPTION:
KOKERNOT BRANCH 44.0
END DESCRIPTION:
XS GIS Cut Line= 3
      2521975.01     13711324.97        2521875.       13711525.
      2521775.01     13712224.96
#Sta/Elev= 30
  4772.1  351.68  4875.5  347.37    4965     345  4981.8  342.74  4987.4  342.69
  4992.9  339.79  4998.3  339.79  5005.8  336.88  5013.7   334.7    5014   334.2
  5017.8   334.2  5018.1   334.7    5026  337.85  5046.2  343.12  5137.2   343.9
    5218  343.72  5238.2  343.07  5248.3  341.89  5268.5   340.9  5278.6  342.33
  5308.9  344.35  5389.7  345.51  5450.3  347.21  5490.7  347.19  5510.9  348.54
  5536.1  348.44  5601.8  350.54  5652.3  352.99  5682.6  355.43  5702.8  355.61
#Mann= 4 ,-1 , 0
  4772.1    .045       0  5013.7    .045       0  5018.1    .045       0
  5536.1     .05       0
Bank Sta=5013.7,5018.1
XS Rating Curve= 0 ,0
Exp/Cntr=0.3,0.1

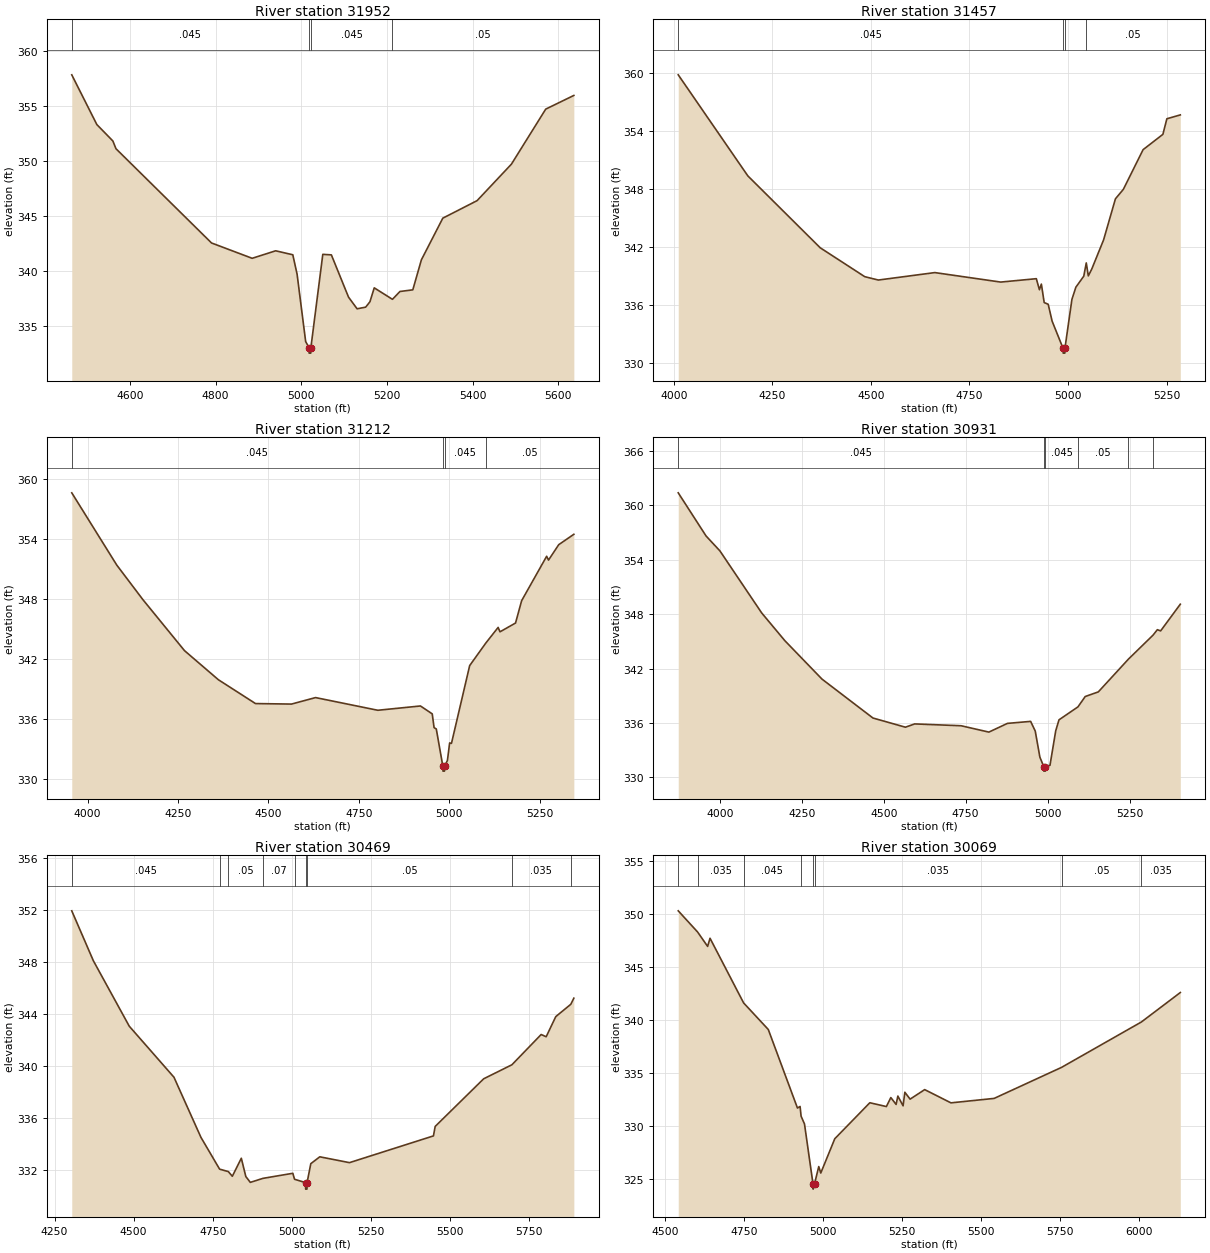
Type RM Length L Ch R = 1 ,31952   ,495,495,495
BEGIN DESCRIPTION:
A19556
END DESCRIPTION:
XS GIS Cut Line= 3
       2521827.1     13711149.34      2521616.73     13711566.57
      2521606.22     13712270.63
#Sta/Elev= 30
  4464.6   357.8  4523.1  353.29  4560.5   351.8  4567.7   351.1  4790.7  342.55
  4885.5  341.16  4940.3  341.84  4980.3  341.48  4990.3  339.72  5010.3  333.61
  5018.1  333.06  5018.4  332.56  5022.2  332.56  5022.5  333.06  5050.3  341.52
  5070.3  341.47  5110.3  337.64  5130.3  336.58  5150.3  336.73  5160.3  337.22
  5170.3  338.48  5212.8  337.44  5230.3  338.15  5260.3   338.3  5280.3  341.02
  5330.3   344.8  5410.3  346.39  5490.4   349.7  5570.4  354.69    5636  355.93
#Mann= 4 ,-1 , 0
  4464.6    .045       0  5018.1    .045       0  5022.5    .045       0
  5212.8     .05       0
Bank Sta=5018.1,5022.5
XS Rating Curve= 0 ,0
Exp/Cntr=0.3,0.1

Type RM Length L Ch R = 1 ,31457   ,245,245,245
BEGIN DESCRIPTION:
A19555
END DESCRIPTION:
XS GIS Cut Line= 3
      2521742.96     13711075.71      2521381.84      13711766.4
      2521339.91     13712259.02
#Sta/Elev= 30
  4011.2  359.81  4187.8  349.37  4371.5  341.94  4484.3  338.96  4518.9  338.61
  4662.2  339.38  4829.3   338.4  4919.7  338.75  4927.5  337.61  4932.5  338.19
  4939.7  336.28  4949.8  336.11  4959.8  334.36  4987.5  331.56  4987.9  331.06
    4992  331.06  4992.3  331.56    5010  336.61    5020  337.87  5040.1  339.01
  5046.4  340.38  5051.6  339.04  5060.2  339.73  5090.3  342.75  5120.4     347
  5140.5  347.98  5190.6  352.08  5240.8  353.66  5250.9  355.27    5285  355.67
#Mann= 4 ,-1 , 0
  4011.2    .045       0  4987.5    .045       0  4992.3    .045       0
  5046.4     .05       0
Bank Sta=4987.5,4992.3
XS Rating Curve= 0 ,0
Exp/Cntr=0.3,0.1

Type RM Length L Ch R = 1 ,31212   ,281,281,281
BEGIN DESCRIPTION:
A19554
END DESCRIPTION:
XS GIS Cut Line= 3
      2521707.86     13711075.79      2521174.99     13711896.12
      2521083.85     13712295.75
#Sta/Elev= 30
  3956.2  358.62  4080.6  351.39  4153.1  347.92  4267.8  342.83  4361.4  339.92
  4464.2  337.53  4563.7  337.48  4630.2  338.13  4802.3  336.86  4920.2  337.29
  4952.8   336.5  4957.9  335.12    4964  334.99  4982.1  331.27  4982.5  330.77
  4986.6  330.77  4986.9  331.27  4994.8  331.84  5000.9  333.59    5006  333.55
  5056.3  341.33  5100.8  343.58    5135  345.15  5140.1  344.71  5183.1  345.59
  5199.9  347.82  5269.1  352.27  5274.3  351.89  5302.5  353.43  5344.3  354.47
#Mann= 4 ,-1 , 0
  3956.2    .045       0  4982.1    .045       0  4986.9    .045       0
  5100.8     .05       0
Bank Sta=4982.1,4986.9
XS Rating Curve= 0 ,0
Exp/Cntr=0.3,0.1

Type RM Length L Ch R = 1 ,30931   ,462,462,462
BEGIN DESCRIPTION:
KOKERNOT BRANCH 43.0
END DESCRIPTION:
XS GIS Cut Line= 3
      2521724.97     13711025.03        2520925.       13711825.
        2520925.     13712224.97
#Sta/Elev= 30
  3873.3  361.36  3958.1  356.61  4000.5  354.96  4127.8  348.13  4198.5  345.07
  4311.7  340.84  4467.2  336.55  4566.2  335.54  4594.5   335.9  4735.9   335.7
  4820.8     335  4877.4  335.96  4948.1  336.18  4962.2  335.11  4976.3  332.24
  4988.1   331.2  4988.4   330.7  4992.5   330.7  4992.9   331.2  5007.1  331.34
  5024.6  335.14  5034.6  336.35  5092.5  337.78  5114.6  338.92  5154.6  339.43
  5246.4  343.04  5321.1  345.67  5334.6  346.28  5344.6  346.15  5404.6  349.09
#Mann= 6 ,-1 , 0
  3873.3    .045       0  4988.1    .045       0  4992.9    .045       0
  5092.5     .05       0  5246.4    .035       0  5321.1     .05       0
Bank Sta=4988.1,4992.9
XS Rating Curve= 0 ,0
Exp/Cntr=0.3,0.1

Type RM Length L Ch R = 1 ,30469   ,400,400,400
BEGIN DESCRIPTION:
A19553
END DESCRIPTION:
XS GIS Cut Line= 3
      2521343.25     13710956.57      2520726.25     13711520.99
      2520417.71     13712204.67
#Sta/Elev= 30
  4304.5  351.95  4372.8   348.1  4486.2  343.06  4627.4  339.13  4712.6   334.5
  4771.6  332.05  4799.2  331.86  4811.8   331.5  4840.2  332.89  4854.4  331.48
  4868.6  331.03  4908.6  331.34    5003  331.73  5008.3  331.27  5043.2  331.01
  5043.5  330.51  5047.6  330.51    5048  331.01  5059.7  332.47  5088.1     333
  5181.9  332.55  5447.2  334.61  5452.7  335.34  5605.9  339.01  5695.1  340.09
  5787.5  342.42  5803.4  342.25  5833.7   343.8  5881.2  344.75  5890.8  345.22
#Mann= 9 ,-1 , 0
  4304.5    .045       0  4771.6     .07       0  4799.2     .05       0
  4908.6     .07       0  5008.3     .05       0  5043.2     .05       0
    5048     .05       0  5695.1    .035       0  5881.2     .05       0
Bank Sta=5043.2,5048
XS Rating Curve= 0 ,0
Exp/Cntr=0.3,0.1

Type RM Length L Ch R = 1 ,30069   ,174,174,174
BEGIN DESCRIPTION:
A19552
END DESCRIPTION:
XS GIS Cut Line= 4
      2521101.39     13710760.21      2520810.39     13711012.64
      2520645.61     13711331.68      2520400.19     13712138.05
#Sta/Elev= 30
  4542.1  350.31  4603.3  348.31    4635  346.95  4642.6  347.72  4748.8  341.61
  4826.8   339.1    4919  331.68  4927.3  331.83  4930.5  330.91  4941.2  330.18
  4968.1  324.52  4968.5  324.02    4973  324.52  4986.3  326.15  4992.7  325.54
    5037  328.78  5147.8  332.18  5200.1  331.82  5214.2  332.67  5230.8  332.02
  5236.4  332.81  5252.9  331.89  5258.5  333.17  5275.1  332.52  5321.2  333.42
  5404.2  332.17  5540.8  332.59  5753.8  335.52  6006.3  339.81  6129.3  342.59
#Mann= 8 ,-1 , 0
  4542.1     .07       0  4603.3    .035       0  4748.8    .045       0
  4930.5    .035       0  4968.1    .035       0    4973    .035       0
  5753.8     .05       0  6006.3    .035       0
Bank Sta=4968.1,4973
XS Rating Curve= 0 ,0
Exp/Cntr=0.3,0.1

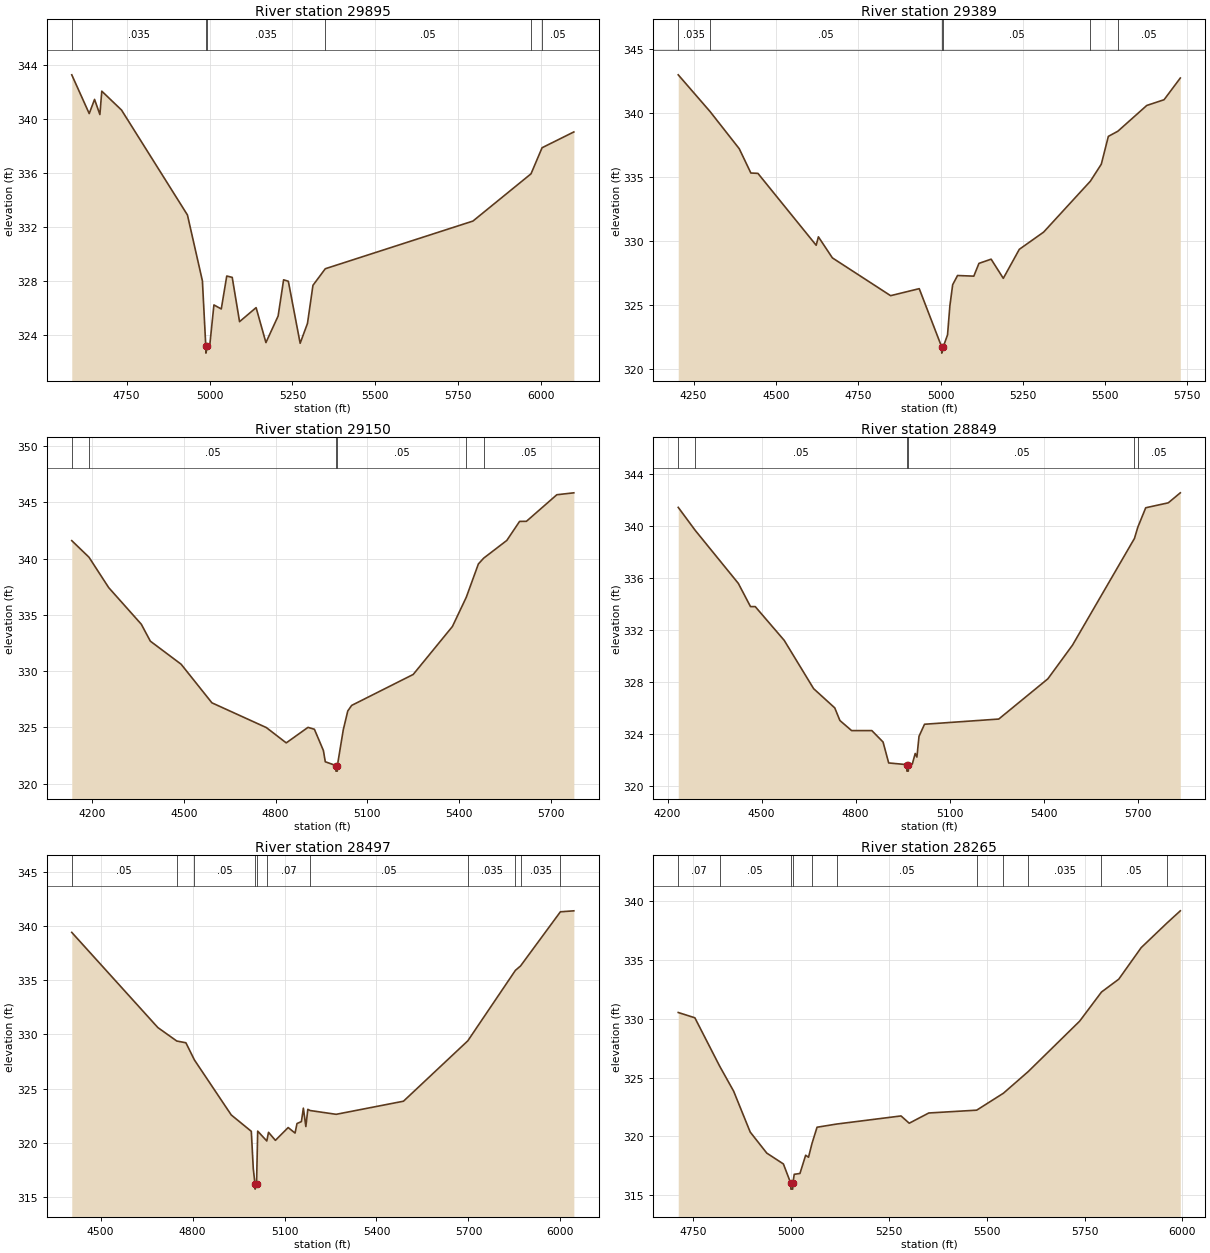
Type RM Length L Ch R = 1 ,29895   ,506,506,506
BEGIN DESCRIPTION:
A19551
END DESCRIPTION:
XS GIS Cut Line= 4
      2520862.96     13710609.49      2520691.19     13710921.49
      2520442.27     13711401.79      2520119.86     13711927.46
#Sta/Elev= 30
  4584.6  343.28  4637.2  340.41  4653.3  341.46  4669.4  340.34  4675.1  342.07
  4734.7  340.67  4933.4   332.9  4978.5  328.02  4988.7  323.17    4989  322.67
  4993.6  323.17    5001  323.33  5013.2  326.24  5035.4  325.94  5051.9  328.38
  5068.4  328.28  5090.5     325  5140.4  326.04    5170  323.45  5206.8  325.42
  5223.3   328.1  5237.6  327.99  5273.2   323.4  5295.3  324.87  5311.8  327.69
    5349  328.92  5794.2  332.45  5969.3  335.95  6002.6  337.88  6098.4  339.05
#Mann= 6 ,-1 , 0
  4584.6    .035       0  4988.7    .035       0  4993.6    .035       0
    5349     .05       0  5969.3    .035       0  6002.6     .05       0
Bank Sta=4988.7,4993.6
XS Rating Curve= 0 ,0
Exp/Cntr=0.3,0.1

Type RM Length L Ch R = 1 ,29389   ,239,239,239
BEGIN DESCRIPTION:
A19550
END DESCRIPTION:
XS GIS Cut Line= 3
      2520827.92     13710605.95      2520347.61     13711121.32
      2519926.91       13711826.
#Sta/Elev= 30
  4203.3  343.01  4300.1  340.13  4388.7  337.22  4423.9  335.32  4445.4  335.29
  4622.3  329.66  4629.1  330.32  4671.6  328.67  4848.5  325.71  4935.4  326.26
  5003.4  321.71  5003.8  321.21  5008.4  321.71  5021.4  322.64  5028.5  324.92
    5037  326.57  5051.8  327.29  5101.2  327.24  5116.8  328.24  5153.8  328.57
  5190.8  327.07  5239.4  329.34  5313.3  330.69  5455.3  334.68  5488.5  336.01
  5509.9  338.19  5538.7  338.59  5626.6  340.61  5679.2  341.06  5728.5  342.76
#Mann= 6 ,-1 , 0
  4203.3    .035       0  4300.1     .05       0  5003.4     .05       0
  5008.4     .05       0  5455.3    .035       0  5538.7     .05       0
Bank Sta=5003.4,5008.4
XS Rating Curve= 0 ,0
Exp/Cntr=0.3,0.1

Type RM Length L Ch R = 1 ,29150   ,301,301,301
BEGIN DESCRIPTION:
A19549
END DESCRIPTION:
XS GIS Cut Line= 3
      2520796.39     13710588.41      2520000.53     13711163.39
      2519485.18     13711573.58
#Sta/Elev= 30
  4134.2   341.6  4190.4  340.13  4254.8  337.43  4361.5  334.17  4390.9  332.67
  4491.5  330.62  4592.1  327.19    4770  324.99    4835  323.63  4906.1  325.01
    4927  324.84  4956.4  322.95  4962.6  321.95  4996.9  321.62  4997.3  321.12
  5001.7  321.12  5002.1  321.62  5021.4   324.8  5036.1  326.47  5048.8  326.96
  5249.8  329.71  5377.9  333.97  5423.1  336.56  5462.8  339.53  5480.3  340.05
  5555.7  341.62  5597.4  343.31  5619.8  343.32  5719.1  345.68  5774.7  345.85
#Mann= 6 ,-1 , 0
  4134.2    .035       0  4190.4     .05       0  4996.9     .05       0
  5002.1     .05       0  5423.1    .035       0  5480.3     .05       0
Bank Sta=4996.9,5002.1
XS Rating Curve= 0 ,0
Exp/Cntr=0.3,0.1

Type RM Length L Ch R = 1 ,28849   ,352,352,352
BEGIN DESCRIPTION:
A19548
END DESCRIPTION:
XS GIS Cut Line= 3
      2520789.39     13710549.85      2520028.58     13710851.37
      2519416.44     13711341.08
#Sta/Elev= 30
    4234  341.46  4288.2  339.69  4425.7  335.61  4464.6  333.82  4479.7  333.82
  4572.2  331.22  4666.1   327.5  4733.5  326.02  4749.9  325.05  4787.3  324.27
  4851.9  324.27  4887.7  323.39  4905.6  321.78  4963.4  321.65  4963.8  321.15
  4968.2  321.15  4968.6  321.65  4980.9  321.69  4990.3  322.51  4995.7  322.23
  5002.4  323.83    5020  324.76  5256.9  325.16  5413.7  328.26  5492.2  330.85
    5690  339.07  5700.5  339.92  5725.9  341.43  5797.9  341.81  5836.3  342.58
#Mann= 6 ,-1 , 0
    4234    .035       0  4288.2     .05       0  4963.4     .05       0
  4968.6     .05       0    5690    .035       0  5700.5     .05       0
Bank Sta=4963.4,4968.6
XS Rating Curve= 0 ,0
Exp/Cntr=0.3,0.1

Type RM Length L Ch R = 1 ,28497   ,232,232,232
BEGIN DESCRIPTION:
A19547
END DESCRIPTION:
XS GIS Cut Line= 4
      2520701.69     13710420.16      2520140.77     13710518.32
      2519954.96     13710665.56      2519394.04     13711279.07
#Sta/Elev= 30
    4406   339.4  4686.9  330.62  4748.6  329.38  4778.3  329.22  4806.2  327.63
  4926.3  322.56  4991.7  321.05  4998.1  317.61  5003.6  316.22    5004  315.72
  5008.8  316.22  5012.5  321.07  5042.2  320.16  5047.8  320.96  5070.3  320.22
  5111.9   321.4  5134.4  320.89  5140.7  321.77  5155.1  321.95  5161.5  323.19
  5169.6  321.49    5176  323.08  5183.5  322.97  5268.5  322.62  5488.1  323.83
  5697.9   329.4  5853.2   335.9  5869.8   336.3  5999.9   341.3  6043.8  341.39
#Mann= 11 ,-1 , 0
    4406     .05       0  4748.6     .07       0  4806.2     .05       0
  5003.6     .05       0  5008.8     .05       0  5042.2     .07       0
  5183.5     .05       0  5697.9    .035       0  5853.2     .05       0
  5869.8    .035       0  5999.9     .05       0
Bank Sta=5003.6,5008.8
XS Rating Curve= 0 ,0
Exp/Cntr=0.3,0.1

Type RM Length L Ch R = 1 ,28265   ,210,210,210
BEGIN DESCRIPTION:
KOKERNOT BRANCH 38.0
END DESCRIPTION:
XS GIS Cut Line= 3
      2520175.02     13710174.98        2519975.       13710375.
      2519374.98     13711175.02
#Sta/Elev= 30
  4711.6  330.53  4754.1  330.08  4817.3  325.98  4853.1  323.85  4895.5  320.37
  4937.9  318.58  4980.3  317.66  4999.1  316.02  4999.5  315.52    5004  315.52
  5004.5  316.02    5008  316.78  5022.6  316.85  5037.2   318.4  5044.5  318.23
  5053.3  319.39  5066.3  320.78  5116.3  321.05  5280.9  321.74  5301.8  321.12
  5351.8  321.99  5474.2  322.23  5542.5  323.67  5605.9  325.51  5737.2  329.79
  5793.1  332.27  5837.2  333.36  5894.5  336.04    5960  338.12  5994.5  339.17
#Mann= 11 ,-1 , 0
  4711.6     .07       0  4817.3     .05       0  4999.1     .05       0
  5004.5     .05       0  5053.3     .07       0  5116.3     .05       0
  5474.2    .035       0  5542.5     .05       0  5605.9    .035       0
  5793.1     .05       0    5960    .035       0
Bank Sta=4999.1,5004.5
XS Rating Curve= 0 ,0
Exp/Cntr=0.3,0.1

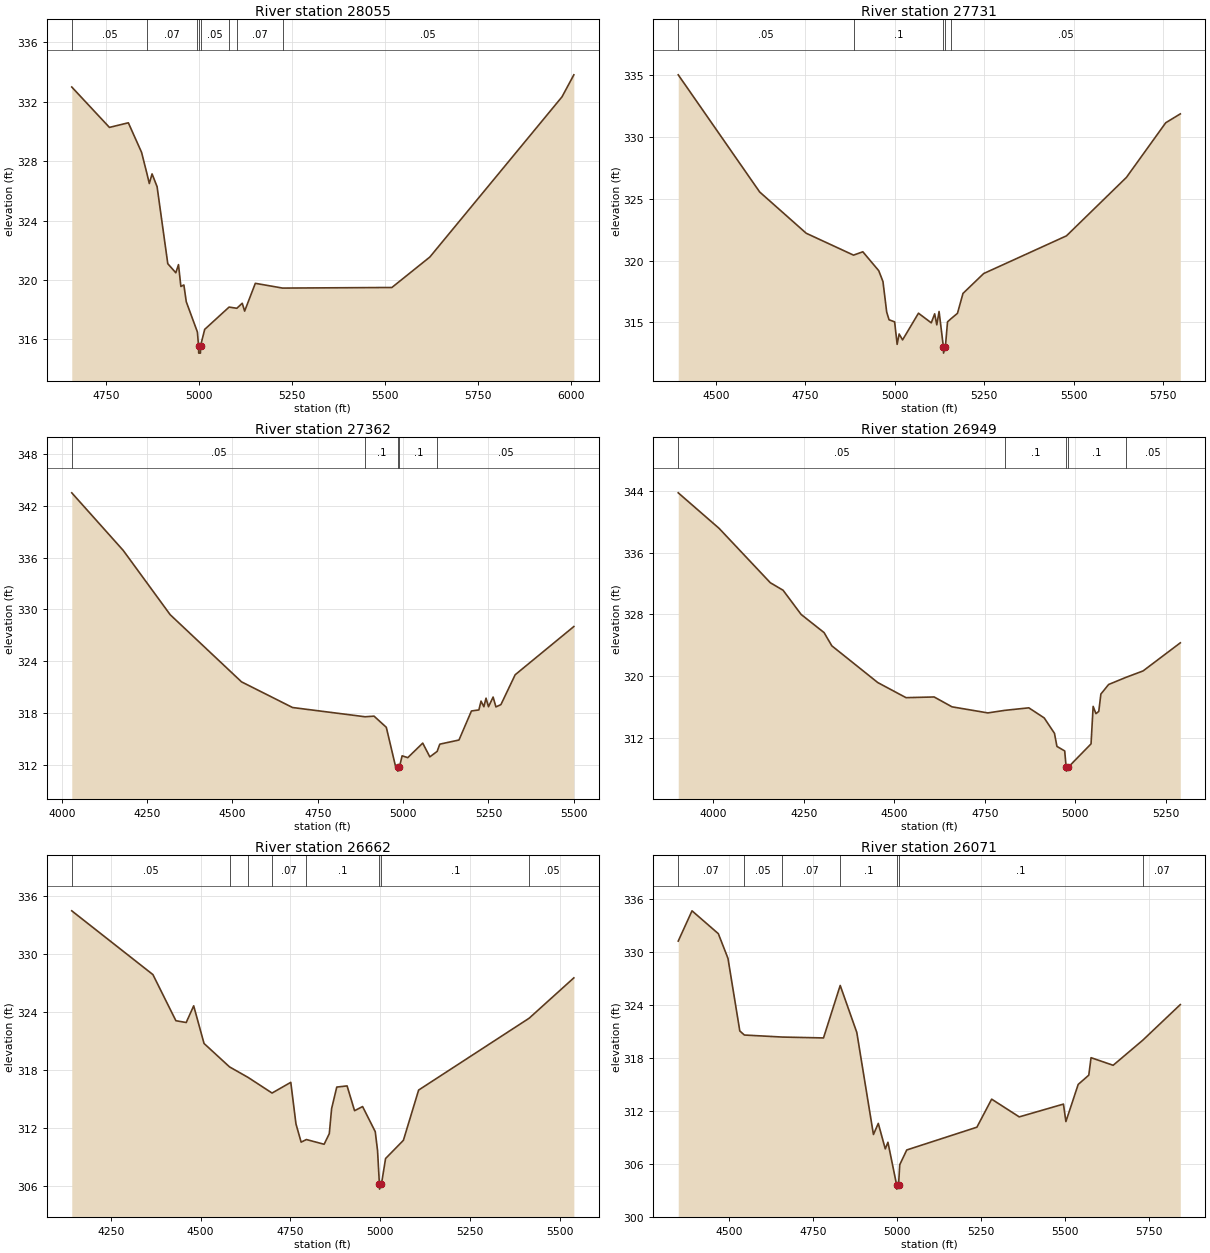
Type RM Length L Ch R = 1 ,28055   ,324,324,324
BEGIN DESCRIPTION:
A19545
END DESCRIPTION:
XS GIS Cut Line= 2
      2520109.18     13709925.87      2519268.89     13710983.24
#Sta/Elev= 30
  4656.9  332.99  4758.2  330.27  4809.1  330.58  4844.7  328.59  4859.3  327.14
  4865.5  326.49  4872.9  327.14  4886.4  326.28  4915.2  321.09  4936.8  320.48
    4944  321.03  4950.4  319.56  4958.5  319.66  4964.9  318.53  4994.9  316.49
  4997.9  315.57  4998.4  315.07    5003  315.07  5003.4  315.57  5014.5  316.67
  5080.1  318.17    5101  318.09  5115.5  318.43  5121.9   317.9  5150.7  319.77
    5224  319.45    5518  319.49  5620.1  321.54  5975.7  332.33  6007.5  333.81
#Mann= 8 ,-1 , 0
  4656.9     .05       0  4859.3     .07       0  4994.9     .05       0
  4997.9     .05       0  5003.4     .05       0  5080.1      .1       0
    5101     .07       0    5224     .05       0
Bank Sta=4997.9,5003.4
XS Rating Curve= 0 ,0
Exp/Cntr=0.3,0.1

Type RM Length L Ch R = 1 ,27731   ,369,369,369
BEGIN DESCRIPTION:
KOKERNOT BRANCH 37.0
END DESCRIPTION:
XS GIS Cut Line= 3
      2519856.79     13709680.43      2519555.29     13710304.46
      2519180.17     13710907.45
#Sta/Elev= 30
  4395.3  335.03  4622.9  325.55    4753  322.21  4885.2  320.44  4911.2  320.71
  4955.7  319.18  4967.5   318.3  4977.9  315.83  4984.5  315.21  5000.1  315.04
  5007.1  313.22  5012.7  314.06  5022.3  313.58  5066.7  315.74  5102.5  314.96
    5112  315.69  5117.9   314.8  5124.3  315.88  5136.4  313.01  5136.8  312.51
  5141.9  313.01  5147.9  315.04  5157.5  315.29  5175.7  315.73  5191.1  317.34
  5248.9  318.95  5480.3     322  5647.9  326.73  5757.7  331.15  5798.5  331.87
#Mann= 5 ,-1 , 0
  4395.3     .05       0  4885.2      .1       0  5136.4     .05       0
  5141.9      .1       0  5157.5     .05       0
Bank Sta=5136.4,5141.9
XS Rating Curve= 0 ,0
Exp/Cntr=0.3,0.1

Type RM Length L Ch R = 1 ,27362   ,413,413,413
BEGIN DESCRIPTION:
KOKERNOT BRANCH 36.0
END DESCRIPTION:
XS GIS Cut Line= 3
      2519825.03     13709474.96        2519275.       13710275.
      2518974.98     13710675.02
#Sta/Elev= 30
  4029.2  343.49  4180.1  336.82  4317.5  329.39  4526.5  321.62    4676  318.65
  4888.6  317.58  4914.8  317.65  4950.7  316.36  4977.7  311.85  4983.8  311.79
  4984.3  311.29  4989.3  311.79    4997  313.06  5013.6  312.85  5057.4  314.53
  5078.2  312.94  5099.6  313.57  5107.4  314.41  5163.6  314.89  5200.1  318.25
  5221.9  318.37  5228.2  319.39  5236.5  318.74  5242.8  319.73  5250.1  318.74
  5263.6  319.86  5271.9  318.72  5286.5  318.99  5328.2  322.44  5500.1  328.02
#Mann= 5 ,-1 , 0
  4029.2     .05       0  4888.6      .1       0  4983.8     .05       0
  4989.3      .1       0  5099.6     .05       0
Bank Sta=4983.8,4989.3
XS Rating Curve= 0 ,0
Exp/Cntr=0.3,0.1

Type RM Length L Ch R = 1 ,26949   ,287,287,287
BEGIN DESCRIPTION:
KOKERNOT BRANCH 35.0
END DESCRIPTION:
XS GIS Cut Line= 3
        2519725.       13709425.        2518975.       13710225.
      2518825.02     13710474.97
#Sta/Elev= 30
  3902.7   343.8  4015.8  339.18  4157.4  332.12  4192.6  331.15  4242.4  328.01
  4305.9  325.65  4327.4  323.93  4454.4  319.16  4532.5   317.2  4610.2  317.29
  4659.6  316.01  4758.7  315.22  4805.4  315.55    4872  315.88  4914.5  314.57
  4942.9  312.57  4949.7  310.87  4971.2  310.28  4975.2  308.16  4975.7  307.66
  4980.8  308.16    5044   311.2  5049.8  316.07  5057.6  315.12  5065.4  315.42
  5071.2  317.67  5092.6  318.91  5140.2  319.83  5187.8  320.67  5290.8  324.32
#Mann= 5 ,-1 , 0
  3902.7     .05       0  4805.4      .1       0  4975.2     .05       0
  4980.8      .1       0  5140.2     .05       0
Bank Sta=4975.2,4980.8
XS Rating Curve= 0 ,0
Exp/Cntr=0.3,0.1

Type RM Length L Ch R = 1 ,26662   ,591,591,591
BEGIN DESCRIPTION:
A19546
END DESCRIPTION:
XS GIS Cut Line= 3
       2519383.5     13709326.33      2518759.46     13710094.11
      2518552.59     13710444.73
#Sta/Elev= 30
  4141.9  334.49  4367.6  327.88  4431.5   323.1  4460.2  322.91    4481  324.64
  4509.8  320.74  4580.8  318.31  4632.8  317.21    4699   315.6  4751.1  316.71
  4765.5   312.4  4779.9  310.51  4794.5  310.78  4843.8  310.29  4858.2  311.39
  4864.6  313.98    4879  316.22  4907.7  316.34  4928.5  313.77  4950.8   314.2
    4986   311.6  4992.4  309.65  4997.6  306.14    4998  305.64  5003.2  306.14
  5014.7  308.81  5064.3   310.7  5106.7  315.91  5414.2  323.36  5538.4  327.54
#Mann= 8 ,-1 , 0
  4141.9     .05       0  4580.8     .07       0  4632.8     .05       0
    4699     .07       0  4794.5      .1       0  4997.6     .05       0
  5003.2      .1       0  5414.2     .05       0
Bank Sta=4997.6,5003.2
XS Rating Curve= 0 ,0
Exp/Cntr=0.3,0.1

Type RM Length L Ch R = 1 ,26071   ,463,463,463
BEGIN DESCRIPTION:
KOKERNOT BRANCH 34.0
END DESCRIPTION:
XS GIS Cut Line= 3
      2519316.89     13709049.36       2518780.5     13709704.96
        2518475.     13710274.99
#Sta/Elev= 30
    4349  331.23    4390  334.66  4468.3  332.07    4497  329.27  4532.2  321.04
  4545.8  320.58  4658.4  320.35  4781.2  320.25  4830.9   326.2  4880.3  320.87
  4929.8   309.3  4944.2  310.56    4965  307.67  4972.9  308.42  4998.7  303.61
  4999.2  303.11  5004.5  303.61  5008.1  305.88  5028.9  307.55  5237.6  310.13
  5281.5  313.31  5363.6   311.3  5495.1  312.75  5502.4  310.77    5539  314.98
  5570.5  316.03  5577.2  318.01    5643  317.15    5731  319.99  5842.8  324.03
#Mann= 7 ,-1 , 0
    4349     .07       0  4545.8     .05       0  4658.4     .07       0
  4830.9      .1       0  4998.7     .05       0  5004.5      .1       0
    5731     .07       0
Bank Sta=4998.7,5004.5
XS Rating Curve= 0 ,0
Exp/Cntr=0.3,0.1

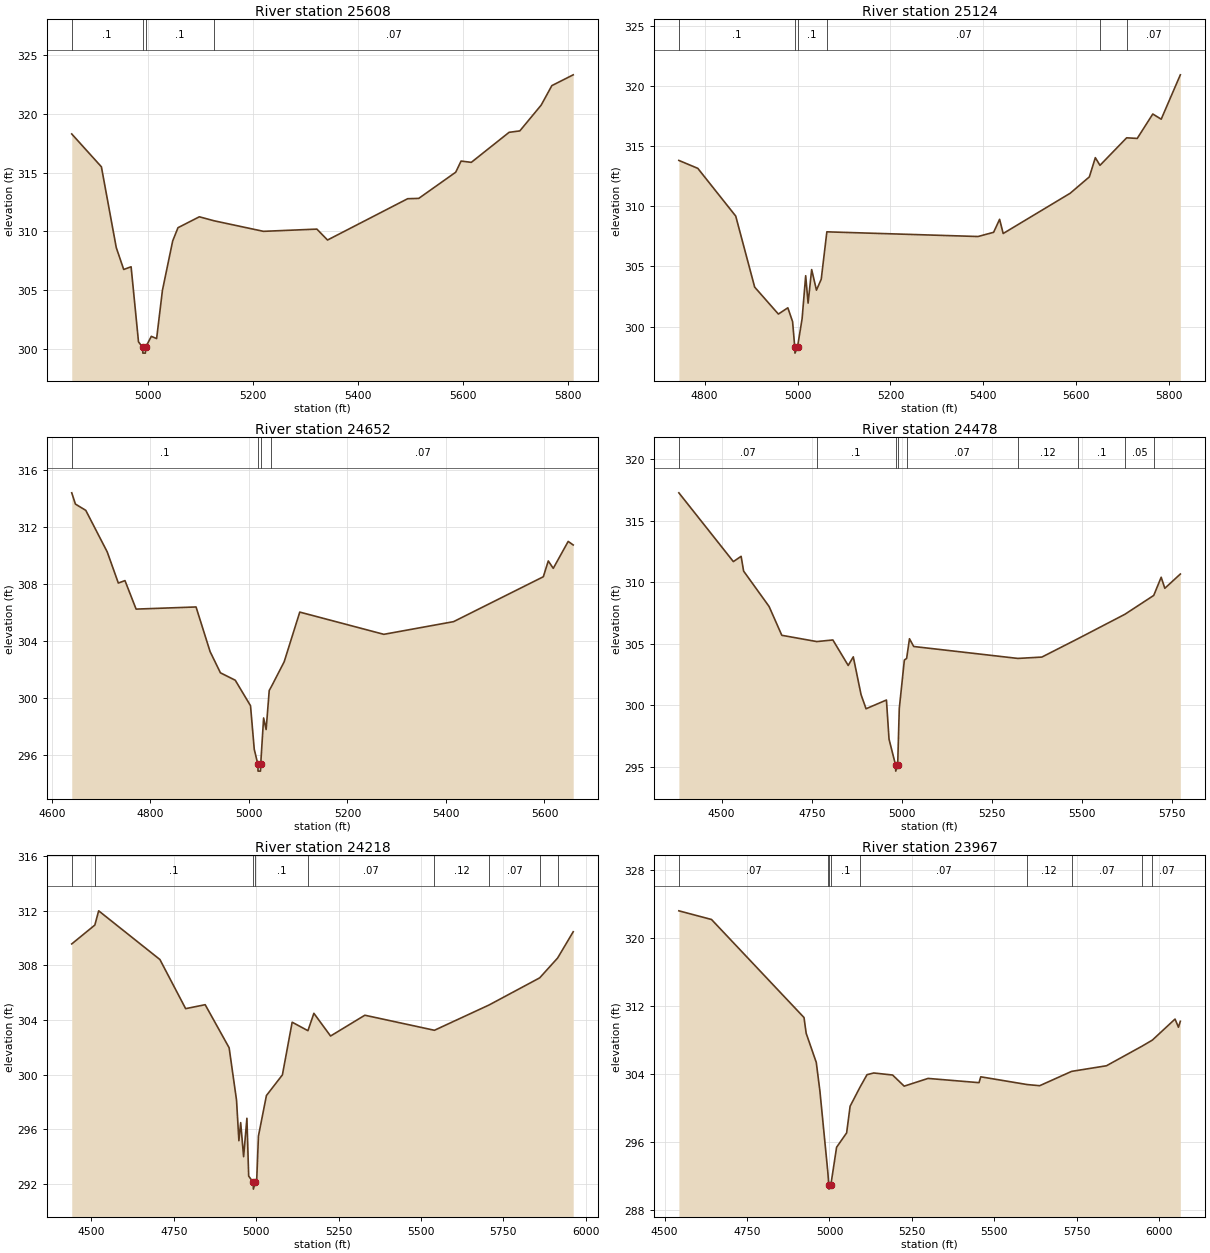
Type RM Length L Ch R = 1 ,25608   ,484,484,484
BEGIN DESCRIPTION:
KOKERNOT BRANCH 33.0
END DESCRIPTION:
XS GIS Cut Line= 3
      2518624.98     13709325.02        2518525.       13709425.
      2518375.01     13710224.97
#Sta/Elev= 30
  4854.2  318.31  4910.7  315.51    4939  308.63  4953.2  306.76  4967.3  306.99
  4981.4  300.59  4989.2  300.13  4989.7  299.63  4994.5  299.63    4995  300.13
  5005.8  301.06  5015.9  300.87    5027  304.99  5046.5  309.19  5056.6  310.32
  5097.3  311.25  5125.3  310.91  5219.4  310.01  5321.2   310.2  5341.5  309.27
  5494.1  312.79  5515.3  312.82  5585.7  315.05  5595.9     316  5615.4  315.89
  5687.4  318.45  5707.8  318.57  5748.5  320.77  5768.8  322.43  5809.5  323.35
#Mann= 4 ,-1 , 0
  4854.2      .1       0  4989.2     .05       0    4995      .1       0
  5125.3     .07       0
Bank Sta=4989.2,4995
XS Rating Curve= 0 ,0
Exp/Cntr=0.3,0.1

Type RM Length L Ch R = 1 ,25124   ,472,472,472
BEGIN DESCRIPTION:
KOKERNOT BRANCH 32.0
END DESCRIPTION:
XS GIS Cut Line= 3
        2518125.     13709074.98        2518075.       13709325.
        2518275.     13710125.01
#Sta/Elev= 30
  4744.5  313.82  4785.3  313.16  4866.9  309.19  4907.7  303.28  4958.7  301.04
  4979.1  301.56  4989.3  300.41    4994  298.29  4994.5  297.79  4999.9  298.29
  5009.8  300.65  5017.5  304.23  5022.7  301.95  5030.4  304.74  5040.7  303.03
    5051  303.94  5063.1  307.88  5388.6  307.49  5422.1  307.84    5435  308.92
  5442.7  307.74    5587  311.09  5628.2  312.45  5641.1  314.05  5651.1  313.41
  5708.5   315.7  5731.3  315.65  5764.8  317.68  5782.9  317.25  5824.1  320.94
#Mann= 6 ,-1 , 0
  4744.5      .1       0    4994     .05       0  4999.9      .1       0
  5063.1     .07       0  5651.1     .05       0  5708.5     .07       0
Bank Sta=4994,4999.9
XS Rating Curve= 0 ,0
Exp/Cntr=0.3,0.1

Type RM Length L Ch R = 1 ,24652   ,174,174,174
BEGIN DESCRIPTION:
KOKERNOT BRANCH 31.0
END DESCRIPTION:
XS GIS Cut Line= 3
      2517974.97     13709025.02        2517675.       13709225.
      2517775.01     13709875.03
#Sta/Elev= 30
  4640.2   314.4  4647.7  313.61  4668.7  313.17  4712.3  310.25  4734.8  308.07
  4748.3  308.24  4770.9  306.24  4892.6  306.39  4921.1  303.26  4942.1  301.77
  4972.2  301.25  5003.2  299.46  5010.8   296.4    5018  295.37  5018.5  294.87
  5023.4  294.87  5023.9  295.37  5029.8   298.6  5034.9  297.79  5041.2  300.53
  5045.7  300.81  5071.5  302.54  5103.2  306.03  5273.9  304.47  5415.5  305.36
  5597.7  308.51  5607.8  309.62  5617.9   309.1  5648.2  310.99  5658.4  310.74
#Mann= 4 ,-1 , 0
  4640.2      .1       0    5018     .05       0  5023.9      .1       0
  5045.7     .07       0
Bank Sta=5018,5023.9
XS Rating Curve= 0 ,0
Exp/Cntr=0.3,0.1

Type RM Length L Ch R = 1 ,24478   ,260,260,260
BEGIN DESCRIPTION:
A19544
END DESCRIPTION:
XS GIS Cut Line= 3
      2517932.11     13708758.34      2517483.33     13709231.67
      2517535.92     13709967.93
#Sta/Elev= 30
  4381.6  317.26  4532.7  311.67  4554.2   312.1  4561.1   310.9  4631.8  308.02
    4667  305.68    4764  305.17  4808.6   305.3  4851.1  303.23  4865.2  303.93
  4886.7  300.86  4900.6  299.71  4957.1  300.42  4964.3  297.24  4982.4  295.14
  4982.9  294.64  4988.3  295.14  4992.7  299.72  5006.8  303.67  5013.1   303.8
    5021   305.4  5032.7  304.77  5321.6   303.8  5388.1  303.91  5487.2  305.39
  5618.4  307.39  5698.2  308.92  5718.9   310.4    5729   309.5    5772  310.66
#Mann= 9 ,-1 , 0
  4381.6     .07       0    4764      .1       0  4982.4     .05       0
  4988.3      .1       0  5013.1     .07       0  5321.6     .12       0
  5487.2      .1       0  5618.4     .05       0  5698.2     .07       0
Bank Sta=4982.4,4988.3
XS Rating Curve= 0 ,0
Exp/Cntr=0.3,0.1

Type RM Length L Ch R = 1 ,24218   ,251,251,251
BEGIN DESCRIPTION:
A19543
END DESCRIPTION:
XS GIS Cut Line= 3
      2517599.04     13708470.86      2517339.59     13709119.48
      2517472.57     13709931.37
#Sta/Elev= 30
  4440.4  309.56  4510.5  310.94  4522.1  311.98  4707.9  308.42    4786  304.83
  4845.2  305.12  4917.9  301.97  4940.3  298.15  4947.5  295.18  4952.9   296.5
  4961.8  294.01  4971.8  296.82  4977.2  292.59    4991  292.14  4991.5  291.64
  4997.2  292.14  5001.4  292.21  5006.8  295.52    5031  298.48  5079.5  299.99
  5109.1  303.84  5156.9  303.22    5175  304.49  5225.6  302.83  5329.6  304.35
  5540.7  303.25  5706.6   305.1    5860  307.08  5914.4  308.53  5961.7  310.45
#Mann= 9 ,-1 , 0
  4440.4     .12       0  4510.5      .1       0    4991     .05       0
  4997.2      .1       0  5156.9     .07       0  5540.7     .12       0
  5706.6     .07       0    5860     .05       0  5914.4     .07       0
Bank Sta=4991,4997.2
XS Rating Curve= 0 ,0
Exp/Cntr=0.3,0.1

Type RM Length L Ch R = 1 ,23967   ,340,340,340
BEGIN DESCRIPTION:
A19542
END DESCRIPTION:
XS GIS Cut Line= 3
      2517066.13     13708488.43       2517223.9     13709182.59
      2517448.14     13709960.45
#Sta/Elev= 30
  4543.2  323.25  4642.2  322.23  4922.9  310.68  4929.4  308.83  4960.1  305.39
  4971.1  302.02  4994.9  292.57  4998.1  290.97  4998.6  290.47  5004.3  290.97
  5021.7   295.4  5052.2   297.1  5062.7  300.23  5092.2  302.44    5114  303.95
  5134.5  304.15  5191.6  303.91  5226.8   302.6  5299.2  303.51  5453.9  303.01
  5459.1   303.7  5599.4  302.79  5637.8  302.65  5734.8  304.34  5840.4     305
    5948   307.3  5979.6  308.02  6048.5   310.5  6058.9  309.54  6064.6  310.24
#Mann= 9 ,-1 , 0
  4543.2     .07       0  4994.9      .1       0  4998.1     .05       0
  5004.3      .1       0  5092.2     .07       0  5599.4     .12       0
  5734.8     .07       0    5948     .05       0  5979.6     .07       0
Bank Sta=4998.1,5004.3
XS Rating Curve= 0 ,0
Exp/Cntr=0.3,0.1