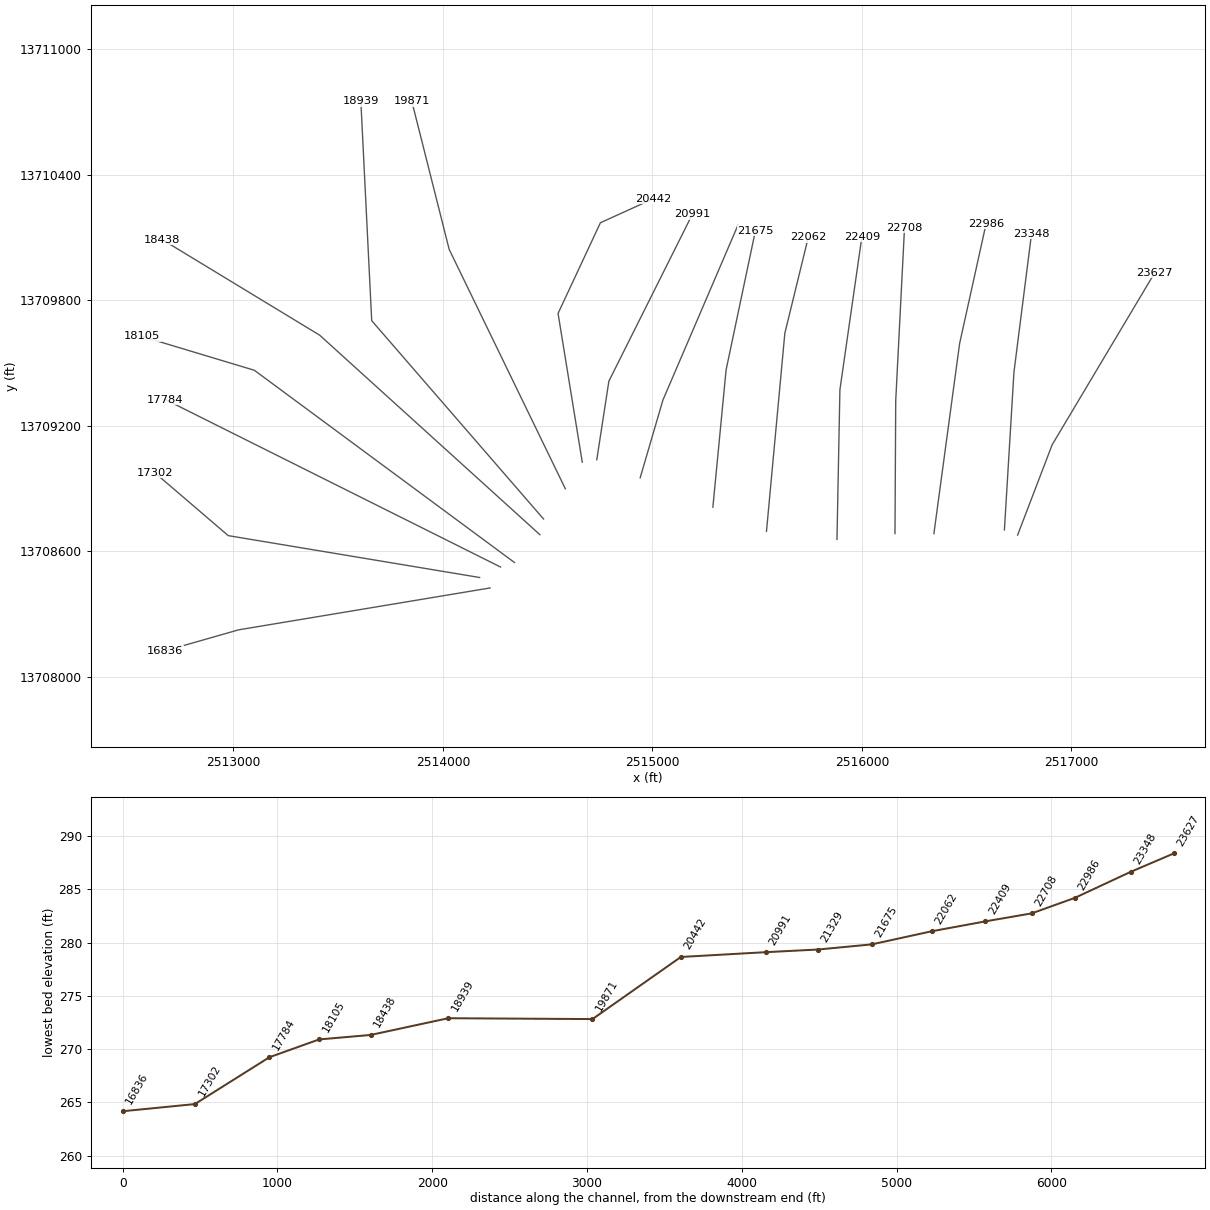
HEC-RAS study KOKERNOT BRANCH.prj: KOKERNOT BRANCH Base Level Engineering

--- KOKERNOT BRANCH.g01 (geometry) --- (continued)

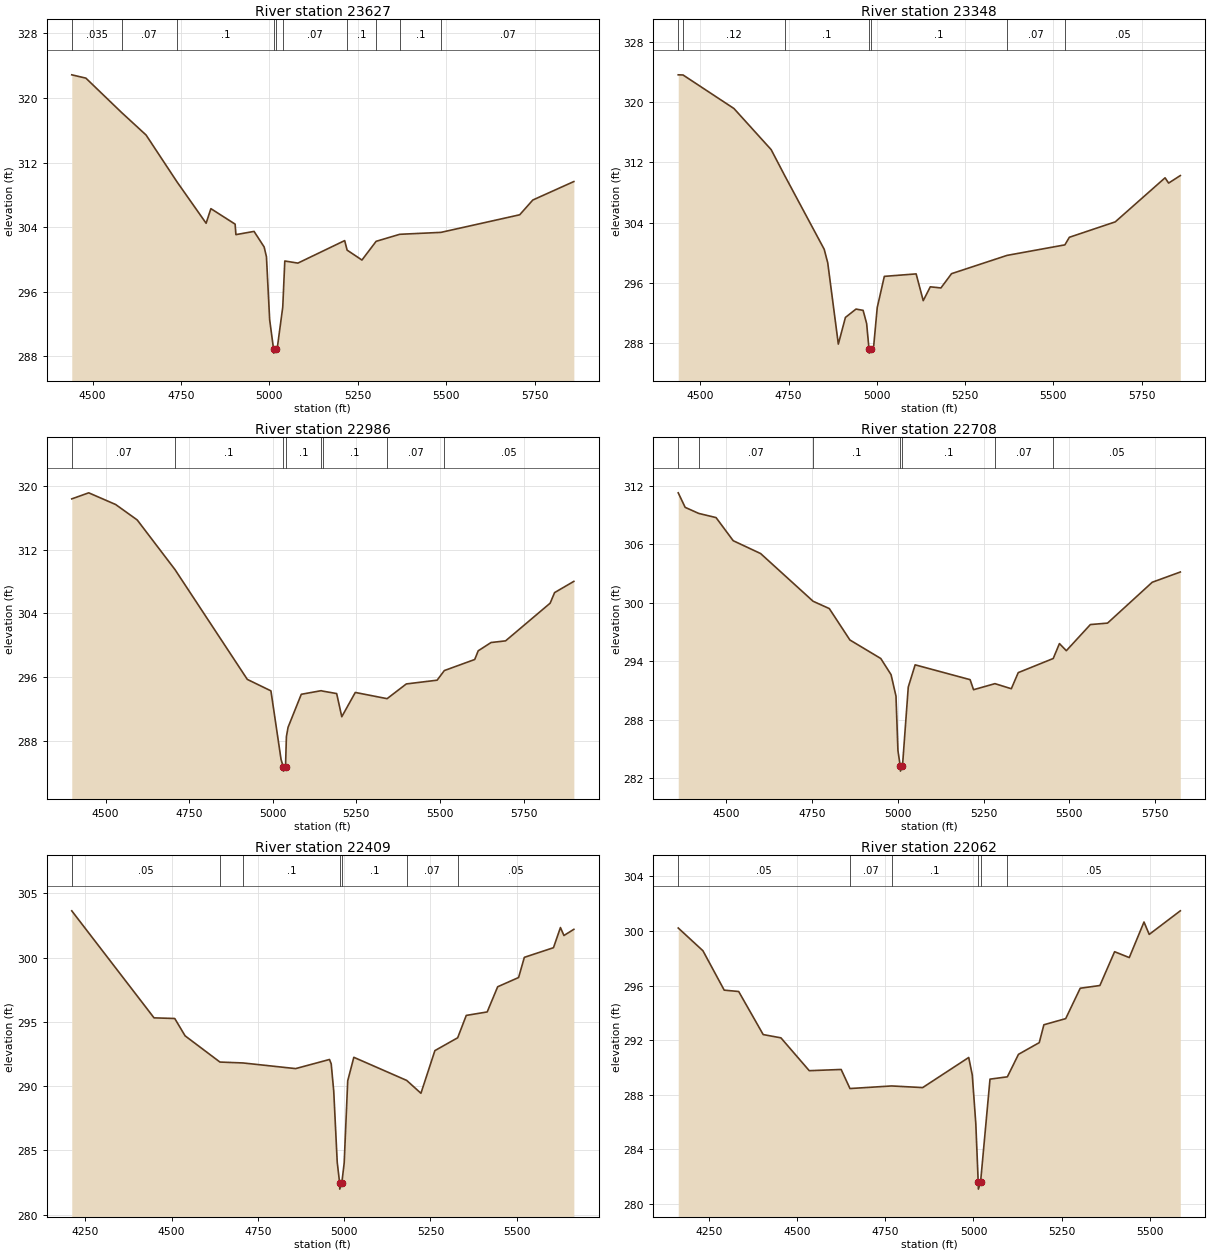
Type RM Length L Ch R = 1 ,23627   ,279,279,279
BEGIN DESCRIPTION:
A19541
END DESCRIPTION:
XS GIS Cut Line= 3
      2516743.58     13708677.72      2516908.37     13709108.96
      2517398.34     13709931.42
#Sta/Elev= 30
  4441.4  322.87  4481.3  322.46  4582.4  318.19  4651.4  315.41  4738.7  309.61
  4821.1  304.47  4834.6  306.28  4903.1  304.36  4905.3  303.06  4956.6  303.46
  4985.1  301.53  4991.6  300.32  5000.7  292.51  5011.7  288.87  5012.2  288.37
    5018  288.87  5022.1  288.97  5037.7  294.08  5039.5  295.85  5043.5  299.79
  5080.5  299.53  5212.7  302.32  5219.6  301.14  5261.5  299.91  5301.6  302.23
  5368.3   303.1  5484.8  303.34  5707.4  305.52  5744.4  307.35  5860.4  309.64
#Mann= 10 ,-1 , 0
  4441.4    .035       0  4582.4     .07       0  4738.7      .1       0
  5011.7     .05       0    5018      .1       0  5039.5     .07       0
  5219.6      .1       0  5301.6     .07       0  5368.3      .1       0
  5484.8     .07       0
Bank Sta=5011.7,5018
XS Rating Curve= 0 ,0
Exp/Cntr=0.3,0.1

Type RM Length L Ch R = 1 ,23348   ,362,362,362
BEGIN DESCRIPTION:
A19540
END DESCRIPTION:
XS GIS Cut Line= 3
      2516680.49      13708702.3      2516726.06     13709456.04
       2516810.1     13710117.81
#Sta/Elev= 30
  4437.4  323.66    4451  323.64  4595.2  319.18  4700.6  313.71  4739.3  310.23
  4850.9  300.45  4860.9  298.65  4890.9  287.84    4911  291.39    4941   292.5
  4961.1  292.33  4971.1  290.57  4977.9  287.14  4978.4  286.64  4984.3  287.14
  4991.1   287.6  5001.1   292.7  5021.2  296.85  5111.3  297.18  5131.4  293.62
  5151.4  295.46  5181.5  295.31  5211.6  297.21  5368.7  299.64  5532.6  301.04
  5545.3  302.05  5675.3   304.1  5816.4  309.96  5826.5  309.26  5859.6  310.26
#Mann= 7 ,-1 , 0
  4437.4     .07       0    4451     .12       0  4739.3      .1       0
  4977.9     .05       0  4984.3      .1       0  5368.7     .07       0
  5532.6     .05       0
Bank Sta=4977.9,4984.3
XS Rating Curve= 0 ,0
Exp/Cntr=0.3,0.1

Type RM Length L Ch R = 1 ,22986   ,278,278,278
BEGIN DESCRIPTION:
A19539
END DESCRIPTION:
XS GIS Cut Line= 3
      2516343.93     13708684.78      2516466.63     13709592.77
      2516592.85     13710164.25
#Sta/Elev= 30
    4399  318.38  4449.7  319.14  4530.4  317.67  4594.8  315.73  4707.7   309.5
    4924  295.71  4994.6  294.27  5024.9  285.66  5031.8  284.69  5032.3  284.19
  5038.2  284.69  5040.9  288.53  5045.9   289.7  5085.4  293.84  5144.6  294.29
  5150.7  294.23  5191.2  293.93  5206.5  291.02  5246.9  294.07    5342  293.29
  5399.5  295.14  5491.6  295.61  5513.2  296.82  5604.1  298.21  5614.5   299.3
  5652.9  300.34  5696.4  300.55  5829.6  305.28  5842.9  306.61  5900.5  308.02
#Mann= 8 ,-1 , 0
    4399     .07       0  4707.7      .1       0  5031.8     .05       0
  5038.2      .1       0  5144.6     .07       0  5150.7      .1       0
    5342     .07       0  5513.2     .05       0
Bank Sta=5031.8,5038.2
XS Rating Curve= 0 ,0
Exp/Cntr=0.3,0.1

Type RM Length L Ch R = 1 ,22708   ,299,299,299
BEGIN DESCRIPTION:
A19538
END DESCRIPTION:
XS GIS Cut Line= 3
      2516158.12     13708684.79      2516161.62     13709319.32
      2516203.69     13710146.71
#Sta/Elev= 30
  4360.2  311.28  4380.4  309.79  4419.8  309.17  4470.4  308.74  4520.4  306.37
  4600.4  305.05  4753.2  300.16  4800.4  299.41  4860.4  296.19  4950.4  294.29
  4980.4  292.63  4994.7  290.43  5000.4  284.85  5007.2  283.24  5007.7  282.74
  5013.6  283.24  5030.5  291.36  5050.5  293.64  5210.7  292.12  5220.7  291.09
  5283.1  291.71  5330.8  291.19  5350.9  292.84  5452.9  294.29    5471  295.82
  5491.1  295.09  5561.1  297.77  5611.2  297.92  5741.4  302.11  5823.2  303.16
#Mann= 7 ,-1 , 0
  4360.2     .05       0  4419.8     .07       0  4753.2      .1       0
  5007.2     .05       0  5013.6      .1       0  5283.1     .07       0
  5452.9     .05       0
Bank Sta=5007.2,5013.6
XS Rating Curve= 0 ,0
Exp/Cntr=0.3,0.1

Type RM Length L Ch R = 1 ,22409   ,347,347,347
BEGIN DESCRIPTION:
A19537
END DESCRIPTION:
XS GIS Cut Line= 3
      2515881.15     13708656.74      2515895.18      13709371.9
      2516000.18      13710103.4
#Sta/Elev= 30
  4211.1  303.65  4449.4  295.32  4509.4  295.27  4539.4  293.92  4640.3  291.88
  4707.1  291.81  4859.5  291.37  4957.6  292.08  4962.6  291.74  4969.9  289.62
    4980  284.09  4986.9  282.49  4987.4  281.99  4993.4  282.49  5000.2  284.04
  5010.4  290.42  5028.1  292.25  5181.3  290.45  5222.5  289.45  5262.9  292.77
  5328.9  293.77  5353.8  295.51  5414.4  295.78  5444.8  297.74  5505.4  298.46
    5522  300.03  5606.4  300.78  5626.6  302.35  5636.7  301.73  5665.4  302.21
#Mann= 7 ,-1 , 0
  4211.1     .05       0  4640.3     .07       0  4707.1      .1       0
  4986.9     .05       0  4993.4      .1       0  5181.3     .07       0
  5328.9     .05       0
Bank Sta=4986.9,4993.4
XS Rating Curve= 0 ,0
Exp/Cntr=0.3,0.1

Type RM Length L Ch R = 1 ,22062   ,387,387,387
BEGIN DESCRIPTION:
A19536
END DESCRIPTION:
XS GIS Cut Line= 3
      2515544.59     13708695.27      2515632.24     13709641.85
      2515744.28     13710100.54
#Sta/Elev= 30
  4163.4  300.22  4233.4  298.55  4293.7  295.66  4334.7  295.56  4404.2   292.4
  4454.4  292.16  4534.7  289.75  4625.1  289.84  4650.1  288.44    4768  288.63
  4856.1  288.51  4986.6  290.72  4996.7  289.43  5006.7  285.85  5013.5  281.56
    5014  281.06  5020.1  281.56  5046.9  289.13  5096.1   289.3  5127.6  290.95
  5186.5  291.81  5199.6  293.12  5261.4  293.57  5302.6   295.8  5358.3     296
    5400  298.48  5441.6  298.05  5483.3  300.66  5498.1  299.75  5586.2  301.48
#Mann= 6 ,-1 , 0
  4163.4     .05       0  4650.1     .07       0    4768      .1       0
  5013.5     .05       0  5020.1      .1       0  5096.1     .05       0
Bank Sta=5013.5,5020.1
XS Rating Curve= 0 ,0
Exp/Cntr=0.3,0.1

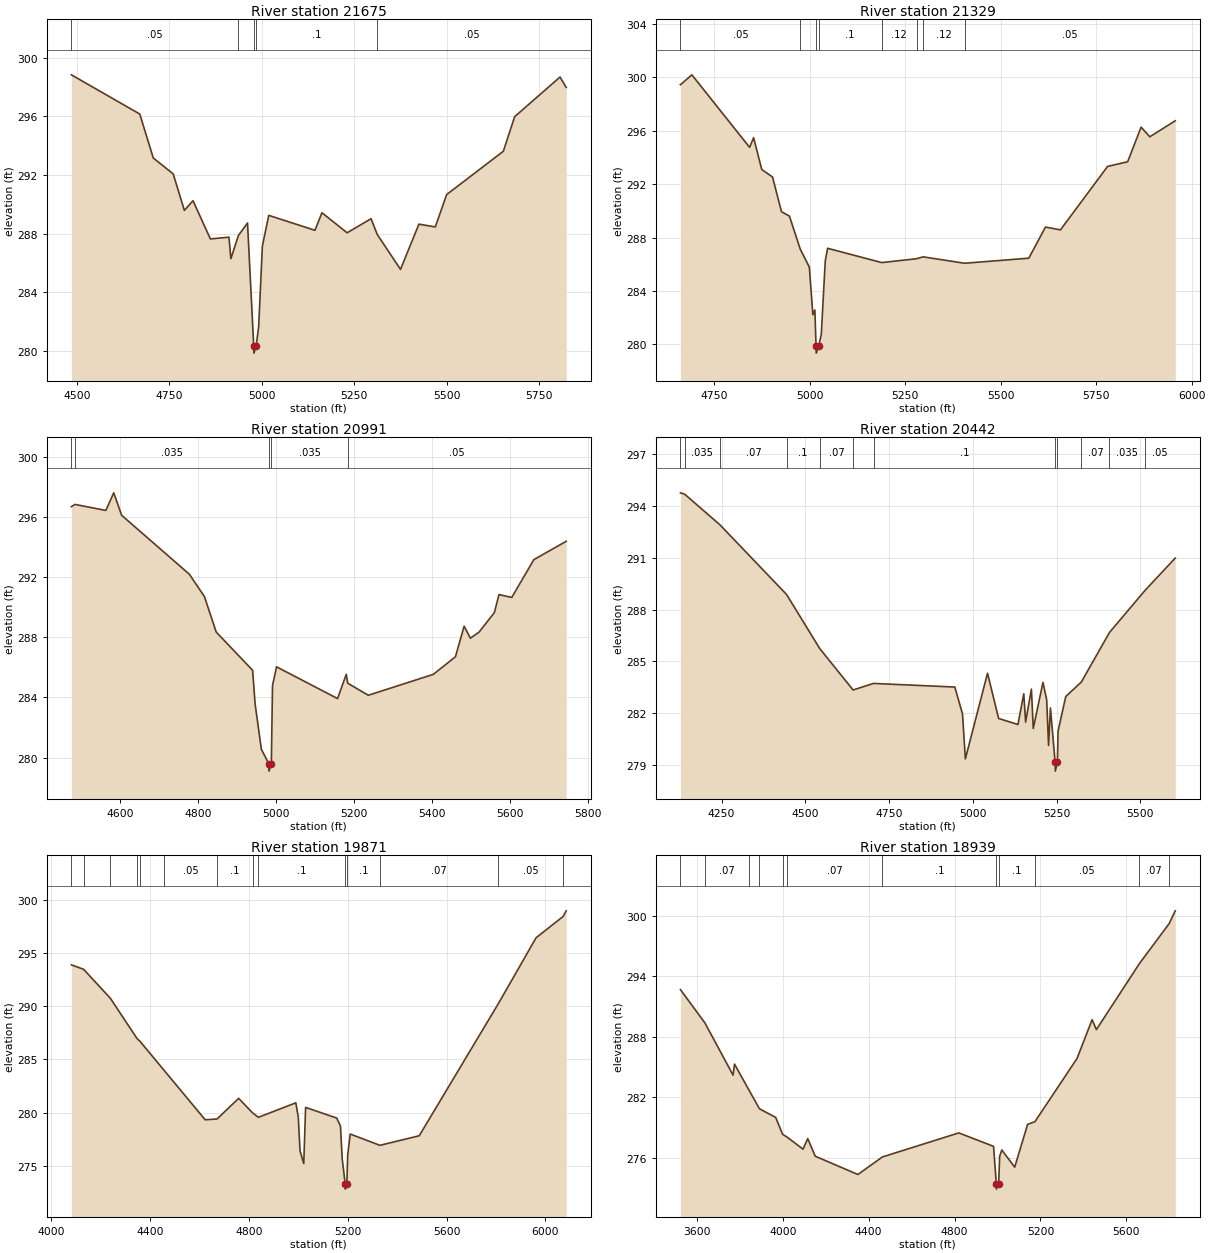
Type RM Length L Ch R = 1 ,21675   ,346,346,346
BEGIN DESCRIPTION:
A19535
END DESCRIPTION:
XS GIS Cut Line= 3
      2515288.66     13708810.96      2515351.77     13709466.56
      2515491.73     13710131.36
#Sta/Elev= 30
    4485  298.84  4669.9  296.16  4706.4  293.16  4760.3  292.07  4790.4  289.58
  4813.8  290.24  4860.8  287.63    4911  287.75  4916.2  286.28  4936.7  287.87
  4961.2  288.72    4978  280.33  4978.5  279.83  4984.6  280.33  4991.4  281.64
  5001.4  287.14  5018.6  289.24  5143.6  288.22  5162.5  289.42  5230.5  288.05
  5295.3  289.01  5312.1  287.93  5374.9  285.55  5424.7  288.64    5469  288.45
  5499.7  290.66    5653  293.62  5683.6  295.98  5806.3  298.69    5823  297.98
#Mann= 5 ,-1 , 0
    4485     .05       0  4936.7      .1       0    4978     .05       0
  4984.6      .1       0  5312.1     .05       0
Bank Sta=4978,4984.6
XS Rating Curve= 0 ,0
Exp/Cntr=0.3,0.1

Type RM Length L Ch R = 1 ,21329   ,338,338,338
BEGIN DESCRIPTION:
A19534
END DESCRIPTION:
XS GIS Cut Line= 3
       2514941.6     13708951.24      2515050.27     13709322.82
      2515407.85     13710157.18
#Sta/Elev= 30
  4662.2  299.45  4692.1  300.19  4843.2  294.76  4853.7  295.48    4875   293.1
  4903.2  292.54  4926.6  289.94  4947.4  289.61  4975.6  287.15  4999.5  285.79
  5008.8  282.22    5014  282.58  5017.1  279.85  5017.6  279.35  5023.7  279.85
  5030.8  280.75  5041.2  286.26  5047.4   287.2  5188.9  286.13  5280.4  286.42
  5297.3  286.56  5405.8  286.08  5573.9  286.46  5617.5  288.79  5656.7  288.58
    5780  293.33  5832.6  293.68  5867.7  296.27  5890.6  295.55  5957.1  296.75
#Mann= 8 ,-1 , 0
  4662.2     .05       0  4975.6      .1       0  5017.1     .05       0
  5023.7      .1       0  5188.9     .12       0  5280.4      .1       0
  5297.3     .12       0  5405.8     .05       0
Bank Sta=5017.1,5023.7
XS Rating Curve= 0 ,0
Exp/Cntr=0.3,0.1

Type RM Length L Ch R = 1 ,20991   ,549,549,549
BEGIN DESCRIPTION:
A19533
END DESCRIPTION:
XS GIS Cut Line= 3
      2514734.45     13709037.61      2514792.22     13709413.09
      2515190.32     13710209.31
#Sta/Elev= 30
  4474.6  296.67  4483.9  296.82    4563  296.42  4583.3  297.59  4603.5   296.1
  4777.4  292.18    4816   290.7  4846.3  288.34  4939.7   285.8  4946.1  283.58
  4962.1  280.56  4981.1   279.6  4981.6   279.1  4987.8   279.6  4990.8  284.78
  5001.2  286.03  5157.8  283.92  5180.1  285.53  5183.9  284.94  5236.8  284.14
  5403.7  285.53  5460.4   286.7  5482.7  288.73  5498.8  287.93  5521.1  288.34
  5560.2  289.63  5572.2  290.83    5605  290.64  5661.6  293.15  5744.7  294.37
#Mann= 5 ,-1 , 0
  4474.6     .12       0  4483.9    .035       0  4981.1    .035       0
  4987.8    .035       0  5183.9     .05       0
Bank Sta=4981.1,4987.8
XS Rating Curve= 0 ,0
Exp/Cntr=0.3,0.1

Type RM Length L Ch R = 1 ,20442   ,571,571,571
BEGIN DESCRIPTION:
A19532
END DESCRIPTION:
XS GIS Cut Line= 4
      2514665.13     13709026.02      2514549.59      13709736.6
      2514751.78     13710169.86      2515005.93     13710285.38
#Sta/Elev= 30
  4127.3  294.77    4140  294.69  4245.6  292.91  4444.2  288.88  4543.5  285.74
  4642.8  283.35  4703.8  283.73  4946.5  283.52  4969.4  281.96  4977.9  279.36
  5044.1  284.32  5077.2   281.7  5134.9  281.35  5152.3  283.13  5157.8  281.49
  5175.1   283.4  5180.6  281.12  5209.6  283.79  5220.6  282.79  5226.3  280.14
  5231.9  282.31  5245.9  279.15  5246.4  278.65  5252.6  279.15  5254.7  280.97
  5277.6  282.97  5324.1  283.81  5408.1  286.68  5514.8  289.13  5604.5  290.99
#Mann= 12 ,-1 , 0
  4127.3     .12       0    4140    .035       0  4245.6     .07       0
  4444.2      .1       0  4543.5     .07       0  4642.8     .05       0
  4703.8      .1       0  5245.9     .05       0  5252.6      .1       0
  5324.1     .07       0  5408.1    .035       0  5514.8     .05       0
Bank Sta=5245.9,5252.6
XS Rating Curve= 0 ,0
Exp/Cntr=0.3,0.1

Type RM Length L Ch R = 1 ,19871   ,932,932,932
BEGIN DESCRIPTION:
KOKERNOT BRANCH 23.0
END DESCRIPTION:
XS GIS Cut Line= 3
      2514584.25     13708898.96      2514029.67     13710042.77
      2513851.02     13710751.64
#Sta/Elev= 30
  4081.8  293.87  4131.3  293.45  4239.2  290.74  4347.2  286.96  4359.5  286.69
  4455.1  284.02  4623.1  279.33    4671   279.4  4758.6  281.34  4815.2  279.97
  4838.6  279.56  4989.9  280.92  4999.8  279.59  5006.9  276.41    5022  275.22
  5029.5  280.49  5155.4  279.49  5170.5  278.74  5177.6  275.66  5189.7  273.32
  5190.2  272.82  5196.4  273.32  5199.9  276.05  5210.1  277.99  5330.1  276.93
  5489.3  277.83  5809.7  290.24    5962  296.41  6070.9   298.4    6084  298.94
#Mann= 14 ,-1 , 0
  4081.8    .035       0  4131.3     .05       0  4239.2     .07       0
  4347.2     .05       0  4359.5     .07       0  4455.1     .05       0
    4671      .1       0  4815.2     .05       0  4838.6      .1       0
  5189.7     .05       0  5196.4      .1       0  5330.1     .07       0
  5809.7     .05       0  6070.9     .07       0
Bank Sta=5189.7,5196.4
XS Rating Curve= 0 ,0
Exp/Cntr=0.3,0.1

Type RM Length L Ch R = 1 ,18939   ,501,501,501
BEGIN DESCRIPTION:
A19531
END DESCRIPTION:
XS GIS Cut Line= 3
      2514480.24     13708754.57      2513659.95     13709701.94
      2513608.04     13710751.71
#Sta/Elev= 30
  3523.5  292.67  3637.3  289.38  3768.5   284.2  3775.4  285.29  3843.9  282.67
  3891.6  280.86    3967  280.01  3999.3  278.33  4018.7  278.08  4094.3  276.86
  4116.2  277.91  4151.3  276.16  4349.8  274.35    4464  276.09  4819.8  278.47
  4981.6  277.14  4994.5   273.4    4995   272.9  5005.4   273.4    5010  276.15
    5020  276.78  5080.1  275.08  5140.2  279.32  5174.2  279.58  5370.4  285.85
  5440.5  289.69  5460.5  288.71  5661.1  295.26  5799.2  299.21  5827.7  300.48
#Mann= 12 ,-1 , 0
  3523.5    .035       0  3637.3     .07       0  3843.9    .035       0
  3891.6     .07       0  3999.3     .05       0  4018.7     .07       0
    4464      .1       0  4994.5     .05       0  5005.4      .1       0
  5174.2     .05       0  5661.1     .07       0  5799.2     .05       0
Bank Sta=4994.5,5005.4
XS Rating Curve= 0 ,0
Exp/Cntr=0.3,0.1

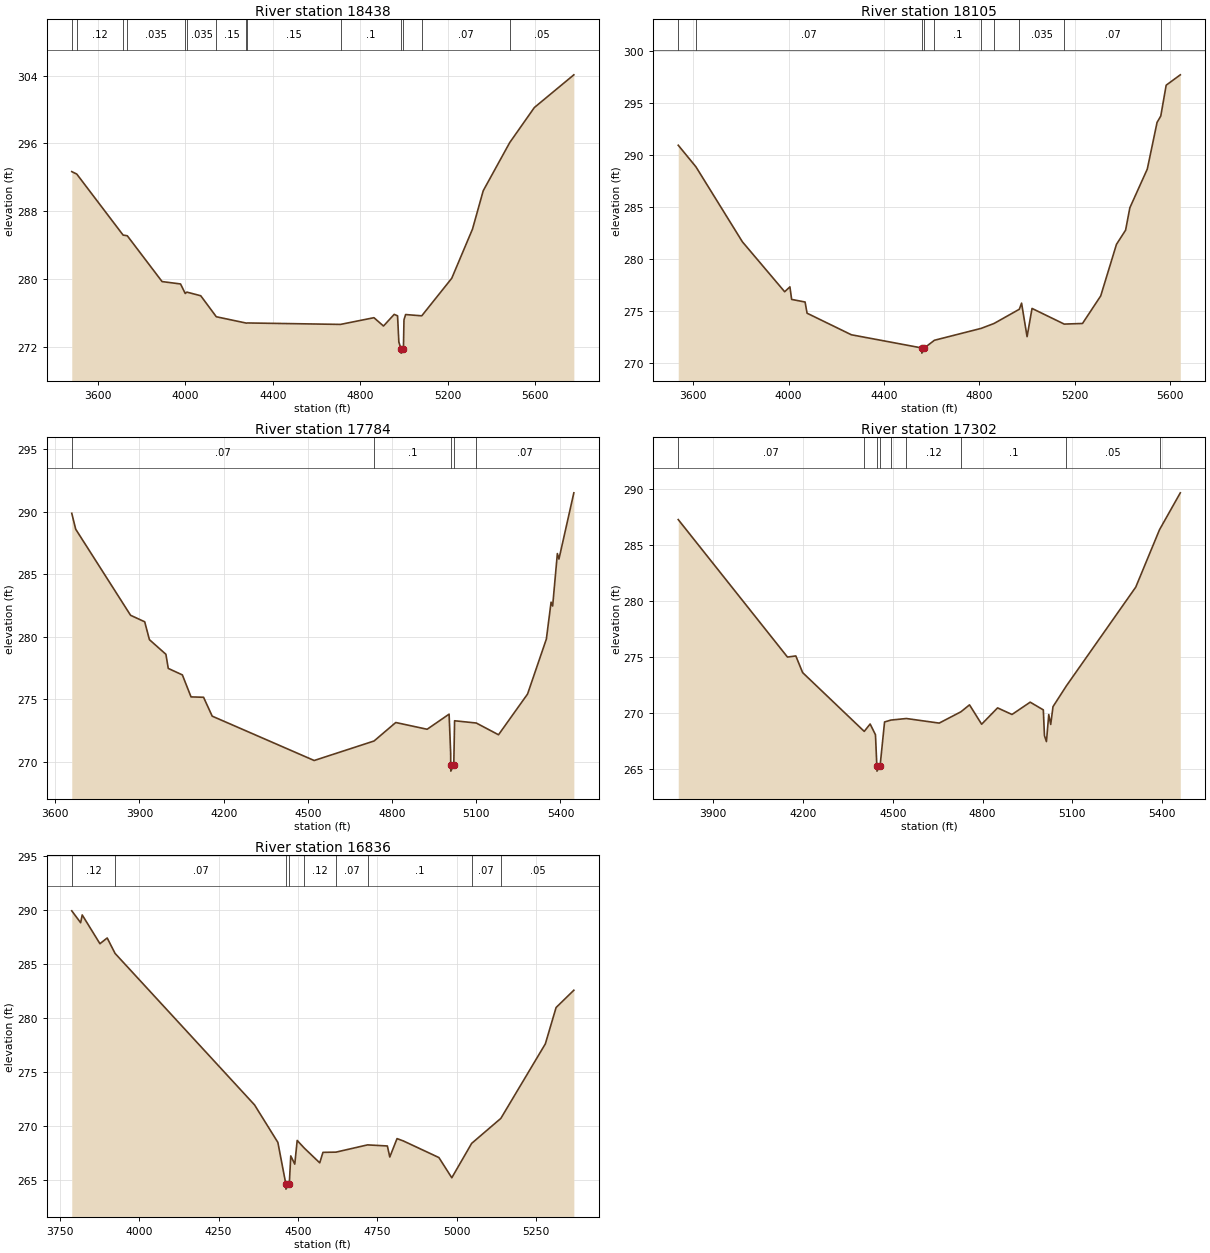
Type RM Length L Ch R = 1 ,18438   ,333,333,333
BEGIN DESCRIPTION:
KOKERNOT BRANCH 22.0
END DESCRIPTION:
XS GIS Cut Line= 3
      2514462.96     13708679.41      2513411.55     13709632.61
      2512660.52     13710089.01
#Sta/Elev= 30
  3479.6  292.69  3502.6   292.4  3714.6  285.22  3733.8  285.14  3892.9  279.75
  3977.4  279.47    3999  278.35  4006.5  278.51    4070  278.08  4141.2  275.61
  4279.2  274.86  4283.4  274.88  4709.9  274.71  4862.7   275.5  4906.4  274.52
  4955.3  275.89  4970.8  275.72  4976.6  272.64  4986.6  271.83  4987.1  271.33
  4997.6  271.83  5000.1  275.24  5007.6  275.87  5081.5  275.72  5218.8  280.14
  5313.8  285.93  5362.8  290.44  5484.2  296.11  5596.8  300.23  5777.6  304.08
#Mann= 14 ,-1 , 0
  3479.6    .035       0  3502.6     .12       0  3714.6     .07       0
  3733.8    .035       0    3999     .05       0  4006.5    .035       0
  4141.2     .15       0  4279.2    .035       0  4283.4     .15       0
  4709.9      .1       0  4986.6     .05       0  4997.6      .1       0
  5081.5     .07       0  5484.2     .05       0
Bank Sta=4986.6,4997.6
XS Rating Curve= 0 ,0
Exp/Cntr=0.3,0.1

Type RM Length L Ch R = 1 ,18105   ,321,321,321
BEGIN DESCRIPTION:
KOKERNOT BRANCH 21.0
END DESCRIPTION:
XS GIS Cut Line= 3
      2514341.62     13708546.56       2513099.6     13709465.09
      2512562.39     13709626.83
#Sta/Elev= 30
  3537.5  290.96  3611.7  288.88  3806.5  281.65  3983.9  276.83  4005.9   277.3
  4013.2  276.09  4069.5  275.84  4077.9  274.76  4263.7  272.68  4558.8  271.41
  4559.3  270.91  4569.8  271.41    4612  272.15  4808.5   273.3  4862.1  273.77
    4968  275.14  4977.5  275.73  5000.6   272.5  5021.4  275.22  5156.5  273.71
  5233.1  273.77  5309.5  276.43  5375.5   281.4  5413.8  282.77  5431.7  284.93
  5504.8  288.66  5545.8  293.16  5561.4  293.78    5584  296.75  5643.3  297.75
#Mann= 10 ,-1 , 0
  3537.5     .12       0  3611.7     .07       0  4558.8    .035       0
  4569.8     .07       0    4612      .1       0  4808.5    .035       0
  4862.1      .1       0    4968    .035       0  5156.5     .07       0
  5561.4     .05       0
Bank Sta=4558.8,4569.8
XS Rating Curve= 0 ,0
Exp/Cntr=0.3,0.1

Type RM Length L Ch R = 1 ,17784   ,482,482,482
BEGIN DESCRIPTION:
KOKERNOT BRANCH 20.0
END DESCRIPTION:
XS GIS Cut Line= 3
      2514275.01       13708525.        2513075.       13709125.
      2512674.97     13709325.02
#Sta/Elev= 30
  3658.8  289.87  3672.8   288.6  3868.4  281.71  3918.7  281.19  3935.5  279.76
  3994.2  278.59  4002.6  277.46  4052.9  276.94  4083.7  275.18  4128.4  275.15
  4159.1  273.64  4522.5  270.09  4735.8  271.65  4813.2  273.13    4925  272.59
  5003.2   273.8  5008.8   270.7  5008.9  269.74  5009.4  269.24  5019.9  269.74
  5022.8  273.27    5100  273.09  5179.3  272.15  5282.8  275.41  5349.8  279.81
  5366.6  282.76  5372.2  282.45    5389  286.65  5394.6  286.21  5447.7  291.51
#Mann= 5 ,-1 , 0
  3658.8     .07       0  4735.8      .1       0  5008.9     .05       0
  5019.9      .1       0    5100     .07       0
Bank Sta=5008.9,5019.9
XS Rating Curve= 0 ,0
Exp/Cntr=0.3,0.1

Type RM Length L Ch R = 1 ,17302   ,466,466,466
BEGIN DESCRIPTION:
KOKERNOT BRANCH 19.0
END DESCRIPTION:
XS GIS Cut Line= 3
      2514175.02       13708475.        2512975.       13708675.
      2512624.96     13708975.03
#Sta/Elev= 30
  3783.3  287.31  4148.3  275.03  4176.2  275.13    4199  273.64  4404.8  268.39
  4424.5  269.05  4442.3  268.09  4446.9  265.34  4447.4  264.84  4457.9  265.34
  4472.7  269.23    4494   269.4  4545.4  269.54  4655.2  269.13  4727.8  270.14
  4756.6  270.76  4797.1  269.03  4850.3  270.49  4898.5   269.9  4959.3     271
  5003.2  270.31    5007     268  5013.6  267.48  5021.3  269.89  5027.9  269.01
  5035.5   270.6  5080.6  272.47  5312.1  281.28  5391.5  286.41  5460.9   289.7
#Mann= 9 ,-1 , 0
  3783.3     .07       0  4404.8     .12       0  4446.9     .05       0
  4457.9     .12       0    4494     .07       0  4545.4     .12       0
  4727.8      .1       0  5080.6     .05       0  5391.5     .07       0
Bank Sta=4446.9,4457.9
XS Rating Curve= 0 ,0
Exp/Cntr=0.3,0.1

Type RM Length L Ch R = 1 ,16836   ,456,456,456
BEGIN DESCRIPTION:
KOKERNOT BRANCH 18.0
END DESCRIPTION:
XS GIS Cut Line= 3
      2514224.99       13708425.        2513025.       13708225.
      2512675.04     13708125.01
#Sta/Elev= 30
  3787.9   289.9  3815.8   288.8  3820.8  289.52  3876.6  286.86  3899.4  287.39
  3924.3  285.96  4363.2  271.96  4436.7  268.49  4461.6  264.67  4462.1  264.17
  4472.7  264.67  4477.3  267.24  4489.9  266.48  4497.5  268.67  4520.3  267.95
  4568.5   266.6  4578.6  267.57  4619.6  267.59    4719  268.26  4781.4  268.16
    4789  267.14  4811.8  268.84  4832.1  268.62  4943.6  267.09  4984.2  265.22
  5046.7   268.4  5138.6  270.71  5278.7   277.6  5312.5  280.96  5368.4  282.56
#Mann= 9 ,-1 , 0
  3787.9     .12       0  3924.3     .07       0  4461.6     .05       0
  4472.7     .07       0  4520.3     .12       0  4619.6     .07       0
    4719      .1       0  5046.7     .07       0  5138.6     .05       0
Bank Sta=4461.6,4472.7
XS Rating Curve= 0 ,0
Exp/Cntr=0.3,0.1