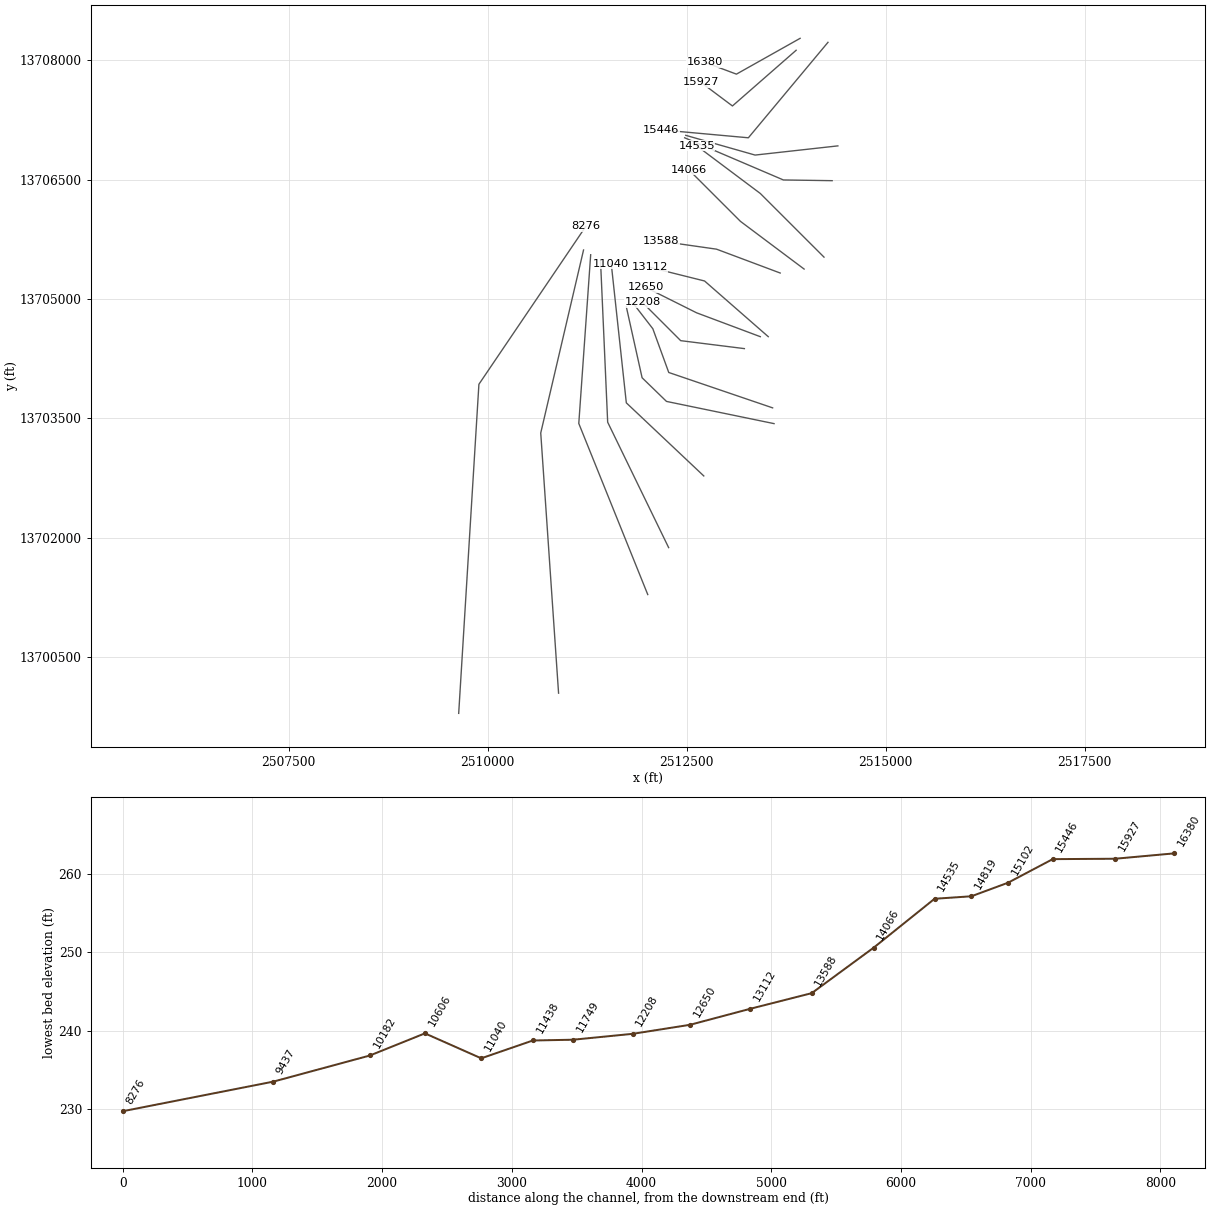
HEC-RAS study KOKERNOT BRANCH.prj: KOKERNOT BRANCH Base Level Engineering

--- KOKERNOT BRANCH.g01 (geometry) --- (continued)

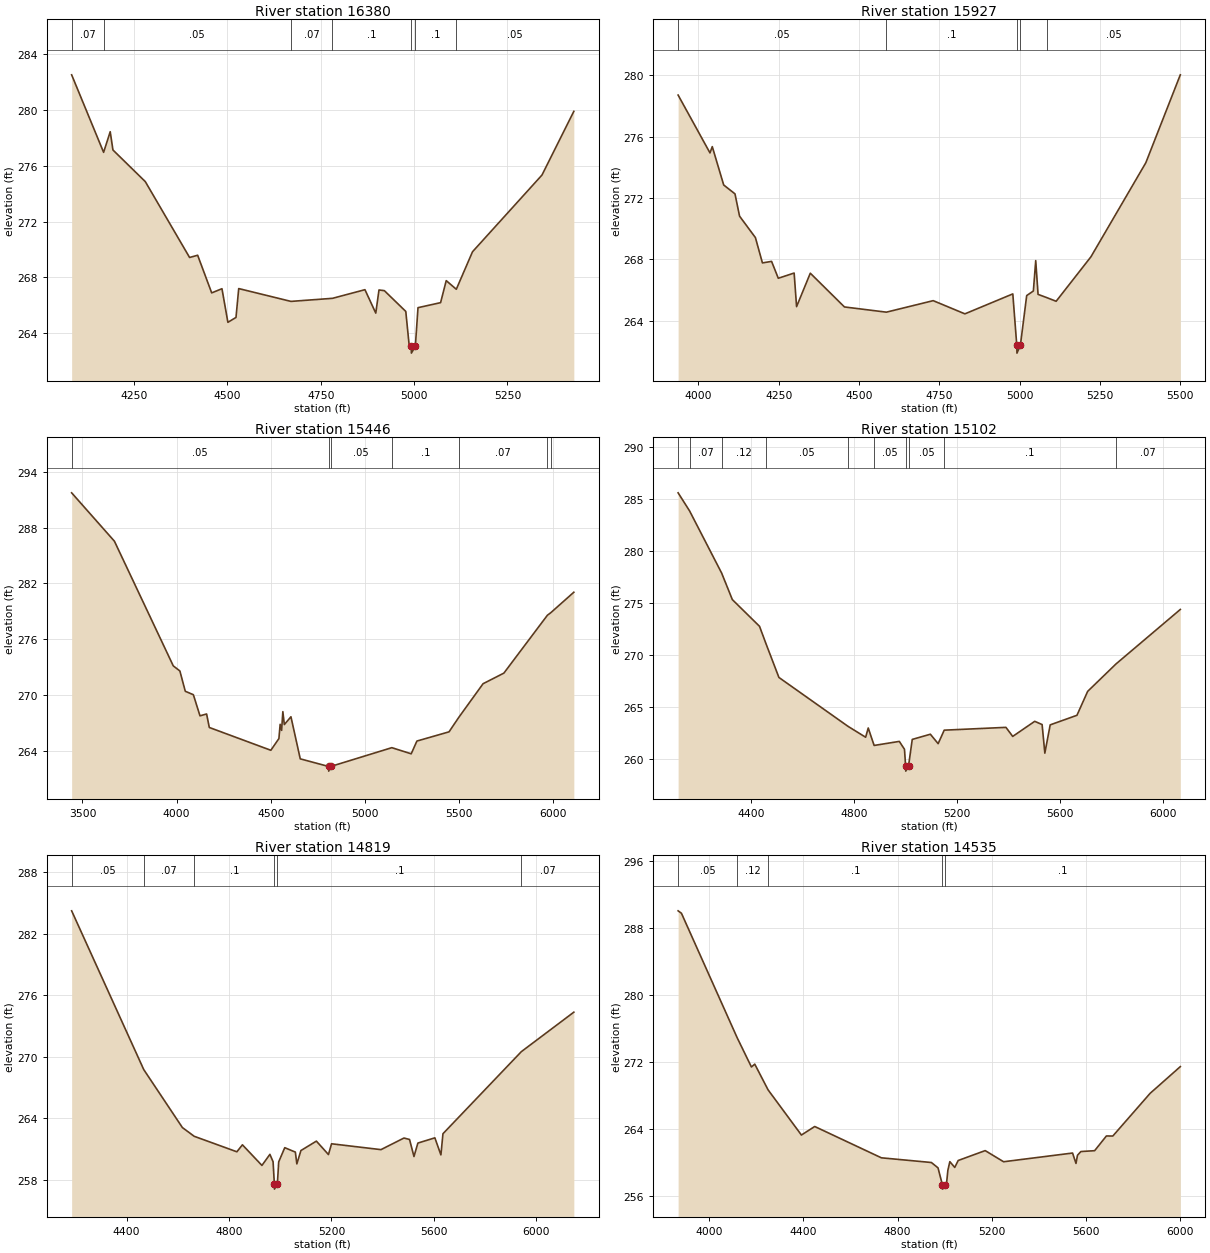
Type RM Length L Ch R = 1 ,16380   ,453,453,453
BEGIN DESCRIPTION:
KOKERNOT BRANCH 17.0
END DESCRIPTION:
XS GIS Cut Line= 3
      2513925.02     13708275.01        2513125.       13707825.
      2512725.01       13707975.
#Sta/Elev= 30
  4082.6  282.53  4168.2  276.97  4185.9  278.45  4193.2  277.14  4279.9  274.87
  4398.5  269.43  4420.1  269.59  4457.7  266.89  4485.2  267.19  4501.1  264.78
  4522.8  265.13  4530.1   267.2    4670  266.28  4781.2   266.5  4868.2  267.12
  4897.2  265.44  4905.8   267.1  4920.2  267.05  4977.6  265.56  4986.8  263.09
  4992.1  263.07  4992.6  262.57  5003.2  263.07  5010.3  265.83  5070.8  266.19
  5085.9  267.77  5112.9  267.15  5156.3  269.84  5342.3  275.34  5427.7  279.91
#Mann= 7 ,-1 , 0
  4082.6     .07       0  4168.2     .05       0    4670     .07       0
  4781.2      .1       0  4992.1     .05       0  5003.2      .1       0
  5112.9     .05       0
Bank Sta=4992.1,5003.2
XS Rating Curve= 0 ,0
Exp/Cntr=0.3,0.1

Type RM Length L Ch R = 1 ,15927   ,481,481,481
BEGIN DESCRIPTION:
KOKERNOT BRANCH 16.0
END DESCRIPTION:
XS GIS Cut Line= 3
        2513875.       13708125.        2513075.       13707425.
      2512675.01     13707724.99
#Sta/Elev= 30
  3937.1  278.71  4036.3  274.94  4043.4  275.35    4079  272.85  4114.1  272.27
  4128.3  270.82  4177.7  269.42  4199.5  267.77    4228  267.87  4248.9  266.77
  4298.2  267.11  4305.8  264.92  4348.5   267.1  4454.8   264.9  4585.3  264.56
    4731  265.31  4829.7  264.45  4978.8  265.75  4991.2  262.39  4991.7  261.89
  5002.3  262.39    5022  265.64  5042.8  265.94  5050.1  267.92  5057.4  265.72
  5084.3  265.51  5113.7  265.27    5222  268.17  5392.8   274.3  5500.1  280.03
#Mann= 5 ,-1 , 0
  3937.1     .05       0  4585.3      .1       0  4991.2     .05       0
  5002.3      .1       0  5084.3     .05       0
Bank Sta=4991.2,5002.3
XS Rating Curve= 0 ,0
Exp/Cntr=0.3,0.1

Type RM Length L Ch R = 1 ,15446   ,344,344,344
BEGIN DESCRIPTION:
KOKERNOT BRANCH 15.0
END DESCRIPTION:
XS GIS Cut Line= 3
      2514275.02     13708225.02        2513275.       13707025.
      2512175.02       13707125.
#Sta/Elev= 30
  3442.5  291.74  3669.7  286.54  3982.1  273.15  4017.2   272.6  4045.9  270.42
  4088.8  270.05    4124  267.78  4159.1  267.98  4173.4  266.53  4500.2  264.08
  4543.1  265.34  4549.6  266.87  4557.4  266.22    4564  268.23  4571.8  266.84
  4606.9  267.68  4656.4  263.16    4807  262.34  4807.5  261.84  4818.1  262.34
  5142.7  264.36  5245.6   263.7  5275.7  265.07  5446.4  266.06    5499  267.64
  5627.1  271.23  5737.6  272.37  5968.8  278.59  5986.1  278.85  6109.1  281.06
#Mann= 7 ,-1 , 0
  3442.5     .05       0    4807     .05       0  4818.1     .05       0
  5142.7      .1       0    5499     .07       0  5968.8      .1       0
  5986.1     .07       0
Bank Sta=4807,4818.1
XS Rating Curve= 0 ,0
Exp/Cntr=0.3,0.1

Type RM Length L Ch R = 1 ,15102   ,283,283,283
BEGIN DESCRIPTION:
A19530
END DESCRIPTION:
XS GIS Cut Line= 3
      2514399.43     13706923.27      2513359.56     13706807.73
      2512488.65     13707055.74
#Sta/Elev= 30
  4114.9  285.61  4159.7  283.86  4284.3  277.88  4325.6  275.34  4431.3  272.77
    4457  271.06  4506.7  267.85  4775.7  263.14  4843.8   262.1  4853.8  262.99
  4876.7  261.31  4974.6   261.7  4994.7  260.94  4999.1  259.34  4999.6  258.84
  5010.4  259.34  5024.9  261.89  5095.3  262.39  5125.5  261.48  5149.1  262.78
    5389  263.05  5415.4  262.18  5500.9  263.63  5529.6  263.32  5540.2  260.57
    5561  263.29    5665  264.21  5706.6  266.51  5816.8  269.15  6066.7  274.39
#Mann= 10 ,-1 , 0
  4114.9     .05       0  4159.7     .07       0  4284.3     .12       0
    4457     .05       0  4775.7     .07       0  4876.7     .05       0
  4999.1     .05       0  5010.4     .05       0  5149.1      .1       0
  5816.8     .07       0
Bank Sta=4999.1,5010.4
XS Rating Curve= 0 ,0
Exp/Cntr=0.3,0.1

Type RM Length L Ch R = 1 ,14819   ,284,284,284
BEGIN DESCRIPTION:
KOKERNOT BRANCH 14.0
END DESCRIPTION:
XS GIS Cut Line= 3
      2514327.49     13706485.93      2513714.97     13706494.94
        2512475.       13707025.
#Sta/Elev= 30
  4185.5  284.24  4467.1  268.76    4618  263.11  4664.1  262.26  4830.7  260.75
  4852.4  261.43  4928.6  259.42  4959.7   260.5  4972.1  259.78  4977.1  257.61
  4977.6  257.11  4988.8  257.61  4994.1  259.77  5017.7  261.15  5059.1  260.72
  5064.9  259.57  5080.8  260.87  5141.2  261.79  5188.4  260.48  5200.4  261.53
  5393.4  260.96  5483.2  262.09    5505  261.95  5522.3  260.29  5537.6   261.6
  5603.9  262.11  5627.5  260.45  5635.5  262.51  5941.5  270.51  6146.6  274.36
#Mann= 6 ,-1 , 0
  4185.5     .05       0  4467.1     .07       0  4664.1      .1       0
  4977.1     .05       0  4988.8      .1       0  5941.5     .07       0
Bank Sta=4977.1,4988.8
XS Rating Curve= 0 ,0
Exp/Cntr=0.3,0.1

Type RM Length L Ch R = 1 ,14535   ,469,469,469
BEGIN DESCRIPTION:
KOKERNOT BRANCH 13.0
END DESCRIPTION:
XS GIS Cut Line= 3
        2514225.       13705525.        2513425.       13706325.
      2512624.98     13706925.01
#Sta/Elev= 30
  3868.6  290.03  3882.7  289.74  4118.8   274.9  4179.7  271.38  4193.9  271.72
  4250.4  268.65  4391.9  263.25  4448.4  264.27  4731.3  260.53  4943.4  259.97
  4971.7  259.33  4990.4  257.29  4990.9  256.79  5002.5  257.29  5007.3  257.31
  5013.5  259.04  5021.9  260.07  5042.7  259.38  5057.3  260.21  5171.9  261.39
    5250  260.06  5542.7   261.1  5557.3  259.86  5563.5  260.83  5578.1  261.28
  5636.4  261.38  5686.4  263.14  5713.5  263.13  5871.9  268.23    6000  271.42
#Mann= 5 ,-1 , 0
  3868.6     .05       0  4118.8     .12       0  4250.4      .1       0
  4990.4     .05       0  5002.5      .1       0
Bank Sta=4990.4,5002.5
XS Rating Curve= 0 ,0
Exp/Cntr=0.3,0.1

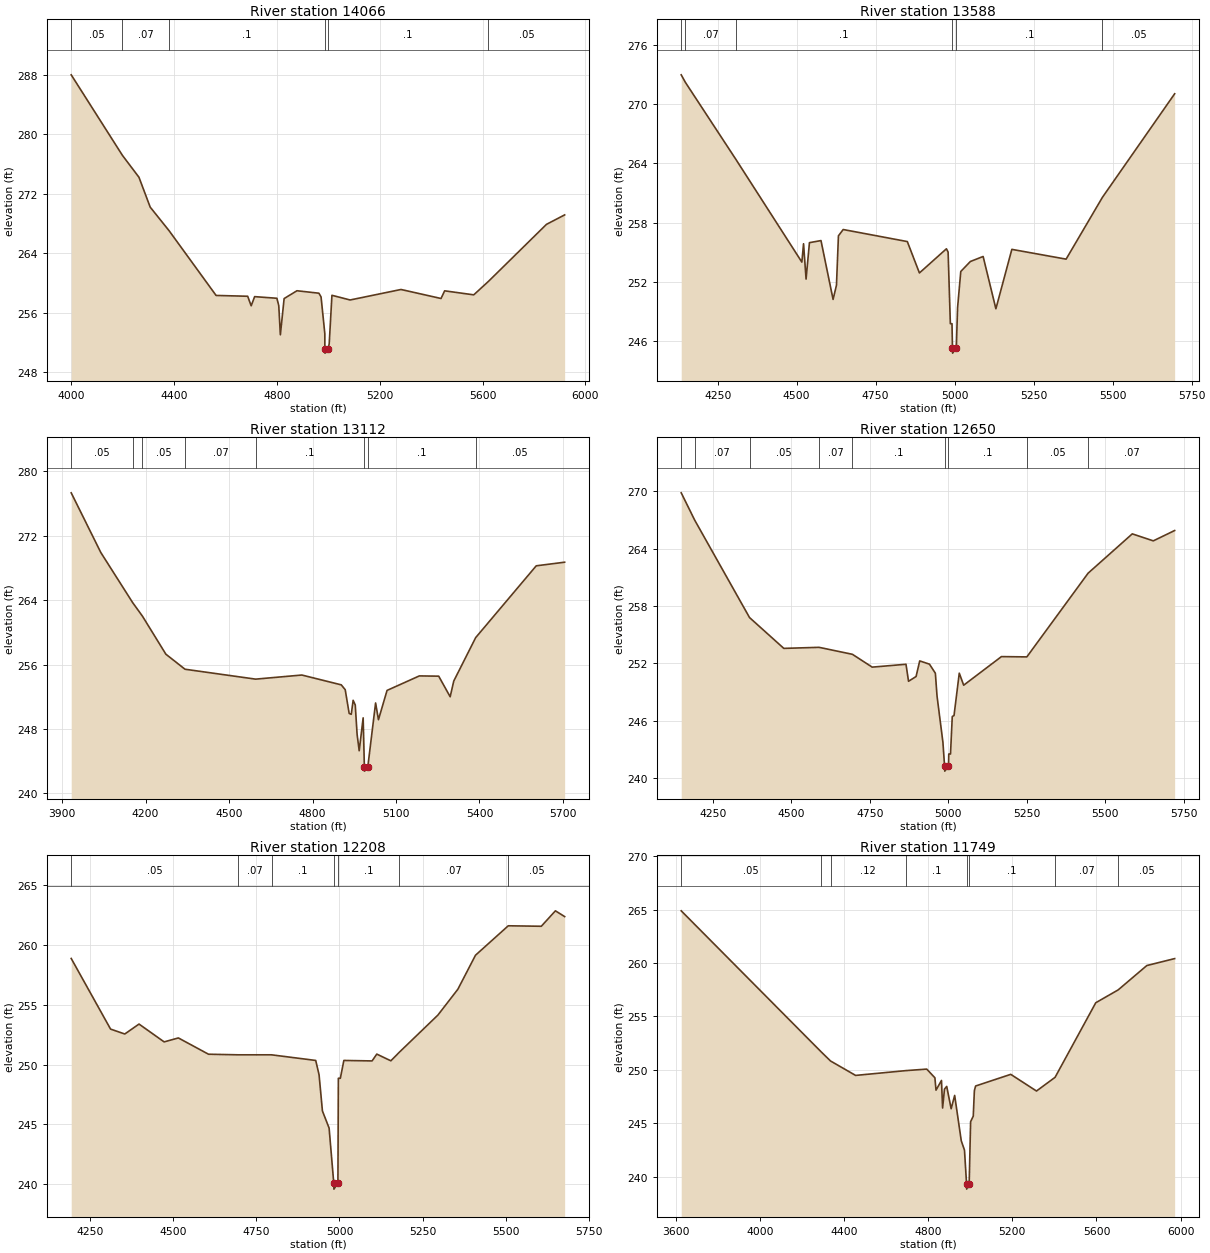
Type RM Length L Ch R = 1 ,14066   ,478,478,478
BEGIN DESCRIPTION:
KOKERNOT BRANCH 12.0
END DESCRIPTION:
XS GIS Cut Line= 3
      2513974.98     13705375.02        2513175.       13705975.
      2512525.01     13706624.99
#Sta/Elev= 30
  3999.8  287.96  4199.2  277.13  4263.3   274.2  4307.1  270.18  4381.1  266.99
  4563.3  258.32  4686.2  258.21  4699.8  256.93  4713.3  258.16  4799.8  257.94
  4807.1  256.95  4813.3  253.03  4827.9   257.9  4877.9  258.95  4963.3  258.62
  4971.6  258.12  4986.2   253.2  4986.4  251.07  4986.9  250.57  4998.5  251.07
  5003.3  251.83  5013.9  258.34  5084.6  257.71  5282.6  259.12  5438.2  257.91
  5452.3  258.94  5565.5   258.4  5622.7  260.21  5848.3  267.87    5919  269.14
#Mann= 6 ,-1 , 0
  3999.8     .05       0  4199.2     .07       0  4381.1      .1       0
  4986.4     .05       0  4998.5      .1       0  5622.7     .05       0
Bank Sta=4986.4,4998.5
XS Rating Curve= 0 ,0
Exp/Cntr=0.3,0.1

Type RM Length L Ch R = 1 ,13588   ,476,476,476
BEGIN DESCRIPTION:
KOKERNOT BRANCH 11.0
END DESCRIPTION:
XS GIS Cut Line= 3
      2513674.99     13705325.01        2512875.       13705625.
      2512174.99       13705725.
#Sta/Elev= 30
  4134.7  272.96  4147.8   272.2  4307.4  264.41  4516.5  253.99  4521.8  255.85
  4529.8  252.27  4540.5  255.96    4577  256.17  4615.3  250.21    4626  251.65
  4632.2  256.65  4647.3  257.29  4850.2  256.07  4888.5  252.89    4974  255.34
  4979.3     255  4986.4  247.75  4991.6  247.75  4993.1  245.27  4993.6  244.77
  5005.2  245.27  5009.3  249.39  5019.4  253.04  5049.7  254.05  5090.1  254.56
  5130.5  249.26    5181  255.28  5352.7  254.29  5467.8  260.56  5696.2  271.04
#Mann= 6 ,-1 , 0
  4134.7     .05       0  4147.8     .07       0  4307.4      .1       0
  4993.1     .05       0  5005.2      .1       0  5467.8     .05       0
Bank Sta=4993.1,5005.2
XS Rating Curve= 0 ,0
Exp/Cntr=0.3,0.1

Type RM Length L Ch R = 1 ,13112   ,462,462,462
BEGIN DESCRIPTION:
KOKERNOT BRANCH 10.0
END DESCRIPTION:
XS GIS Cut Line= 4
      2513524.98     13704525.01        2512725.       13705225.
        2512325.       13705325.       2512035.9     13705397.27
#Sta/Elev= 30
  3932.8  277.35  4039.1  269.94  4153.6  263.71  4188.9  262.02    4273   257.3
  4341.8  255.43  4595.6   254.2  4761.8  254.71  4903.3  253.49  4917.5  252.89
  4931.7  249.94  4939.3  249.83    4946  251.57  4953.6  250.99  4960.2  247.35
  4967.8   245.3    4982  249.39  4986.4  243.27  4986.9  242.77  4998.6  243.27
  5026.7  251.24    5037  249.16  5067.9   252.8  5183.9   254.6  5253.5  254.57
  5294.7  252.01  5307.6  253.96  5386.4  259.36    5604  268.28  5706.1  268.73
#Mann= 8 ,-1 , 0
  3932.8     .05       0  4153.6     .07       0  4188.9     .05       0
  4341.8     .07       0  4595.6      .1       0  4986.4     .05       0
  4998.6      .1       0  5386.4     .05       0
Bank Sta=4986.4,4998.6
XS Rating Curve= 0 ,0
Exp/Cntr=0.3,0.1

Type RM Length L Ch R = 1 ,12650   ,442,442,442
BEGIN DESCRIPTION:
KOKERNOT BRANCH 9.0
END DESCRIPTION:
XS GIS Cut Line= 4
      2513424.99       13704525.        2512625.       13704825.
        2512225.       13705025.      2511984.31     13705145.34
#Sta/Elev= 30
  4149.8  269.83  4192.8  266.97  4367.3  256.79  4476.4  253.57  4588.6  253.68
  4694.8  252.95  4757.7  251.61  4865.3  251.91  4873.4  250.13  4897.4  250.63
    4909  252.26  4940.1  251.92  4958.8  250.97  4964.1  248.59  4982.8  243.77
  4988.2  241.24  4988.7  240.74  5000.6  241.24  5001.5  242.53    5007  242.53
  5012.6  246.45  5018.2  246.55  5034.9  250.98  5048.9  249.72  5169.1  252.71
    5250  252.68    5445  261.43  5585.6  265.54  5652.6  264.81  5720.5  265.89
#Mann= 9 ,-1 , 0
  4149.8     .05       0  4192.8     .07       0  4367.3     .05       0
  4588.6     .07       0  4694.8      .1       0  4988.2     .05       0
  5000.6      .1       0    5250     .05       0    5445     .07       0
Bank Sta=4988.2,5000.6
XS Rating Curve= 0 ,0
Exp/Cntr=0.3,0.1

Type RM Length L Ch R = 1 ,12208   ,459,459,459
BEGIN DESCRIPTION:
KOKERNOT BRANCH 8.0
END DESCRIPTION:
XS GIS Cut Line= 4
      2513224.95     13704375.01        2512425.       13704475.
        2512175.       13704725.      2511945.36     13704954.64
#Sta/Elev= 30
    4193  258.86  4311.4  252.96  4354.2  252.55    4397  253.38  4472.6  251.89
  4515.4  252.22  4606.1  250.86  4696.2  250.81  4795.7  250.81  4928.6  250.34
  4938.7  249.14  4948.8  246.12  4968.9  244.69  4982.9  240.09  4983.4  239.59
  4995.4  240.09  4996.7  248.85  5002.7  248.85  5013.3  250.34  5098.2   250.3
  5112.3  250.87  5154.7  250.31  5180.3  251.03  5296.2  254.13  5356.3  256.29
  5409.3  259.13  5507.9  261.59  5607.3  261.55  5649.7  262.84  5677.5  262.36
#Mann= 7 ,-1 , 0
    4193     .05       0  4696.2     .07       0  4795.7      .1       0
  4982.9     .05       0  4995.4      .1       0  5180.3     .07       0
  5507.9     .05       0
Bank Sta=4982.9,4995.4
XS Rating Curve= 0 ,0
Exp/Cntr=0.3,0.1

Type RM Length L Ch R = 1 ,11749   ,311,311,311
BEGIN DESCRIPTION:
KOKERNOT BRANCH 7.0
END DESCRIPTION:
XS GIS Cut Line= 4
       2513579.8      13703630.3        2512275.       13704075.
        2512075.       13704625.      2511841.24     13704927.47
#Sta/Elev= 30
  3625.8  264.88  4291.9  251.67  4335.7  250.83  4454.9  249.48    4695  249.93
    4793  250.07  4831.9  249.26  4837.2   248.1  4863.2  249.01  4868.5  246.43
  4877.5   248.2  4888.1  248.45  4909.2  246.36  4925.9  247.61  4957.3  243.36
  4972.6  242.49  4982.4  239.34  4982.9  238.84  4994.9  239.34  5001.7  245.15
  5014.3  245.67  5019.6  248.06  5025.6  248.49  5192.5  249.58  5314.9  248.02
  5403.2   249.3  5596.8  256.28  5703.2  257.48  5839.5  259.76  5971.8  260.41
#Mann= 8 ,-1 , 0
  3625.8     .05       0  4291.9     .07       0  4335.7     .12       0
    4695      .1       0  4982.4     .05       0  4994.9      .1       0
  5403.2     .07       0  5703.2     .05       0
Bank Sta=4982.4,4994.9
XS Rating Curve= 0 ,0
Exp/Cntr=0.3,0.1

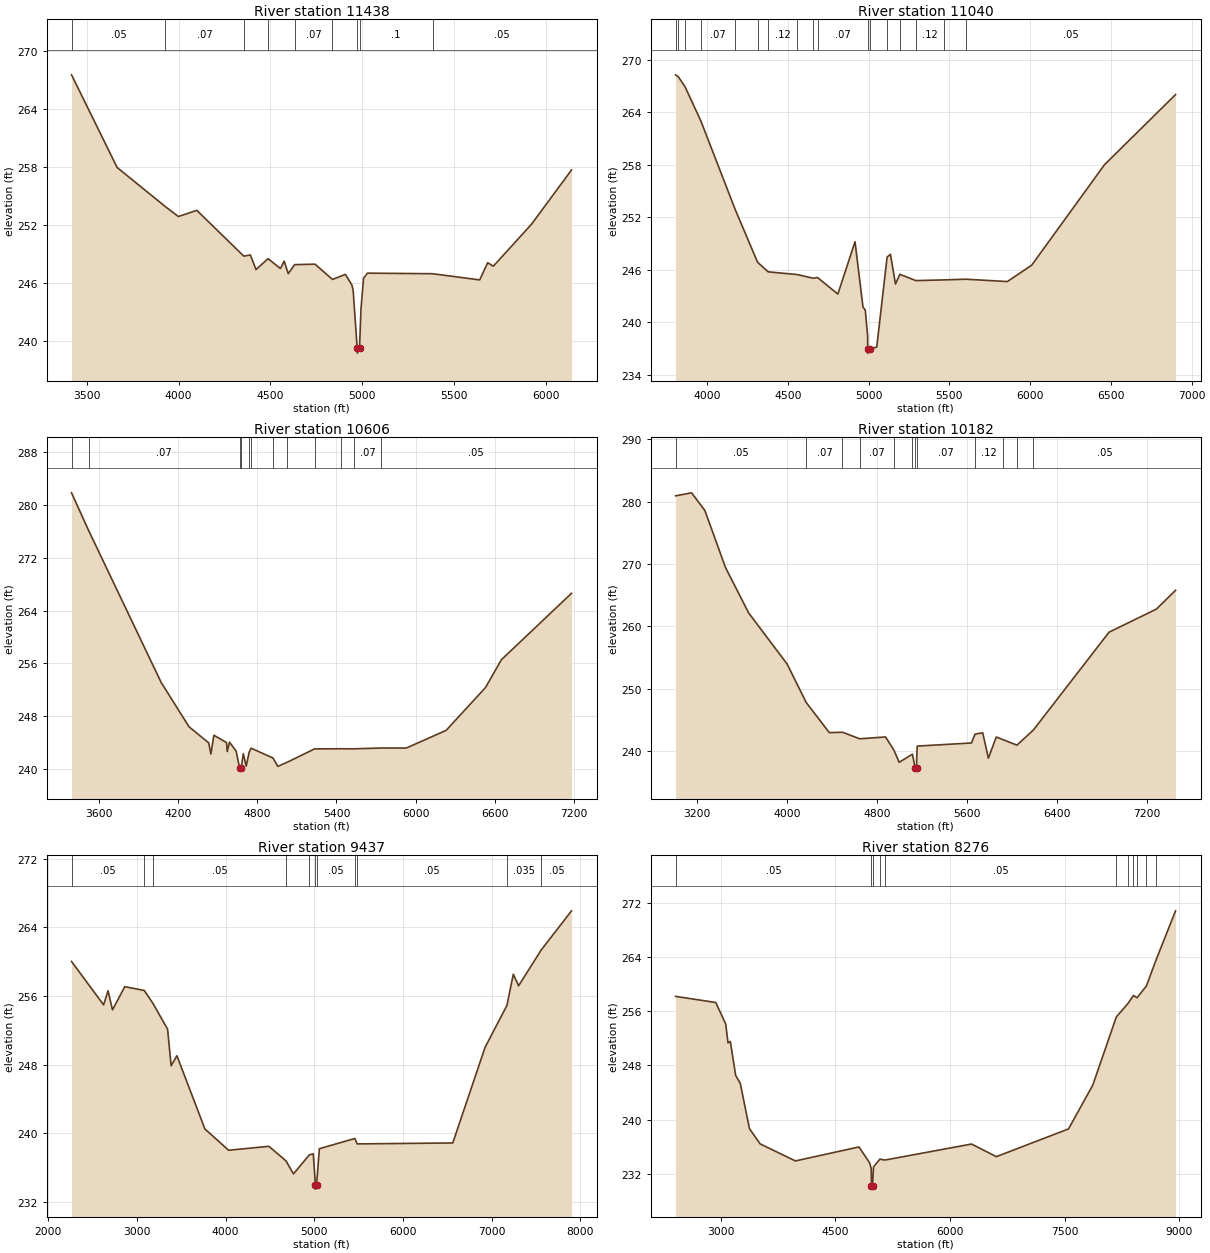
Type RM Length L Ch R = 1 ,11438   ,398,398,398
BEGIN DESCRIPTION:
A19529
END DESCRIPTION:
XS GIS Cut Line= 4
      2513597.82     13703432.11      2512246.61     13703711.36
      2511940.32     13704008.64       2511742.2      13704900.2
#Sta/Elev= 30
    3418  267.55  3665.9  257.96    3927  253.93  3999.2  252.88  4099.6  253.52
    4355  248.78  4390.8   248.9  4421.6  247.39  4486.9  248.52  4554.3   247.5
  4574.8  248.26  4596.8  246.97  4631.9   247.9  4742.4  247.95  4837.6  246.37
  4907.6  246.89  4942.9   245.8    4950  245.23  4972.1  239.24  4972.6  238.74
  4984.6  239.24  4992.5  243.29  5006.6  246.49  5027.7  247.02  5381.7  246.96
  5638.4  246.32  5681.8   248.1  5712.6  247.74  5920.1  252.08  6137.9   257.7
#Mann= 9 ,-1 , 0
    3418     .05       0    3927     .07       0    4355     .05       0
  4486.9     .12       0  4631.9     .07       0  4837.6      .1       0
  4972.1     .05       0  4984.6      .1       0  5381.7     .05       0
Bank Sta=4972.1,4984.6
XS Rating Curve= 0 ,0
Exp/Cntr=0.3,0.1

Type RM Length L Ch R = 1 ,11040   ,434,434,434
BEGIN DESCRIPTION:
A19528
END DESCRIPTION:
XS GIS Cut Line= 3
      2512715.02     13702774.51      2511742.14     13703693.34
      2511553.02     13705440.45
#Sta/Elev= 30
  3804.9  268.28  3821.7  268.06  3862.7  266.95  3960.9  263.03  4175.3  252.83
  4312.9  246.85  4378.7  245.76  4558.2  245.45  4657.2  245.03    4684  245.11
  4809.6  243.22    4916   249.2  4965.3  241.73  4979.5  241.39  4993.7  238.48
  4994.7  236.97  4995.2  236.47  5007.2  236.97  5050.3  237.16  5114.6  247.45
  5135.2  247.76  5166.4  244.37  5193.5  245.48  5292.3  244.76  5466.4  244.84
  5602.2  244.92  5858.9  244.65  6009.8  246.52  6460.6  258.01  6900.4  266.02
#Mann= 17 ,-1 , 0
  3804.9    .035       0  3821.7     .07       0  3862.7    .035       0
  3960.9     .07       0  4175.3     .12       0  4312.9     .07       0
  4378.7     .12       0  4558.2     .07       0  4657.2     .12       0
    4684     .07       0  4994.7     .05       0  5007.2     .07       0
  5114.6      .1       0  5193.5     .07       0  5292.3     .12       0
  5466.4     .07       0  5602.2     .05       0
Bank Sta=4994.7,5007.2
XS Rating Curve= 0 ,0
Exp/Cntr=0.3,0.1

Type RM Length L Ch R = 1 ,10606   ,424,424,424
BEGIN DESCRIPTION:
A19527
END DESCRIPTION:
XS GIS Cut Line= 3
      2512273.63     13701873.67      2511507.92     13703450.12
      2511417.84     13705486.05
#Sta/Elev= 30
  3391.7  281.84  3521.8  276.11  4071.3  253.09  4282.6  246.37  4431.3  243.94
  4448.3  242.25  4470.9  245.09  4566.7  243.98  4572.2  242.62  4589.2  244.04
  4639.9  242.67  4665.4  240.15  4665.9  239.65  4677.9  240.15  4693.9  242.29
  4716.1  240.41  4737.8  242.49  4752.8  243.13    4919  241.64  4955.8  240.37
    5027     241  5234.2  243.02  5431.1  243.04  5529.5  243.03  5738.6  243.15
  5929.9  243.15  6231.8  245.83  6530.5  252.33  6650.6  256.54  7182.2  266.61
#Mann= 12 ,-1 , 0
  3391.7     .05       0  3521.8     .07       0  4665.4     .05       0
  4677.9     .07       0  4737.8     .12       0  4752.8     .07       0
    4919     .12       0    5027     .07       0  5234.2    .035       0
  5431.1     .12       0  5529.5     .07       0  5738.6     .05       0
Bank Sta=4665.4,4677.9
XS Rating Curve= 0 ,0
Exp/Cntr=0.3,0.1

Type RM Length L Ch R = 1 ,10182   ,745,745,745
BEGIN DESCRIPTION:
A19526
END DESCRIPTION:
XS GIS Cut Line= 3
      2512011.34     13701283.56      2511145.14     13703434.14
      2511294.48     13705554.82
#Sta/Elev= 30
  3011.8  280.92  3154.1   281.4  3272.1  278.58  3455.4  269.45  3661.7  262.16
  4002.8     254  4172.7  247.83  4378.8  242.99  4495.6  243.06  4648.2  242.01
  4878.4   242.3  4951.3  240.24  4999.2  238.25  5117.4  239.54  5141.4  237.33
  5141.9  236.83  5154.5  237.33    5155  238.88  5160.4  240.84  5641.9  241.34
    5674  242.76  5742.1  242.97  5792.3   238.9  5862.4  242.29  5920.9  241.88
  6046.1  240.99  6191.8   243.4  6864.9  259.08    7286  262.78  7456.2  265.79
#Mann= 12 ,-1 , 0
  3011.8     .05       0  4172.7     .07       0  4495.6     .12       0
  4648.2     .07       0  4951.3     .12       0  5117.4     .07       0
  5141.4     .05       0  5154.5     .07       0    5674     .12       0
  5920.9     .05       0  6046.1    .035       0  6191.8     .05       0
Bank Sta=5141.4,5154.5
XS Rating Curve= 0 ,0
Exp/Cntr=0.3,0.1

Type RM Length L Ch R = 1 ,9437    ,1161,1161,1161
BEGIN DESCRIPTION:
A19525
END DESCRIPTION:
XS GIS Cut Line= 3
      2510891.25     13700044.04      2510667.24     13703314.66
      2511204.88     13705614.57
#Sta/Elev= 30
  2262.2  260.03    2624  254.97  2674.1  256.62  2724.4  254.39  2862.7  257.09
  3082.5  256.65    3181  255.14  3345.7  252.14  3385.8  247.87  3451.1  249.04
  3766.7  240.51  4034.5  238.03  4488.4  238.49  4680.9   236.8  4766.2  235.28
  4945.2   237.5  4989.5  237.61    5013     234  5013.5   233.5  5026.2     234
  5057.9  238.21  5457.8   239.4  5484.9  238.77  6562.9  238.88  6927.2  250.02
  7174.1  254.91  7245.6  258.54    7306   257.2    7560  261.36  7902.4  265.93
#Mann= 11 ,-1 , 0
  2262.2     .05       0  3082.5    .035       0    3181     .05       0
  4680.9     .15       0  4945.2     .05       0    5013     .05       0
  5026.2     .05       0  5457.8      .1       0  5484.9     .05       0
  7174.1    .035       0    7560     .05       0
Bank Sta=5013,5026.2
XS Rating Curve= 0 ,0
Exp/Cntr=0.3,0.1

Type RM Length L Ch R = 1 ,8276    ,0,0,0
BEGIN DESCRIPTION:
KOKERNOT BRANCH 6.0
END DESCRIPTION:
XS GIS Cut Line= 3
      2509636.76     13699790.17      2509890.65     13703926.97
      2511233.62      13705911.6
#Sta/Elev= 30
    2410  258.16  2935.8  257.26  3066.1  254.09  3096.1  251.29  3126.2  251.51
  3196.3   246.5  3256.4  245.34  3376.6  238.65  3516.9   236.4  3977.8  233.89
  4809.3  235.95  4949.6  233.59  4969.6  232.74    4973  230.23  4973.5  229.73
  4986.3  230.23  4999.7  233.02  5082.7  234.15  5149.7  234.02  6282.1  236.38
  6606.8  234.52  7550.5  238.61  7868.1  245.07  8176.2  255.13  8325.1  257.07
  8400.5  258.29  8446.3  257.96  8569.1  259.68  8688.8  263.33  8950.9  270.78
#Mann= 11 ,-1 , 0
    2410     .05       0    4973     .05       0  4986.3     .05       0
  5082.7     .07       0  5149.7     .05       0  8176.2     .07       0
  8325.1     .05       0  8400.5     .07       0  8446.3     .05       0
  8569.1    .035       0  8688.8     .05       0
Bank Sta=4973,4986.3
XS Rating Curve= 0 ,0
Exp/Cntr=0.3,0.1

Chan Stop Cuts=-1
Use User Specified Reach Order=0
Composite Channel Slope=5