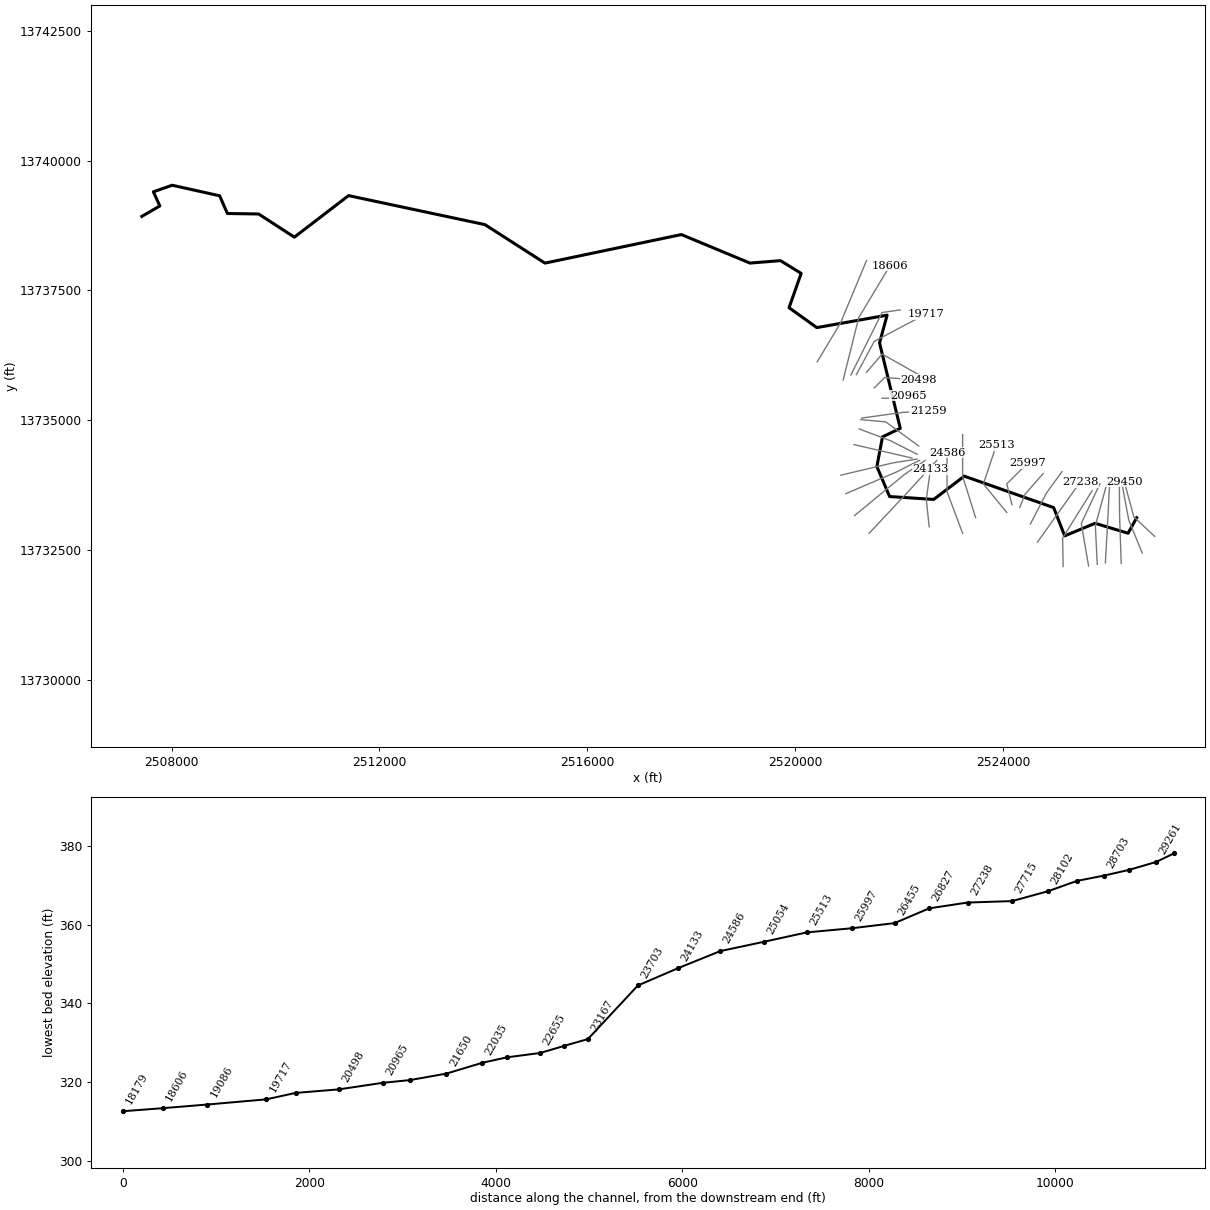
--- LIVEOAK BRANCH.prj (project) ---

Proj Title=LIVEOAK BRANCH Base Level Engineering
Current Plan=p01
Default Exp/Contr=0.3,0.1
English Units
Geom File=g01
Flow File=f01
Plan File=p01
Y Axis Title=Elevation
X Axis Title(PF)=Main Channel Distance
X Axis Title(XS)=Station
BEGIN DESCRIPTION:
LIVEOAK BRANCH
END DESCRIPTION:
DSS Export Rating Curves= 0
DSS Export Rating Curve Sorted= 0
DSS Export Volume Flow Curves= 0
DXF OffsetX= 0
DXF OffsetY= 0
DXF ScaleX= 1
DXF ScaleY= 10

--- LIVEOAK BRANCH.p01 (plan) ---

Plan Title=Multiple Run
Short Identifier=Multiple
Geom File=g01
Flow File=f01
Subcritical Flow
K Sum by GR= 0
Std Step Tol= 0.01
Critical Tol= 0.01
Num of Std Step Trials= 20
Max Error Tol= 0.3
Flow Tol Ratio= 0.001
Split Flow NTrial= 30
Split Flow Tol= 0.02
Split Flow Ratio= 0.02
Log Output Level= 0
Friction Slope Method= 1
Unsteady Friction Slope Method= 2
Unsteady Bridges Friction Slope Method= 1
Parabolic Critical Depth
Global Vel Dist=  1 , 1 , 1
Global Log Level= 0
CheckData=True
Encroach Param= -1, 0, 0, 0
BEGIN DESCRIPTION:
Multiple Run
END DESCRIPTION:

--- LIVEOAK BRANCH.f01 (steady flow) ---

Flow Title=Multiple
Number of Profiles=7
Profile Names=10-year,25-year,50-year,1pct_min,100-year,1pct_plu,500-year
River Rch & RM= LIVEOAK BRANCH,Reach-1,29450
    1025    1710    2353    1568    3129    6244    5478
River Rch & RM= LIVEOAK BRANCH,Reach-1,27715
    1427    2410    3341    2240    4470    8919    7924
River Rch & RM= LIVEOAK BRANCH,Reach-1,22908
    1771    3011    4191    2818    5623   11220   10031
River Rch & RM= LIVEOAK BRANCH,Reach-1,15514
    2080    3554    4965    3349    6682   13332   11990
River Rch & RM= LIVEOAK BRANCH,Reach-1,11386
    2108    3593    5009    3371    6725   13419   12013
River Rch & RM= LIVEOAK BRANCH,Reach-1,6734
    2380    4076    5702    3848    7678   15319   13794
River Rch & RM= LIVEOAK BRANCH,Reach-1,4479
    2766    4764    6690    4530    9038   18034   16349
Boundary for River Rch & Prof#=LIVEOAK BRANCH,Reach-1,1
Up Type=0
Dn Type=3
Dn Slope=0.005
Boundary for River Rch & Prof#=LIVEOAK BRANCH,Reach-1,2
Up Type=0
Dn Type=3
Dn Slope=0.005
Boundary for River Rch & Prof#=LIVEOAK BRANCH,Reach-1,3
Up Type=0
Dn Type=3
Dn Slope=0.005
Boundary for River Rch & Prof#=LIVEOAK BRANCH,Reach-1,4
Up Type=0
Dn Type=3
Dn Slope=0.005
Boundary for River Rch & Prof#=LIVEOAK BRANCH,Reach-1,5
Up Type=0
Dn Type=3
Dn Slope=0.005
Boundary for River Rch & Prof#=LIVEOAK BRANCH,Reach-1,6
Up Type=0
Dn Type=3
Dn Slope=0.005
Boundary for River Rch & Prof#=LIVEOAK BRANCH,Reach-1,7
Up Type=0
Dn Type=3
Dn Slope=0.005

--- LIVEOAK BRANCH.g01 (geometry) ---

Geom Title=Existing Conditions
Program Version=4.10

River Reach=LIVEOAK BRANCH  ,Reach-1
Reach XY= 30
        2526575.       13733125.       2526410.3     13732825.88
       2525775.1     13733017.69       2525189.4     13732775.74
      2524977.47     13733319.55      2523256.72     13733925.07
      2522669.14     13733477.06      2521818.81     13733532.75
      2521574.53     13734109.84      2521682.72      13734681.5
      2522024.95     13734845.01      2521625.52     13736490.22
      2521771.56     13737023.81      2520418.33     13736784.39
      2519883.85     13737168.05      2520117.01     13737828.34
      2519718.97     13738073.36      2519131.12     13738026.76
      2517811.18     13738575.44      2515185.44     13738026.04
      2514028.67     13738767.31      2511404.89     13739325.12
       2510360.9     13738525.24      2509673.77     13738971.57
      2509072.38     13738980.73      2508923.52     13739321.54
      2508009.58     13739524.97      2507647.86     13739398.64
      2507771.54     13739126.48        2507425.       13738925.

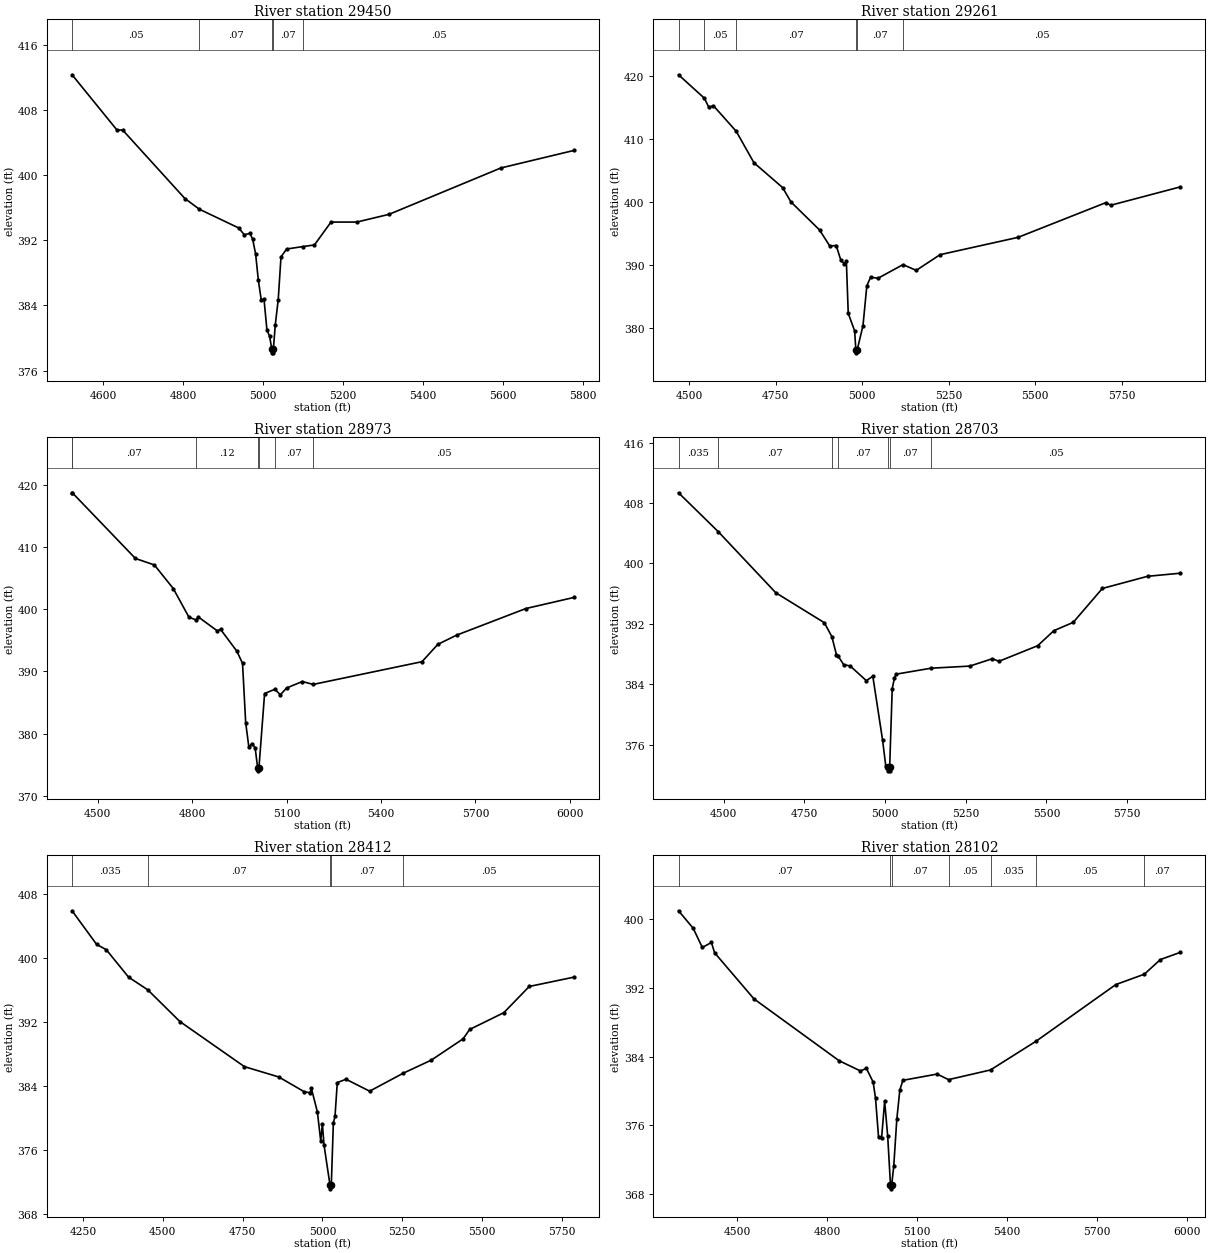
Type RM Length L Ch R = 1 ,29450   ,189,189,189
BEGIN DESCRIPTION:
A19711
END DESCRIPTION:
XS GIS Cut Line= 3
      2526923.55     13732764.55      2526522.53     13733139.54
      2526335.27     13733820.95
#Sta/Elev= 30
  4522.3  412.35  4634.7  405.56  4648.9  405.56  4804.7  397.14  4840.8  395.83
  4939.1  393.53  4953.2   392.7  4967.4  392.85  4974.2  392.15  4981.6  390.34
  4988.4  387.12  4995.7  384.68  5002.6  384.78  5009.9  381.02  5016.7  380.19
    5022  378.68  5022.3  378.18  5025.9  378.18  5026.1  378.68  5030.9  381.66
  5038.2  384.72  5045.1  389.97  5059.2  390.94  5100.4  391.24  5128.8  391.44
  5170.3  394.25  5234.8  394.25  5315.5   395.2  5595.5   400.9    5778  403.05
#Mann= 5 ,-1 , 0
  4522.3     .05       0  4840.8     .07       0    5022     .05       0
  5026.1     .07       0  5100.4     .05       0
Bank Sta=5022,5026.1
XS Rating Curve= 0 ,0
Exp/Cntr=0.3,0.1

Type RM Length L Ch R = 1 ,29261   ,288,288,288
BEGIN DESCRIPTION:
A19710
END DESCRIPTION:
XS GIS Cut Line= 3
      2526683.99     13732441.61      2526423.57     13733077.04
      2526282.94     13733827.05
#Sta/Elev= 30
  4469.4  420.27    4544  416.54  4556.6  415.13  4570.3  415.34  4635.9  411.29
  4687.3  406.27  4770.1  402.32  4794.1  400.04  4876.9  395.57  4906.3  393.02
  4924.9   393.1  4937.8  390.86  4948.6  390.15  4954.3  390.59  4959.7  382.31
  4978.3   379.5  4981.6  376.52  4981.9  376.02  4985.7  376.52  5002.3  380.34
  5013.4  386.67  5024.2  388.05  5045.8  387.89    5118  390.06  5156.1  389.14
    5225  391.64  5450.5   394.4  5703.5  399.91  5718.4  399.51  5919.2  402.43
#Mann= 6 ,-1 , 0
  4469.4     .07       0    4544     .05       0  4635.9     .07       0
  4981.6     .05       0  4985.7     .07       0    5118     .05       0
Bank Sta=4981.6,4985.7
XS Rating Curve= 0 ,0
Exp/Cntr=0.3,0.1

Type RM Length L Ch R = 1 ,28973   ,270,270,270
BEGIN DESCRIPTION:
A19709
END DESCRIPTION:
XS GIS Cut Line= 3
      2526277.74     13732243.69      2526246.49     13733160.37
      2526241.28     13733837.43
#Sta/Elev= 30
  4418.4  418.74  4419.2  418.74  4619.8  408.17  4679.9  407.13  4739.9  403.34
  4789.9  398.71  4812.1   398.3  4819.9  398.75    4880  396.52    4890  396.78
    4942  393.26    4960   391.3    4970  381.76    4980  377.86    4990   378.4
  5000.1   377.7    5008  374.51  5008.3  374.01  5012.2  374.51  5030.1  386.45
  5062.7  387.13  5080.1  386.24  5100.1  387.34  5150.1  388.38  5184.4  387.91
  5530.3  391.57  5580.3  394.35  5640.3  395.84  5860.3  400.12  6012.7   401.9
#Mann= 7 ,-1 , 0
  4418.4     .05       0  4419.2     .07       0  4812.1     .12       0
    5008     .05       0  5012.2     .12       0  5062.7     .07       0
  5184.4     .05       0
Bank Sta=5008,5012.2
XS Rating Curve= 0 ,0
Exp/Cntr=0.3,0.1

Type RM Length L Ch R = 1 ,28703   ,291,291,291
BEGIN DESCRIPTION:
A19708
END DESCRIPTION:
XS GIS Cut Line= 3
      2525972.53     13732254.17       2526014.2     13732998.91
      2526055.86     13733806.23
#Sta/Elev= 30
  4360.6  409.36  4483.4  404.22  4661.9  396.12  4812.1  392.16  4835.4  390.32
  4849.8  387.91  4855.6  387.69  4872.2   386.6  4892.3  386.43  4942.3  384.48
  4962.4  385.06  4992.4  376.68  5002.4  373.22  5010.4  373.04  5010.7  372.54
  5014.3  372.54  5014.6  373.04  5022.5  383.43  5029.4  384.84  5034.4  385.34
  5142.5  386.13  5262.8  386.41  5332.9  387.39  5352.9  387.04  5473.1  389.11
  5523.2   391.1  5583.2   392.2  5673.4  396.69  5813.5   398.3  5914.9  398.71
#Mann= 7 ,-1 , 0
  4360.6    .035       0  4483.4     .07       0  4835.4     .12       0
  4855.6     .07       0  5010.4     .05       0  5014.6     .07       0
  5142.5     .05       0
Bank Sta=5010.4,5014.6
XS Rating Curve= 0 ,0
Exp/Cntr=0.3,0.1

Type RM Length L Ch R = 1 ,28412   ,310,310,310
BEGIN DESCRIPTION:
A19707
END DESCRIPTION:
XS GIS Cut Line= 3
      2525816.28     13732228.06      2525779.82     13732972.87
      2525998.58     13733769.79
#Sta/Elev= 30
  4215.7  405.87  4292.7  401.67  4322.8  401.02  4392.8  397.59  4452.9  396.01
  4553.4  392.06  4755.7  386.43  4863.4  385.14  4943.5  383.29  4961.4  383.18
  4965.4  383.73  4984.3  380.77  4994.7  377.17  4999.9  379.27  5005.1  376.64
  5023.7  371.69    5024  371.19  5027.9  371.69  5034.3   379.4  5039.5  380.23
  5046.6  384.44  5073.9  384.86    5148  383.37  5252.6   385.6    5341  387.24
  5440.6  389.89  5461.4  391.07  5568.4  393.16    5648  396.43  5787.8  397.59
#Mann= 5 ,-1 , 0
  4215.7    .035       0  4452.9     .07       0  5023.7     .05       0
  5027.9     .07       0  5252.6     .05       0
Bank Sta=5023.7,5027.9
XS Rating Curve= 0 ,0
Exp/Cntr=0.3,0.1

Type RM Length L Ch R = 1 ,28102   ,387,387,387
BEGIN DESCRIPTION:
A19706
END DESCRIPTION:
XS GIS Cut Line= 3
      2525649.62     13732196.78      2525508.99     13733014.54
      2525868.31     13733780.04
#Sta/Elev= 30
  4303.2  401.01  4352.1  398.97  4382.6  396.73    4413  397.31  4423.6  396.11
  4555.1  390.73  4839.2  383.52  4910.2  382.33  4930.5  382.62  4952.9  381.03
  4960.9  379.14  4971.1  374.57  4981.2  374.52  4991.4  378.79  5001.5  374.73
  5010.8  369.07    5011  368.57    5015  369.07  5021.8  371.23    5032   376.7
  5042.1   380.1  5052.3  381.23  5166.6  381.96  5204.7  381.31  5344.8  382.44
  5496.9  385.79  5763.1   392.4  5858.4  393.61  5912.1  395.32  5978.6  396.16
#Mann= 7 ,-1 , 0
  4303.2     .07       0  5010.8     .05       0    5015     .07       0
  5204.7     .05       0  5344.8    .035       0  5496.9     .05       0
  5858.4     .07       0
Bank Sta=5010.8,5015
XS Rating Curve= 0 ,0
Exp/Cntr=0.3,0.1

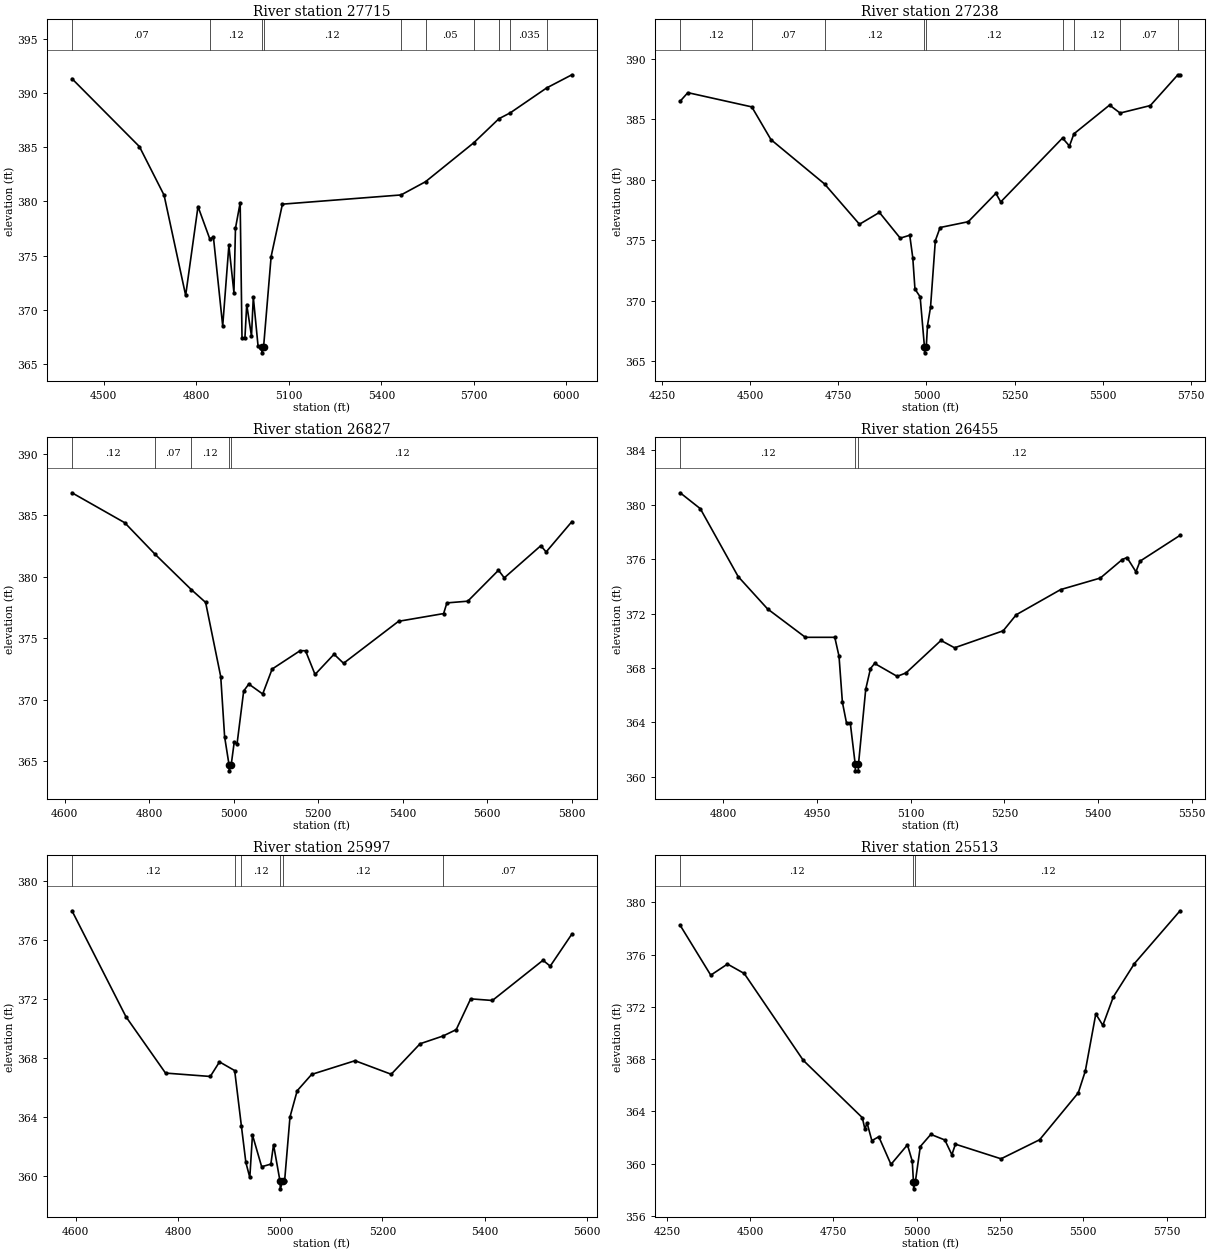
Type RM Length L Ch R = 1 ,27715   ,477,477,477
BEGIN DESCRIPTION:
A19705
END DESCRIPTION:
XS GIS Cut Line= 3
      2525160.03     13732186.44      2525149.61     13732733.29
      2525717.34     13733644.79
#Sta/Elev= 30
  4396.9  391.32  4615.5  385.06  4695.5  380.58  4765.5  371.34  4805.5  379.53
  4843.8  376.54  4855.5  376.71  4885.6  368.52  4905.6  375.94    4922   371.6
    4927  377.53  4942.2  379.88  4948.2  367.41  4957.6   367.4  4963.5  370.49
  4978.9  367.58  4984.8  371.18  5000.1   366.7  5012.9  366.54  5013.3  366.04
    5018  366.54  5042.6  374.92  5079.2  379.75  5463.9   380.6  5543.2  381.82
    5700  385.42  5781.2  387.63    5818  388.17  5936.1  390.47  6017.7  391.68
#Mann= 10 ,-1 , 0
  4396.9     .07       0  4843.8     .12       0  5012.9     .05       0
    5018     .12       0  5463.9     .07       0  5543.2     .05       0
    5700    .035       0  5781.2     .05       0    5818    .035       0
  5936.1     .07       0
Bank Sta=5012.9,5018
XS Rating Curve= 0 ,0
Exp/Cntr=0.3,0.1

Type RM Length L Ch R = 1 ,27238   ,411,411,411
BEGIN DESCRIPTION:
A19704
END DESCRIPTION:
XS GIS Cut Line= 2
      2524665.23     13732655.16      2525487.63     13733810.68
#Sta/Elev= 30
  4301.1  386.51  4322.9  387.22  4504.4  386.04  4558.7  383.33  4710.7  379.66
  4809.9  376.32  4866.4   377.3  4925.5  375.17  4952.5  375.41  4961.1  373.55
  4967.3  370.95    4982  370.31  4994.2  366.17  4994.6  365.67  4999.4  366.17
  5002.9  367.93  5011.5  369.46  5025.1  374.96  5038.6  376.05  5118.5  376.53
  5196.9  378.88  5210.7  378.17  5385.9  383.46  5405.6   382.8  5418.3  383.81
  5519.4  386.19  5549.3  385.53    5635  386.15  5713.2   388.7  5719.4  388.69
#Mann= 9 ,-1 , 0
  4301.1     .12       0  4504.4     .07       0  4710.7     .12       0
  4994.2     .05       0  4999.4     .12       0  5385.9     .07       0
  5418.3     .12       0  5549.3     .07       0  5713.2     .12       0
Bank Sta=4994.2,4999.4
XS Rating Curve= 0 ,0
Exp/Cntr=0.3,0.1

Type RM Length L Ch R = 1 ,26827   ,372,372,372
BEGIN DESCRIPTION:
A19703
END DESCRIPTION:
XS GIS Cut Line= 3
       2524529.8     13733004.09      2524837.11     13733597.87
      2525139.17     13734014.51
#Sta/Elev= 30
    4617  386.85  4741.9  384.41  4813.2  381.86  4899.5  378.96  4933.3  377.92
  4969.1  371.87  4978.3  366.97  4988.7   364.7  4989.1   364.2  4993.9   364.7
  5000.9  366.51  5007.8  366.42  5023.4   370.7  5035.5  371.27  5068.4  370.46
  5090.7  372.49  5157.1  373.99  5169.8  373.98  5192.3  372.05  5237.3   373.7
  5259.8  372.96  5389.9  376.38  5496.6  377.01  5504.4  377.88  5553.8  378.02
  5626.5  380.54  5640.2  379.92  5726.7  382.54  5739.3  382.03  5800.2   384.5
#Mann= 5 ,-1 , 0
    4617     .12       0  4813.2     .07       0  4899.5     .12       0
  4988.7     .05       0  4993.9     .12       0
Bank Sta=4988.7,4993.9
XS Rating Curve= 0 ,0
Exp/Cntr=0.3,0.1

Type RM Length L Ch R = 1 ,26455   ,458,458,458
BEGIN DESCRIPTION:
LIVEOAK BRANCH 49.0
END DESCRIPTION:
XS GIS Cut Line= 3
      2524324.99     13733324.98        2524425.       13733575.
      2524775.01     13733975.01
#Sta/Elev= 30
  4730.7  380.89    4763  379.72  4823.6  374.73  4870.7  372.35  4931.3  370.26
  4978.4  370.26  4985.2  368.87  4990.6  365.49  4997.3  363.93  5003.3  363.93
  5011.1  360.94  5011.5  360.44    5016  360.44  5016.4  360.94    5028  366.45
  5035.6  367.96  5042.2  368.34  5078.3  367.39  5092.5  367.64  5148.5  370.03
  5170.3  369.49  5248.2  370.74  5269.1  371.92  5340.2  373.77  5403.8  374.62
  5438.9  375.98  5446.5  376.13  5460.8  375.08  5467.4  375.86  5531.5  377.76
#Mann= 3 ,-1 , 0
  4730.7     .12       0  5011.1     .05       0  5016.4     .12       0
Bank Sta=5011.1,5016.4
XS Rating Curve= 0 ,0
Exp/Cntr=0.3,0.1

Type RM Length L Ch R = 1 ,25997   ,484,484,484
BEGIN DESCRIPTION:
LIVEOAK BRANCH 48.0
END DESCRIPTION:
XS GIS Cut Line= 3
      2524175.01     13733374.98        2524075.       13733775.
      2524474.99     13734174.99
#Sta/Elev= 30
  4592.7  378.01  4698.4  370.81  4775.7  366.99  4863.3  366.76  4881.3  367.75
    4911  367.16  4924.1  363.41  4932.9  360.92  4940.6   359.9  4945.8  362.79
  4963.8  360.63  4981.8  360.81    4987  362.13  4999.8  359.63  5000.2  359.13
  5005.2  359.63  5008.6  359.63  5019.2  364.01  5033.3  365.79  5061.6   366.9
  5146.5  367.83  5217.2  366.91  5273.7  368.98  5318.8  369.51  5344.4  369.94
  5372.7  372.03  5415.2  371.92  5514.2  374.65  5528.3  374.25  5570.7  376.43
#Mann= 6 ,-1 , 0
  4592.7     .12       0    4911     .07       0  4924.1     .12       0
  4999.8     .05       0  5005.2     .12       0  5318.8     .07       0
Bank Sta=4999.8,5005.2
XS Rating Curve= 0 ,0
Exp/Cntr=0.3,0.1

Type RM Length L Ch R = 1 ,25513   ,459,459,459
BEGIN DESCRIPTION:
LIVEOAK BRANCH 47.0
END DESCRIPTION:
XS GIS Cut Line= 3
      2524074.99     13733225.02        2523625.       13733775.
      2523875.01     13734525.02
#Sta/Elev= 30
  4289.5  378.25  4381.4  374.43  4431.6  375.28  4481.9  374.56  4659.2  367.91
  4836.5  363.52  4844.3  362.65  4850.8  363.11  4865.2  361.76    4886  362.06
  4922.6  359.94  4972.1  361.44  4986.5  360.19  4990.2  358.57  4990.7  358.07
  4995.6  358.57  5010.7  361.31  5042.3  362.24  5084.4  361.81  5105.5  360.68
  5116.1  361.49  5253.1  360.37    5369  361.83    5485  365.42  5506.1  367.08
  5537.7  371.46  5558.8  370.59  5590.4  372.77  5653.7  375.32  5790.7  379.36
#Mann= 3 ,-1 , 0
  4289.5     .12       0  4990.2     .05       0  4995.6     .12       0
Bank Sta=4990.2,4995.6
XS Rating Curve= 0 ,0
Exp/Cntr=0.3,0.1

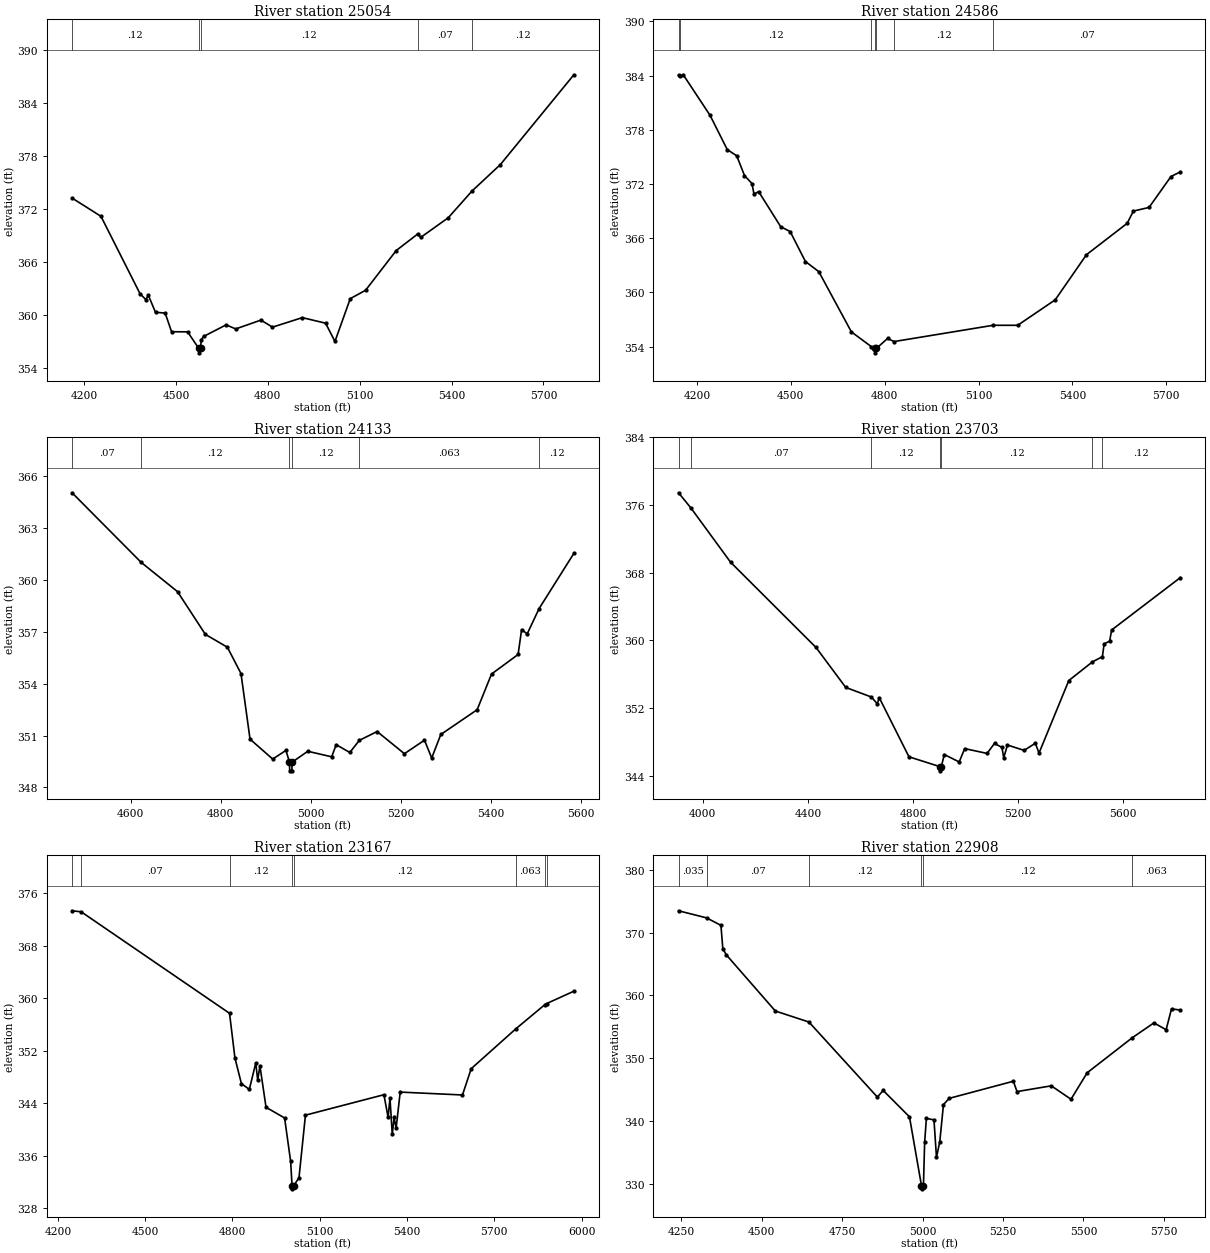
Type RM Length L Ch R = 1 ,25054   ,468,468,468
BEGIN DESCRIPTION:
LIVEOAK BRANCH 46.0
END DESCRIPTION:
XS GIS Cut Line= 3
      2523475.01     13733124.98        2523225.       13733925.
        2523225.     13734725.02
#Sta/Elev= 30
    4161  373.22  4255.3  371.15  4382.6   362.4    4402   361.7  4409.8  362.22
  4433.4  360.27  4464.9  360.19  4485.8  358.07  4538.2  358.06  4574.7  356.18
  4575.1  355.68  4580.3  356.18  4582.7  357.16  4590.6  357.54  4663.9  358.85
  4695.3  358.39  4777.6  359.39  4815.3  358.59  4912.7  359.67  4988.7  359.04
  5019.2  356.97  5069.2  361.82  5119.2  362.77  5219.2  367.27  5289.1  369.14
  5299.2  368.76  5389.2  370.99  5466.8  374.02  5559.2  377.01  5799.2  387.19
#Mann= 5 ,-1 , 0
    4161     .12       0  4574.7     .05       0  4580.3     .12       0
  5289.1     .07       0  5466.8     .12       0
Bank Sta=4574.7,4580.3
XS Rating Curve= 0 ,0
Exp/Cntr=0.3,0.1

Type RM Length L Ch R = 1 ,24586   ,453,453,453
BEGIN DESCRIPTION:
LIVEOAK BRANCH 45.0
END DESCRIPTION:
XS GIS Cut Line= 3
      2523224.99     13732825.02        2522925.       13733625.
        2522925.     13734375.02
#Sta/Elev= 30
  4140.9  384.05  4145.9  383.94    4156   384.1  4241.5  379.62  4296.6  375.82
  4326.9  375.13  4351.8  372.94  4375.8  372.05  4382.1   370.9  4397.2  371.16
  4467.5  367.28  4497.8  366.74  4546.7  363.42  4589.4   362.3  4693.6  355.63
  4757.2     354  4768.2  353.81  4768.7  353.31  4773.8  353.81  4809.3   354.9
  4830.3  354.56  5146.6  356.36  5225.3  356.36  5345.3  359.18  5445.3  364.18
  5575.3  367.65  5595.3  369.01  5645.3  369.41  5715.3  372.83  5745.3  373.35
#Mann= 7 ,-1 , 0
  4140.9     .07       0  4145.9     .12       0  4757.2     .07       0
  4768.2     .05       0  4773.8     .07       0  4830.3     .12       0
  5146.6     .07       0
Bank Sta=4768.2,4773.8
XS Rating Curve= 0 ,0
Exp/Cntr=0.3,0.1

Type RM Length L Ch R = 1 ,24133   ,430,430,430
BEGIN DESCRIPTION:
LIVEOAK BRANCH 44.0
END DESCRIPTION:
XS GIS Cut Line= 3
      2522581.32      13732952.2        2522525.       13733475.
      2522605.51     13734057.64
#Sta/Elev= 30
  4469.7  365.02  4623.1     361  4703.8  359.31  4765.7  356.84  4814.5   356.1
  4844.7  354.58  4864.8  350.79  4915.1  349.64  4944.5  350.14  4952.4  349.46
  4952.8  348.96  4957.7  348.96  4958.2  349.46    4993  350.09    5046  349.77
  5056.1  350.47  5086.4  350.02  5107.4  350.72    5147  351.23  5207.5  349.95
  5252.1  350.73  5268.1   349.7  5288.3  351.06    5369  352.49  5400.9  354.55
  5459.9  355.68  5467.7  357.12  5480.1  356.87  5506.5  358.33  5583.7  361.52
#Mann= 6 ,-1 , 0
  4469.7     .07       0  4623.1     .12       0  4952.4     .05       0
  4958.2     .12       0  5107.4    .063       0  5506.5     .12       0
Bank Sta=4952.4,4958.2
XS Rating Curve= 0 ,0
Exp/Cntr=0.3,0.1

Type RM Length L Ch R = 1 ,23703   ,536,536,536
BEGIN DESCRIPTION:
LIVEOAK BRANCH 43.0
END DESCRIPTION:
XS GIS Cut Line= 3
      2521424.99     13732824.99        2522175.       13733625.
      2522724.97     13734224.97
#Sta/Elev= 30
  3907.5  377.44  3955.2  375.62  4105.6  369.23  4430.9  359.15  4544.2  354.42
  4641.7  353.29  4664.4  352.48  4671.7  353.21  4784.8  346.22  4902.3  345.06
  4902.7  344.56  4908.1  345.06  4919.3  346.49    4976  345.61    4997  347.19
  5082.1  346.62  5110.5   347.8  5138.8  347.33  5145.6  346.11  5159.8  347.61
  5223.3  346.98  5265.9  347.82    5280  346.66  5393.5  355.24  5483.6  357.45
  5521.3  358.06  5527.9  359.58  5548.9  359.89  5556.3  361.21    5818  367.41
#Mann= 7 ,-1 , 0
  3907.5     .05       0  3955.2     .07       0  4641.7     .12       0
  4902.3     .05       0  4908.1     .12       0  5483.6    .063       0
  5521.3     .12       0
Bank Sta=4902.3,4908.1
XS Rating Curve= 0 ,0
Exp/Cntr=0.3,0.1

Type RM Length L Ch R = 1 ,23167   ,259,259,259
BEGIN DESCRIPTION:
A19702
END DESCRIPTION:
XS GIS Cut Line= 3
      2521144.96     13733166.45      2522108.71      13733959.9
      2522503.51     13734226.97
#Sta/Elev= 30
  4248.6  373.34  4280.1  373.18  4789.9   357.7  4808.5  350.88  4830.7  346.97
    4858  346.09  4880.2  350.14  4886.7  347.49  4894.5  349.66  4915.4  343.36
  4979.2  341.73    5000   335.1  5004.8  331.42  5005.3  330.92  5010.9  331.42
  5028.7  332.62  5050.9  342.16  5320.7  345.28    5335  341.83  5341.5  344.75
  5349.3  339.22  5355.8  341.82  5362.6  340.15  5376.6  345.68  5590.7  345.24
  5620.7  349.25  5774.1  355.33  5874.5  359.04  5879.8  359.18  5973.6  361.07
#Mann= 8 ,-1 , 0
  4248.6    .035       0  4280.1     .07       0  4789.9     .12       0
  5004.8     .05       0  5010.9     .12       0  5774.1    .063       0
  5874.5     .12       0  5879.8     .07       0
Bank Sta=5004.8,5010.9
XS Rating Curve= 0 ,0
Exp/Cntr=0.3,0.1

Type RM Length L Ch R = 1 ,22908   ,253,253,253
BEGIN DESCRIPTION:
A19701
END DESCRIPTION:
XS GIS Cut Line= 3
      2520978.51     13733588.33      2521953.89     13734006.35
       2522398.2     13734230.44
#Sta/Elev= 30
  4242.1  373.48  4329.2  372.35  4373.8  371.16  4379.7  367.44  4390.6  366.45
  4542.9   357.5  4647.1  355.75  4859.7  343.79  4877.9  344.84  4959.5  340.64
  4996.8  329.66  4997.3  329.16  5002.9  329.66  5006.6  336.56    5012  340.38
  5035.6  340.16  5043.4  334.17  5053.7   336.7  5065.1  342.59  5082.8  343.58
  5282.2  346.31  5293.6  344.66    5400  345.58  5461.3  343.44  5511.5  347.66
  5652.3  353.27  5718.9  355.61  5756.8  354.52  5773.5  357.85  5800.9  357.65
#Mann= 6 ,-1 , 0
  4242.1    .035       0  4329.2     .07       0  4647.1     .12       0
  4996.8     .05       0  5002.9     .12       0  5652.3    .063       0
Bank Sta=4996.8,5002.9
XS Rating Curve= 0 ,0
Exp/Cntr=0.3,0.1

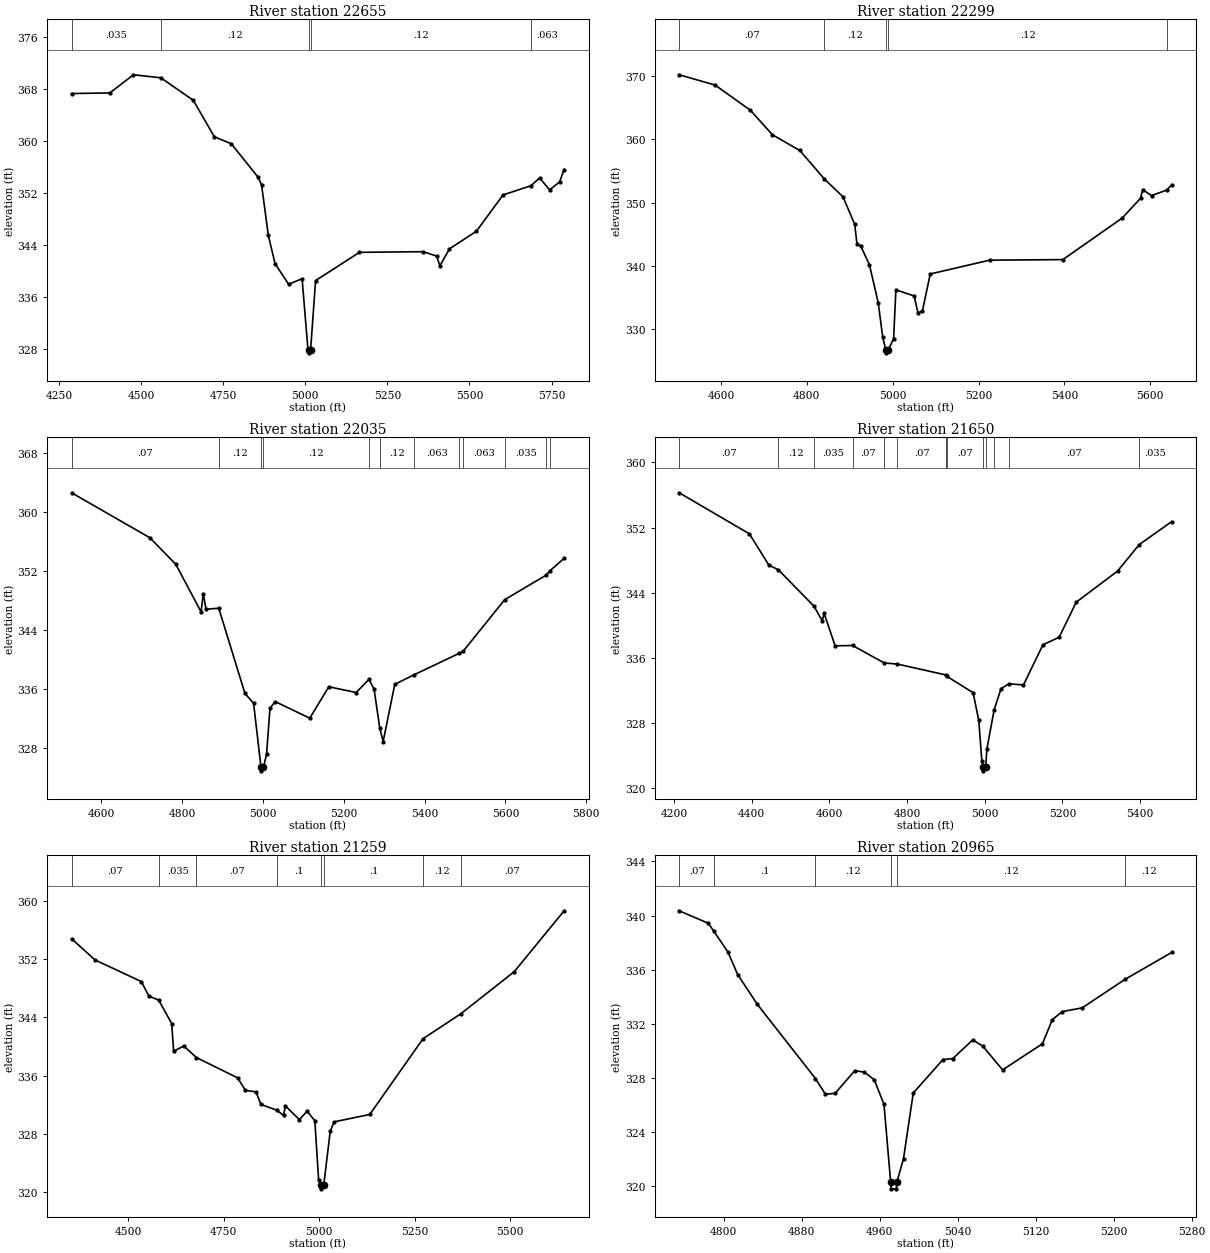
Type RM Length L Ch R = 1 ,22655   ,356,356,356
BEGIN DESCRIPTION:
A19700
END DESCRIPTION:
XS GIS Cut Line= 3
      2520881.74     13733944.42      2521884.21     13734180.52
      2522348.72     13734254.07
#Sta/Elev= 30
  4288.2  367.29  4404.7  367.39  4476.5  370.18  4559.9  369.72  4658.9  366.25
    4723  360.63  4774.4  359.57  4856.6  354.39  4866.9   353.2  4887.4  345.45
    4908  341.08  4949.1  337.95  4990.2  338.78    5008  327.97  5010.1  327.88
  5010.6  327.38  5016.2  327.88  5031.3   338.5  5164.8  342.85  5359.4  342.95
  5399.9  342.27    5410  340.78    5439  343.38  5521.4  346.11  5602.4  351.69
  5686.7  353.09  5713.8   354.3  5744.1  352.46  5774.5  353.69  5788.4   355.6
#Mann= 5 ,-1 , 0
  4288.2    .035       0  4559.9     .12       0  5010.1     .05       0
  5016.2     .12       0  5686.7    .063       0
Bank Sta=5010.1,5016.2
XS Rating Curve= 0 ,0
Exp/Cntr=0.3,0.1

Type RM Length L Ch R = 1 ,22299   ,264,264,264
BEGIN DESCRIPTION:
A19699
END DESCRIPTION:
XS GIS Cut Line= 2
      2521133.27     13734532.76      2522250.93     13734273.65
#Sta/Elev= 30
  4502.7  370.23  4586.6   368.6  4668.7  364.61    4720  360.74  4783.7  358.26
    4841  353.75  4884.3  350.94  4911.7  346.56  4916.8  343.47  4925.3  343.21
  4945.9  340.18  4966.4  334.16  4976.7  328.79  4983.8  326.77  4984.3  326.27
    4990  326.77  5002.2  328.52  5007.5  336.23    5050  335.27  5058.8  332.61
  5069.1  332.83  5087.5  338.74  5225.8  340.92  5396.4  341.01  5534.7  347.58
  5577.4  350.71  5582.5  352.06  5602.9  351.13  5638.2     352    5650  352.82
#Mann= 5 ,-1 , 0
  4502.7     .07       0    4841     .12       0  4983.8     .05       0
    4990     .12       0  5638.2    .063       0
Bank Sta=4983.8,4990
XS Rating Curve= 0 ,0
Exp/Cntr=0.3,0.1

Type RM Length L Ch R = 1 ,22035   ,385,385,385
BEGIN DESCRIPTION:
A19698
END DESCRIPTION:
XS GIS Cut Line= 3
      2521233.93     13734834.66      2521837.77     13734606.29
      2522348.64     13734346.98
#Sta/Elev= 30
  4526.7  362.66  4720.3  356.55  4784.4  352.95    4847  346.48  4852.4  348.95
  4859.3  346.84  4890.7  346.98  4955.5  335.41  4976.9  334.06  4995.2  325.39
  4995.7  324.89  5001.4  325.39    5009  327.15  5017.4  333.38  5030.3   334.3
  5115.9  332.04  5162.9  336.31  5230.6  335.53  5262.3  337.32  5275.1  335.97
    5289   330.7  5297.4  328.87  5326.2  336.64  5374.3  337.95  5486.3  340.87
  5495.1  341.12  5598.3  348.15  5701.2  351.49  5710.3  352.08  5745.2  353.76
#Mann= 12 ,-1 , 0
  4526.7     .07       0  4890.7     .12       0  4995.2     .05       0
  5001.4     .12       0  5262.3    .063       0    5289     .12       0
  5374.3    .063       0  5486.3     .07       0  5495.1    .063       0
  5598.3    .035       0  5701.2    .063       0  5710.3    .035       0
Bank Sta=4995.2,5001.4
XS Rating Curve= 0 ,0
Exp/Cntr=0.3,0.1

Type RM Length L Ch R = 1 ,21650   ,391,391,391
BEGIN DESCRIPTION:
A19697
END DESCRIPTION:
XS GIS Cut Line= 3
      2521264.94      13735012.7      2521744.87     13734970.13
      2522379.67     13734505.64
#Sta/Elev= 30
  4213.1  356.27  4393.9  351.23  4444.1  347.39  4468.6  346.81  4560.5  342.33
  4581.4  340.55  4586.4  341.46  4614.7  337.48  4659.6  337.52  4741.3  335.37
  4775.1  335.24  4899.2  333.91  4901.8  333.75    4970  331.72  4984.6  328.33
  4992.5  323.34  4996.2  322.63  4996.7  322.13  5002.5  322.63  5005.5   324.8
  5024.2  329.63    5042  332.23  5062.3  332.81  5099.7  332.68  5149.9  337.61
  5191.6  338.53  5235.6  342.84  5342.1  346.66  5397.8  349.91  5481.5  352.73
#Mann= 13 ,-1 , 0
  4213.1     .07       0  4468.6     .12       0  4560.5    .035       0
  4659.6     .07       0  4741.3    .035       0  4775.1     .07       0
  4899.2      .1       0  4901.8     .07       0  4996.2     .05       0
  5002.5     .07       0  5024.2      .1       0  5062.3     .07       0
  5397.8    .035       0
Bank Sta=4996.2,5002.5
XS Rating Curve= 0 ,0
Exp/Cntr=0.3,0.1

Type RM Length L Ch R = 1 ,21259   ,294,294,294
BEGIN DESCRIPTION:
A19696
END DESCRIPTION:
XS GIS Cut Line= 3
      2521284.23     13735043.66        2522070.     13735152.05
      2522565.43     13735183.01
#Sta/Elev= 30
  4351.4  354.76  4412.7  351.86  4533.9   348.9  4554.1  346.88  4579.2  346.37
  4613.5  343.14  4618.5  339.34  4644.9  340.06  4678.2  338.48  4786.2  335.69
  4806.4  333.98  4834.3  333.77  4846.8  332.06    4888  331.28  4906.2  330.55
  4911.3  331.84  4947.8  329.97  4967.9  331.12  4988.2  329.82  4998.2  321.69
  5005.1  320.98  5005.6  320.48  5011.5  320.98  5028.5  328.36  5038.6  329.66
  5132.1  330.68  5271.5  341.06    5370  344.46  5510.3  350.25    5641   358.6
#Mann= 8 ,-1 , 0
  4351.4     .07       0  4579.2    .035       0  4678.2     .07       0
    4888      .1       0  5005.1     .05       0  5011.5      .1       0
  5271.5     .12       0    5370     .07       0
Bank Sta=5005.1,5011.5
XS Rating Curve= 0 ,0
Exp/Cntr=0.3,0.1

Type RM Length L Ch R = 1 ,20965   ,467,467,467
BEGIN DESCRIPTION:
LIVEOAK BRANCH 37.0
END DESCRIPTION:
XS GIS Cut Line= 3
      2521674.97       13735425.        2521925.       13735425.
      2522175.02       13735475.
#Sta/Elev= 30
  4754.5  340.35  4784.5  339.42  4789.9  338.85  4804.5   337.3  4814.5  335.63
  4834.5  333.44  4894.2  327.94  4904.5  326.77  4914.5  326.85  4934.5  328.52
  4944.5  328.41  4954.5  327.85  4964.5  326.03  4971.3  320.28  4971.8  319.78
  4977.2  319.78  4977.7  320.28  4984.5  322.02  4994.5  326.87  5024.9  329.34
  5035.1  329.42  5055.5   330.8  5065.7  330.34  5086.1  328.58  5126.9  330.51
  5137.1   332.3  5147.3  332.89  5167.7  333.17  5211.9  335.29  5259.5  337.27
#Mann= 6 ,-1 , 0
  4754.5     .07       0  4789.9      .1       0  4894.2     .12       0
  4971.3     .05       0  4977.7     .12       0  5211.9     .12       0
Bank Sta=4971.3,4977.7
XS Rating Curve= 0 ,0
Exp/Cntr=0.3,0.1

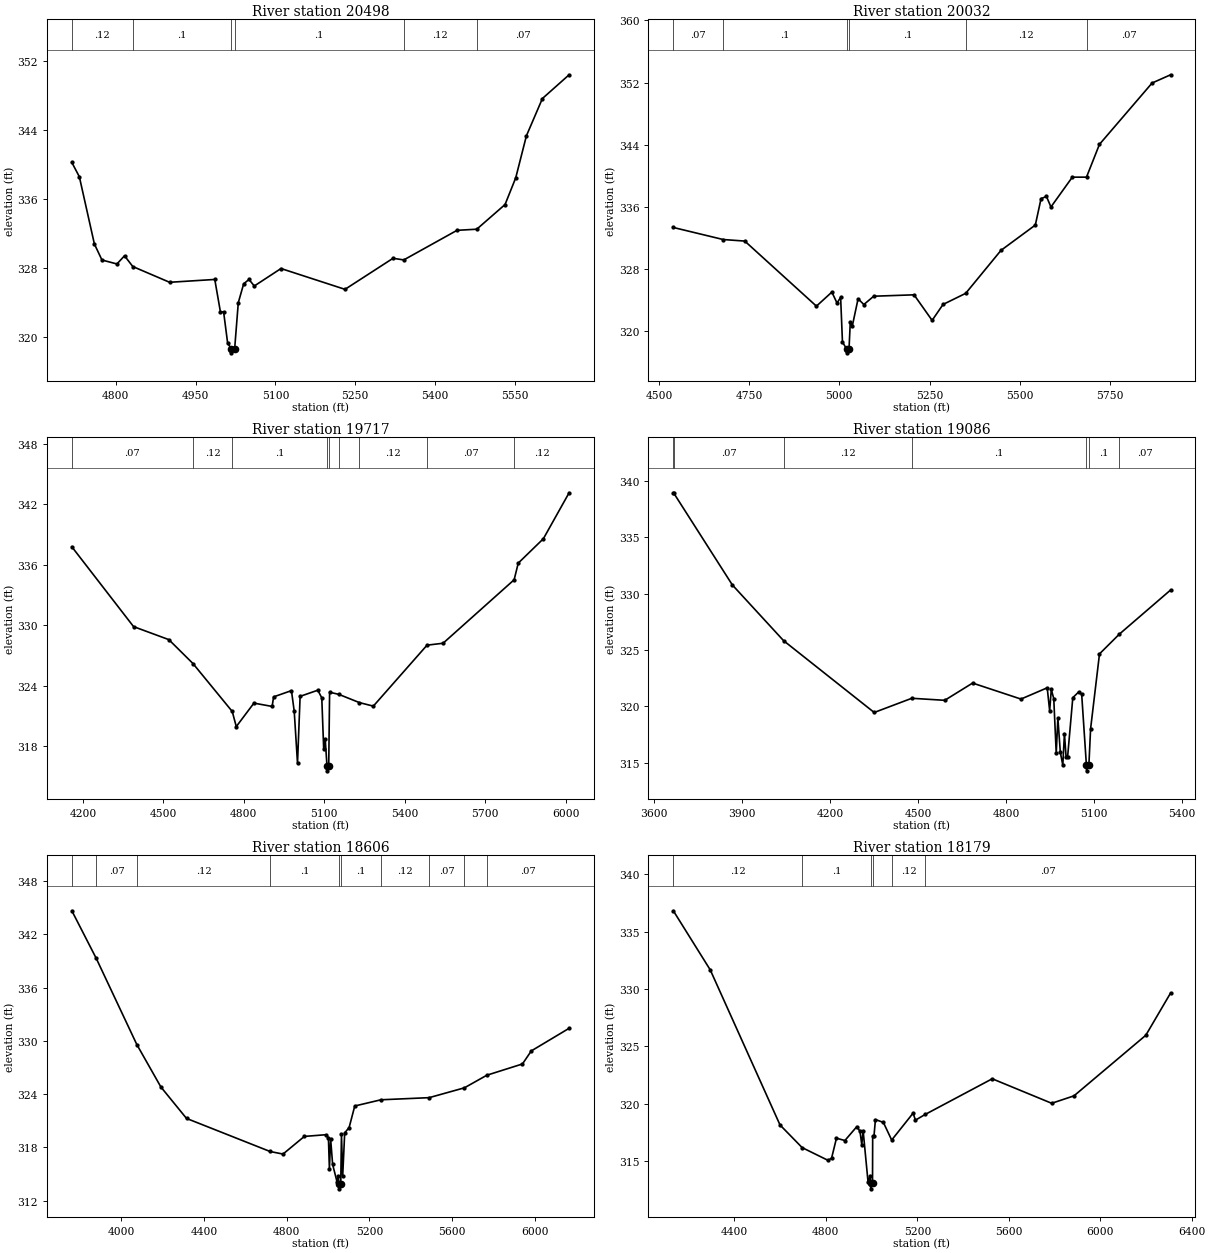
Type RM Length L Ch R = 1 ,20498   ,466,466,466
BEGIN DESCRIPTION:
LIVEOAK BRANCH 36.0
END DESCRIPTION:
XS GIS Cut Line= 3
      2521525.01     13735625.01        2521725.       13735825.
      2522375.05       13735775.
#Sta/Elev= 30
  4717.3  340.25  4731.4  338.59  4759.7  330.77  4773.9  328.91  4802.1  328.45
  4816.3   329.4  4831.9  328.15  4901.1  326.32    4986  326.65  4996.6  322.88
  5002.6  322.88  5010.2  319.24  5016.9  318.62  5017.4  318.12  5023.4  318.62
  5030.2  323.95  5040.3  326.14  5050.3  326.65  5060.3  325.89  5110.5  327.92
  5230.8   325.5  5321.1  329.11  5341.3  328.92  5441.4  332.36  5478.5  332.49
  5531.7  335.36  5551.8  338.47  5571.8  343.34  5601.9  347.68  5652.1  350.44
#Mann= 6 ,-1 , 0
  4717.3     .12       0  4831.9      .1       0  5016.9     .05       0
  5023.4      .1       0  5341.3     .12       0  5478.5     .07       0
Bank Sta=5016.9,5023.4
XS Rating Curve= 0 ,0
Exp/Cntr=0.3,0.1

Type RM Length L Ch R = 1 ,20032   ,315,315,315
BEGIN DESCRIPTION:
LIVEOAK BRANCH 35.0
END DESCRIPTION:
XS GIS Cut Line= 3
      2521374.97     13735924.97        2521675.       13736275.
      2522475.01       13735825.
#Sta/Elev= 30
  4539.6  333.35  4677.7   331.8  4737.7   331.6  4936.4  323.22  4979.2  325.03
  4993.5  323.62  5003.5  324.36  5008.6  318.59  5020.3  317.71  5020.8  317.21
  5026.8  317.71  5030.3  321.19    5036  320.69  5051.9  324.17  5067.9  323.43
  5095.3   324.5  5207.1  324.68  5257.2  321.39  5287.5  323.44  5350.3  324.87
  5448.1   330.4  5543.4  333.66  5559.3  337.07  5574.3  337.34  5586.7  335.99
    5646  339.83  5685.3  339.83  5721.2  344.05  5867.2  351.95  5918.5  353.01
#Mann= 6 ,-1 , 0
  4539.6     .07       0  4677.7      .1       0  5020.3     .05       0
  5026.8      .1       0  5350.3     .12       0  5685.3     .07       0
Bank Sta=5020.3,5026.8
XS Rating Curve= 0 ,0
Exp/Cntr=0.3,0.1

Type RM Length L Ch R = 1 ,19717   ,631,631,631
BEGIN DESCRIPTION:
A19695
END DESCRIPTION:
XS GIS Cut Line= 3
      2521180.11     13735878.96      2521524.93      13736520.7
      2522520.47     13737047.19
#Sta/Elev= 30
  4158.4   337.8  4388.6  329.88  4520.1  328.59  4610.4  326.21  4756.7  321.46
  4771.7  319.96  4837.5  322.29  4905.4  321.96    4911  322.91  4977.5  323.53
  4987.8  321.49  5000.1  316.32  5009.8  322.96  5075.8  323.57  5090.6  322.81
  5097.8  317.71  5103.5   318.7    5110  316.07  5110.5  315.57  5116.5  316.07
  5119.8  323.37    5154  323.16  5231.1  322.34  5282.9  321.99  5483.2  328.04
    5543  328.23  5808.1  334.53  5823.4  336.18  5917.1   338.6  6013.1  343.16
#Mann= 9 ,-1 , 0
  4158.4     .07       0  4610.4     .12       0  4756.7      .1       0
    5110     .05       0  5116.5      .1       0    5154     .07       0
  5231.1     .12       0  5483.2     .07       0  5808.1     .12       0
Bank Sta=5110,5116.5
XS Rating Curve= 0 ,0
Exp/Cntr=0.3,0.1

Type RM Length L Ch R = 1 ,19086   ,480,480,480
BEGIN DESCRIPTION:
LIVEOAK BRANCH 34.0
END DESCRIPTION:
XS GIS Cut Line= 3
        2521075.       13735875.        2521675.       13737075.
      2522025.01       13737125.
#Sta/Elev= 30
  3664.9  338.94  3665.6  338.94  3866.1  330.76  4040.9  325.81  4349.7  319.44
  4477.8   320.7  4590.1  320.52  4685.1  322.05    4850  320.63  4939.5  321.63
  4947.8  319.59  4953.4  321.48  4961.8  320.67  4970.2  315.82  4975.8  318.94
  4984.2   315.9  4992.6  314.77  4998.2  317.57  5003.7  315.53  5009.1  315.53
  5026.7  320.75  5046.9  321.27    5057  321.05  5073.1  314.76  5073.6  314.26
  5081.5  314.76  5087.4     318  5117.7  324.64  5185.3  326.39  5360.1  330.31
#Mann= 7 ,-1 , 0
  3664.9     .12       0  3665.6     .07       0  4040.9     .12       0
  4477.8      .1       0  5073.1     .05       0  5081.5      .1       0
  5185.3     .07       0
Bank Sta=5073.1,5081.5
XS Rating Curve= 0 ,0
Exp/Cntr=0.3,0.1

Type RM Length L Ch R = 1 ,18606   ,427,427,427
BEGIN DESCRIPTION:
LIVEOAK BRANCH 33.0
END DESCRIPTION:
XS GIS Cut Line= 3
        2520925.     13735774.98        2521225.       13736975.
      2521824.98     13737974.96
#Sta/Elev= 30
    3762  344.67    3880   339.3    4076  329.59  4192.4   324.8  4316.1  321.26
    4720  317.53  4782.5  317.24  4885.6  319.23  4988.6  319.42  5001.9  319.08
  5006.7  315.58  5012.6  318.95  5022.3  316.07  5043.7   314.1  5049.5   314.8
  5053.1  313.82  5053.6  313.32  5061.5  313.82    5065  319.45  5070.9  314.76
  5080.6  319.63    5102  320.23  5129.2  322.66  5255.7  323.36  5488.8   323.6
  5659.2  324.71  5767.5  326.13  5939.7   327.4  5982.4  328.87  6165.1  331.42
#Mann= 10 ,-1 , 0
    3762     .12       0    3880     .07       0    4076     .12       0
    4720      .1       0  5053.1     .05       0  5061.5      .1       0
  5255.7     .12       0  5488.8     .07       0  5659.2     .12       0
  5767.5     .07       0
Bank Sta=5053.1,5061.5
XS Rating Curve= 0 ,0
Exp/Cntr=0.3,0.1

Type RM Length L Ch R = 1 ,18179   ,469,469,469
BEGIN DESCRIPTION:
LIVEOAK BRANCH 32.0
END DESCRIPTION:
XS GIS Cut Line= 3
      2520424.98     13736124.97        2520875.       13736875.
      2521375.01     13738075.02
#Sta/Elev= 30
  4132.9  336.83  4294.3  331.67  4599.4  318.13  4696.2  316.15  4809.3  315.04
  4824.9  315.22  4846.3  316.97  4883.2  316.77  4935.7  317.99  4949.3  317.56
    4957  316.41  4962.9  317.64  4984.3  313.18    4994   313.7  4995.6  313.05
  4996.1  312.55    5004  313.05  5004.7  317.14  5010.3  317.14  5016.8   318.6
  5051.5  318.35  5087.8  316.81  5181.5  319.16  5191.7  318.55  5235.7  319.06
  5527.6  322.16  5787.6  320.02  5885.1  320.67  6199.2  325.96  6307.6  329.65
#Mann= 6 ,-1 , 0
  4132.9     .12       0  4696.2      .1       0  4995.6     .05       0
    5004      .1       0  5087.8     .12       0  5235.7     .07       0
Bank Sta=4995.6,5004
XS Rating Curve= 0 ,0
Exp/Cntr=0.3,0.1