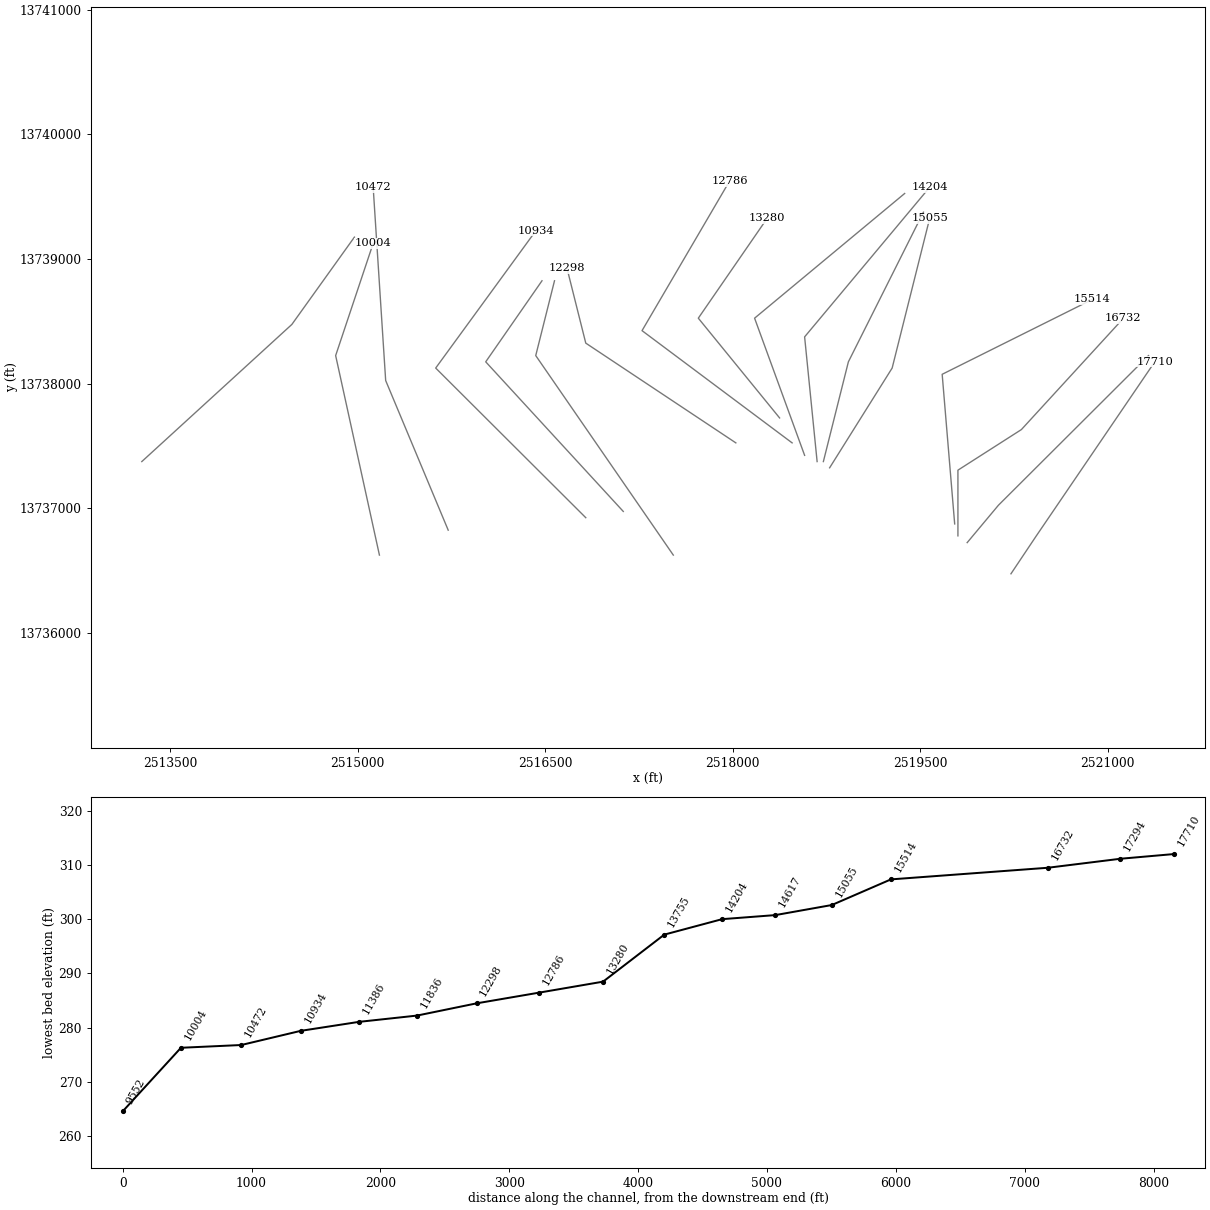
HEC-RAS study LIVEOAK BRANCH.prj: LIVEOAK BRANCH Base Level Engineering

--- LIVEOAK BRANCH.g01 (geometry) --- (continued)

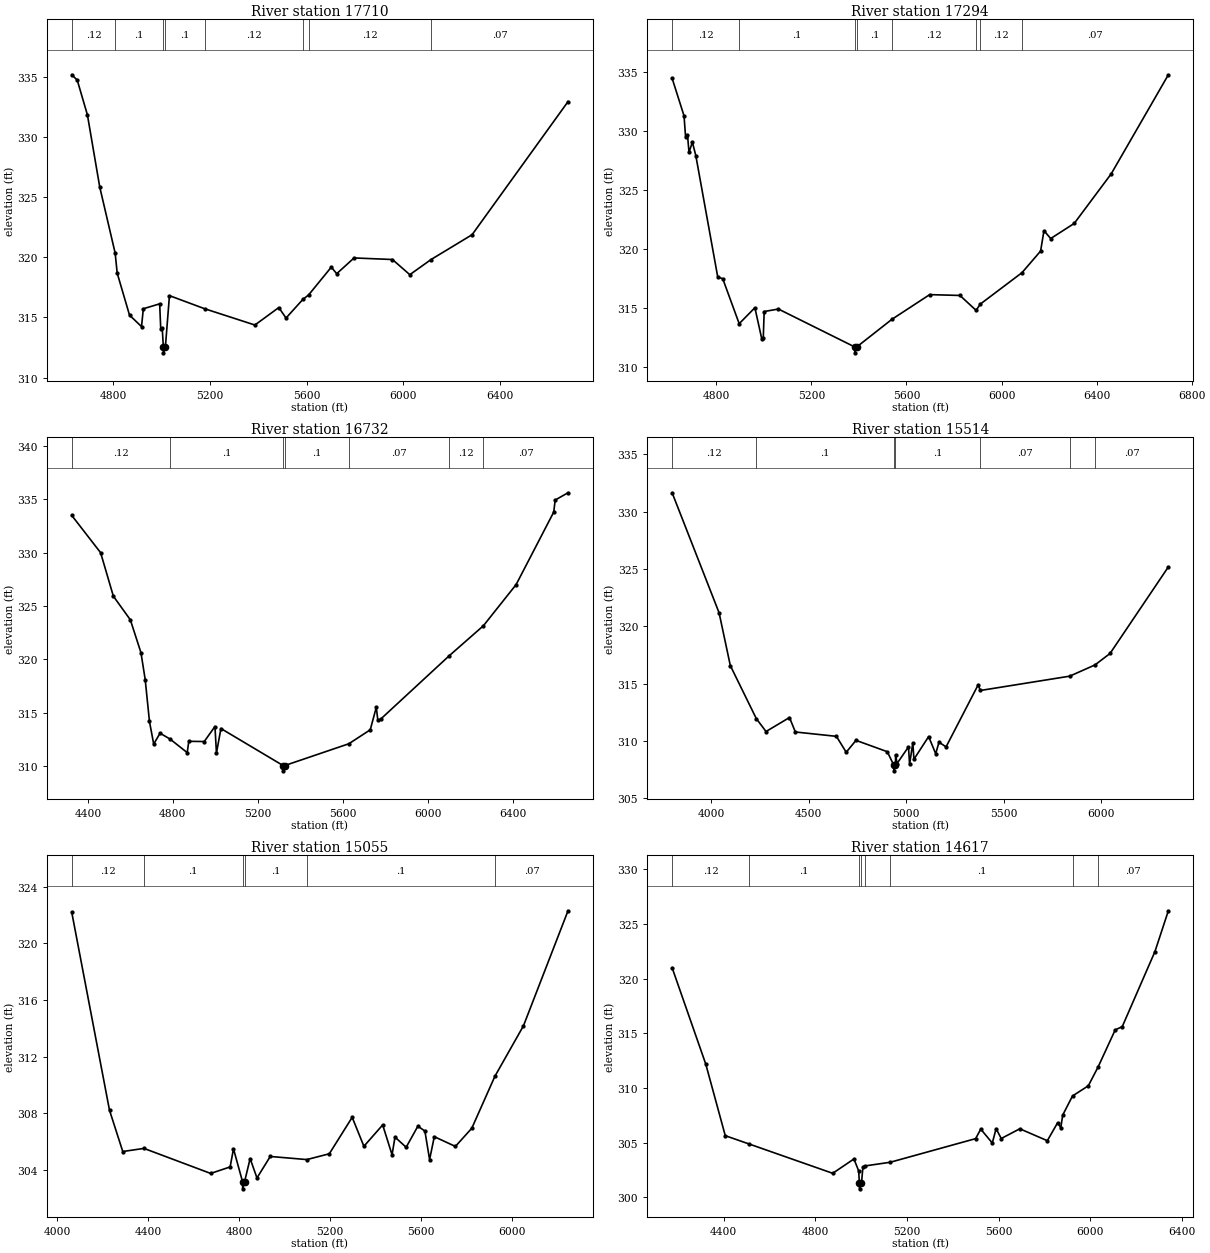
Type RM Length L Ch R = 1 ,17710   ,416,416,416
BEGIN DESCRIPTION:
LIVEOAK BRANCH 31.0
END DESCRIPTION:
XS GIS Cut Line= 3
      2520225.02     13736475.03        2520425.       13736775.
      2521374.99     13738174.99
#Sta/Elev= 30
  4628.2  335.15  4650.7  334.71  4692.8  331.82  4743.8  325.83  4807.6  320.34
    4816  318.68    4867  315.19  4916.6  314.24  4924.1  315.72  4991.7  316.13
  4996.2     314  5002.2  314.12  5006.9  312.56  5007.4  312.06  5015.4  312.56
  5032.1  316.81  5178.1  315.72  5385.5  314.37  5484.4  315.82  5514.3  314.95
  5583.6  316.49  5607.8  316.87  5701.7  319.18  5723.8  318.63  5795.7  319.94
  5954.4  319.81  6026.3  318.55  6114.3  319.81  6283.9  321.87  6680.6  332.92
#Mann= 8 ,-1 , 0
  4628.2     .12       0  4807.6      .1       0  5006.9     .05       0
  5015.4      .1       0  5178.1     .12       0  5583.6     .07       0
  5607.8     .12       0  6114.3     .07       0
Bank Sta=5006.9,5015.4
XS Rating Curve= 0 ,0
Exp/Cntr=0.3,0.1

Type RM Length L Ch R = 1 ,17294   ,562,562,562
BEGIN DESCRIPTION:
LIVEOAK BRANCH 30.0
END DESCRIPTION:
XS GIS Cut Line= 3
      2519874.98     13736724.98        2520125.       13737025.
        2521325.       13738225.
#Sta/Elev= 30
  4614.3  334.44  4664.4  331.26    4671  329.45  4678.8  329.67  4685.3  328.18
  4699.6  329.03  4713.9   327.9  4806.3   317.6  4827.2  317.47  4896.4  313.66
  4962.5  315.01  4991.2  312.39  4997.7  312.44  5001.6  314.69  5061.4   314.9
  5382.4  311.69  5382.9  311.19    5391  311.69    5539  314.03  5697.8  316.12
  5825.1  316.05    5893  314.79  5910.9  315.32  6086.2  317.98  6164.5  319.81
  6178.6  321.54  6206.9  320.87  6305.9  322.15  6461.5  326.35  6701.9  334.74
#Mann= 8 ,-1 , 0
  4614.3     .12       0  4896.4      .1       0  5382.4     .05       0
    5391      .1       0    5539     .12       0    5893     .07       0
  5910.9     .12       0  6086.2     .07       0
Bank Sta=5382.4,5391
XS Rating Curve= 0 ,0
Exp/Cntr=0.3,0.1

Type RM Length L Ch R = 1 ,16732   ,1218,1218,1218
BEGIN DESCRIPTION:
A19694
END DESCRIPTION:
XS GIS Cut Line= 4
      2519800.95     13736779.29      2519800.95     13737306.06
      2520308.57      13737631.7      2521122.69     13738522.45
#Sta/Elev= 30
  4324.4  333.49  4460.1     330  4520.1  325.92  4600.1   323.7  4650.1  320.62
  4670.1  318.09  4690.1  314.17  4710.1  312.04  4740.1  313.06  4787.2  312.51
  4867.9  311.24  4875.4   312.3  4948.1  312.28  4998.5  313.69  5005.6   311.2
  5026.7   313.5  5319.1  310.03  5319.6  309.53  5327.7  310.03  5628.9  312.07
  5729.8  313.38  5758.2  315.49  5765.6  314.27  5779.8   314.4  6101.2  320.32
  6262.4  323.14  6416.8  327.01  6593.8  333.81  6600.6  334.94    6661  335.62
#Mann= 7 ,-1 , 0
  4324.4     .12       0  4787.2      .1       0  5319.1     .05       0
  5327.7      .1       0  5628.9     .07       0  6101.2     .12       0
  6262.4     .07       0
Bank Sta=5319.1,5327.7
XS Rating Curve= 0 ,0
Exp/Cntr=0.3,0.1

Type RM Length L Ch R = 1 ,15514   ,459,459,459
BEGIN DESCRIPTION:
LIVEOAK BRANCH 29.0
END DESCRIPTION:
XS GIS Cut Line= 3
        2519775.     13736874.98        2519675.       13738075.
      2520874.98     13738674.99
#Sta/Elev= 30
  3799.9  331.64  4040.8  321.17  4098.5  316.56  4231.7  311.94  4281.6  310.81
    4402  312.03  4432.1  310.77  4642.8  310.39    4693     309  4743.2  310.04
  4903.7  309.05    4937  307.88  4937.5  307.38  4945.8  307.88  4946.4  308.78
  4953.9  308.02  5012.5  309.47  5018.1  307.95  5034.8  309.83  5040.4  308.39
  5115.9  310.37  5152.2  308.87    5169  309.88  5205.3  309.47  5370.2  314.89
  5380.8  314.39  5839.6  315.64  5969.3  316.62  6046.6  317.62  6345.7  325.17
#Mann= 7 ,-1 , 0
  3799.9     .12       0  4231.7      .1       0    4937     .05       0
  4945.8      .1       0  5380.8     .07       0  5839.6     .12       0
  5969.3     .07       0
Bank Sta=4937,4945.8
XS Rating Curve= 0 ,0
Exp/Cntr=0.3,0.1

Type RM Length L Ch R = 1 ,15055   ,438,438,438
BEGIN DESCRIPTION:
LIVEOAK BRANCH 28.0
END DESCRIPTION:
XS GIS Cut Line= 3
      2518775.02     13737325.03        2519275.       13738125.
        2519575.       13739325.
#Sta/Elev= 30
  4064.2  322.19  4229.9   308.2  4288.2  305.28  4381.3   305.5  4674.4  303.73
  4759.9  304.19  4774.7  305.47  4814.5  303.14    4815  302.64  4823.3  303.14
  4847.8  304.78  4877.9  303.41  4936.2  304.93    5097  304.71  5195.7  305.12
  5296.2   307.7  5347.7  305.65  5430.2  307.16  5471.4  305.05  5484.3   306.3
  5533.3  305.58  5584.8  307.07  5615.7  306.73  5636.3  304.71    5657  306.33
  5749.7  305.64  5821.9  306.93  5923.2   310.6  6048.7  314.17  6244.5  322.31
#Mann= 6 ,-1 , 0
  4064.2     .12       0  4381.3      .1       0  4814.5     .05       0
  4823.3      .1       0    5097      .1       0  5923.2     .07       0
Bank Sta=4814.5,4823.3
XS Rating Curve= 0 ,0
Exp/Cntr=0.3,0.1

Type RM Length L Ch R = 1 ,14617   ,413,413,413
BEGIN DESCRIPTION:
LIVEOAK BRANCH 27.0
END DESCRIPTION:
XS GIS Cut Line= 3
      2518724.99     13737374.96        2518925.       13738175.
        2519525.       13739375.
#Sta/Elev= 30
  4175.1  320.99    4322  312.18  4407.1  305.64  4509.8  304.89  4876.1   302.2
  4968.8  303.51  4989.5  302.42  4992.7  301.28  4993.2  300.78  5001.6  301.28
  5008.1  302.78  5016.1  302.87  5127.2  303.21  5500.1  305.37  5522.4  306.24
  5572.8  304.97  5589.5  306.28  5611.9  305.38  5692.9  306.27  5813.1  305.18
  5857.9  306.82  5871.8  306.36  5880.2  307.52    5923  309.27    5992   310.2
  6034.7  311.92  6109.4  315.31  6140.2  315.61  6282.7  322.46  6341.4   326.2
#Mann= 8 ,-1 , 0
  4175.1     .12       0  4509.8      .1       0  4992.7     .05       0
  5001.6      .1       0  5016.1     .12       0  5127.2      .1       0
    5923     .12       0  6034.7     .07       0
Bank Sta=4992.7,5001.6
XS Rating Curve= 0 ,0
Exp/Cntr=0.3,0.1

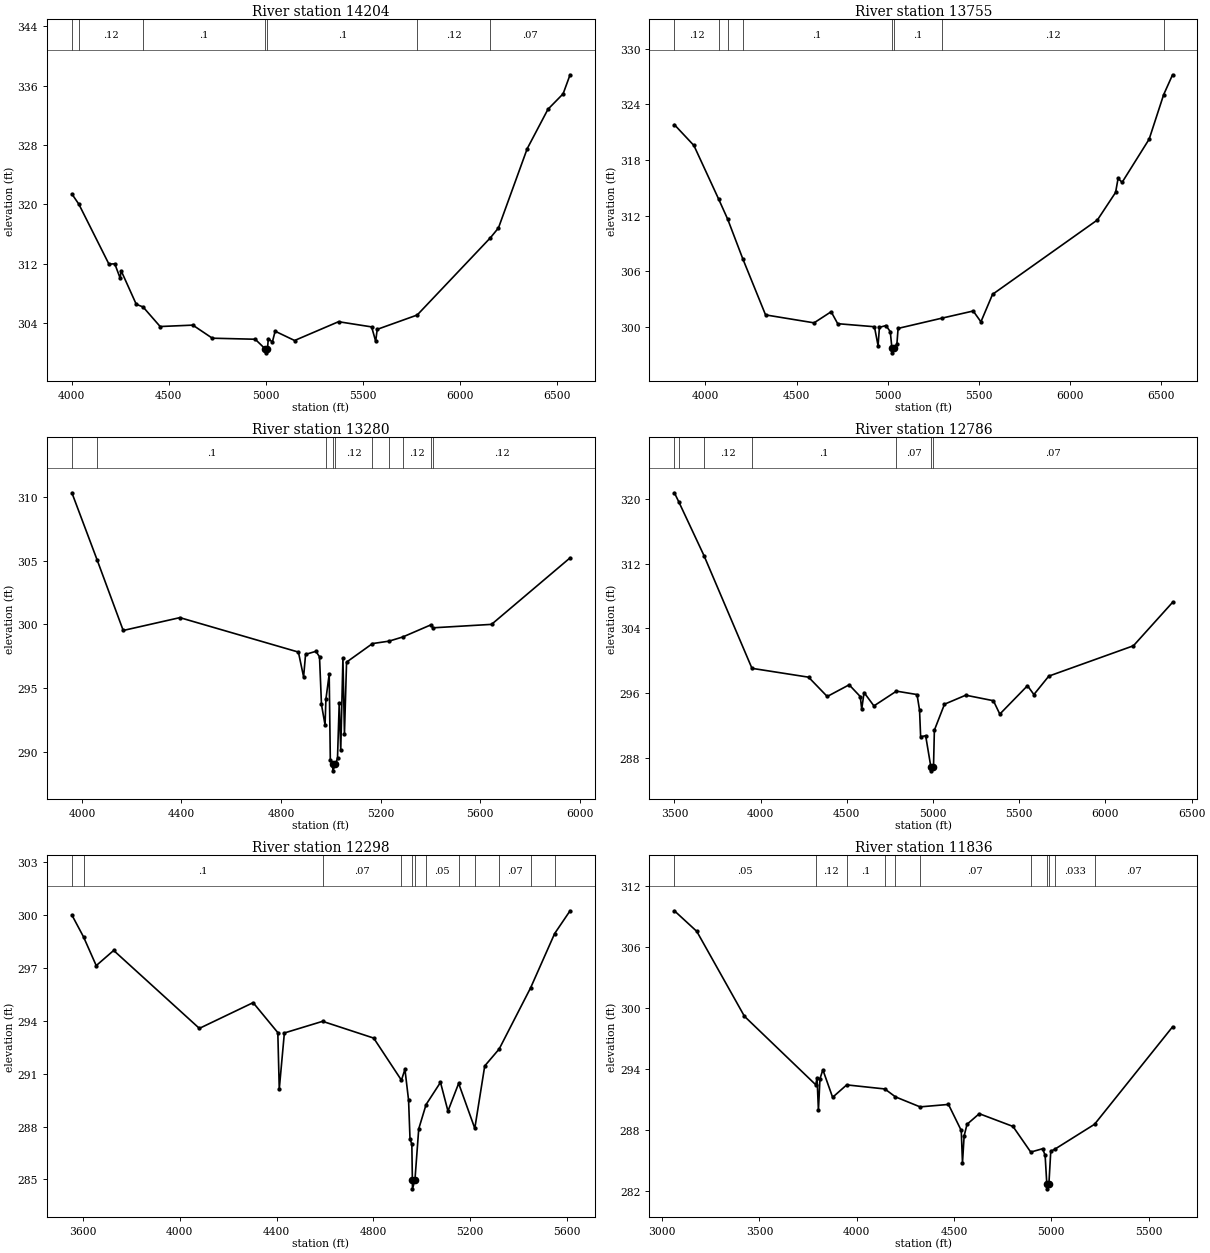
Type RM Length L Ch R = 1 ,14204   ,449,449,449
BEGIN DESCRIPTION:
LIVEOAK BRANCH 26.0
END DESCRIPTION:
XS GIS Cut Line= 3
        2518675.       13737375.        2518575.       13738375.
      2519574.98     13739574.97
#Sta/Elev= 30
  4000.3  321.41  4036.3  320.03  4191.2  311.97  4221.4  312.01    4249  310.07
  4254.1  311.08  4331.9  306.57  4367.2   306.2  4455.1  303.57  4623.4  303.76
  4723.9     302    4945  301.86  4997.5  300.53    4998  300.03    5008  300.53
  5012.4  301.94  5033.3  301.49  5047.6  302.94  5147.8  301.69  5374.3  304.22
  5544.8  303.52  5565.7  301.58  5573.5  303.19  5779.6  305.12  6157.3  315.53
  6198.3  316.84  6346.7  327.52  6453.4  332.81  6531.5  334.89  6567.3  337.45
#Mann= 7 ,-1 , 0
  4000.3     .07       0  4036.3     .12       0  4367.2      .1       0
  4997.5     .05       0    5008      .1       0  5779.6     .12       0
  6157.3     .07       0
Bank Sta=4997.5,5008
XS Rating Curve= 0 ,0
Exp/Cntr=0.3,0.1

Type RM Length L Ch R = 1 ,13755   ,475,475,475
BEGIN DESCRIPTION:
LIVEOAK BRANCH 25.0
END DESCRIPTION:
XS GIS Cut Line= 3
      2518575.01     13737424.97        2518175.       13738525.
      2519375.04     13739525.03
#Sta/Elev= 30
  3829.5  321.82  3936.6  319.57  4072.3  313.78  4122.1   311.6  4204.1  307.36
  4329.6  301.27  4595.7  300.41  4689.4  301.61  4725.3  300.32  4926.8  299.99
  4946.8  297.94  4954.1  299.92    4990  300.12  5013.7  299.46  5022.7  297.67
  5023.2  297.17  5033.2  297.67  5050.1  298.13  5056.6  299.81  5295.3  300.91
  5468.6  301.69  5510.9  300.52  5574.7  303.49  6150.1  311.53  6249.6   314.5
  6263.3  316.02  6285.4  315.59  6433.8  320.26  6513.2  325.06  6562.1  327.21
#Mann= 8 ,-1 , 0
  3829.5     .12       0  4072.3     .07       0  4122.1     .12       0
  4204.1      .1       0  5022.7     .05       0  5033.2      .1       0
  5295.3     .12       0  6513.2     .07       0
Bank Sta=5022.7,5033.2
XS Rating Curve= 0 ,0
Exp/Cntr=0.3,0.1

Type RM Length L Ch R = 1 ,13280   ,494,494,494
BEGIN DESCRIPTION:
LIVEOAK BRANCH 24.0
END DESCRIPTION:
XS GIS Cut Line= 3
      2518375.02     13737724.97        2517725.       13738525.
      2518274.98     13739324.97
#Sta/Elev= 30
  3959.8  310.35  4060.6   305.1    4166  299.52  4393.7  300.53  4869.9  297.82
  4890.8  295.87  4898.7  297.64  4940.3  297.88  4954.7  297.45  4962.6   293.7
    4977  292.08  4980.4  294.11  4993.6  296.08  4998.1  289.37  5007.7  288.98
  5008.2  288.48  5018.3  288.98    5027  289.47  5033.9  293.81    5040  290.09
  5048.8  297.35  5054.9  291.37  5063.4  297.03  5167.6  298.49  5233.9  298.68
  5289.4  299.01  5400.8  299.95  5411.3  299.73  5645.9     300  5961.4  305.23
#Mann= 10 ,-1 , 0
  3959.8     .12       0  4060.6      .1       0  4980.4     .12       0
  5007.7     .05       0  5018.3     .12       0  5167.6     .12       0
  5233.9     .07       0  5289.4     .12       0  5400.8     .07       0
  5411.3     .12       0
Bank Sta=5007.7,5018.3
XS Rating Curve= 0 ,0
Exp/Cntr=0.3,0.1

Type RM Length L Ch R = 1 ,12786   ,488,488,488
BEGIN DESCRIPTION:
LIVEOAK BRANCH 23.0
END DESCRIPTION:
XS GIS Cut Line= 3
      2518475.02     13737524.98        2517275.       13738425.
      2517975.01     13739625.03
#Sta/Elev= 30
    3500  320.72  3526.3  319.57  3671.7  312.98    3950  299.09  4278.2     298
  4386.5  295.62  4513.6  297.06  4578.2  295.61  4586.5  294.05    4600  296.11
  4657.3  294.46  4787.9  296.28  4907.3  295.86  4921.9  293.94  4928.2  290.66
  4957.3  290.79  4987.4  286.96  4987.9  286.46    4998  286.96  5002.9  286.97
  5007.9  291.47  5066.6  294.67  5189.8  295.78  5350.2   295.1  5387.4  293.45
  5547.9  296.95  5585.1  295.86  5671.5  298.13  6162.3  301.87  6389.3  307.22
#Mann= 7 ,-1 , 0
    3500     .12       0  3526.3     .07       0  3671.7     .12       0
    3950      .1       0  4787.9     .07       0  4987.4     .05       0
    4998     .07       0
Bank Sta=4987.4,4998
XS Rating Curve= 0 ,0
Exp/Cntr=0.3,0.1

Type RM Length L Ch R = 1 ,12298   ,462,462,462
BEGIN DESCRIPTION:
LIVEOAK BRANCH 22.0
END DESCRIPTION:
XS GIS Cut Line= 3
      2518025.01     13737524.99        2516825.       13738325.
        2516675.       13738925.
#Sta/Elev= 30
  3553.4     300  3601.5  298.76  3654.1  297.13  3726.2  297.99  4080.7  293.57
  4303.1  295.03  4405.2  293.33  4411.2  290.13  4432.3  293.31  4590.4  293.97
  4801.8  293.02  4916.6  290.63    4931  291.25  4946.1   289.5  4952.1  287.28
  4959.6  287.01  4961.8  284.97  4962.3  284.47  4972.4  284.97  4988.1  287.87
  5018.5  289.25  5078.1  290.51    5109  288.88  5153.2  290.45    5220   287.9
  5261.1  291.44  5320.8   292.4  5451.2  295.88  5550.4  298.95  5614.1  300.24
#Mann= 12 ,-1 , 0
  3553.4     .12       0  3601.5      .1       0  4590.4     .07       0
  4916.6    .033       0  4961.8    .033       0  4972.4    .033       0
  5018.5     .05       0  5153.2     .07       0    5220     .05       0
  5320.8     .07       0  5451.2     .12       0  5550.4     .07       0
Bank Sta=4961.8,4972.4
XS Rating Curve= 0 ,0
Exp/Cntr=0.3,0.1

Type RM Length L Ch R = 1 ,11836   ,450,450,450
BEGIN DESCRIPTION:
LIVEOAK BRANCH 21.0
END DESCRIPTION:
XS GIS Cut Line= 3
      2517524.99     13736625.01        2516425.       13738225.
        2516575.       13738825.
#Sta/Elev= 30
  3063.1  309.52  3178.1   307.5    3423  299.16  3789.1  292.44  3796.4  293.07
  3803.3  289.92  3811.3  293.03  3826.2   293.9  3876.2   291.2  3948.7  292.42
  4144.5  292.02  4199.4  291.24  4325.7  290.26  4471.6   290.5  4537.3  287.94
  4543.6  284.75  4552.1  287.41    4567  288.55  4629.9  289.59  4803.1  288.34
  4894.4  285.82  4955.4  286.15  4968.3   285.5  4976.9  282.71  4977.4  282.21
  4987.8  282.71  4997.3   285.9  5017.8   286.1  5222.2  288.55  5623.2  298.12
#Mann= 11 ,-1 , 0
  3063.1     .05       0  3789.1     .12       0  3948.7      .1       0
  4144.5     .07       0  4199.4     .12       0  4325.7     .07       0
  4894.4     .05       0  4976.9     .05       0  4987.8     .05       0
  5017.8    .033       0  5222.2     .07       0
Bank Sta=4976.9,4987.8
XS Rating Curve= 0 ,0
Exp/Cntr=0.3,0.1

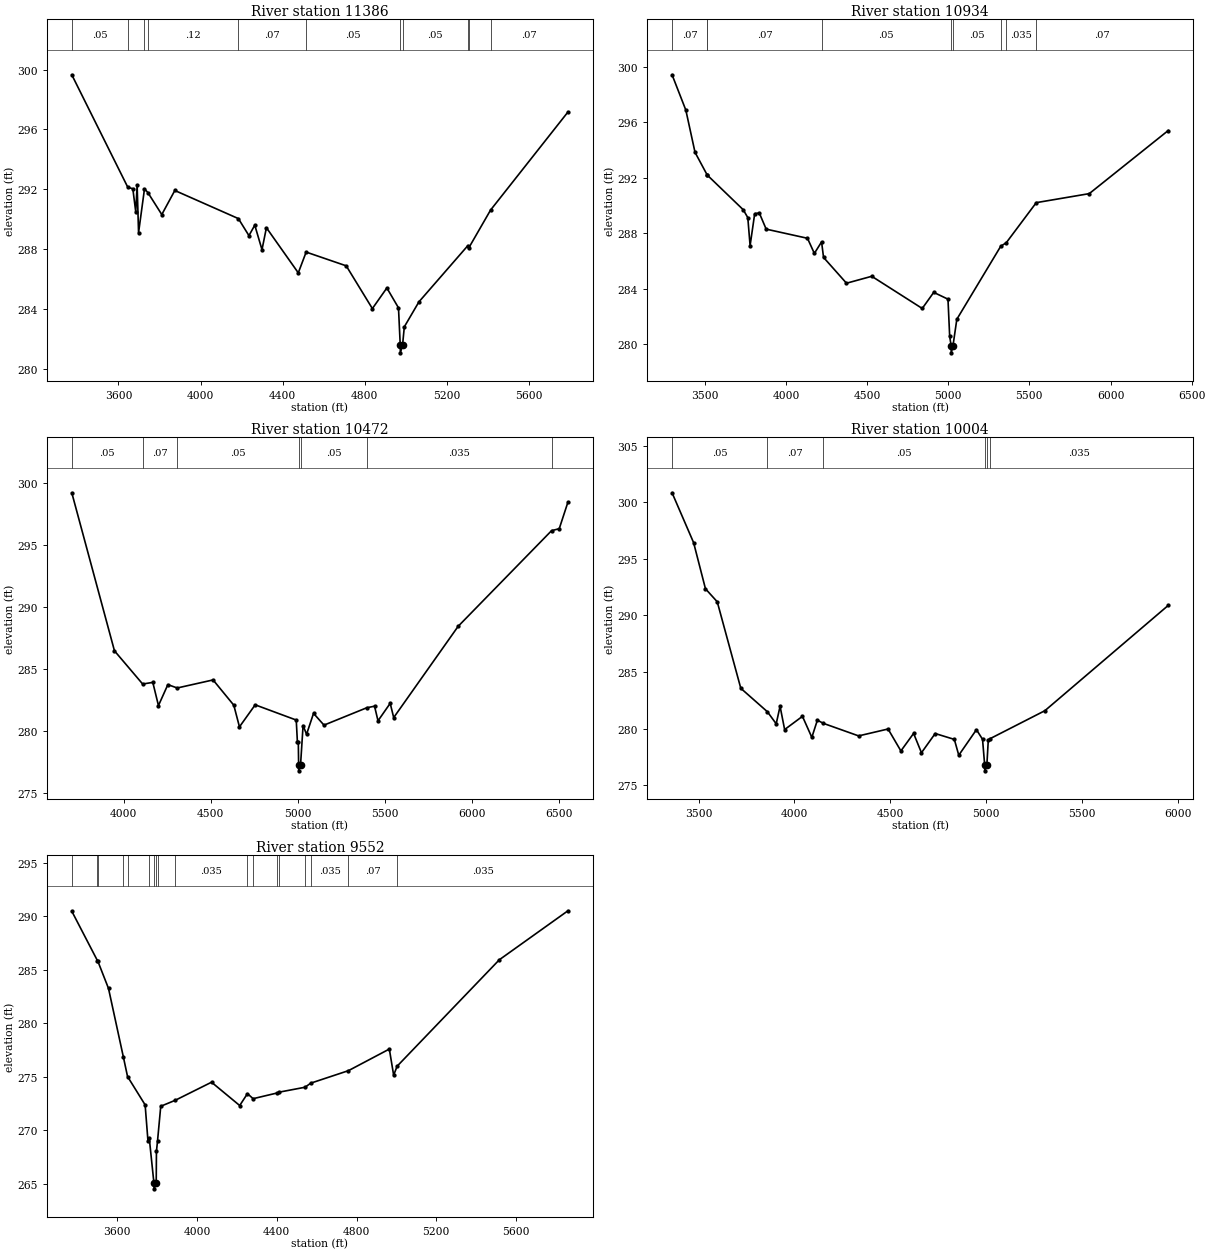
Type RM Length L Ch R = 1 ,11386   ,452,452,452
BEGIN DESCRIPTION:
LIVEOAK BRANCH 20.0
END DESCRIPTION:
XS GIS Cut Line= 3
      2517124.98     13736975.02        2516025.       13738175.
      2516474.99     13738824.99
#Sta/Elev= 30
  3372.6  299.65  3645.8  292.12  3670.1  292.03  3684.3  290.49  3691.1  292.25
  3698.1  289.09    3727  292.02  3743.5  291.77  3811.3   290.3  3874.8  291.91
  4184.6  290.03  4236.1  288.89  4264.5  289.59  4299.7  287.95  4321.2  289.42
  4476.6   286.4  4514.9  287.79  4710.3  286.87  4837.7  284.01  4908.3  285.39
    4965  284.06  4973.6  281.55  4974.1  281.05  4984.7  281.55  4993.4  282.79
  5064.6  284.46  5303.6  288.23  5308.4  288.09  5413.8   290.6    5791  297.16
#Mann= 11 ,-1 , 0
  3372.6     .05       0  3645.8     .12       0    3727     .07       0
  3743.5     .12       0  4184.6     .07       0  4514.9     .05       0
  4973.6     .05       0  4984.7     .05       0  5303.6     .07       0
  5308.4     .05       0  5413.8     .07       0
Bank Sta=4973.6,4984.7
XS Rating Curve= 0 ,0
Exp/Cntr=0.3,0.1

Type RM Length L Ch R = 1 ,10934   ,462,462,462
BEGIN DESCRIPTION:
LIVEOAK BRANCH 19.0
END DESCRIPTION:
XS GIS Cut Line= 3
        2516825.       13736925.        2515625.       13738125.
        2516425.       13739225.
#Sta/Elev= 30
  3298.4  299.44  3383.3  296.89  3439.8  293.85    3515  292.21  3515.9   292.2
  3736.8  289.71  3765.1  289.14  3779.2  287.12  3807.5  289.42  3835.8  289.48
  3878.2  288.31  4132.8  287.65  4175.2  286.56  4219.6  287.39  4231.8  286.27
  4373.2  284.41  4528.8  284.91  4839.9  282.59  4910.6  283.75  4998.5  283.26
    5009  280.57  5018.1  279.89  5018.6  279.39  5029.2  279.89    5053  281.81
  5323.8  287.08  5357.7  287.33  5542.5  290.22  5869.1  290.87  6355.6  295.42
#Mann= 9 ,-1 , 0
  3298.4     .07       0    3515     .12       0  3515.9     .07       0
  4219.6     .05       0  5018.1     .05       0  5029.2     .05       0
  5323.8     .07       0  5357.7    .035       0  5542.5     .07       0
Bank Sta=5018.1,5029.2
XS Rating Curve= 0 ,0
Exp/Cntr=0.3,0.1

Type RM Length L Ch R = 1 ,10472   ,468,468,468
BEGIN DESCRIPTION:
LIVEOAK BRANCH 18.0
END DESCRIPTION:
XS GIS Cut Line= 3
      2515725.02     13736824.96        2515225.       13738025.
        2515125.     13739575.03
#Sta/Elev= 30
  3700.5  299.22  3945.9  286.46    4108  283.78  4166.4  283.91  4198.9  282.04
    4253  283.73    4307  283.46    4513  284.11  4632.2  282.07  4664.7  280.32
  4755.2   282.1  4991.3  280.87  4997.8  279.13  5003.1  279.13    5005  277.27
  5005.5  276.77  5016.1  277.27  5030.6  280.43  5050.6  279.72  5090.7  281.41
  5150.9  280.46  5396.4  281.86  5441.5  281.99  5461.5  280.81  5531.6  282.22
  5551.7  281.07  5922.5  288.44  6459.5  296.16  6503.7  296.32  6553.8  298.47
#Mann= 7 ,-1 , 0
  3700.5     .05       0    4108     .07       0    4307     .05       0
    5005     .05       0  5016.1     .05       0  5396.4    .035       0
  6459.5     .07       0
Bank Sta=5005,5016.1
XS Rating Curve= 0 ,0
Exp/Cntr=0.3,0.1

Type RM Length L Ch R = 1 ,10004   ,452,452,452
BEGIN DESCRIPTION:
LIVEOAK BRANCH 17.0
END DESCRIPTION:
XS GIS Cut Line= 3
      2515175.01     13736624.97        2514825.       13738225.
      2515124.98     13739124.95
#Sta/Elev= 30
  3361.8  300.85  3474.1  296.44  3535.9  292.36  3597.3  291.21  3720.1  283.56
  3858.5  281.49  3904.7  280.42  3924.8  281.97  3948.6  279.91  4041.5  281.08
  4090.4  279.22  4119.3  280.74  4150.4  280.46  4334.3  279.35  4487.8  279.96
  4554.7  278.02  4620.9  279.57  4661.9  277.86  4733.5  279.56  4833.3  279.04
  4856.4  277.64  4948.5   279.9  4980.3  279.05  4991.5  276.76    4992  276.26
  5002.8  276.76  5010.2  278.96  5019.1   279.1  5305.4  281.58  5948.3  290.89
#Mann= 6 ,-1 , 0
  3361.8     .05       0  3858.5     .07       0  4150.4     .05       0
  4991.5     .05       0  5002.8     .05       0  5019.1    .035       0
Bank Sta=4991.5,5002.8
XS Rating Curve= 0 ,0
Exp/Cntr=0.3,0.1

Type RM Length L Ch R = 1 ,9552    ,479,479,479
BEGIN DESCRIPTION:
LIVEOAK BRANCH 16.0
END DESCRIPTION:
XS GIS Cut Line= 3
        2513275.       13737375.        2514475.       13738475.
      2514974.99     13739174.99
#Sta/Elev= 30
  3372.1  290.47  3500.4  285.86  3501.4  285.86  3556.2  283.25  3630.5  276.86
  3651.7  275.01  3739.9  272.36  3754.1  268.99  3760.7  269.24  3784.2  265.01
  3784.7  264.51  3795.5  265.01  3796.6  268.01    3802  268.97  3818.2  272.23
  3890.9  272.79  4072.9  274.48  4214.1   272.3    4253  273.41  4281.5  272.94
  4403.3  273.48  4411.7  273.55  4541.9  274.01  4570.1  274.39  4759.4  275.56
  4964.5  277.58  4986.1  275.14  5003.7  275.98  5516.1  285.93  5860.2  290.51
#Mann= 18 ,-1 , 0
  3372.1     .05       0  3500.4    .035       0  3501.4     .05       0
  3630.5    .035       0  3651.7     .05       0  3760.7    .035       0
  3784.2     .05       0  3795.5    .035       0    3802      .1       0
  3890.9    .035       0    4253     .07       0  4281.5    .035       0
  4403.3     .05       0  4411.7    .035       0  4541.9     .07       0
  4570.1    .035       0  4759.4     .07       0  5003.7    .035       0
Bank Sta=3784.2,3795.5
XS Rating Curve= 0 ,0
Exp/Cntr=0.3,0.1