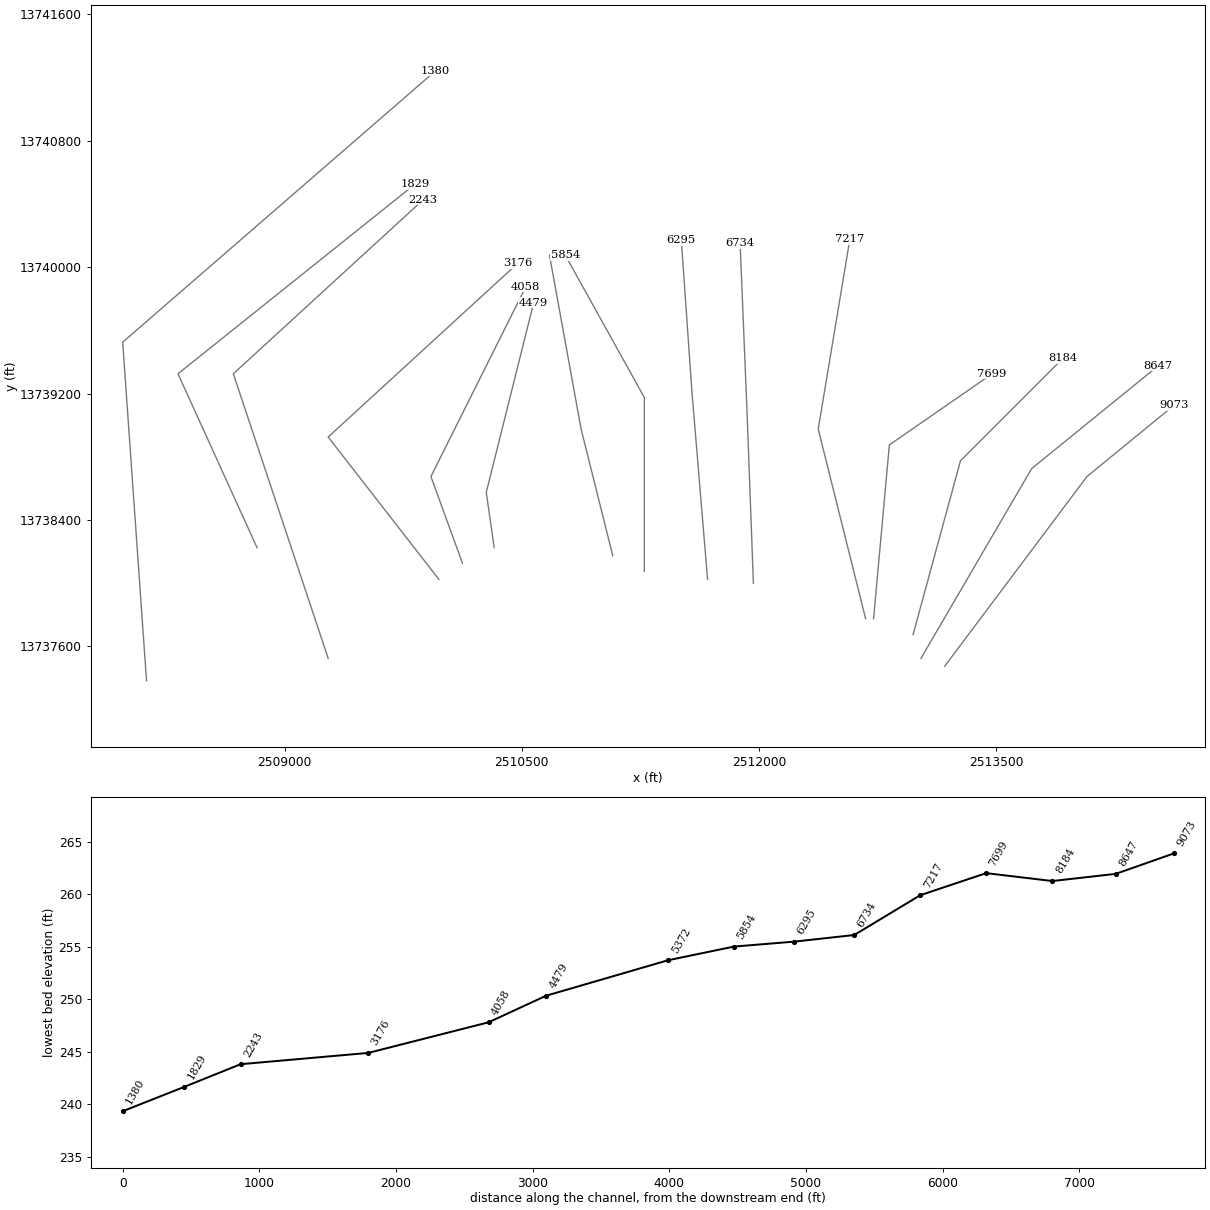
HEC-RAS study LIVEOAK BRANCH.prj: LIVEOAK BRANCH Base Level Engineering

--- LIVEOAK BRANCH.g01 (geometry) --- (continued)

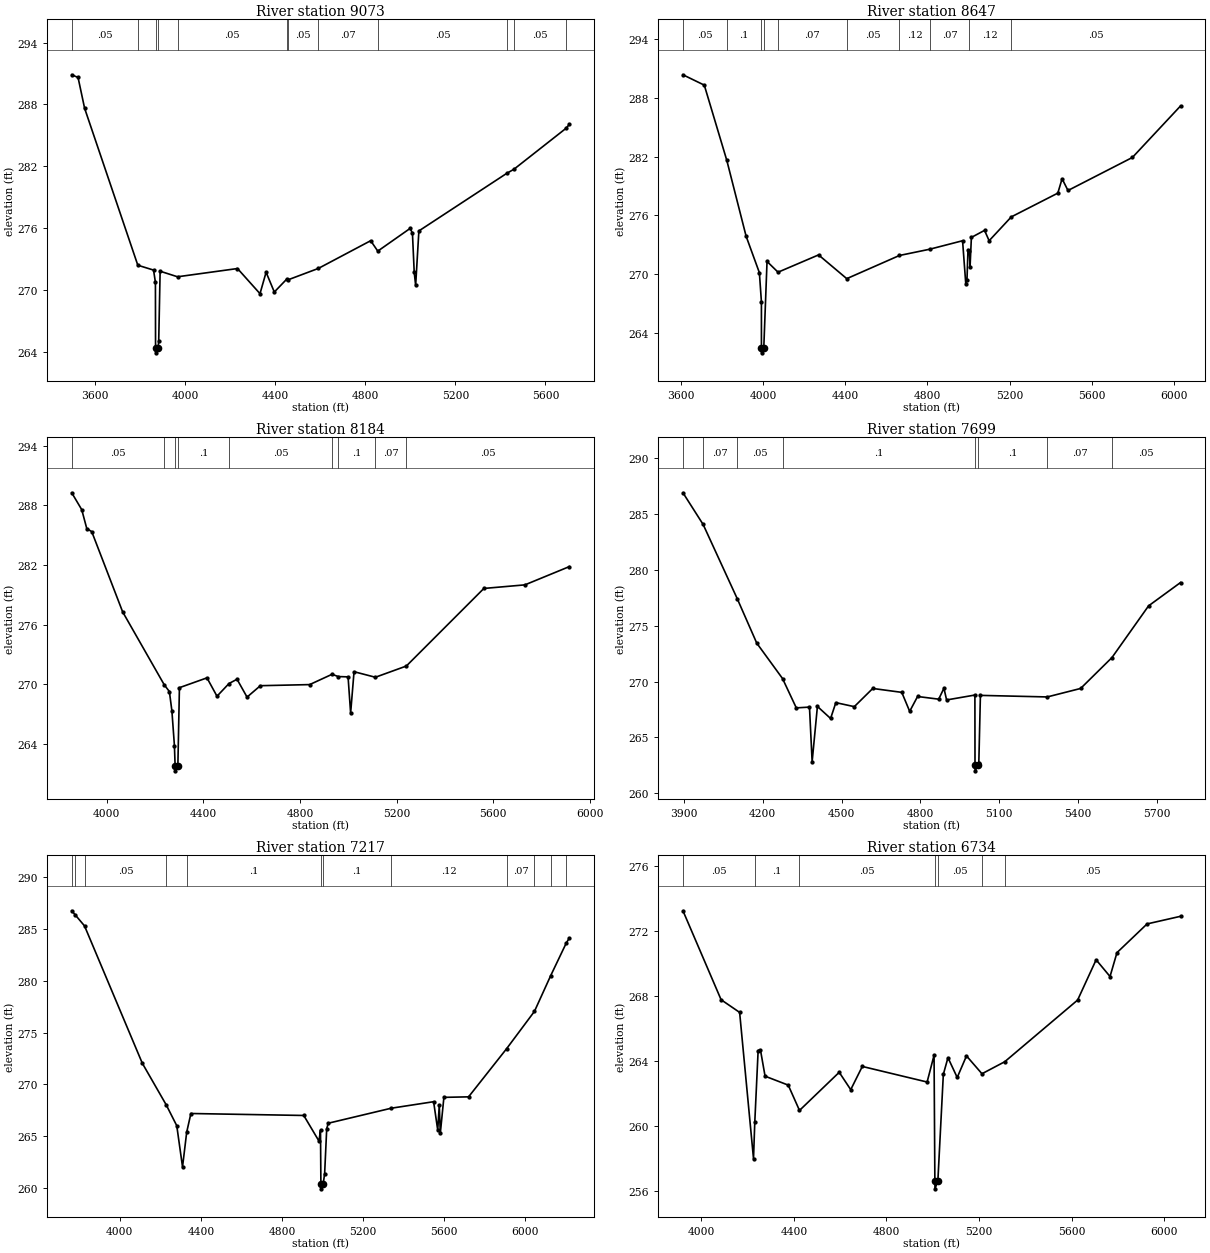
Type RM Length L Ch R = 1 ,9073    ,426,426,426
BEGIN DESCRIPTION:
LIVEOAK BRANCH 15.0
END DESCRIPTION:
XS GIS Cut Line= 3
      2513175.03     13737475.04        2514075.       13738675.
      2514625.01     13739125.01
#Sta/Elev= 30
  3495.6  290.87  3523.7  290.61  3552.8  287.62  3789.2  272.39  3859.1  271.92
  3867.4  270.73    3868  264.39  3868.5  263.89  3879.4  264.39    3882     265
  3888.3  271.81  3965.6  271.27    4232  272.07    4332  269.63  4359.1  271.71
  4395.6  269.79  4449.8  271.02  4457.3  270.98  4591.2  272.08  4823.7  274.77
  4855.3  273.76  4998.8  275.96  5009.2  275.52  5017.1  271.72  5023.5  270.44
  5037.9  275.72  5429.2  281.32    5460   281.7  5690.7  285.66  5706.2  286.05
#Mann= 12 ,-1 , 0
  3495.6     .05       0  3789.2      .1       0    3868     .05       0
  3879.4      .1       0  3965.6     .05       0  4449.8     .12       0
  4457.3     .05       0  4591.2     .07       0  4855.3     .05       0
  5429.2     .07       0    5460     .05       0  5690.7     .07       0
Bank Sta=3868,3879.4
XS Rating Curve= 0 ,0
Exp/Cntr=0.3,0.1

Type RM Length L Ch R = 1 ,8647    ,463,463,463
BEGIN DESCRIPTION:
LIVEOAK BRANCH 14.0
END DESCRIPTION:
XS GIS Cut Line= 3
      2513025.01     13737525.02        2513725.       13738725.
      2514525.01       13739375.
#Sta/Elev= 30
  3610.8  290.39  3714.6  289.33  3824.1  281.63    3918  273.87  3982.5  270.14
  3992.4  267.16  3992.5  262.44    3993  261.94  4003.9  262.44  4019.7  271.29
  4073.3  270.19  4270.3  271.96  4407.5  269.53  4663.5   271.9  4810.6  272.54
  4970.7  273.41  4986.4  268.98  4992.2  269.43  4997.1   272.5  5003.5  272.37
  5007.2  270.76  5013.6  273.75  5077.6  274.47  5099.9  273.41  5207.7  275.85
  5433.9  278.28  5454.7  279.75  5483.4  278.55  5796.6  281.93  6030.8   287.2
#Mann= 10 ,-1 , 0
  3610.8     .05       0  3824.1      .1       0  3992.5     .05       0
  4003.9      .1       0  4073.3     .07       0  4407.5     .05       0
  4663.5     .12       0  4810.6     .07       0  5003.5     .12       0
  5207.7     .05       0
Bank Sta=3992.5,4003.9
XS Rating Curve= 0 ,0
Exp/Cntr=0.3,0.1

Type RM Length L Ch R = 1 ,8184    ,485,485,485
BEGIN DESCRIPTION:
LIVEOAK BRANCH 13.0
END DESCRIPTION:
XS GIS Cut Line= 3
        2512975.     13737675.01        2513275.       13738775.
        2513925.       13739425.
#Sta/Elev= 30
  3855.2  289.28  3896.6  287.58  3917.4  285.68  3938.1  285.36  4065.9  277.28
  4238.1  269.93  4259.4  269.25  4269.8  267.29  4280.2   263.8  4283.1  261.76
  4283.6  261.26  4294.5  261.76  4300.9  269.64  4414.9  270.63  4456.4  268.78
  4506.2  270.06  4539.3  270.49  4580.8  268.69    4636  269.84  4839.9  269.95
  4932.7  270.99  4958.3  270.76  4998.9  270.73  5009.5  267.08  5023.6  271.25
  5111.9  270.69    5240  271.82    5561  279.64  5730.8     280  5914.6  281.84
#Mann= 9 ,-1 , 0
  3855.2     .05       0  4238.1      .1       0  4283.1     .05       0
  4294.5      .1       0  4506.2     .05       0  4932.7     .12       0
  4958.3      .1       0  5111.9     .07       0    5240     .05       0
Bank Sta=4283.1,4294.5
XS Rating Curve= 0 ,0
Exp/Cntr=0.3,0.1

Type RM Length L Ch R = 1 ,7699    ,482,482,482
BEGIN DESCRIPTION:
LIVEOAK BRANCH 12.0
END DESCRIPTION:
XS GIS Cut Line= 3
        2512725.     13737775.04        2512825.       13738875.
      2513475.03     13739325.02
#Sta/Elev= 30
  3895.9  286.92  3972.8  284.08  4102.5  277.44    4177  273.45  4275.1  270.28
  4327.6  267.65  4377.8  267.72  4387.9  262.83    4408  267.78  4458.2   266.7
  4478.2  268.12  4548.5  267.76  4618.8  269.39  4729.3  269.04  4759.4  267.34
  4789.5  268.67  4869.9  268.43  4889.9  269.41    4900  268.36  5007.8   268.8
  5008.2  262.51  5008.7  262.01  5019.6  262.51  5022.7  262.69  5028.8  268.77
  5283.3  268.63  5410.5  269.39  5529.9  272.16  5669.3  276.79    5791  278.88
#Mann= 8 ,-1 , 0
  3895.9     .05       0  3972.8     .07       0  4102.5     .05       0
  4275.1      .1       0  5008.2     .05       0  5019.6      .1       0
  5283.3     .07       0  5529.9     .05       0
Bank Sta=5008.2,5019.6
XS Rating Curve= 0 ,0
Exp/Cntr=0.3,0.1

Type RM Length L Ch R = 1 ,7217    ,483,483,483
BEGIN DESCRIPTION:
LIVEOAK BRANCH 11.0
END DESCRIPTION:
XS GIS Cut Line= 3
      2512674.99     13737775.03        2512375.       13738975.
      2512574.99     13740174.95
#Sta/Elev= 30
  3763.5  286.78  3779.6  286.41  3826.5  285.32  4111.4  272.05  4229.5  268.02
  4281.4  266.01  4309.8  262.03  4330.3  265.38    4351  267.19  4907.6     267
  4982.4  264.53  4990.1  265.56    4992  260.41  4992.5  259.91  5003.6  260.41
  5010.5  261.39  5020.7  265.72  5028.3  266.25  5338.6   267.7  5547.8  268.33
  5568.1  265.59  5575.7  267.99  5580.8  265.28  5598.5  268.75  5720.2   268.8
  5907.6  273.45    6045  277.06  6125.3  280.52  6202.3  283.68  6216.9  284.14
#Mann= 12 ,-1 , 0
  3763.5     .05       0  3779.6     .07       0  3826.5     .05       0
  4229.5     .07       0  4330.3      .1       0    4992     .05       0
  5003.6      .1       0  5338.6     .12       0  5907.6     .07       0
    6045     .05       0  6125.3     .07       0  6202.3     .05       0
Bank Sta=4992,5003.6
XS Rating Curve= 0 ,0
Exp/Cntr=0.3,0.1

Type RM Length L Ch R = 1 ,6734    ,439,439,439
BEGIN DESCRIPTION:
LIVEOAK BRANCH 10.0
END DESCRIPTION:
XS GIS Cut Line= 3
      2511964.86     13738000.21        2511925.       13739075.
      2511880.83     13740149.56
#Sta/Elev= 30
  3920.1  273.25    4085  267.77  4165.1  266.99  4225.1  257.98  4230.6  260.22
  4245.1  264.64  4255.1  264.68  4275.1  263.06  4375.2  262.51  4423.9  260.95
  4595.6   263.3  4645.4  262.23  4695.4  263.66  4975.6   262.7  5005.6  264.35
  5009.1  256.62  5009.6  256.12  5022.1  256.62  5045.7  263.17  5065.7   264.2
  5105.7  262.98  5145.8  264.31  5212.7  263.21  5311.1  263.95  5626.2  267.75
  5706.2  270.23  5766.3   269.2  5796.3  270.67  5926.4  272.44  6071.1  272.91
#Mann= 7 ,-1 , 0
  3920.1     .05       0  4230.6      .1       0  4423.9     .05       0
  5009.1     .05       0  5022.1     .05       0  5212.7     .07       0
  5311.1     .05       0
Bank Sta=5009.1,5022.1
XS Rating Curve= 0 ,0
Exp/Cntr=0.3,0.1

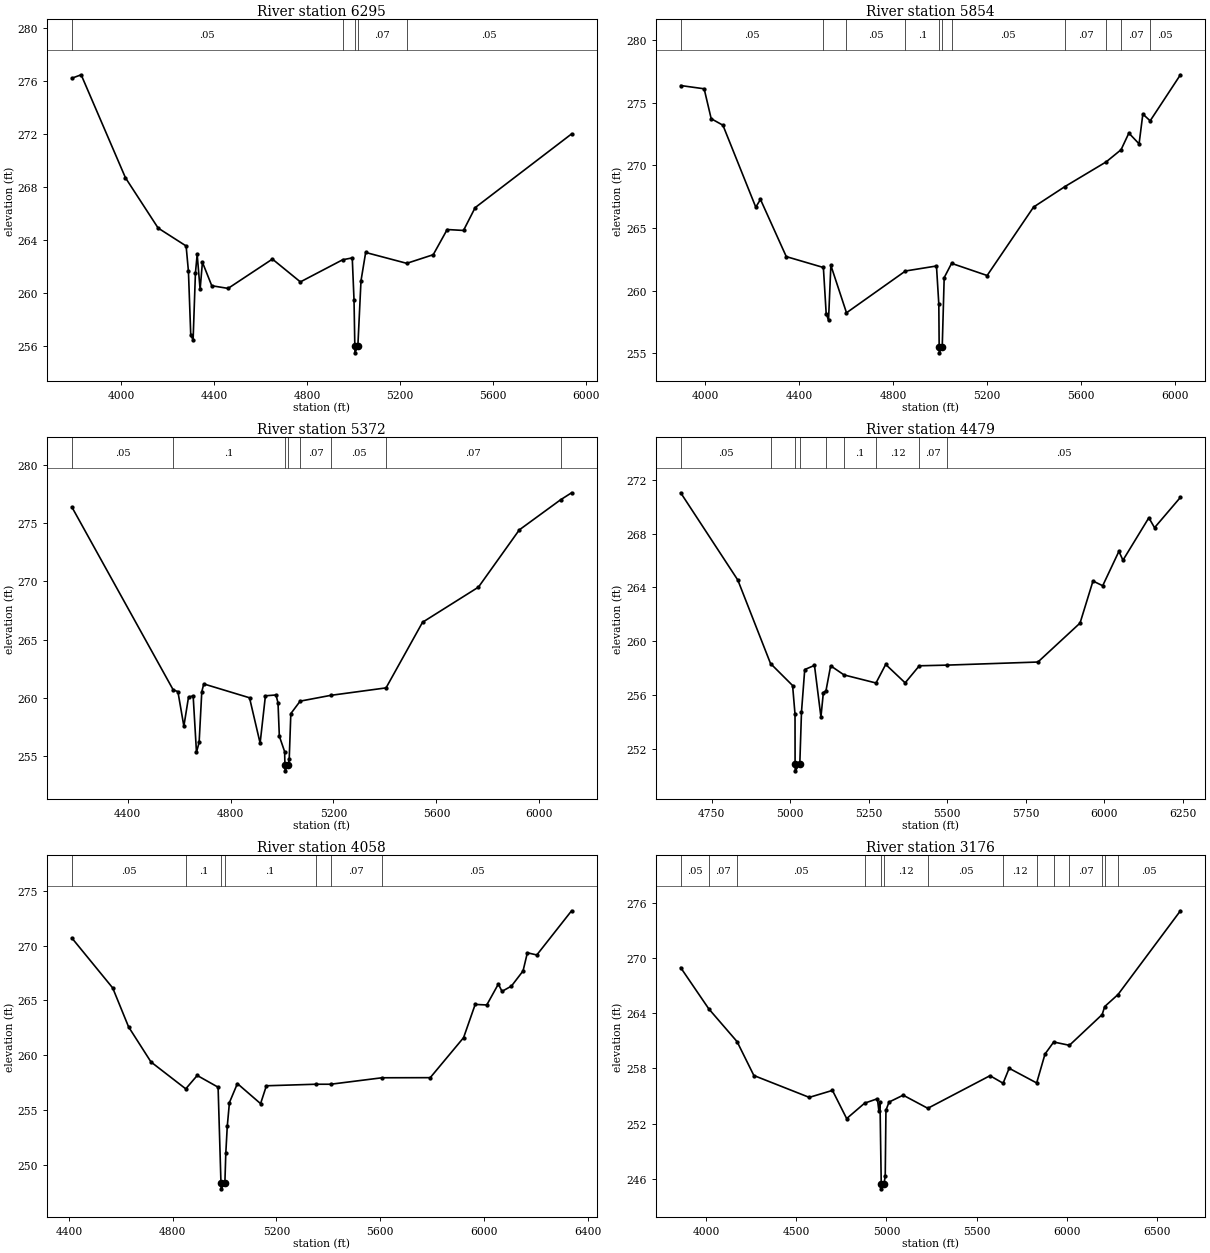
Type RM Length L Ch R = 1 ,6295    ,441,441,441
BEGIN DESCRIPTION:
LIVEOAK BRANCH 9.0
END DESCRIPTION:
XS GIS Cut Line= 3
        2511675.     13738025.02        2511575.       13739225.
      2511509.14     13740168.97
#Sta/Elev= 30
  3788.2   276.2  3828.3  276.46    4019  268.69  4159.5   264.9  4279.9  263.55
  4289.9  261.64  4299.9  256.81    4310  256.47    4320  261.51  4327.5  262.91
  4340.1  260.27  4350.1  262.32  4390.3  260.55  4460.5  260.35  4651.2  262.56
  4771.6  260.84  4953.6  262.51  4994.8  262.65  5002.4  259.48  5005.9  255.99
  5006.4  255.49  5018.9  255.99  5032.4  260.92  5052.5  263.06  5229.3  262.24
  5343.2  262.89  5403.3  264.79  5473.5  264.72  5523.6  266.44  5938.6     272
#Mann= 5 ,-1 , 0
  3788.2     .05       0  4953.6     .07       0  5005.9     .05       0
  5018.9     .07       0  5229.3     .05       0
Bank Sta=5005.9,5018.9
XS Rating Curve= 0 ,0
Exp/Cntr=0.3,0.1

Type RM Length L Ch R = 1 ,5854    ,482,482,482
BEGIN DESCRIPTION:
LIVEOAK BRANCH 8.0
END DESCRIPTION:
XS GIS Cut Line= 3
        2511275.     13738074.99        2511275.       13739175.
      2510774.98     13740075.03
#Sta/Elev= 30
  3894.9  276.38  3994.9  276.12  4024.9  273.73  4074.9  273.21  4214.9  266.66
  4234.9  267.28  4344.9  262.71    4503  261.84  4514.9  258.16  4524.9  257.62
  4534.9  262.01  4601.5  258.22  4852.8  261.56  4984.9  261.96  4994.9  258.91
  4996.4  255.52  4996.9  255.02  5009.5  255.52  5017.8  261.03  5049.3  262.17
  5200.8   261.2  5398.7  266.67  5532.6  268.31  5708.1  270.28  5771.5  271.25
  5804.8  272.58  5848.3  271.72  5864.3   274.1  5895.5  273.56  6024.5  277.24
#Mann= 11 ,-1 , 0
  3894.9     .05       0    4503     .07       0  4601.5     .05       0
  4852.8      .1       0  4996.4     .05       0  5009.5      .1       0
  5049.3     .05       0  5532.6     .07       0  5708.1     .05       0
  5771.5     .07       0  5895.5     .05       0
Bank Sta=4996.4,5009.5
XS Rating Curve= 0 ,0
Exp/Cntr=0.3,0.1

Type RM Length L Ch R = 1 ,5372    ,893,893,893
BEGIN DESCRIPTION:
LIVEOAK BRANCH 7.0
END DESCRIPTION:
XS GIS Cut Line= 3
      2511075.01     13738174.96        2510875.       13738975.
        2510675.     13740075.01
#Sta/Elev= 30
  4182.9   276.4  4576.9  260.68  4595.2  260.53  4618.4  257.56  4636.5  260.06
  4654.5  260.16  4667.4  255.32  4677.7  256.16    4688  260.51  4695.7  261.19
  4873.6     260  4914.8   256.1  4935.4  260.17  4976.6  260.24  4984.4  259.55
  4989.5   256.7  5010.1  255.37  5011.2  254.22  5011.7  253.72  5024.3  254.22
  5027.9  254.71  5034.2  258.64  5070.4  259.71  5189.7  260.21  5404.3  260.85
  5546.2  266.49  5763.5  269.51  5922.3  274.43  6082.9  277.02  6125.6  277.62
#Mann= 8 ,-1 , 0
  4182.9     .05       0  4576.9      .1       0  5011.2     .05       0
  5024.3      .1       0  5070.4     .07       0  5189.7     .05       0
  5404.3     .07       0  6082.9     .05       0
Bank Sta=5011.2,5024.3
XS Rating Curve= 0 ,0
Exp/Cntr=0.3,0.1

Type RM Length L Ch R = 1 ,4479    ,421,421,421
BEGIN DESCRIPTION:
LIVEOAK BRANCH 6.0
END DESCRIPTION:
XS GIS Cut Line= 3
      2510325.01     13738224.96        2510275.       13738575.
      2510574.99     13739774.97
#Sta/Elev= 30
  4651.5  271.04  4833.4  264.54  4937.4  258.33  5007.7  256.69  5015.4  254.55
  5015.6  250.84  5016.1  250.34  5030.6  250.84    5036  254.73  5046.3  257.88
  5077.3  258.19  5097.9  254.35  5105.6  256.17  5113.9   256.3  5128.8  258.16
  5171.4  257.48  5273.1  256.88    5304  258.26  5365.9  256.89  5410.9  258.16
  5499.1  258.21  5788.5  258.44  5922.5  261.34  5963.7  264.47  5994.6  264.12
  6046.2  266.68  6059.1  266.02  6141.5  269.18  6159.6  268.44    6242   270.7
#Mann= 9 ,-1 , 0
  4651.5     .05       0  4937.4      .1       0  5015.6     .05       0
  5030.6      .1       0  5113.9     .12       0  5171.4      .1       0
  5273.1     .12       0  5410.9     .07       0  5499.1     .05       0
Bank Sta=5015.6,5030.6
XS Rating Curve= 0 ,0
Exp/Cntr=0.3,0.1

Type RM Length L Ch R = 1 ,4058    ,882,882,882
BEGIN DESCRIPTION:
LIVEOAK BRANCH 5.0
END DESCRIPTION:
XS GIS Cut Line= 3
      2510124.99     13738125.03        2509925.       13738675.
      2510524.98     13739874.96
#Sta/Elev= 30
  4411.4  270.69    4569  266.13  4630.2  262.58  4716.6  259.38  4850.6  256.93
  4894.8  258.15  4975.3  257.08  4986.4  248.31  4986.9  247.81  5001.4  248.31
    5005  251.05  5010.6   253.5    5019  255.68  5049.7  257.41  5139.1  255.58
  5161.5  257.21    5351  257.35  5409.2  257.35  5607.2  257.94  5793.2  257.95
  5921.8   261.6  5966.5  264.63  6011.2  264.58  6055.9  266.49  6069.9  265.82
  6106.2   266.3    6151  267.68  6167.7  269.34  6204.1  269.14  6338.2  273.17
#Mann= 7 ,-1 , 0
  4411.4     .05       0  4850.6      .1       0  4986.4     .05       0
  5001.4      .1       0    5351     .12       0  5409.2     .07       0
  5607.2     .05       0
Bank Sta=4986.4,5001.4
XS Rating Curve= 0 ,0
Exp/Cntr=0.3,0.1

Type RM Length L Ch R = 1 ,3176    ,933,933,933
BEGIN DESCRIPTION:
LIVEOAK BRANCH 4.0
END DESCRIPTION:
XS GIS Cut Line= 3
      2509975.01     13738024.99        2509275.       13738925.
      2510475.02     13740025.02
#Sta/Elev= 30
    3860  268.98  4015.7  264.49  4172.4  260.92  4265.4  257.23  4572.2  254.85
  4700.7  255.61  4779.4  252.54  4878.9  254.22  4949.5   254.7  4957.7   253.4
    4964  254.38  4970.9  245.39  4971.4  244.89    4986  245.39    4993  246.27
    4997  253.45  5014.1  254.34  5092.4  255.09  5228.8  253.66  5573.3  257.21
  5645.9  256.39  5679.4  258.02  5831.8  256.42    5878  259.57  5926.2  260.88
  6013.2  260.52  6194.6  263.87  6208.7  264.74  6282.4  266.05  6628.1  275.17
#Mann= 14 ,-1 , 0
    3860     .05       0  4015.7     .07       0  4172.4     .05       0
  4878.9     .12       0  4970.9     .05       0    4986     .12       0
  5228.8     .05       0  5645.9     .12       0  5831.8     .07       0
  5926.2     .12       0  6013.2     .07       0  6194.6     .05       0
  6208.7     .07       0  6282.4     .05       0
Bank Sta=4970.9,4986
XS Rating Curve= 0 ,0
Exp/Cntr=0.3,0.1

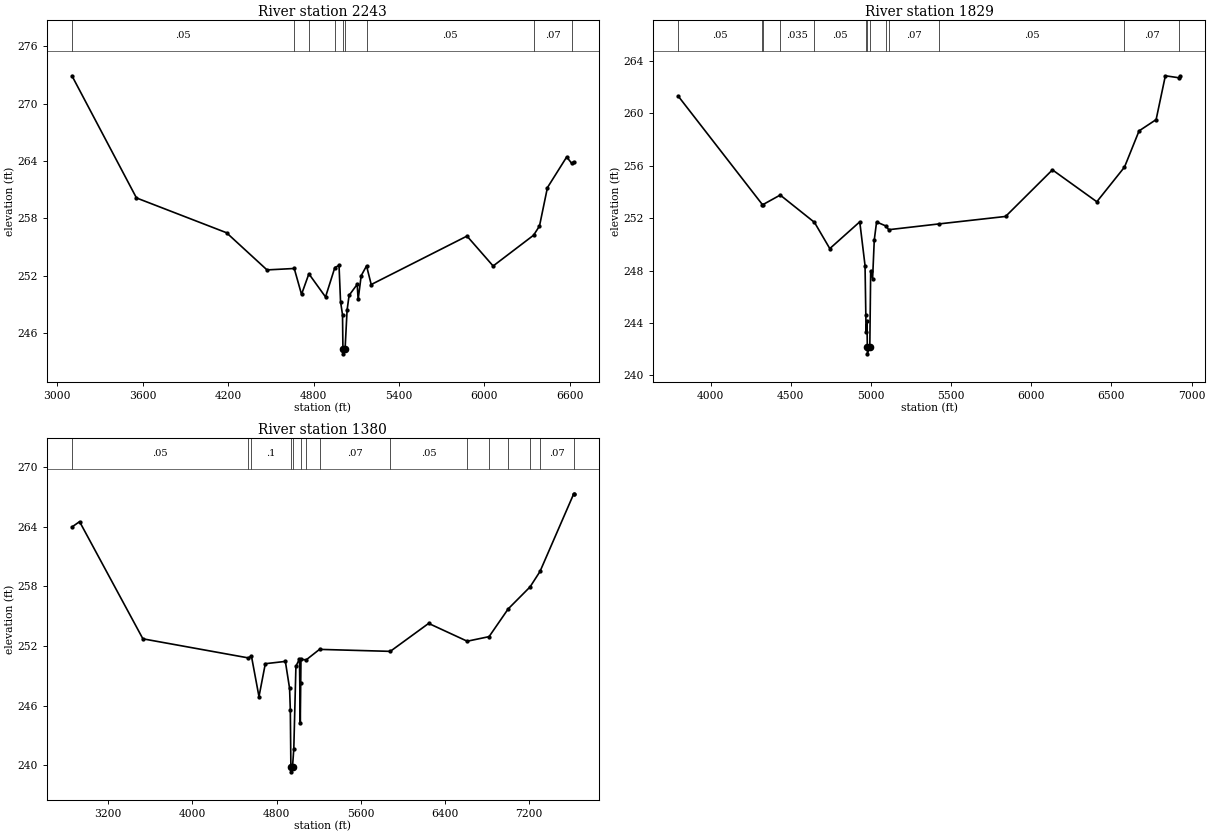
Type RM Length L Ch R = 1 ,2243    ,414,414,414
BEGIN DESCRIPTION:
LIVEOAK BRANCH 3.0
END DESCRIPTION:
XS GIS Cut Line= 3
      2509275.02     13737524.95        2508675.       13739325.
        2509875.       13740425.
#Sta/Elev= 30
  3102.5  272.91  3555.8  260.13  4188.3  256.49  4472.9   252.6  4664.2  252.75
  4715.3  250.04    4767  252.19    4884  249.77  4949.4  252.85  4978.8  253.07
  4989.4  249.29  5003.3   247.9  5006.2  244.32  5006.7  243.82  5021.3  244.32
  5035.4   248.4  5049.6  249.94  5106.3  251.09  5113.1  249.51  5134.6     252
  5172.1  253.02  5204.9  251.07  5877.7  256.14  6061.4  253.01  6345.6  256.23
    6387  257.19  6442.8  261.21  6578.2  264.42  6613.5  263.74  6627.8   263.9
#Mann= 9 ,-1 , 0
  3102.5     .05       0  4664.2     .12       0    4767     .05       0
  4949.4     .07       0  5006.2     .05       0  5021.3     .07       0
  5172.1     .05       0  6345.6     .07       0  6613.5     .12       0
Bank Sta=5006.2,5021.3
XS Rating Curve= 0 ,0
Exp/Cntr=0.3,0.1

Type RM Length L Ch R = 1 ,1829    ,449,449,449
BEGIN DESCRIPTION:
LIVEOAK BRANCH 2.0
END DESCRIPTION:
XS GIS Cut Line= 3
      2508825.02     13738224.96        2508325.       13739325.
      2509825.01     13740525.01
#Sta/Elev= 30
    3799  261.28  4322.9  253.03  4326.3  253.02  4434.5  253.75    4648  251.67
  4743.7  249.67  4930.5  251.71  4963.4  248.38  4968.3  244.63    4970  243.33
  4975.5  244.12  4977.7  242.15  4978.2  241.65  4993.1  242.15  4998.6  247.98
  5010.6  247.39    5021  250.33  5035.4   251.7  5094.1  251.39    5111  251.11
  5423.6  251.55  5839.8  252.12  6131.9  255.67  6408.8  253.24  6581.3  255.88
  6672.2  258.64  6778.6   259.5  6836.2  262.84  6920.1  262.69  6928.3  262.82
#Mann= 13 ,-1 , 0
    3799     .05       0  4322.9    .035       0  4326.3     .05       0
  4434.5    .035       0    4648     .05       0  4968.3     .12       0
  4977.7     .05       0  4993.1     .12       0  5094.1     .05       0
    5111     .07       0  5423.6     .05       0  6581.3     .07       0
  6920.1     .12       0
Bank Sta=4977.7,4993.1
XS Rating Curve= 0 ,0
Exp/Cntr=0.3,0.1

Type RM Length L Ch R = 1 ,1380    ,0,0,0
BEGIN DESCRIPTION:
LIVEOAK BRANCH 1.0
END DESCRIPTION:
XS GIS Cut Line= 3
      2508125.83     13737382.68        2507975.       13739525.
       2509953.7     13741241.21
#Sta/Elev= 30
  2856.2  263.95  2928.7  264.49  3530.2  252.71  4533.2  250.79  4560.8     251
  4632.9   246.9  4693.1  250.21  4883.5  250.44  4923.6  247.73  4930.6  245.59
    4936  239.84  4936.5  239.34  4951.4  239.84  4963.7  241.67  4983.8  249.95
  5017.6   250.7  5025.2  244.24  5029.4  248.31  5031.8  250.64  5081.9   250.6
    5208  251.65  5880.1  251.45  6244.6  254.26    6611  252.47  6818.6  252.93
  7000.4  255.72  7208.1  257.93  7302.3  259.48    7623  267.29  7623.1  267.28
#Mann= 15 ,-1 , 0
  2856.2     .05       0  4533.2     .07       0  4560.8      .1       0
    4936     .05       0  4951.4      .1       0  5029.4     .12       0
  5081.9      .1       0    5208     .07       0  5880.1     .05       0
    6611     .07       0  6818.6     .05       0  7000.4     .07       0
  7208.1     .05       0  7302.3     .07       0    7623     .12       0
Bank Sta=4936,4951.4
XS Rating Curve= 0 ,0
Exp/Cntr=0.3,0.1

Chan Stop Cuts=-1
Use User Specified Reach Order=0
Composite Channel Slope=5