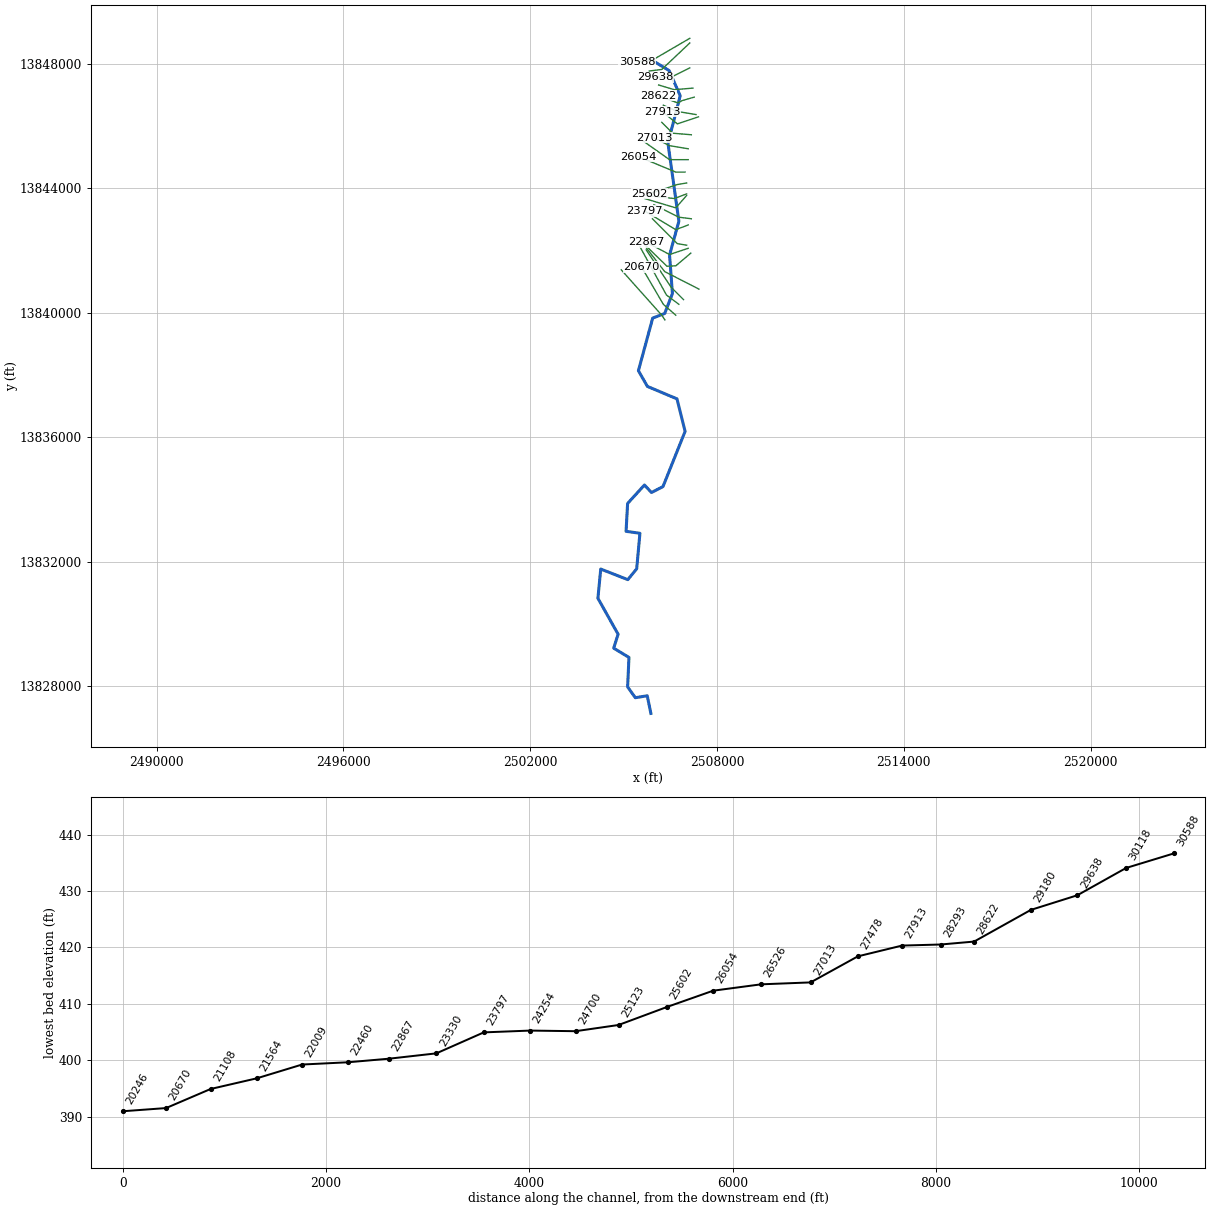
--- Little Copperas Creek.prj (project) ---

Proj Title=Little Copperas Creek Base Level Eng
Current Plan=p01
Default Exp/Contr=0.3,0.1
English Units
Geom File=g01
Flow File=f01
Plan File=p01
Y Axis Title=Elevation
X Axis Title(PF)=Main Channel Distance
X Axis Title(XS)=Station
BEGIN DESCRIPTION:
Little Copperas Creek
END DESCRIPTION:
DSS Export Rating Curves= 0
DSS Export Rating Curve Sorted= 0
DSS Export Volume Flow Curves= 0
DXF OffsetX= 0
DXF OffsetY= 0
DXF ScaleX= 1
DXF ScaleY= 10

--- Little Copperas Creek.p01 (plan) ---

Plan Title=Multiple Run
Program Version=4.10
Short Identifier=Multiple
Geom File=g01
Flow File=f01
Subcritical Flow
K Sum by GR= 0
Std Step Tol= 0.01
Critical Tol= 0.01
Num of Std Step Trials= 20
Max Error Tol= 0.3
Flow Tol Ratio= 0.001
Split Flow NTrial= 30
Split Flow Tol= 0.02
Split Flow Ratio= 0.02
Log Output Level= 0
Friction Slope Method= 1
Unsteady Friction Slope Method= 2
Unsteady Bridges Friction Slope Method= 1
Parabolic Critical Depth
Global Vel Dist= 1 , 1 , 1
Global Log Level= 0
CheckData=True
Encroach Param=-1 ,0,0, 0
BEGIN DESCRIPTION:
Multiple Run
END DESCRIPTION:
Computation Interval=1HOUR
Output Interval=1HOUR
Run HTab= 0
Run UNet= 0
Run PostProcess= 0
Run WQNet= 0
UNET Theta= 1
UNET Theta Warmup= 1
UNET ZTol= 0.02
UNET ZSATol= 0.05
UNET MxIter= 20
UNET MaxInSteps= 0
UNET DtIC= 0
UNET DtMin= 0
UNET MaxCRTS= 20
UNET WFStab= 2
UNET SFStab= 1
UNET WFX= 1
UNET SFX= 1
UNET DSS MLevel= 4
UNET DZMax Abort= 100
UNET Convert EG Bridges= 0
UNET Use Existing IB Tables=-1
UNET Froude Reduction=False
UNET Froude Limit= 1
UNET Froude Power= 10
UNET Time Slicing=0,0, 5
UNET Junction Losses=0
Instantaneous Interval=1HOUR
Write IC File= 0
Write IC File at Sim End=0
Echo Input=False
Echo Parameters=False
Echo Output=False
Write Detailed= 0
WQ AD Non Conservative
WQ ULTIMATE=-1
WQ Max Comp Step=1HOUR
WQ Output Interval=15MIN
WQ Output Selected Increments= 0
WQ Output face flow=0
WQ Output face velocity=0
WQ Output face area=0
WQ Output face dispersion=0
WQ Output cell volume=0
WQ Output cell surface area=0
WQ Output cell continuity=0
WQ Output cumulative cell continuity=0
WQ Output face conc=0
WQ Output face dconc_dx=0
WQ Output face courant=0
WQ Output face peclet=0
WQ Output face adv mass=0
WQ Output face disp mass=0
WQ Output cell mass=0
WQ Output cell source sink temp=0
WQ Output cell source sink nsm=0
WQ Output MaxMinRange=-1
WQ Daily Max Min Mean=-1
WQ Daily Range=0
WQ Daily Time=0
WQ Create Restart=0
WQ Fixed Restart=0
WQ System Summary=0
WQ Use Fixed Temperature=0
Sorting and Armoring Iterations= 10
XS Update Threshold= 0.02
Hydraulics Update Threshold= 0.02
Energy Slope Method= 1
Volume Change Method= 0
XS Weighting Method= 0
Number of US Weighted Cross Sections= 1
Number of DS Weighted Cross Sections= 1
Upstream XS Weight=0.25
Main XS Weight=0.5
Downstream XS Weight=0.25
Number of DS XS's Weighted with US Boundary= 1
Upstream Boundary Weight= 1
Weight of XSs Associated with US Boundary= 0
Number of US XS's Weighted with DS Boundary= 1
Downstream Boundary Weight= 0.5
Weight of XSs Associated with DS Boundary= 0.5
Sediment Output Level= 4
Mass or Volume Output= 0
Output Increment Type= 1
Profile and TS Output Increment= 10
XS Output Flag= 0
XS Output Increment= 10
Disregard all LS=0
Disregard all Conn=0
Disregard all Breaches=0
Disregard all Pumps=0

--- Little Copperas Creek.f01 (steady flow) ---

Flow Title=Multiple
Number of Profiles=7
Profile Names=10-year,25-year,50-year,1pct_min,100-year,1pct_plu,500-year
River Rch & RM= Little Cooperas ,Reach-1,30588
     525     837    1117     724    1444    2881    2384
River Rch & RM= Little Cooperas ,Reach-1,28293
     685    1106    1489     971    1938    3867    3248
River Rch & RM= Little Cooperas ,Reach-1,25602
    1007    1653    2248    1479    2951    5887    5033
River Rch & RM= Little Cooperas ,Reach-1,22009
    1625    2737    3785    2529    5046   10068    8882
River Rch & RM= Little Cooperas ,Reach-1,20670
    2216    3785    5285    3561    7106   14178   12726
River Rch & RM= Little Cooperas ,Reach-1,19823
    2227    3784    5264    3532    7047   14061   12517
River Rch & RM= Little Cooperas ,Reach-1,15225
    2732    4669    6519    4388    8755   17468   15643
River Rch & RM= Little Cooperas ,Reach-1,10252
    2638    4465    6193    4137    8255   16471   14535
River Rch & RM= Little Cooperas ,Reach-1,1907
    2589    4371    6051    4035    8051   16064   14122
Boundary for River Rch & Prof#=Little Cooperas ,Reach-1,1
Up Type=0
Dn Type=3
Dn Slope=0.005
Boundary for River Rch & Prof#=Little Cooperas ,Reach-1,2
Up Type=0
Dn Type=3
Dn Slope=0.005
Boundary for River Rch & Prof#=Little Cooperas ,Reach-1,3
Up Type=0
Dn Type=3
Dn Slope=0.005
Boundary for River Rch & Prof#=Little Cooperas ,Reach-1,4
Up Type=0
Dn Type=3
Dn Slope=0.005
Boundary for River Rch & Prof#=Little Cooperas ,Reach-1,5
Up Type=0
Dn Type=3
Dn Slope=0.005
Boundary for River Rch & Prof#=Little Cooperas ,Reach-1,6
Up Type=0
Dn Type=3
Dn Slope=0.005
Boundary for River Rch & Prof#=Little Cooperas ,Reach-1,7
Up Type=0
Dn Type=3
Dn Slope=0.005

--- Little Copperas Creek.g01 (geometry) ---

Geom Title=Existing Conditions
Program Version=4.10

River Reach=Little Cooperas ,Reach-1
Reach XY= 30
        2505825.       13848175.       2506461.8     13847788.74
      2506817.41     13846978.35      2506424.61       13845450.
      2506775.21     13842945.21      2506475.39     13841859.84
      2506567.51     13840621.38      2506319.82     13839980.44
      2505933.99     13839832.11      2505475.02     13838140.41
      2505764.82     13837635.32      2506714.58     13837234.81
      2506975.19      13836190.3      2506264.81     13834415.32
      2505894.98     13834224.95      2505668.34     13834466.05
      2505128.44     13833873.78      2505078.43     13832976.22
      2505524.04     13832914.73      2505419.54     13831772.55
      2505134.82     13831424.02      2504264.78      13831764.7
      2504174.18       13830825.      2504822.86     13829669.03
      2504680.42     13829222.32      2505171.39     13828923.52
      2505128.75     13827976.55      2505376.47     13827628.52
      2505758.37     13827691.72        2505875.       13827125.

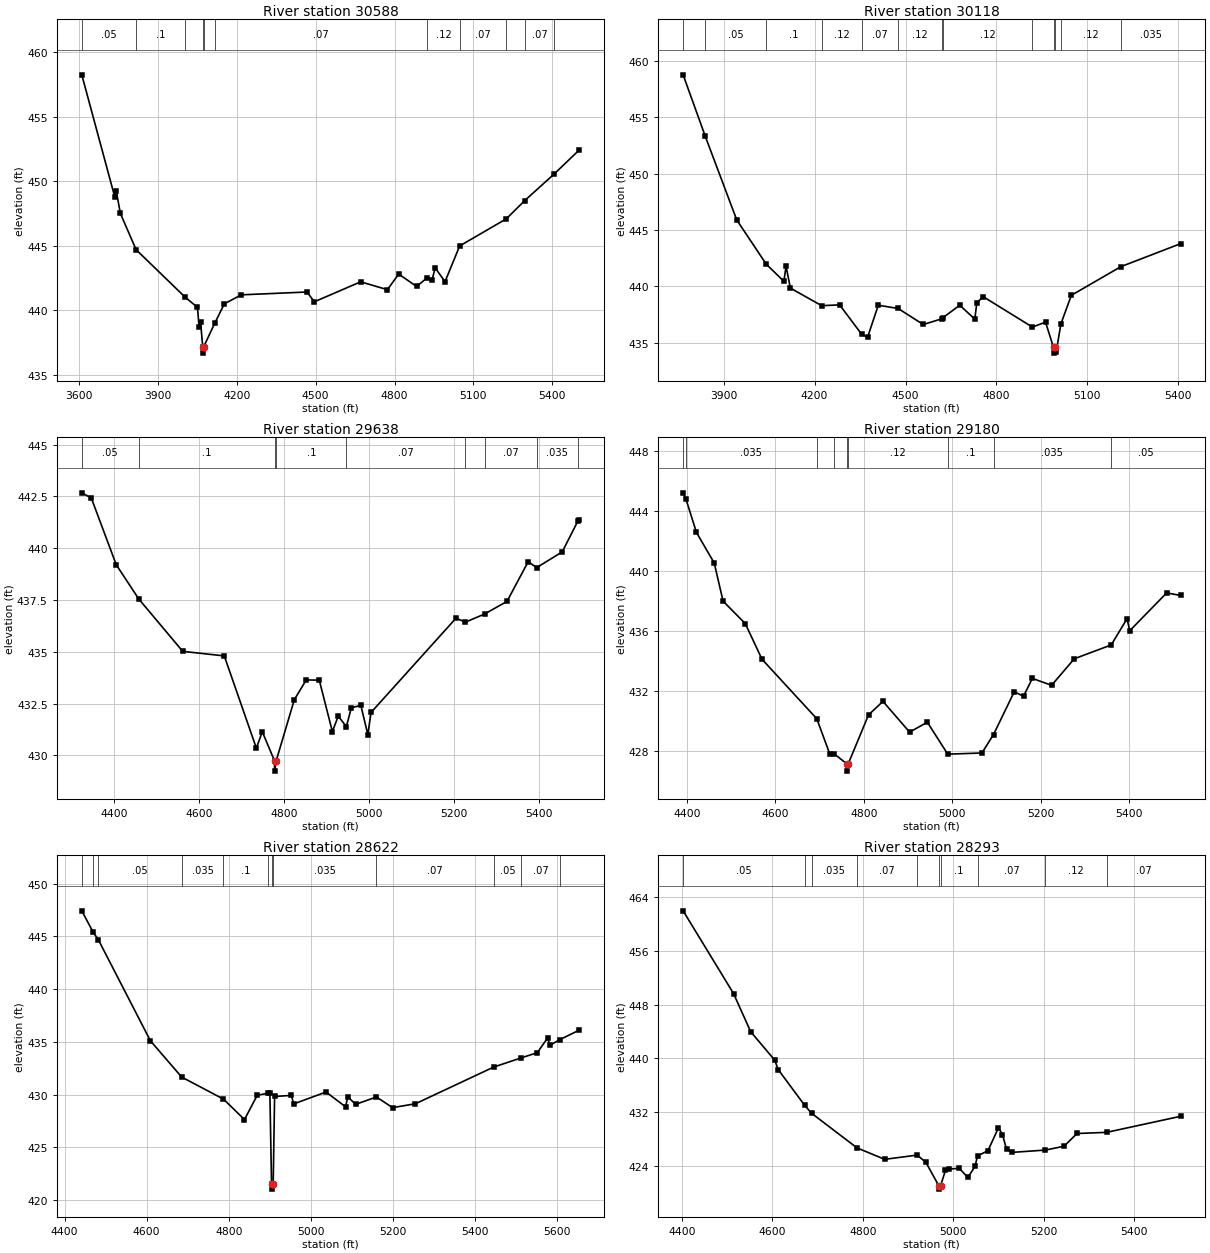
Type RM Length L Ch R = 1 ,30588   ,470,470,470
BEGIN DESCRIPTION:
Little Cooperas Creek 51.0
END DESCRIPTION:
XS GIS Cut Line= 3
      2507125.02     13848825.01        2505925.       13848125.
      2505424.96       13848075.
#Sta/Elev= 30
  3610.6  458.24  3735.9  448.78  3741.7  449.23  3757.4  447.49  3817.2  444.68
  4004.1  440.99  4050.6  440.21  4056.8  438.65  4062.5  439.05  4070.5  437.16
  4070.7  436.66  4074.5  437.16  4116.3  438.98  4152.7  440.48  4217.2  441.18
  4467.3   441.4    4495  440.64  4671.2  442.19  4772.9  441.58  4815.9  442.79
  4884.1  441.83    4924   442.5    4942   442.3  4954.8  443.27    4992   442.2
  5047.8  444.97  5224.9  447.07  5295.3  448.49  5407.2  450.55  5502.4  452.41
#Mann= 11 ,-1 , 0
  3610.6     .05       0  3817.2      .1       0  4004.1     .12       0
  4070.5     .05       0  4074.5     .12       0  4116.3     .07       0
    4924     .12       0  5047.8     .07       0  5224.9    .035       0
  5295.3     .07       0  5407.2    .035       0
Bank Sta=4070.5,4074.5
XS Rating Curve= 0 ,0
Exp/Cntr=0.3,0.1

Type RM Length L Ch R = 1 ,30118   ,480,480,480
BEGIN DESCRIPTION:
Little Cooperas Creek 50.0
END DESCRIPTION:
XS GIS Cut Line= 3
      2507125.02     13848675.01        2506225.       13847825.
      2505824.98       13847775.
#Sta/Elev= 30
  3766.2  458.77  3839.2  453.32  3943.2  445.89  4040.5  441.97  4098.6  440.45
  4105.8  441.78    4120  439.85  4223.3  438.29  4282.6  438.36  4355.3  435.75
  4374.5  435.47  4410.1  438.33  4475.5  438.04  4558.5  436.62  4619.3  437.12
  4623.2  437.22  4678.7  438.33  4728.5   437.1  4735.3  438.57  4756.6  439.08
  4918.6  436.39  4961.9  436.83  4988.2  434.58  4988.5  434.08  4992.2  434.58
  4997.1  434.19  5012.5  436.67    5047  439.21  5210.4  441.75  5407.3  443.79
#Mann= 13 ,-1 , 0
  3766.2     .12       0  3839.2     .05       0  4040.5      .1       0
  4223.3     .12       0  4355.3     .07       0  4475.5     .12       0
  4619.3     .07       0  4623.2     .12       0  4918.6      .1       0
  4988.2     .05       0  4992.2      .1       0  5012.5     .12       0
  5210.4    .035       0
Bank Sta=4988.2,4992.2
XS Rating Curve= 0 ,0
Exp/Cntr=0.3,0.1

Type RM Length L Ch R = 1 ,29638   ,458,458,458
BEGIN DESCRIPTION:
Little Cooperas Creek 49.0
END DESCRIPTION:
XS GIS Cut Line= 3
      2507125.01       13847875.        2506525.       13847575.
      2506025.03       13847575.
#Sta/Elev= 30
  4324.6  442.67    4347  442.42  4405.7   439.2  4458.6  437.55  4562.2  435.02
    4660   434.8  4735.5  430.35  4749.5  431.14  4778.2  429.74  4778.5  429.24
  4782.2  429.74  4824.9  432.69  4852.9  433.64  4883.6  433.63  4914.4  431.15
  4928.3  431.89  4947.4  431.39  4959.1   432.3  4981.5  432.41  4997.9     431
  5005.4  432.07  5205.4  436.62  5227.6  436.43  5272.5  436.82  5325.4  437.43
  5375.4  439.35  5395.2  439.06  5455.4  439.82  5492.6  441.32  5495.4  441.35
#Mann= 9 ,-1 , 0
  4324.6     .05       0  4458.6      .1       0  4778.2     .05       0
  4782.2      .1       0  4947.4     .07       0  5227.6     .05       0
  5272.5     .07       0  5395.2    .035       0  5492.6     .05       0
Bank Sta=4778.2,4782.2
XS Rating Curve= 0 ,0
Exp/Cntr=0.3,0.1

Type RM Length L Ch R = 1 ,29180   ,558,558,558
BEGIN DESCRIPTION:
Little Cooperas Creek 48.0
END DESCRIPTION:
XS GIS Cut Line= 3
      2507225.04       13847225.        2506625.       13847175.
      2506125.03     13847324.99
#Sta/Elev= 30
  4391.4  445.19  4397.6  444.79  4421.5  442.55  4461.7  440.51  4481.7  437.97
  4531.9  436.47  4569.6   434.1  4693.5  430.13  4722.6   427.8  4732.5   427.8
  4760.7  427.14    4761  426.64  4764.7  427.14  4810.4  430.39    4843  431.29
  4903.2  429.24  4943.3   429.9  4989.4  427.77  5066.6  427.85  5092.9  429.08
  5139.7  431.93  5160.6  431.63  5180.6  432.82  5224.1  432.36  5275.4  434.13
  5358.8  435.05  5394.6   436.8  5400.7     436  5484.2  438.52  5515.5  438.35
#Mann= 9 ,-1 , 0
  4391.4     .12       0  4397.6    .035       0  4693.5     .07       0
  4732.5     .12       0  4760.7     .05       0  4764.7     .12       0
  4989.4      .1       0  5092.9    .035       0  5358.8     .05       0
Bank Sta=4760.7,4764.7
XS Rating Curve= 0 ,0
Exp/Cntr=0.3,0.1

Type RM Length L Ch R = 1 ,28622   ,329,329,329
BEGIN DESCRIPTION:
Little Cooperas Creek 47.0
END DESCRIPTION:
XS GIS Cut Line= 6
      2507265.57      13846934.3      2506863.79     13846818.34
      2506835.68     13846794.91      2506757.21     13846759.77
      2506703.33     13846762.12        2506125.       13846975.
#Sta/Elev= 30
    4442  447.43  4469.4  445.42  4482.4  444.68  4609.1   435.1  4685.2  431.66
  4786.9  429.57  4838.1  427.63  4869.2  429.94  4895.2  430.12  4899.9  430.12
    4904  421.53  4904.2  421.03    4908  421.53  4911.4  429.82  4952.3  429.92
  4957.8  429.11  5036.7  430.24  5084.2  428.84  5089.6  429.79  5108.5  429.07
  5159.4  429.77  5198.7  428.76  5254.4  429.13  5444.9  432.61  5512.5  433.49
  5550.9  433.97  5576.3  435.38  5581.6  434.67  5606.2  435.22    5653  436.11
#Mann= 12 ,-1 , 0
    4442      .1       0  4469.4     .07       0  4482.4     .05       0
  4685.2    .035       0  4786.9      .1       0  4895.2    .035       0
    4904    .035       0    4908    .035       0  5159.4     .07       0
  5444.9     .05       0  5512.5     .07       0  5606.2     .05       0
Bank Sta=4904,4908
XS Rating Curve= 0 ,0
Exp/Cntr=0.3,0.1

Type RM Length L Ch R = 1 ,28293   ,380,380,380
BEGIN DESCRIPTION:
Little Cooperas Creek 46.0
END DESCRIPTION:
XS GIS Cut Line= 3
      2507324.96     13846375.01        2506725.       13846475.
      2506274.98     13846675.01
#Sta/Elev= 30
  4402.5  461.98    4514  449.66    4552  443.97  4605.2  439.73  4612.8  438.33
  4671.3  433.01  4686.8  431.81  4787.2  426.66  4848.5  424.95  4920.4  425.58
  4939.8  424.49  4968.2  421.01  4968.4  420.51  4972.2  421.01  4982.9   423.3
  4990.5   423.5  5013.5  423.61  5032.6  422.25  5048.4  423.89  5053.9  425.45
  5077.1  426.25  5100.3  429.66  5109.2  428.65  5118.1  426.43  5131.1  425.99
  5204.2  426.33  5245.3   426.9  5274.1   428.8  5339.6  428.97  5503.2  431.36
#Mann= 10 ,-1 , 0
  4402.5     .05       0  4671.3     .07       0  4686.8    .035       0
  4787.2     .07       0  4920.4      .1       0  4968.2     .05       0
  4972.2      .1       0  5053.9     .07       0  5204.2     .12       0
  5339.6     .07       0
Bank Sta=4968.2,4972.2
XS Rating Curve= 0 ,0
Exp/Cntr=0.3,0.1

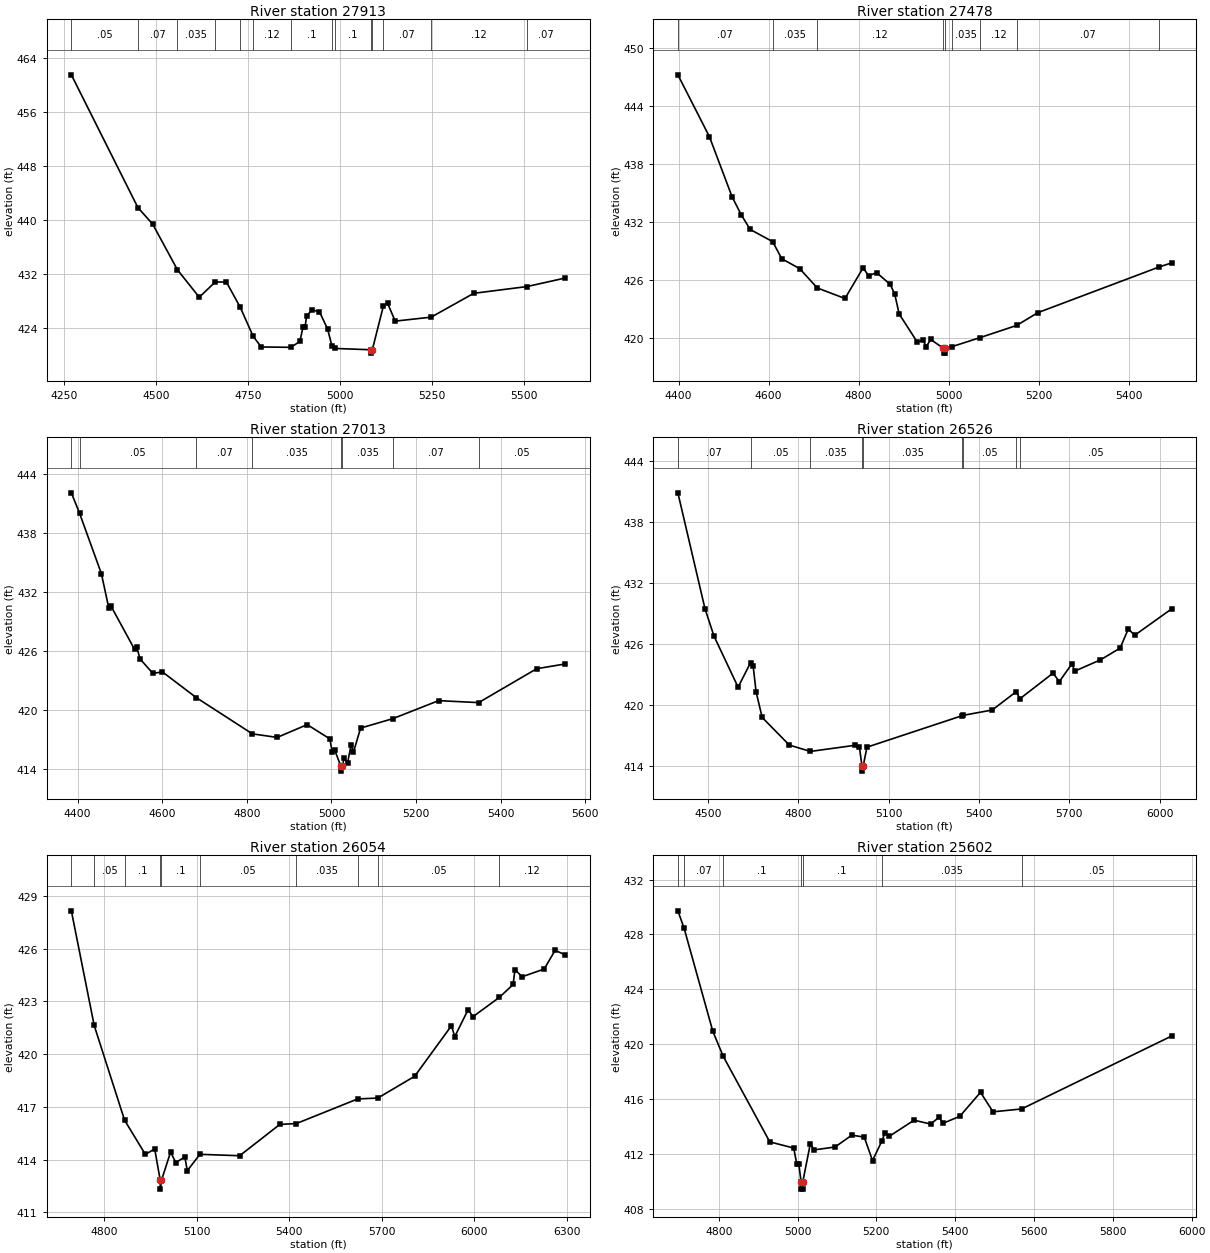
Type RM Length L Ch R = 1 ,27913   ,435,435,435
BEGIN DESCRIPTION:
Little Cooperas Creek 45.0
END DESCRIPTION:
XS GIS Cut Line= 3
      2507405.11      13846301.7        2506725.       13846075.
      2506240.35     13846471.53
#Sta/Elev= 30
  4269.4  461.54  4450.4  441.88  4490.8  439.41    4558  432.66  4617.3   428.6
  4660.9  430.86  4691.1  430.85  4728.8  427.11  4763.8  422.83  4785.9  421.23
  4866.7  421.18  4891.3  422.07  4899.2  424.12  4905.1  424.12  4909.1  425.79
  4923.4  426.71  4944.2  426.46  4966.5  423.88  4978.3  421.36  4987.6  421.01
  5084.1  420.82  5084.3  420.32  5088.1  420.82  5117.9  427.24  5129.4  427.74
  5150.2  425.06  5248.2  425.65  5364.1  429.18  5508.8  430.18  5612.5  431.44
#Mann= 14 ,-1 , 0
  4269.4     .05       0  4450.4     .07       0    4558    .035       0
  4660.9     .07       0  4728.8    .035       0  4763.8     .12       0
  4866.7      .1       0  4978.3     .12       0  4987.6      .1       0
  5084.1     .05       0  5088.1      .1       0  5117.9     .07       0
  5248.2     .12       0  5508.8     .07       0
Bank Sta=5084.1,5088.1
XS Rating Curve= 0 ,0
Exp/Cntr=0.3,0.1

Type RM Length L Ch R = 1 ,27478   ,465,465,465
BEGIN DESCRIPTION:
Little Cooperas Creek 44.0
END DESCRIPTION:
XS GIS Cut Line= 3
        2507175.       13845725.        2506575.       13845775.
      2506224.97     13846125.03
#Sta/Elev= 30
  4398.4  447.19  4468.6  440.78  4518.8  434.58  4538.9  432.74    4559   431.2
    4609  429.94  4629.2  428.17  4669.3  427.14  4708.1  425.15  4769.7  424.06
  4809.8  427.22  4822.4  426.41  4839.9  426.74    4870  425.52  4880.1  424.54
  4890.1  422.46  4930.2  419.56  4942.8  419.76  4950.3  419.09  4960.3  419.82
  4988.4  418.91  4988.7  418.41  4992.2  418.41  4992.4  418.91  5007.5  419.08
  5070.2  420.02  5150.9  421.27  5198.5   422.6  5468.3  427.33  5495.5  427.74
#Mann= 9 ,-1 , 0
  4398.4     .07       0    4609    .035       0  4708.1     .12       0
  4988.4     .05       0  4992.4     .12       0  5007.5    .035       0
  5070.2     .12       0  5150.9     .07       0  5468.3    .035       0
Bank Sta=4988.4,4992.4
XS Rating Curve= 0 ,0
Exp/Cntr=0.3,0.1

Type RM Length L Ch R = 1 ,27013   ,487,487,487
BEGIN DESCRIPTION:
Little Cooperas Creek 43.0
END DESCRIPTION:
XS GIS Cut Line= 3
      2507075.01       13845275.        2506475.       13845375.
        2505975.       13845625.
#Sta/Elev= 30
  4385.1   442.1  4404.6  440.01  4456.1  433.88  4473.8  430.34  4478.9  430.57
  4534.6  426.17  4539.7  426.42  4547.3  425.21  4577.7  423.74  4600.5  423.88
  4680.4  421.27  4813.1  417.58  4871.7  417.22  4942.7  418.52  4996.2  417.07
  5001.8  415.72  5007.4  415.98  5022.1  414.29  5022.4  413.79  5026.1  414.29
  5029.7   415.1  5038.1  414.63  5046.5  416.47  5052.1  415.73  5068.9  418.17
  5145.3  419.13  5253.3  420.96    5348  420.76  5485.3  424.21  5552.4  424.69
#Mann= 8 ,-1 , 0
  4385.1     .07       0  4404.6     .05       0  4680.4     .07       0
  4813.1    .035       0  5022.1    .035       0  5026.1    .035       0
  5145.3     .07       0    5348     .05       0
Bank Sta=5022.1,5026.1
XS Rating Curve= 0 ,0
Exp/Cntr=0.3,0.1

Type RM Length L Ch R = 1 ,26526   ,472,472,472
BEGIN DESCRIPTION:
Little Cooperas Creek 42.0
END DESCRIPTION:
XS GIS Cut Line= 3
      2507074.97       13844925.        2506475.       13844925.
        2505625.       13845525.
#Sta/Elev= 30
  4399.5  440.86  4489.5  429.45  4519.5  426.75  4599.5  421.72    4641  424.13
  4649.5  423.81  4659.5  421.24  4679.5  418.74  4769.5  416.02  4839.7  415.39
  4989.5     416  5002.5  415.85    5011  413.95  5011.2  413.45    5015  413.95
  5027.8  415.81  5342.8   418.9  5348.2  418.95  5443.9  419.47  5523.8  421.28
  5535.5  420.57  5645.9   423.1  5666.8  422.27  5709.4  424.05  5717.3  423.29
  5803.5  424.41  5868.5  425.56  5895.8  427.44  5917.5  426.84  6039.9  429.43
#Mann= 9 ,-1 , 0
  4399.5     .07       0    4641     .05       0  4839.7    .035       0
    5011    .035       0    5015    .035       0  5342.8     .07       0
  5348.2     .05       0  5523.8     .07       0  5535.5     .05       0
Bank Sta=5011,5015
XS Rating Curve= 0 ,0
Exp/Cntr=0.3,0.1

Type RM Length L Ch R = 1 ,26054   ,452,452,452
BEGIN DESCRIPTION:
Little Cooperas Creek 41.0
END DESCRIPTION:
XS GIS Cut Line= 3
      2506974.98       13844525.        2506675.       13844525.
      2505474.98     13845025.01
#Sta/Elev= 30
  4694.2  428.15  4768.2  421.63  4866.7  416.24  4934.2  414.29  4964.2  414.61
  4982.2  412.82  4982.4  412.32  4986.2  412.82  5015.8  414.43  5032.6  413.83
  5061.9  414.15    5070  413.37  5110.8   414.3  5239.6  414.22  5369.6     416
  5423.4  416.05  5621.9  417.45  5687.3   417.5  5806.7  418.74  5925.8  421.61
  5936.7     421    5980  422.53  5995.7  422.13  6081.4  423.23  6125.7  423.96
  6131.7   424.8    6155   424.4  6226.5  424.84  6261.7   425.9  6294.2  425.65
#Mann= 10 ,-1 , 0
  4694.2     .07       0  4768.2     .05       0  4866.7      .1       0
  4982.2     .05       0  4986.2      .1       0  5110.8     .05       0
  5423.4    .035       0  5621.9     .07       0  5687.3     .05       0
  6081.4     .12       0
Bank Sta=4982.2,4986.2
XS Rating Curve= 0 ,0
Exp/Cntr=0.3,0.1

Type RM Length L Ch R = 1 ,25602   ,479,479,479
BEGIN DESCRIPTION:
Little Cooperas Creek 40.0
END DESCRIPTION:
XS GIS Cut Line= 3
      2507024.99       13844175.        2506725.       13844125.
      2505825.01       13843825.
#Sta/Elev= 30
  4696.4  429.72  4712.1  428.46  4785.1  420.94  4811.5  419.12  4929.6  412.89
  4990.4  412.44    4998  411.29  5003.2  411.29  5009.1  409.95  5009.3  409.45
  5012.8  409.45  5013.1  409.95  5032.2  412.72  5042.7  412.31  5095.4  412.52
  5137.6  413.38  5169.2  413.24  5190.3  411.53  5213.4  412.92  5221.9  413.55
  5232.4  413.29  5295.7  414.47  5337.8  414.19  5358.9  414.68  5369.5  414.25
  5411.6  414.75  5464.3   416.5    5496  415.08  5568.6  415.29  5949.2   420.6
#Mann= 7 ,-1 , 0
  4696.4     .05       0  4712.1     .07       0  4811.5      .1       0
  5009.1     .05       0  5013.1      .1       0  5213.4    .035       0
  5568.6     .05       0
Bank Sta=5009.1,5013.1
XS Rating Curve= 0 ,0
Exp/Cntr=0.3,0.1

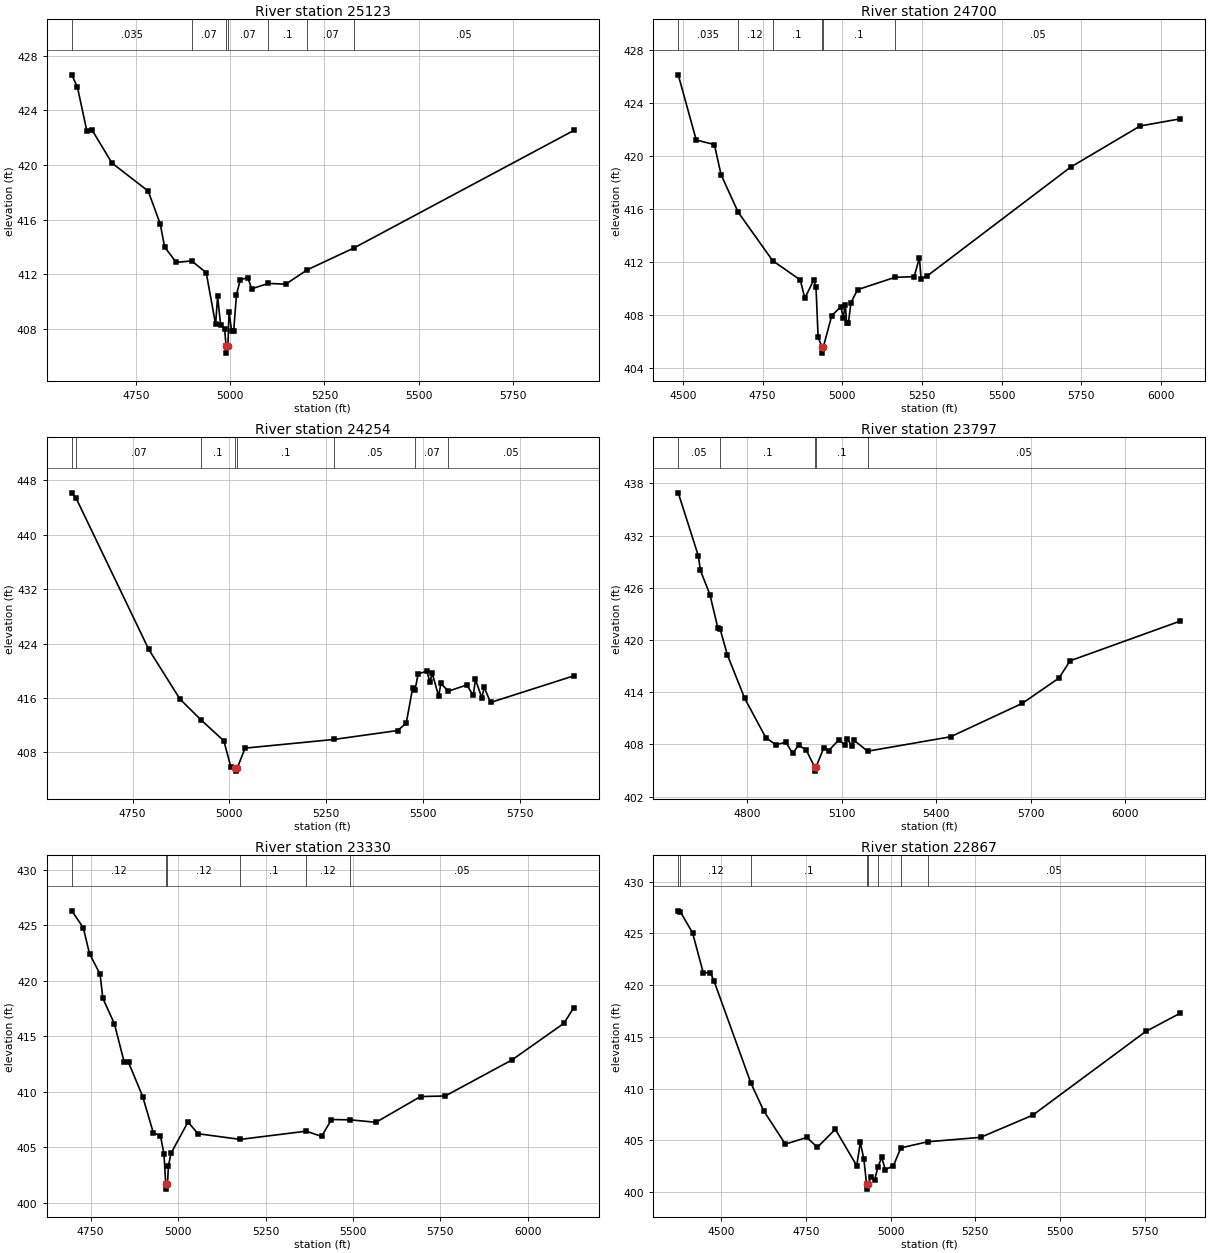
Type RM Length L Ch R = 1 ,25123   ,423,423,423
BEGIN DESCRIPTION:
Little Cooperas Creek 39.0
END DESCRIPTION:
XS GIS Cut Line= 3
      2507024.97     13843824.99        2506625.       13843675.
      2505725.01       13843775.
#Sta/Elev= 30
  4579.4  426.61  4594.5   425.7  4619.4   422.5  4632.8  422.59  4686.2  420.15
  4782.3   418.1  4814.3  415.69  4825.9     414    4857  412.88  4897.7  412.99
  4936.3  412.13  4961.2  408.34  4966.5  410.39  4974.5  408.33  4985.2  408.01
    4989  406.74  4989.3  406.24  4993.9  406.74  4996.8  409.28  5003.9  407.83
  5009.1  407.83  5016.6  410.52  5026.7  411.61  5046.8  411.77  5056.9  410.95
  5101.5  411.34  5147.4  411.29  5204.7  412.34  5327.9  413.93  5912.1  422.54
#Mann= 7 ,-1 , 0
  4579.4    .035       0  4897.7     .07       0    4989     .05       0
  4993.9     .07       0  5101.5      .1       0  5204.7     .07       0
  5327.9     .05       0
Bank Sta=4989,4993.9
XS Rating Curve= 0 ,0
Exp/Cntr=0.3,0.1

Type RM Length L Ch R = 1 ,24700   ,446,446,446
BEGIN DESCRIPTION:
Little Cooperas Creek 38.0
END DESCRIPTION:
XS GIS Cut Line= 3
        2507025.       13843775.        2506675.       13843375.
      2505675.04     13843674.99
#Sta/Elev= 30
  4485.1  426.14  4541.6  421.22  4598.5  420.88  4619.4  418.61    4673  415.78
  4781.2  412.12  4868.1  410.66  4882.3  409.28  4910.3  410.66  4917.4   410.1
  4924.1  406.32  4935.9  405.64  4936.2  405.14  4940.8  405.64  4966.8  407.97
  4995.3  408.64  5002.8  407.82  5009.5  408.79  5013.3  407.44  5019.2  407.44
    5027  408.94  5047.9  409.93  5165.2  410.86  5225.4  410.91  5241.9  412.33
  5247.2  410.74  5267.2  410.98  5716.1  419.17  5934.5  422.28  6060.6  422.82
#Mann= 6 ,-1 , 0
  4485.1    .035       0    4673     .12       0  4781.2      .1       0
  4935.9     .05       0  4940.8      .1       0  5165.2     .05       0
Bank Sta=4935.9,4940.8
XS Rating Curve= 0 ,0
Exp/Cntr=0.3,0.1

Type RM Length L Ch R = 1 ,24254   ,457,457,457
BEGIN DESCRIPTION:
Little Cooperas Creek 37.0
END DESCRIPTION:
XS GIS Cut Line= 3
      2507175.01       13843025.        2506775.       13843075.
      2505975.04     13843474.98
#Sta/Elev= 30
  4592.9  446.14  4604.3  445.33  4791.9  423.13  4872.6  415.83  4926.8  412.78
  4985.9   409.7  5004.4  405.79  5015.9  405.75  5016.3  405.25  5020.9  405.75
  5040.7  408.63  5269.6   409.9  5434.9  411.21  5457.2  412.29    5474   417.5
    5480  417.18    5488  419.52  5510.3  419.95  5518.7  418.33  5524.3  419.63
  5541.1  416.27  5546.7  418.13    5566     417  5613.7   417.9  5630.5  416.37
  5636.1  418.72  5652.9  415.98  5658.5  417.58  5675.2  415.34  5890.4  419.25
#Mann= 8 ,-1 , 0
  4592.9     .05       0  4604.3     .07       0  4926.8      .1       0
  5015.9     .05       0  5020.9      .1       0  5269.6     .05       0
    5480     .07       0    5566     .05       0
Bank Sta=5015.9,5020.9
XS Rating Curve= 0 ,0
Exp/Cntr=0.3,0.1

Type RM Length L Ch R = 1 ,23797   ,467,467,467
BEGIN DESCRIPTION:
Little Cooperas Creek 36.0
END DESCRIPTION:
XS GIS Cut Line= 3
      2507074.98     13842824.99        2506675.       13842675.
      2505674.98     13843275.01
#Sta/Elev= 30
  4581.4  436.92  4645.5  429.64  4651.7  428.01    4682  425.21  4706.9  421.42
  4714.5  421.25  4737.1  418.31  4792.3   413.3  4859.1  408.79  4891.1  407.96
  4923.1  408.25  4944.5  406.97  4963.2   407.9  4987.2  407.38  5013.9  405.43
  5014.2  404.93  5018.9  405.43  5043.6  407.63  5059.1  407.29  5090.2  408.49
  5111.6  407.97  5117.4  408.63    5133  407.82  5138.8  408.48  5182.6  407.22
  5445.9  408.88  5673.3  412.72  5789.9  415.63  5824.9  417.61  6174.8  422.18
#Mann= 5 ,-1 , 0
  4581.4     .05       0  4714.5      .1       0  5013.9     .05       0
  5018.9      .1       0  5182.6     .05       0
Bank Sta=5013.9,5018.9
XS Rating Curve= 0 ,0
Exp/Cntr=0.3,0.1

Type RM Length L Ch R = 1 ,23330   ,463,463,463
BEGIN DESCRIPTION:
Little Cooperas Creek 35.0
END DESCRIPTION:
XS GIS Cut Line= 3
        2507025.       13842175.        2506725.       13842225.
      2505925.01     13843024.99
#Sta/Elev= 30
    4696  426.28  4728.9  424.76  4746.7  422.42  4777.1  420.56  4784.7  418.41
  4817.7  416.12  4845.5   412.7  4858.2  412.63  4898.8  409.55  4929.2  406.28
  4949.4  406.03  4959.6  404.39  4964.6  401.71    4965  401.21  4969.7  401.71
  4972.3   403.3  4979.9  404.45  5028.4  407.26  5056.7   406.2  5177.9  405.69
  5366.3  406.43  5410.3  405.96  5438.5  407.48  5492.7  407.45  5565.8  407.23
  5693.1  409.55  5763.8   409.6  5954.7  412.85  6103.2  416.15  6131.5  417.57
#Mann= 6 ,-1 , 0
    4696     .12       0  4964.6     .05       0  4969.7     .12       0
  5177.9      .1       0  5366.3     .12       0  5492.7     .05       0
Bank Sta=4964.6,4969.7
XS Rating Curve= 0 ,0
Exp/Cntr=0.3,0.1

Type RM Length L Ch R = 1 ,22867   ,407,407,407
BEGIN DESCRIPTION:
Little Cooperas Creek 34.0
END DESCRIPTION:
XS GIS Cut Line= 3
      2507075.03     13842075.01        2506475.       13841875.
      2505724.99     13842275.01
#Sta/Elev= 30
  4372.9  427.19  4379.5  427.07  4415.1  425.07  4446.7  421.21  4467.8   421.2
  4478.3  420.43  4587.4  410.53  4625.9  407.81  4689.2  404.62  4752.4  405.27
    4784  404.32  4836.7  406.06    4900  402.53  4910.5  404.81  4921.1  403.15
    4929  400.77  4929.4  400.27  4934.2  400.77  4942.1  401.47  4952.7  401.14
  4962.8  402.44  4973.8  403.33  4984.3  402.16  5008.2  402.53  5030.2  404.26
  5109.2  404.85  5265.7  405.28  5419.4  407.42  5753.4  415.52  5855.4  417.29
#Mann= 8 ,-1 , 0
  4372.9     .07       0  4379.5     .12       0  4587.4      .1       0
    4929    .035       0  4934.2      .1       0  4962.8    .035       0
  5030.2      .1       0  5109.2     .05       0
Bank Sta=4929,4934.2
XS Rating Curve= 0 ,0
Exp/Cntr=0.3,0.1

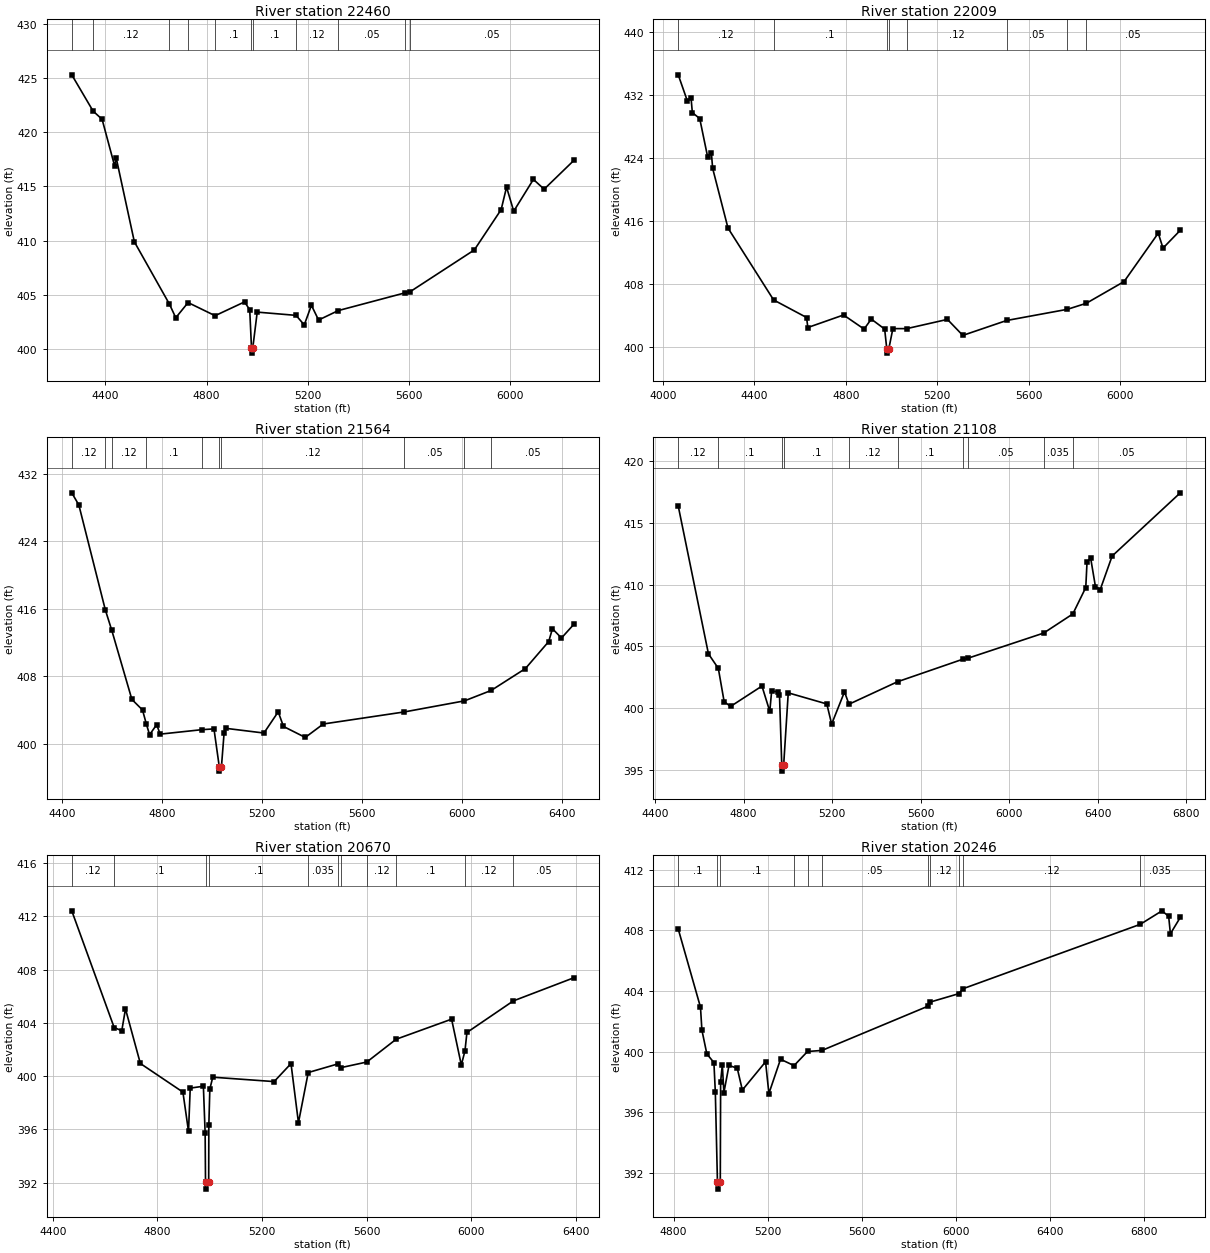
Type RM Length L Ch R = 1 ,22460   ,451,451,451
BEGIN DESCRIPTION:
A19665
END DESCRIPTION:
XS GIS Cut Line= 4
      2507158.32     13841920.07      2506679.15     13841513.82
      2506392.69     13841498.19      2505627.08     13842242.97
#Sta/Elev= 30
  4267.7  425.28  4351.9  421.94  4387.5  421.18  4436.9  416.89  4443.5  417.59
  4514.9  409.89  4653.4  404.15  4678.5  402.89  4727.1  404.29  4833.8  403.08
  4950.1  404.35  4970.6  403.63  4977.6  400.13    4978  399.63  4982.8  400.13
  5000.2  403.41  5153.6  403.11    5186  402.23  5214.3  404.04  5242.6  402.68
  5320.2  403.55  5584.8  405.19  5602.9  405.27  5857.8  409.14  5963.8  412.86
  5985.1  414.93  6013.4  412.71  6091.1  415.64  6133.6  414.74  6250.9  417.39
#Mann= 11 ,-1 , 0
  4267.7    .035       0  4351.9     .12       0  4653.4      .1       0
  4727.1     .12       0  4833.8      .1       0  4977.6     .05       0
  4982.8      .1       0  5153.6     .12       0  5320.2     .05       0
  5584.8    .035       0  5602.9     .05       0
Bank Sta=4977.6,4982.8
XS Rating Curve= 0 ,0
Exp/Cntr=0.3,0.1

Type RM Length L Ch R = 1 ,22009   ,445,445,445
BEGIN DESCRIPTION:
A19664
END DESCRIPTION:
XS GIS Cut Line= 3
      2507418.72     13840763.82      2506319.77     13841326.32
      2505731.23     13842086.73
#Sta/Elev= 30
  4066.9  434.54  4106.4  431.26    4123  431.58  4128.6  429.75  4160.9  428.99
  4195.2  424.17  4211.8  424.65  4217.4  422.68  4284.5   415.1    4484  405.98
  4628.2  403.75  4633.8  402.48    4790  404.07  4879.9  402.28  4911.2  403.55
  4969.8  402.28  4979.2  399.73  4979.7  399.23  4987.7  399.73  5005.7  402.34
  5066.7  402.34  5244.3  403.51  5311.7  401.48  5503.2  403.37  5769.2  404.79
  5851.5  405.55  6017.1  408.31  6166.5  414.45  6187.3  412.55    6263  414.82
#Mann= 8 ,-1 , 0
  4066.9     .12       0    4484      .1       0  4979.2     .05       0
  4987.7      .1       0  5066.7     .12       0  5503.2     .05       0
  5769.2    .035       0  5851.5     .05       0
Bank Sta=4979.2,4987.7
XS Rating Curve= 0 ,0
Exp/Cntr=0.3,0.1

Type RM Length L Ch R = 1 ,21564   ,456,456,456
BEGIN DESCRIPTION:
Little Cooperas Creek 33.0
END DESCRIPTION:
XS GIS Cut Line= 3
      2506925.02     13840424.98        2506525.       13840825.
      2505725.02     13842024.97
#Sta/Elev= 30
  4438.9  429.74  4467.2   428.3  4573.1  415.88  4598.8  413.47  4679.3  405.28
  4721.8  404.03  4737.5  402.33  4750.1   401.1  4778.3  402.29  4792.5  401.17
  4959.9   401.7  5007.6  401.79  5028.9  397.29  5029.4  396.79  5037.4  397.29
  5048.2  401.36  5054.2  401.86  5207.4   401.3  5264.5  403.81  5285.5  402.08
  5372.7  400.78  5444.8  402.37  5769.2   403.8  6009.5  405.11    6116  406.34
    6253  408.93  6346.2  412.13  6361.2  413.65  6397.3  412.55  6446.8  414.17
#Mann= 10 ,-1 , 0
  4438.9     .12       0  4573.1      .1       0  4598.8     .12       0
  4737.5      .1       0  4959.9     .12       0  5028.9     .05       0
  5037.4     .12       0  5769.2     .05       0  6009.5    .035       0
    6116     .05       0
Bank Sta=5028.9,5037.4
XS Rating Curve= 0 ,0
Exp/Cntr=0.3,0.1

Type RM Length L Ch R = 1 ,21108   ,438,438,438
BEGIN DESCRIPTION:
Little Cooperas Creek 32.0
END DESCRIPTION:
XS GIS Cut Line= 3
      2506774.98     13840275.01        2506375.       13840575.
      2505525.02     13842124.96
#Sta/Elev= 30
  4504.4  416.36  4640.8  404.39  4685.5  403.21  4711.7  400.52  4740.8  400.13
  4882.5  401.78  4917.9  399.73  4926.3  401.37  4954.4  401.32  4961.7  401.07
    4972  395.39  4972.5  394.89  4980.6  395.39  5001.3  401.23  5175.5  400.33
  5197.3   398.7  5255.3  401.31  5275.6  400.31  5494.9  402.13  5789.2  403.95
  5812.1  404.03  6154.7  406.07  6286.6  407.62  6345.1  409.76  6350.8  411.83
  6366.9  412.17  6388.7  409.84  6410.5   409.6  6464.2  412.31  6772.1  417.43
#Mann= 10 ,-1 , 0
  4504.4     .12       0  4685.5      .1       0    4972     .05       0
  4980.6      .1       0  5275.6     .12       0  5494.9      .1       0
  5789.2     .12       0  5812.1     .05       0  6154.7    .035       0
  6286.6     .05       0
Bank Sta=4972,4980.6
XS Rating Curve= 0 ,0
Exp/Cntr=0.3,0.1

Type RM Length L Ch R = 1 ,20670   ,424,424,424
BEGIN DESCRIPTION:
Little Cooperas Creek 31.0
END DESCRIPTION:
XS GIS Cut Line= 3
        2506675.       13839925.        2506275.       13840275.
      2505574.98     13841475.04
#Sta/Elev= 30
  4472.1  412.42  4634.3  403.65  4663.4  403.41  4677.6  405.05  4734.5  400.95
  4897.3   398.8  4918.7  395.85  4925.3   399.1  4975.6  399.24  4982.3  395.74
  4983.8  392.01  4984.3  391.51  4995.9  392.01  4996.5  396.33  5000.3  399.03
  5011.5  399.92  5246.3  399.59  5310.8  400.94  5339.3   396.5  5376.7  400.27
  5488.8  400.91  5502.3  400.64  5600.9  401.06  5712.9  402.77  5925.2  404.28
  5962.4  400.84  5976.3  401.89  5983.9  403.28  6161.2  405.65  6392.9  407.39
#Mann= 11 ,-1 , 0
  4472.1     .12       0  4634.3      .1       0  4983.8     .05       0
  4995.9      .1       0  5376.7    .035       0  5488.8     .12       0
  5502.3    .035       0  5600.9     .12       0  5712.9      .1       0
  5976.3     .12       0  6161.2     .05       0
Bank Sta=4983.8,4995.9
XS Rating Curve= 0 ,0
Exp/Cntr=0.3,0.1

Type RM Length L Ch R = 1 ,20246   ,423,423,423
BEGIN DESCRIPTION:
Little Cooperas Creek 30.0
END DESCRIPTION:
XS GIS Cut Line= 3
      2506324.99     13839775.02        2506225.       13839925.
      2504923.95      13841383.6
#Sta/Elev= 30
  4819.8  408.09  4914.4  402.94  4920.4  401.43  4941.5  399.86  4971.5  399.29
  4977.5  397.35  4986.5  391.45    4987  390.95  4998.6  391.45  5000.1  398.03
  5007.2  399.14  5013.9  397.31  5035.6   399.1  5070.7  398.92  5092.4  397.48
  5191.1  399.34  5205.3  397.25  5254.7  399.51  5312.2  399.09  5369.5  400.02
  5430.9  400.09  5883.9  403.02  5889.5  403.27  6012.5  403.83  6031.2  404.16
  6784.2   408.4  6876.6  409.29    6905  408.93  6912.5  407.78  6954.6  408.86
#Mann= 11 ,-1 , 0
  4819.8      .1       0  4986.5     .05       0  4998.6      .1       0
  5312.2     .05       0  5369.5      .1       0  5430.9     .05       0
  5883.9    .035       0  5889.5     .12       0  6012.5     .05       0
  6031.2     .12       0  6784.2    .035       0
Bank Sta=4986.5,4998.6
XS Rating Curve= 0 ,0
Exp/Cntr=0.3,0.1