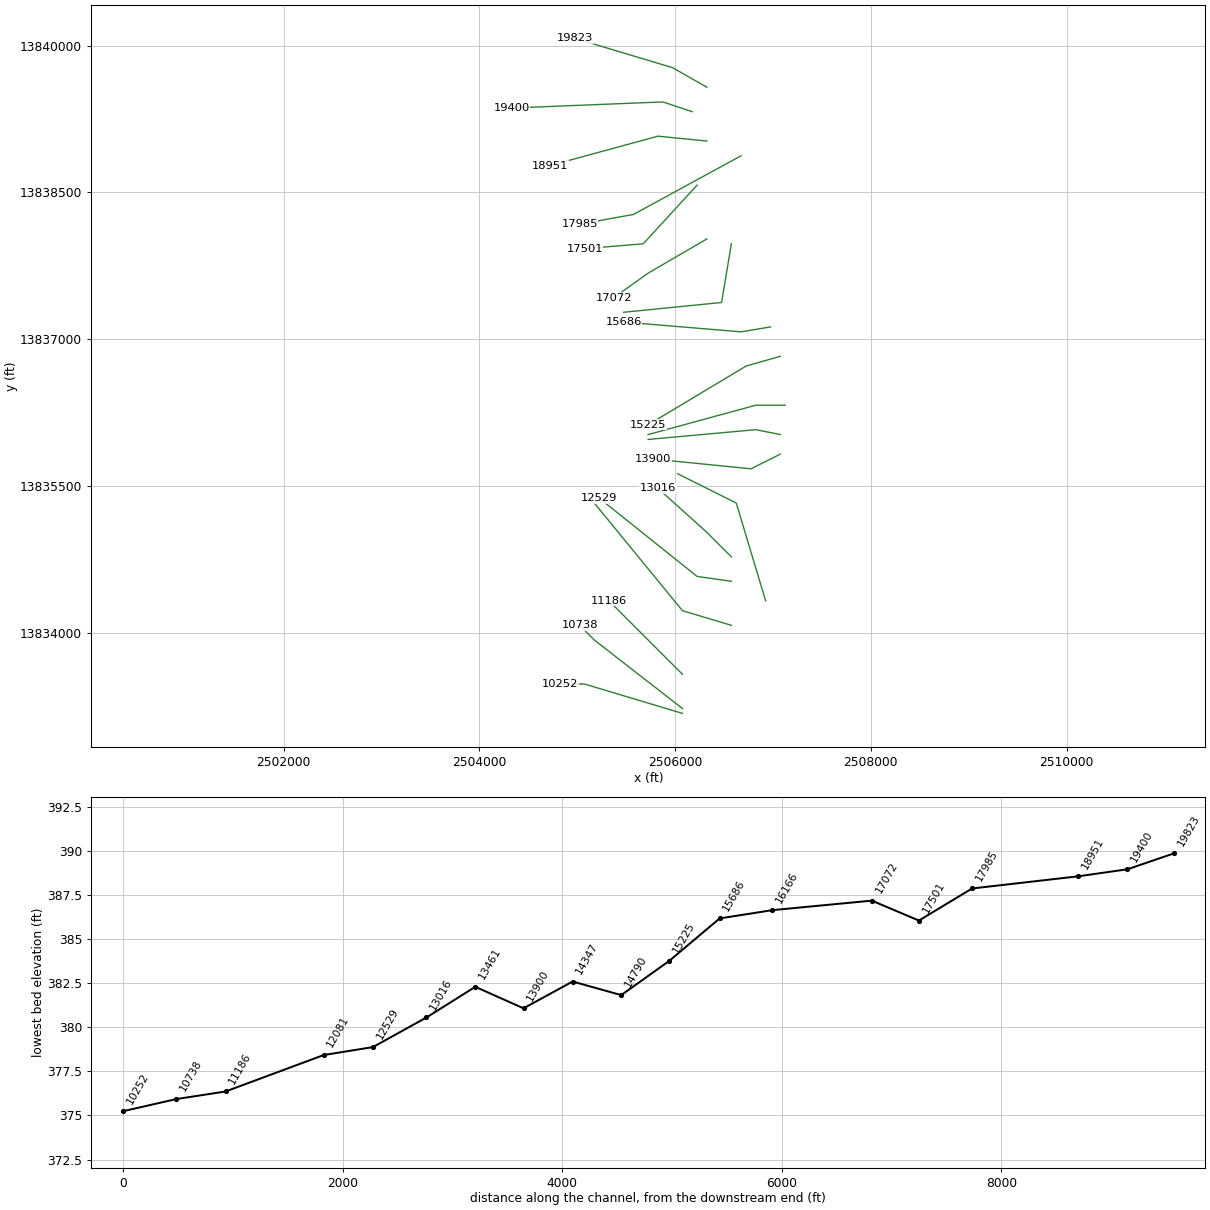
HEC-RAS study Little Copperas Creek.prj: Little Copperas Creek Base Level Eng

--- Little Copperas Creek.g01 (geometry) --- (continued)

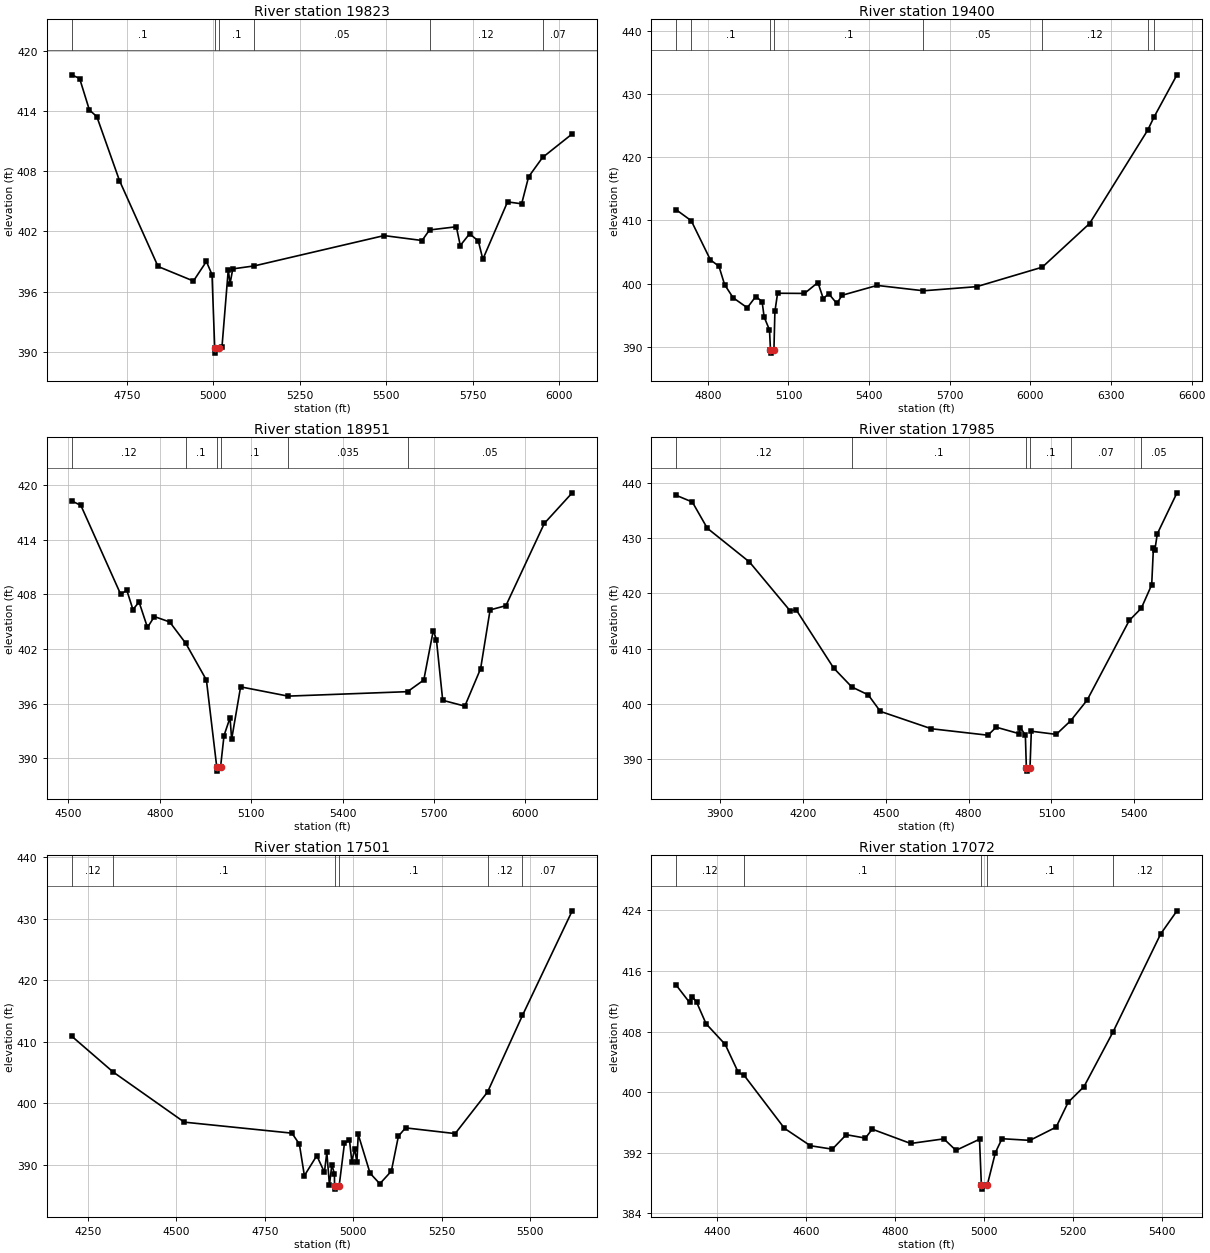
Type RM Length L Ch R = 1 ,19823   ,423,423,423
BEGIN DESCRIPTION:
Little Cooperas Creek 29.0
END DESCRIPTION:
XS GIS Cut Line= 3
      2506324.97     13839575.02        2505975.       13839775.
      2504975.01       13840075.
#Sta/Elev= 30
  4590.5  417.62  4613.5  417.25  4641.6  414.12  4663.2  413.45  4728.7  407.07
  4840.2  398.51  4942.5  397.06  4979.9  399.01  4996.2   397.7    5004  390.37
  5004.5  389.87  5016.2  390.37  5024.9  390.44  5043.2  398.18  5048.4   396.8
  5056.2  398.27  5118.8  398.57  5493.8  401.59  5603.5   401.1    5625  402.15
  5702.6  402.47    5714   400.6  5740.9  401.77  5766.2  401.05  5779.2  399.23
  5850.6  404.95  5891.4  404.76  5911.5  407.45  5951.9  409.38  6037.6  411.73
#Mann= 6 ,-1 , 0
  4590.5      .1       0    5004     .05       0  5016.2      .1       0
  5118.8     .05       0    5625     .12       0  5951.9     .07       0
Bank Sta=5004,5016.2
XS Rating Curve= 0 ,0
Exp/Cntr=0.3,0.1

Type RM Length L Ch R = 1 ,19400   ,449,449,449
BEGIN DESCRIPTION:
Little Cooperas Creek 28.0
END DESCRIPTION:
XS GIS Cut Line= 3
        2506175.       13839325.        2505875.       13839425.
      2504330.18     13839362.77
#Sta/Elev= 30
  4683.1  411.66  4738.2  409.95  4809.6  403.74  4841.2  402.74  4862.3  399.82
  4893.9  397.75  4946.6  396.16  4978.2  397.94  5001.8  397.14  5009.3   394.7
  5029.3  392.65    5033  389.47  5033.5  388.97  5045.8  389.47  5049.4  395.57
  5059.4  398.46  5159.5  398.43  5209.5  400.16  5229.5   397.6  5249.5   398.4
  5279.6  396.84  5299.6  398.14  5429.7   399.7  5602.3  398.85    5800   399.5
  6044.3  402.59  6220.3  409.51  6436.3  424.29  6460.2  426.39  6545.4  433.07
#Mann= 8 ,-1 , 0
  4683.1     .12       0  4738.2      .1       0    5033     .05       0
  5045.8      .1       0  5602.3     .05       0  6044.3     .12       0
  6436.3     .07       0  6460.2     .12       0
Bank Sta=5033,5045.8
XS Rating Curve= 0 ,0
Exp/Cntr=0.3,0.1

Type RM Length L Ch R = 1 ,18951   ,966,966,966
BEGIN DESCRIPTION:
Little Cooperas Creek 27.0
END DESCRIPTION:
XS GIS Cut Line= 3
      2506324.95       13839025.        2505825.       13839075.
      2504725.02     13838775.01
#Sta/Elev= 30
    4511  418.29  4541.1   417.8  4671.8  408.02  4691.9  408.46    4712  406.34
  4732.1  407.17  4759.7  404.37  4782.3  405.57  4832.5  404.98  4885.3  402.63
  4953.1  398.59  4986.9  389.07  4987.4  388.57  4999.7  389.07  5010.9  392.48
  5030.7  394.45  5035.9  392.07  5065.3  397.84  5221.1  396.82  5613.2  397.31
  5666.5  398.59  5697.6  404.03  5707.9  403.04  5728.6  396.36  5801.2  395.72
    5853  399.84  5884.1   406.3    5936  406.77  6062.1  415.82  6153.6  419.18
#Mann= 6 ,-1 , 0
    4511     .12       0  4885.3      .1       0  4986.9     .05       0
  4999.7      .1       0  5221.1    .035       0  5613.2     .05       0
Bank Sta=4986.9,4999.7
XS Rating Curve= 0 ,0
Exp/Cntr=0.3,0.1

Type RM Length L Ch R = 1 ,17985   ,484,484,484
BEGIN DESCRIPTION:
Little Cooperas Creek 26.0
END DESCRIPTION:
XS GIS Cut Line= 3
      2506675.04     13838875.02        2505575.       13838275.
      2505024.96     13838174.99
#Sta/Elev= 30
  3742.2   437.7  3799.7  436.51  3853.8  431.78  4006.6  425.67  4153.7  416.85
  4175.6  417.04  4311.3  406.51    4377  403.09  4436.6  401.66  4480.3  398.68
  4664.9  395.54  4869.9  394.37  4899.8  395.82  4981.5  394.67  4987.2  395.76
  5005.4  394.39  5009.1  388.38  5009.6  387.88  5022.1  388.38    5027  395.09
  5117.2  394.52  5169.4  396.98    5229  400.71  5381.5   415.1  5425.2  417.32
  5462.8  421.55  5469.1  428.28  5474.2  427.82  5483.1  430.76  5554.3  438.17
#Mann= 6 ,-1 , 0
  3742.2     .12       0    4377      .1       0  5009.1     .05       0
  5022.1      .1       0  5169.4     .07       0  5425.2     .05       0
Bank Sta=5009.1,5022.1
XS Rating Curve= 0 ,0
Exp/Cntr=0.3,0.1

Type RM Length L Ch R = 1 ,17501   ,429,429,429
BEGIN DESCRIPTION:
Little Cooperas Creek 25.0
END DESCRIPTION:
XS GIS Cut Line= 3
      2506225.01     13838575.01        2505675.       13837975.
      2505075.04       13837925.
#Sta/Elev= 30
  4203.6  410.93  4320.7  405.11  4522.1  396.95  4826.7  395.16  4847.7  393.38
  4861.9  388.25    4897   391.5  4918.6   388.8  4925.4  392.04  4932.8  386.72
  4939.6  390.04    4947  388.51  4947.2  386.56  4947.7  386.06  4960.2  386.56
  4975.3  393.52  4989.5  394.03  4996.3  390.41  5003.7  392.66  5010.5  390.46
  5014.2  394.96  5047.7  388.65  5075.3  386.93  5107.9  388.98  5127.9  394.67
    5148  396.02  5288.5  395.09  5380.2  401.86  5478.8   414.3  5619.6  431.31
#Mann= 6 ,-1 , 0
  4203.6     .12       0  4320.7      .1       0  4947.2     .05       0
  4960.2      .1       0  5380.2     .12       0  5478.8     .07       0
Bank Sta=4947.2,4960.2
XS Rating Curve= 0 ,0
Exp/Cntr=0.3,0.1

Type RM Length L Ch R = 1 ,17072   ,906,906,906
BEGIN DESCRIPTION:
Little Cooperas Creek 24.0
END DESCRIPTION:
XS GIS Cut Line= 3
        2506325.       13838025.        2505725.       13837675.
      2505375.03     13837425.02
#Sta/Elev= 30
  4309.1  414.09  4338.5  411.85  4344.2  412.63  4354.2  411.91  4375.7  409.03
  4418.7   406.3    4448  402.61  4461.3  402.21  4551.8  395.22  4610.1  392.92
  4659.3  392.47  4690.7  394.38  4733.7  393.93    4749  395.11  4835.4  393.22
  4909.9  393.83  4937.2  392.31  4990.1  393.78  4994.3  387.69  4994.8  387.19
  5007.4  387.69  5025.8  392.02  5040.6  393.85  5103.3  393.63  5162.3  395.38
  5189.3  398.66  5224.9  400.73  5290.2  407.96    5397  420.88  5433.8  423.95
#Mann= 5 ,-1 , 0
  4309.1     .12       0  4461.3      .1       0  4994.3     .05       0
  5007.4      .1       0  5290.2     .12       0
Bank Sta=4994.3,5007.4
XS Rating Curve= 0 ,0
Exp/Cntr=0.3,0.1

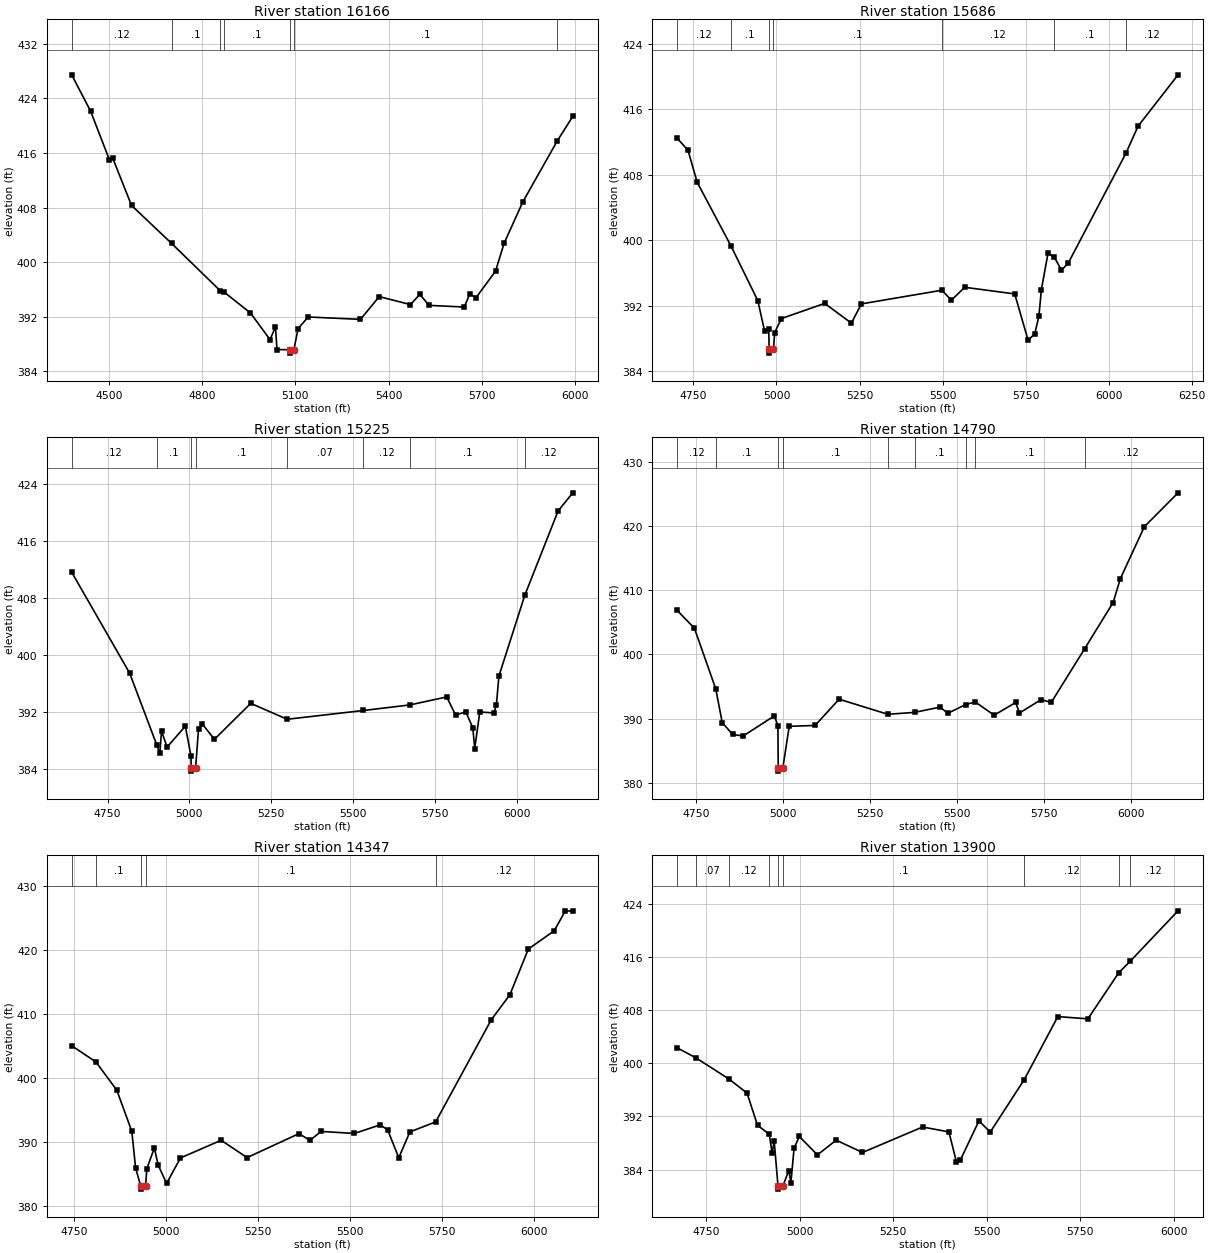
Type RM Length L Ch R = 1 ,16166   ,480,480,480
BEGIN DESCRIPTION:
Little Cooperas Creek 23.0
END DESCRIPTION:
XS GIS Cut Line= 3
        2506575.     13837974.97        2506475.       13837375.
      2505475.04       13837275.
#Sta/Elev= 30
    4380  427.46  4440.8  422.13  4501.6  414.97  4511.8  415.27  4572.6  408.31
  4701.5  402.74  4857.7  395.82  4869.8  395.63  4955.3  392.55  5018.4  388.64
    5036  390.47    5041  387.17  5082.2  387.15  5082.7  386.65  5095.3  387.15
  5108.8  390.24  5141.5  391.95  5309.8   391.6  5370.1  394.94  5470.6  393.77
  5500.8  395.26  5530.9  393.65    5644  393.41  5661.6  395.34  5681.7  394.78
  5744.5  398.66  5772.1  402.75  5832.4  408.82  5943.6  417.79  5993.2  421.36
#Mann= 7 ,-1 , 0
    4380     .12       0  4701.5      .1       0  4857.7     .12       0
  4869.8      .1       0  5082.2     .05       0  5095.3      .1       0
  5943.6     .12       0
Bank Sta=5082.2,5095.3
XS Rating Curve= 0 ,0
Exp/Cntr=0.3,0.1

Type RM Length L Ch R = 1 ,15686   ,461,461,461
BEGIN DESCRIPTION:
Little Cooperas Creek 22.0
END DESCRIPTION:
XS GIS Cut Line= 3
      2506974.98       13837125.        2506675.       13837075.
      2505474.98       13837175.
#Sta/Elev= 30
  4700.6  412.47  4733.5     411  4761.4  407.06  4862.5  399.33  4943.9  392.59
  4964.2  388.87  4976.8  389.12  4977.8  386.68  4978.3  386.18    4991  386.68
  4994.6  388.69  5014.8  390.41  5145.2  392.26  5225.5  389.85  5255.6   392.2
  5497.9  393.87  5526.5  392.65  5566.7  394.23  5717.2  393.42  5757.3  387.78
  5777.4  388.52  5789.9  390.68  5797.5  393.96  5817.5  398.41  5836.9  397.88
  5857.7  396.33  5877.7  397.14  6052.1  410.63  6088.5  413.93  6208.9  420.21
#Mann= 7 ,-1 , 0
  4700.6     .12       0  4862.5      .1       0  4977.8     .05       0
    4991      .1       0  5497.9     .12       0  5836.9      .1       0
  6052.1     .12       0
Bank Sta=4977.8,4991
XS Rating Curve= 0 ,0
Exp/Cntr=0.3,0.1

Type RM Length L Ch R = 1 ,15225   ,435,435,435
BEGIN DESCRIPTION:
Little Cooperas Creek 21.0
END DESCRIPTION:
XS GIS Cut Line= 3
      2507074.97     13836824.99        2506725.       13836725.
      2505724.97     13836124.98
#Sta/Elev= 30
  4640.6  411.64  4817.4  397.51  4900.6   387.4  4909.7  386.24  4914.9  389.37
  4931.8  387.13  4987.7  390.06  5004.6  385.94  5005.8  384.26  5006.3  383.76
    5019  384.26  5027.9  389.65  5039.6  390.36  5076.5  388.22  5187.3  393.26
  5298.6  391.03  5531.6  392.26  5673.6  393.04  5785.9  394.16  5813.1  391.61
  5844.2  392.07  5865.6  389.84  5871.4  386.93    5887  392.06  5929.8  391.91
  5937.5     393  5945.3  397.08  6024.3   408.4  6126.1  420.23  6170.8  422.77
#Mann= 8 ,-1 , 0
  4640.6     .12       0  4900.6      .1       0  5005.8     .05       0
    5019      .1       0  5298.6     .07       0  5531.6     .12       0
  5673.6      .1       0  6024.3     .12       0
Bank Sta=5005.8,5019
XS Rating Curve= 0 ,0
Exp/Cntr=0.3,0.1

Type RM Length L Ch R = 1 ,14790   ,443,443,443
BEGIN DESCRIPTION:
Little Cooperas Creek 20.0
END DESCRIPTION:
XS GIS Cut Line= 3
      2507125.01       13836325.        2506825.       13836325.
      2505724.98       13836025.
#Sta/Elev= 30
    4695  406.88    4745  404.08  4806.3  394.64    4825  389.38    4855  387.54
    4885   387.3    4975  390.44    4985  388.86  4985.9  382.33  4986.4  381.83
  4999.1  382.33  5017.5  388.81  5091.8  388.94  5160.9  393.03  5301.1  390.68
  5378.1  390.98  5451.1   391.8  5473.5  390.84    5525   392.2  5552.2   392.6
  5606.6  390.54  5668.7  392.53  5679.1  390.87  5741.3  392.96  5770.7  392.53
  5866.5  400.87  5948.6  408.09  5969.3   411.8  6038.4   419.9  6135.2  425.17
#Mann= 9 ,-1 , 0
    4695     .12       0  4806.3      .1       0  4985.9     .05       0
  4999.1      .1       0  5301.1     .07       0  5378.1      .1       0
    5525     .12       0  5552.2      .1       0  5866.5     .12       0
Bank Sta=4985.9,4999.1
XS Rating Curve= 0 ,0
Exp/Cntr=0.3,0.1

Type RM Length L Ch R = 1 ,14347   ,447,447,447
BEGIN DESCRIPTION:
Little Cooperas Creek 19.0
END DESCRIPTION:
XS GIS Cut Line= 3
      2507074.97     13836025.01        2506825.       13836075.
      2505724.96       13835975.
#Sta/Elev= 30
  4744.3  404.99  4810.2  402.45  4866.6  398.05  4907.4  391.61  4917.6  385.92
  4931.4   383.1  4931.9   382.6  4944.6   383.1  4948.2   385.8  4968.6  389.03
  4978.8  386.36  5001.7  383.49  5039.4  387.47  5149.8  390.23  5220.1  387.52
  5360.7  391.26  5390.8  390.22    5421  391.61  5511.3  391.29  5581.6  392.64
  5601.7  391.83  5631.8   387.5  5661.9  391.53  5731.9   393.1  5882.9  409.06
  5933.1  412.93  5983.3  420.08  6053.6  422.94  6083.7  426.05  6103.8  426.01
#Mann= 5 ,-1 , 0
  4744.3     .12       0  4810.2      .1       0  4931.4     .05       0
  4944.6      .1       0  5731.9     .12       0
Bank Sta=4931.4,4944.6
XS Rating Curve= 0 ,0
Exp/Cntr=0.3,0.1

Type RM Length L Ch R = 1 ,13900   ,439,439,439
BEGIN DESCRIPTION:
Little Cooperas Creek 18.0
END DESCRIPTION:
XS GIS Cut Line= 3
      2507075.03     13835825.02        2506775.       13835675.
      2505775.03       13835775.
#Sta/Elev= 30
  4671.6  402.33  4721.5  400.84  4809.7  397.67  4858.9  395.52  4886.9  390.68
  4918.4  389.33    4926  386.53  4931.6  388.27  4941.7  381.58  4942.2  381.08
    4955  381.58  4970.7  383.88  4976.3  382.07  4984.7  387.21  4998.7     389
  5047.2  386.23  5097.5  388.44  5167.8  386.59  5328.6  390.42    5399  389.68
  5419.1  385.17  5429.1  385.39  5479.4  391.35  5509.5  389.65  5600.6  397.55
  5690.4  407.02  5770.8  406.68  5853.4  413.62  5883.5  415.31    6012  422.92
#Mann= 9 ,-1 , 0
  4671.6     .12       0  4721.5     .07       0  4809.7     .12       0
  4918.4      .1       0  4941.7     .05       0    4955      .1       0
  5600.6     .12       0  5853.4     .07       0  5883.5     .12       0
Bank Sta=4941.7,4955
XS Rating Curve= 0 ,0
Exp/Cntr=0.3,0.1

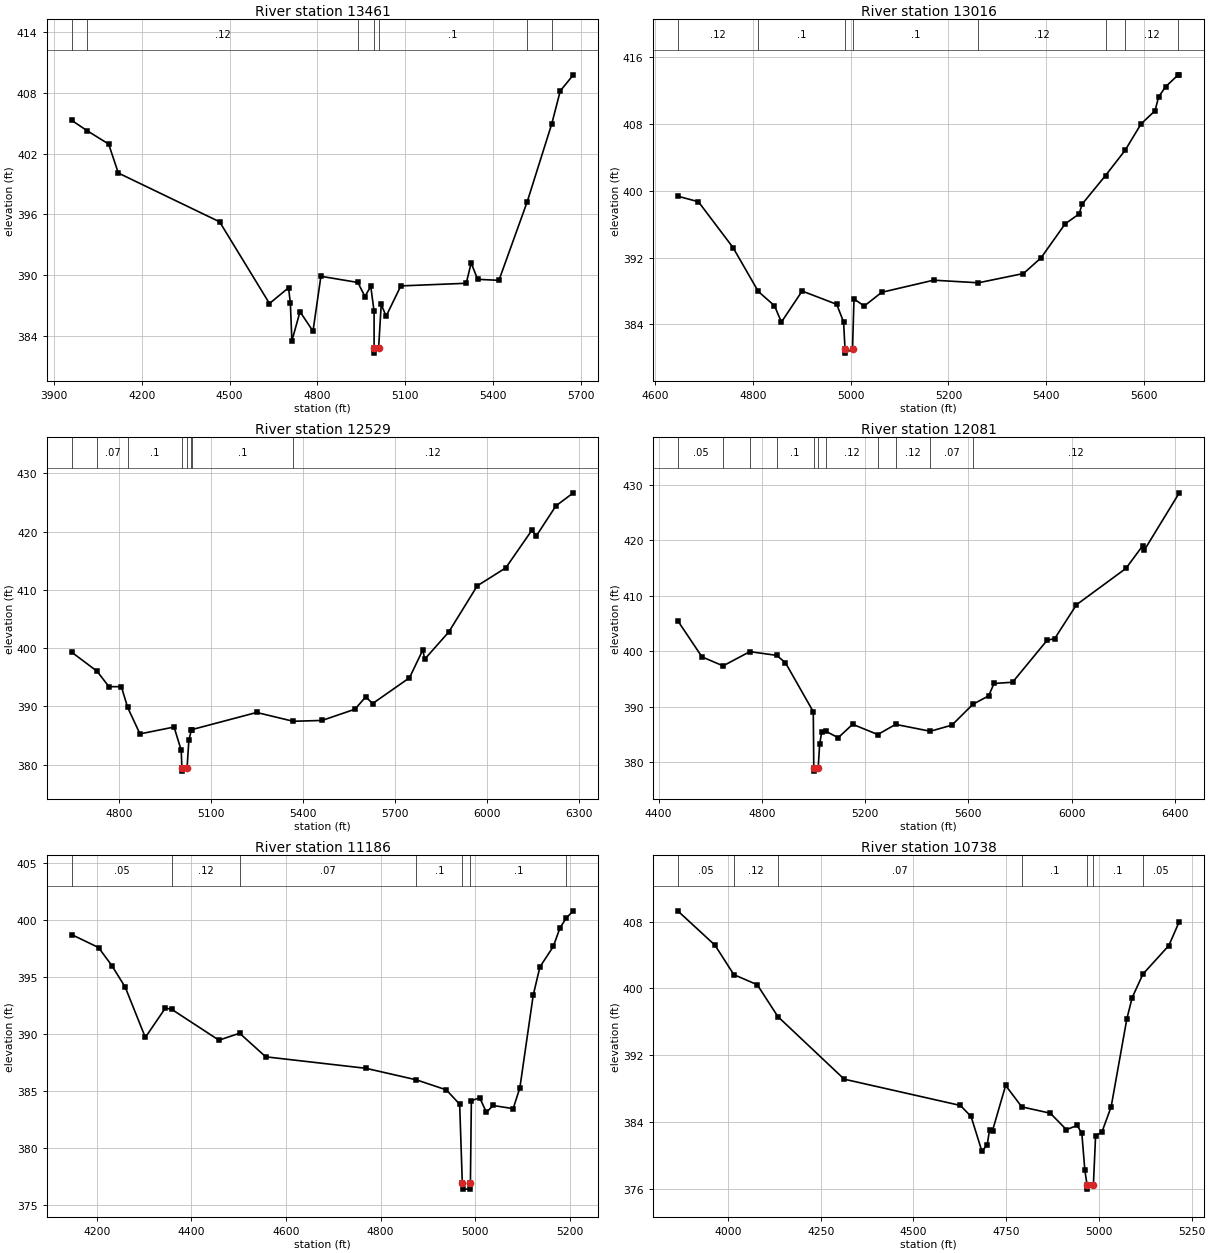
Type RM Length L Ch R = 1 ,13461   ,445,445,445
BEGIN DESCRIPTION:
Little Cooperas Creek 17.0
END DESCRIPTION:
XS GIS Cut Line= 3
      2506925.01     13834324.98        2506625.       13835325.
      2506024.97     13835625.01
#Sta/Elev= 30
  3960.3  405.29  4013.4  404.26  4086.5  402.95  4119.5  400.09  4465.8  395.27
  4636.3   387.2  4701.6  388.76  4707.7  387.21  4712.9  383.51  4740.7  386.39
  4785.1  384.47  4812.1  389.89  4938.5  389.28  4962.6  387.89  4982.6   388.9
  4993.9  386.42    4994   382.8  4994.5   382.3  5009.4   382.8  5018.3  387.11
  5035.1  385.95  5085.4  388.94    5309   389.2  5325.8   391.2  5348.1  389.59
  5420.8  389.49  5517.3  397.24  5601.3  404.94  5630.4   408.2  5675.2  409.79
#Mann= 7 ,-1 , 0
  3960.3     .05       0  4013.4     .12       0  4938.5      .1       0
    4994     .05       0  5009.4      .1       0  5517.3     .12       0
  5601.3     .07       0
Bank Sta=4994,5009.4
XS Rating Curve= 0 ,0
Exp/Cntr=0.3,0.1

Type RM Length L Ch R = 1 ,13016   ,487,487,487
BEGIN DESCRIPTION:
Little Cooperas Creek 16.0
END DESCRIPTION:
XS GIS Cut Line= 3
      2506575.01     13834774.99        2506325.       13835025.
      2505824.96     13835475.03
#Sta/Elev= 30
    4646  399.37  4688.4   398.7  4759.2  393.21  4810.9  387.95    4844  386.24
  4858.2  384.28  4900.6     388  4971.3  386.41  4985.4   384.3  4988.3  381.06
  4988.8  380.56  5003.7  381.06  5006.7  387.06  5027.6   386.2  5063.5  387.85
  5169.6   389.3  5261.3  388.99  5353.5   390.1  5389.4  391.98  5438.7  396.05
  5467.1  397.23  5473.8  398.44  5521.3  401.84  5561.5  404.87  5594.1  408.03
  5622.5   409.6    5630  411.26  5644.2  412.48  5670.1  413.91  5672.3  413.91
#Mann= 8 ,-1 , 0
    4646     .12       0  4810.9      .1       0  4988.3     .05       0
  5003.7      .1       0  5261.3     .12       0  5521.3     .07       0
  5561.5     .12       0  5670.1     .07       0
Bank Sta=4988.3,5003.7
XS Rating Curve= 0 ,0
Exp/Cntr=0.3,0.1

Type RM Length L Ch R = 1 ,12529   ,448,448,448
BEGIN DESCRIPTION:
Little Cooperas Creek 15.0
END DESCRIPTION:
XS GIS Cut Line= 3
      2506574.96     13834525.01        2506225.       13834575.
      2505225.03     13835374.98
#Sta/Elev= 30
    4646  399.29  4728.2  396.04  4767.2  393.38  4807.6  393.38  4828.2  389.81
  4868.2  385.27  4979.3  386.45  5002.7  382.44  5004.7  379.38  5005.2  378.88
  5021.6  379.38  5027.5  384.17  5035.8  385.97  5036.7     386  5248.4  388.95
  5367.3  387.44  5461.3  387.58  5568.6  389.51  5603.8  391.63  5626.2  390.48
  5746.3  394.91  5789.5  399.67  5795.9   398.1  5874.3  402.77  5967.2   410.7
    6060  413.78  6144.9  420.23  6159.3  419.25  6223.3  424.42  6280.1  426.66
#Mann= 8 ,-1 , 0
    4646     .12       0  4728.2     .07       0  4828.2      .1       0
  5004.7     .05       0  5021.6      .1       0  5035.8     .12       0
  5036.7      .1       0  5367.3     .12       0
Bank Sta=5004.7,5021.6
XS Rating Curve= 0 ,0
Exp/Cntr=0.3,0.1

Type RM Length L Ch R = 1 ,12081   ,895,895,895
BEGIN DESCRIPTION:
Little Cooperas Creek 14.0
END DESCRIPTION:
XS GIS Cut Line= 3
        2506575.       13834075.        2506075.       13834225.
      2505174.99     13835325.01
#Sta/Elev= 30
  4473.9  405.54  4567.9  399.01  4649.7  397.39  4753.4  399.95  4857.5  399.28
  4891.5  397.94  4999.2  389.13  5001.1  378.93  5001.6  378.43  5018.1  378.93
  5023.9  383.34  5031.8  385.43  5049.1  385.58  5095.7  384.45  5151.7  386.87
    5249  385.02  5318.1  386.85  5452.5  385.61  5536.4  386.72  5617.5  390.47
  5678.6  391.99  5699.4  394.22  5771.2  394.44  5905.4  402.02  5934.1  402.28
  6018.8   408.4  6210.5  414.95  6275.1  419.01  6282.2  418.28  6417.2  428.56
#Mann= 11 ,-1 , 0
  4473.9     .05       0  4649.7     .07       0  4753.4     .12       0
  4857.5      .1       0  5001.1     .05       0  5018.1      .1       0
  5049.1     .12       0    5249      .1       0  5318.1     .12       0
  5452.5     .07       0  5617.5     .12       0
Bank Sta=5001.1,5018.1
XS Rating Curve= 0 ,0
Exp/Cntr=0.3,0.1

Type RM Length L Ch R = 1 ,11186   ,448,448,448
BEGIN DESCRIPTION:
Little Cooperas Creek 13.0
END DESCRIPTION:
XS GIS Cut Line= 3
      2506075.03     13833574.97        2505475.       13834175.
        2505325.       13834325.
#Sta/Elev= 30
  4146.8  398.69  4203.4  397.56  4231.7  395.97    4260  394.07  4302.4  389.67
  4344.8  392.25  4358.4  392.13    4458  389.43  4501.8  390.04    4557  387.97
  4769.1  386.96  4875.5  385.95  4938.8  385.07  4967.1  383.81  4972.7  376.86
  4973.2  376.36  4989.3  376.36  4989.8  376.86  4991.8  384.12  5009.5  384.37
  5023.7   383.1  5037.8   383.7  5080.2  383.42  5094.4  385.25  5122.6  393.37
  5136.8  395.86  5165.1  397.65  5179.2  399.28  5192.5  400.15  5207.5  400.78
#Mann= 7 ,-1 , 0
  4146.8     .05       0  4358.4     .12       0  4501.8     .07       0
  4875.5      .1       0  4972.7     .05       0  4989.8      .1       0
  5192.5     .05       0
Bank Sta=4972.7,4989.8
XS Rating Curve= 0 ,0
Exp/Cntr=0.3,0.1

Type RM Length L Ch R = 1 ,10738   ,486,486,486
BEGIN DESCRIPTION:
Little Cooperas Creek 12.0
END DESCRIPTION:
XS GIS Cut Line= 3
      2506075.02     13833224.98        2505175.       13833925.
      2505025.03     13834074.97
#Sta/Elev= 30
  3864.3  409.29  3964.8  405.17  4015.7  401.64  4078.8  400.43  4134.4  396.61
  4313.2  389.11  4626.3  385.96  4655.2  384.64  4684.2   380.5  4698.6   381.2
    4705  383.03  4713.1  382.95  4748.4  388.36  4791.9  385.79  4868.8  385.03
  4912.2  383.06  4941.2  383.56  4953.8  382.63    4962  378.18  4967.9  376.43
  4968.4  375.93    4985  376.43  4990.9  382.33    5008  382.78  5032.8  385.79
  5075.2  396.34  5089.4  398.87  5118.4   401.7  5188.4  405.13  5216.6  408.01
#Mann= 7 ,-1 , 0
  3864.3     .05       0  4015.7     .12       0  4134.4     .07       0
  4791.9      .1       0  4967.9     .05       0    4985      .1       0
  5118.4     .05       0
Bank Sta=4967.9,4985
XS Rating Curve= 0 ,0
Exp/Cntr=0.3,0.1

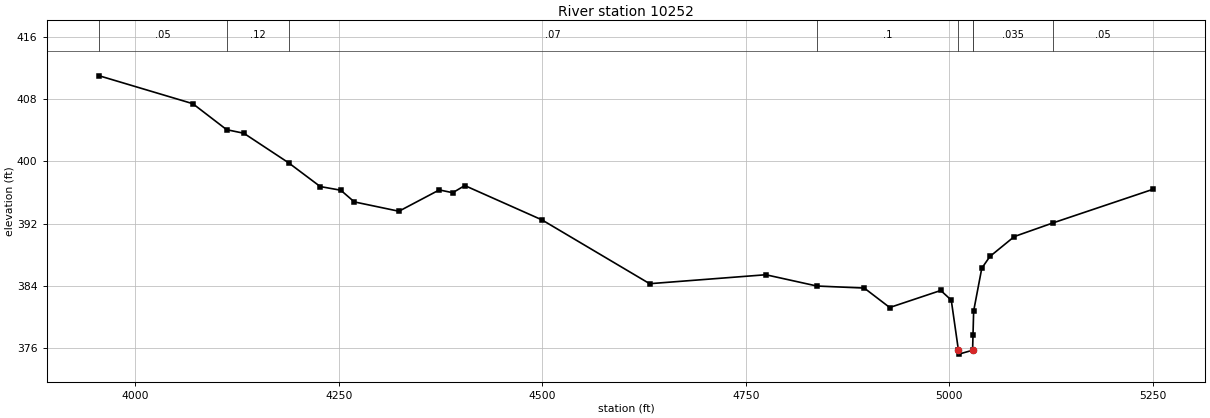
Type RM Length L Ch R = 1 ,10252   ,522,522,522
BEGIN DESCRIPTION:
Little Cooperas Creek 11.0
END DESCRIPTION:
XS GIS Cut Line= 3
      2506074.97     13833175.01        2505075.       13833475.
        2504825.       13833475.
#Sta/Elev= 30
  3955.9     411  4070.7  407.42  4112.3  404.08  4133.4  403.62  4188.3  399.83
  4227.3  396.77  4252.5   396.3  4269.1   394.8  4323.9   393.6  4373.5  396.34
    4390  395.98  4404.8   396.9  4499.6  392.49  4631.9  384.29  4774.6  385.44
  4837.4  383.99  4895.5  383.73  4926.8  381.23  4989.5  383.42  5002.4  382.18
  5011.2  375.74  5011.7  375.24  5028.6  375.74  5029.1  377.68  5029.9  380.78
  5039.9  386.28  5049.9  387.79  5079.9  390.35  5127.6  392.11  5249.9  396.41
#Mann= 8 ,-1 , 0
  3955.9     .05       0  4112.3     .12       0  4188.3     .07       0
  4837.4      .1       0  5011.2     .05       0  5028.6      .1       0
  5029.1    .035       0  5127.6     .05       0
Bank Sta=5011.2,5028.6
XS Rating Curve= 0 ,0
Exp/Cntr=0.3,0.1