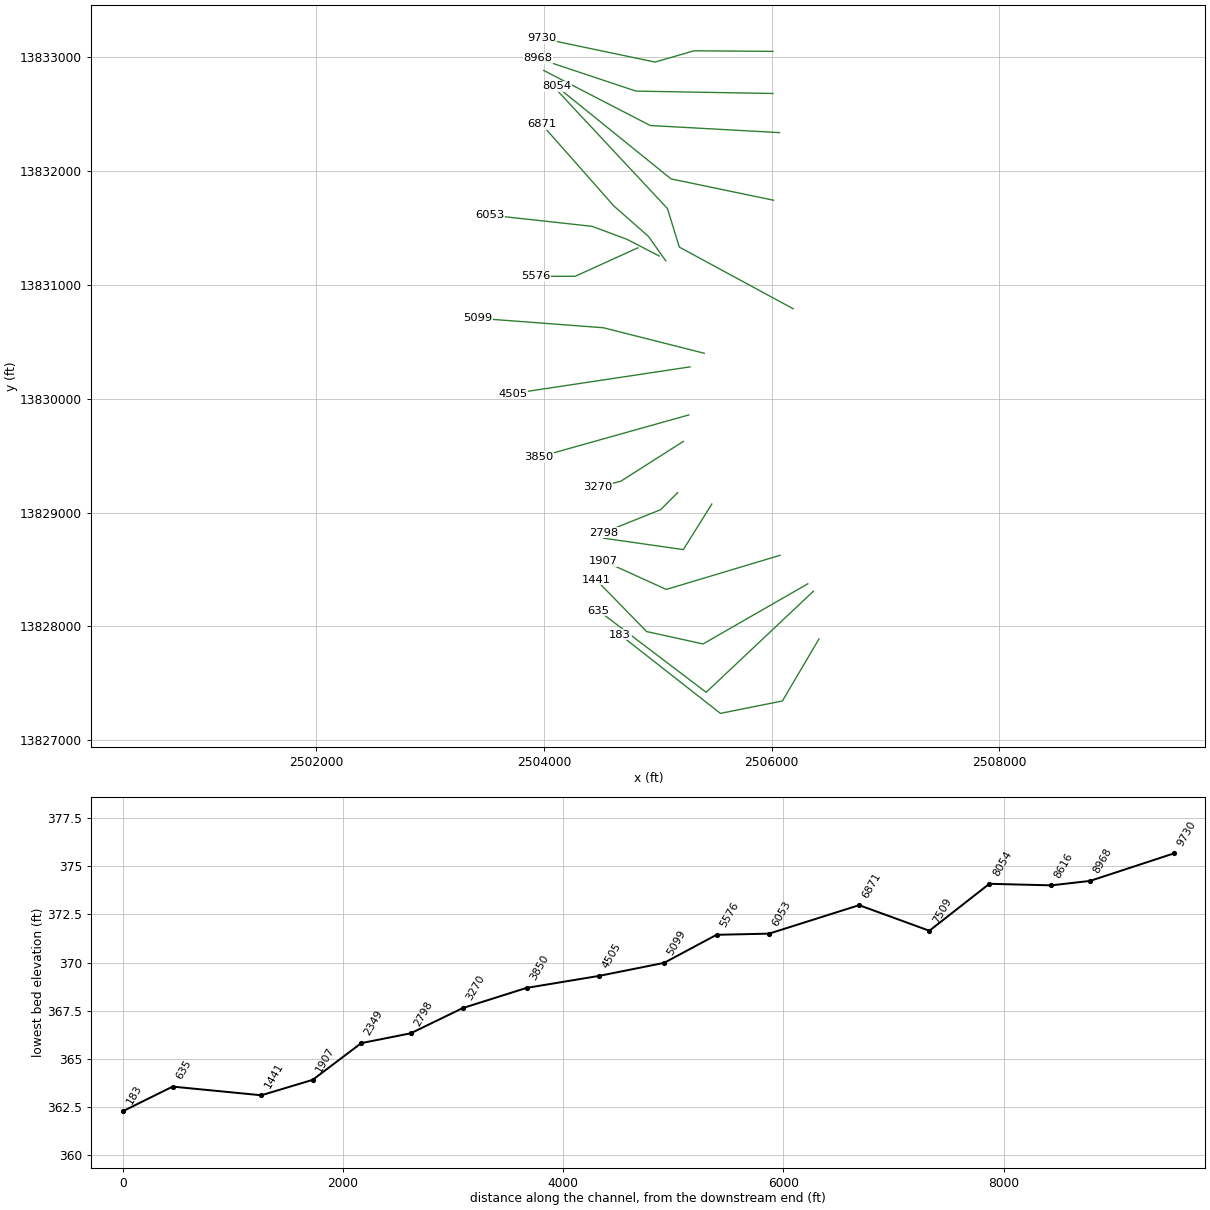
HEC-RAS study Little Copperas Creek.prj: Little Copperas Creek Base Level Eng

--- Little Copperas Creek.g01 (geometry) --- (continued)

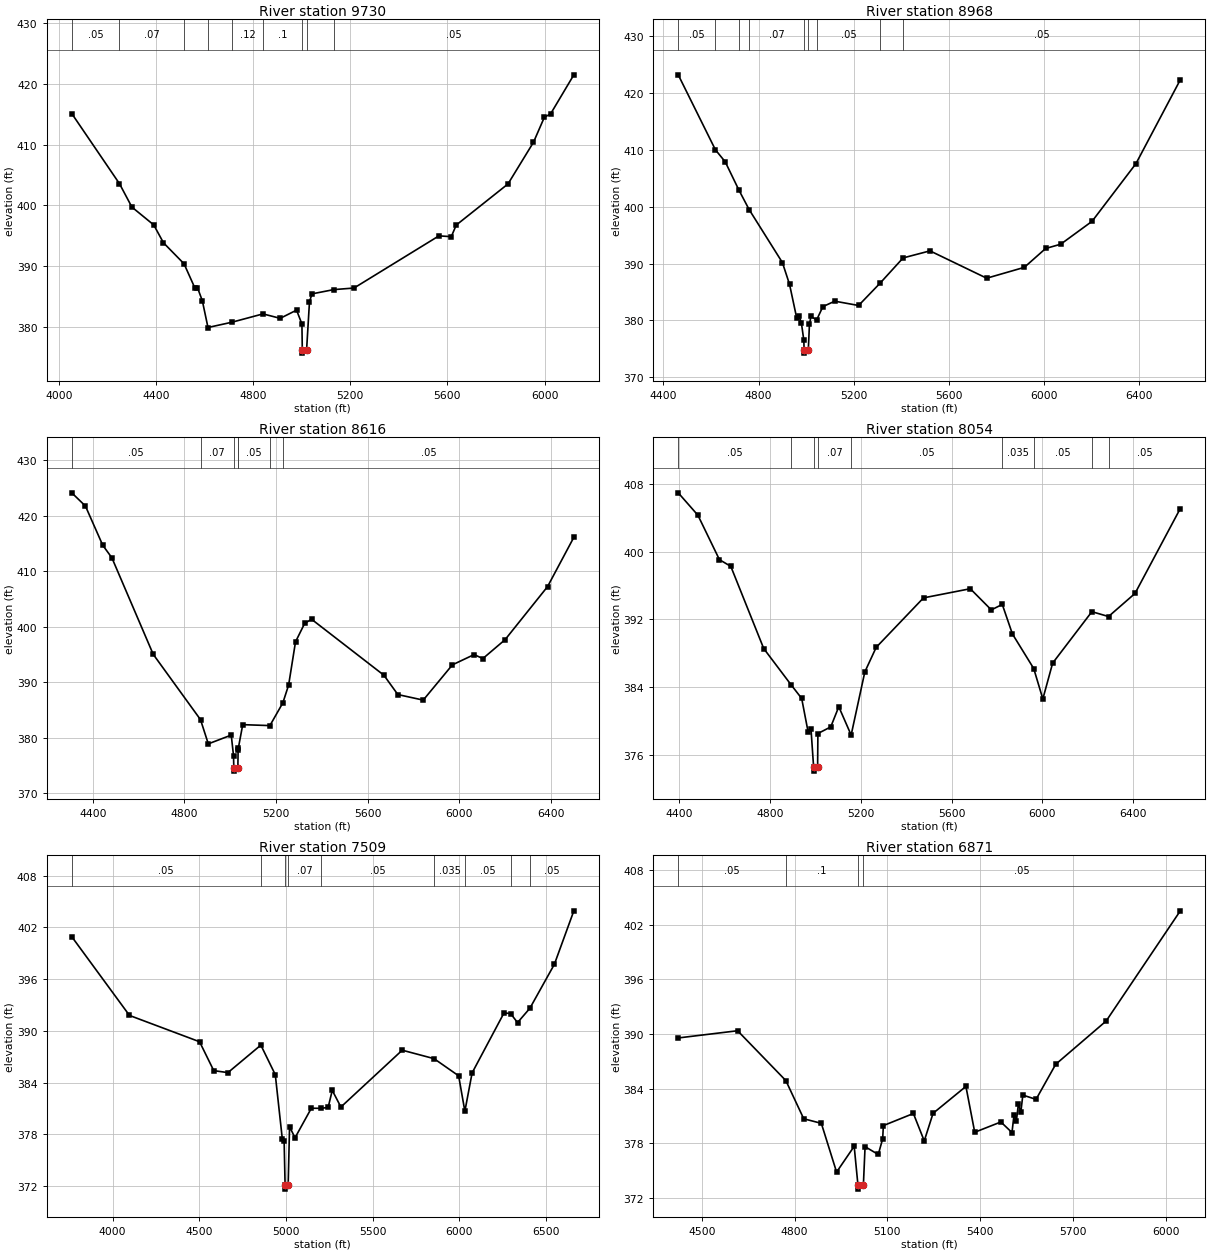
Type RM Length L Ch R = 1 ,9730    ,762,762,762
BEGIN DESCRIPTION:
A19663
END DESCRIPTION:
XS GIS Cut Line= 4
      2506012.45     13833050.27      2505319.77     13833055.48
      2504976.02     13832956.52      2503981.21     13833164.86
#Sta/Elev= 30
  4053.6  415.12    4250  403.57  4301.1  399.72  4391.1  396.78  4431.1  393.84
  4515.8  390.38  4561.1  386.33  4571.1  386.45  4591.1  384.29  4614.3  379.89
  4712.8  380.76  4840.8  382.13  4911.6   381.4    4979  382.75    5001  380.46
  5002.6  376.17  5003.1  375.67  5020.2  376.17  5032.2  384.16  5042.6  385.43
  5132.1  386.13  5215.4  386.39    5565  394.98  5615.9  394.85  5636.3  396.76
  5849.3  403.53  5954.2  410.39  5999.1  414.52  6024.6  415.06  6120.4   421.5
#Mann= 9 ,-1 , 0
  4053.6     .05       0    4250     .07       0  4515.8     .12       0
  4614.3     .07       0  4712.8     .12       0  4840.8      .1       0
  5002.6     .05       0  5020.2      .1       0  5132.1     .05       0
Bank Sta=5002.6,5020.2
XS Rating Curve= 0 ,0
Exp/Cntr=0.3,0.1

Type RM Length L Ch R = 1 ,8968    ,352,352,352
BEGIN DESCRIPTION:
A19662
END DESCRIPTION:
XS GIS Cut Line= 3
      2506012.49     13832680.48      2504809.36     13832701.32
      2503949.96     13832987.78
#Sta/Elev= 30
  4462.3   423.2  4618.5  410.01  4659.8  407.89  4717.1  402.93  4760.2  399.49
  4899.9  390.17  4929.9  386.34  4959.9  380.43  4969.9  380.83  4979.9  379.48
  4989.9   376.5  4991.1  374.74  4991.6  374.24  5008.7  374.74  5013.5  379.32
  5019.9  380.71  5043.5  380.06  5069.9  382.42  5119.9  383.38  5219.9  382.62
  5310.3  386.55    5407  390.99  5519.9  392.23  5758.1  387.42  5916.2  389.33
  6005.8  392.65    6069   393.4  6200.8  397.43  6385.2  407.58  6571.5  422.33
#Mann= 9 ,-1 , 0
  4462.3     .05       0  4618.5     .07       0  4717.1     .05       0
  4760.2     .07       0  4991.1     .05       0  5008.7     .07       0
  5043.5     .05       0  5310.3     .07       0    5407     .05       0
Bank Sta=4991.1,5008.7
XS Rating Curve= 0 ,0
Exp/Cntr=0.3,0.1

Type RM Length L Ch R = 1 ,8616    ,562,562,562
BEGIN DESCRIPTION:
A19661
END DESCRIPTION:
XS GIS Cut Line= 3
      2506069.75     13832336.73      2504934.36     13832399.23
      2503998.41      13832882.8
#Sta/Elev= 30
  4308.6  424.13  4368.2  421.75  4443.6   414.7  4483.6  412.43  4663.9  395.05
  4870.3  383.28  4904.3  378.92  5004.4   380.5  5014.4  376.76  5015.6  374.51
  5016.1  374.01  5033.2  374.51  5034.4  377.86  5035.3  378.14  5054.5  382.38
  5173.1  382.21  5229.6  386.31  5254.8  389.52  5284.8  397.29  5324.9  400.63
  5354.9  401.36  5670.5  391.28  5731.3   387.8    5842   386.8  5969.3  393.15
  6064.1     395  6102.2  394.28  6199.1  397.68  6384.5  407.24  6499.2  416.12
#Mann= 7 ,-1 , 0
  4308.6     .05       0  4870.3     .07       0  5015.6     .05       0
  5033.2     .07       0  5035.3     .05       0  5173.1     .07       0
  5229.6     .05       0
Bank Sta=5015.6,5033.2
XS Rating Curve= 0 ,0
Exp/Cntr=0.3,0.1

Type RM Length L Ch R = 1 ,8054    ,545,545,545
BEGIN DESCRIPTION:
A19660
END DESCRIPTION:
XS GIS Cut Line= 3
      2506017.73     13831742.97      2505116.65     13831930.48
      2504111.44     13832742.98
#Sta/Elev= 30
  4394.7  406.94  4481.3   404.3  4576.3  399.05  4626.4  398.26  4771.5  388.56
  4892.1  384.28  4938.8  382.67  4966.8  378.76  4979.7  379.11  4991.3  374.59
  4991.8  374.09    5009  374.59  5010.3  378.53  5066.9  379.31  5102.3  381.69
  5156.8  378.35  5217.1   385.8  5267.2   388.7  5475.7  394.54  5681.9  395.62
  5774.7  393.12  5822.9  393.77  5867.4  390.29  5961.5   386.2  6001.7  382.61
  6044.9  386.84  6217.8  392.91  6291.2  392.34  6407.8  395.06  6607.6  405.09
#Mann= 9 ,-1 , 0
  4394.7     .05       0  4892.1     .07       0  4991.3     .05       0
    5009     .07       0  5156.8     .05       0  5822.9    .035       0
  5961.5     .05       0  6217.8    .035       0  6291.2     .05       0
Bank Sta=4991.3,5009
XS Rating Curve= 0 ,0
Exp/Cntr=0.3,0.1

Type RM Length L Ch R = 1 ,7509    ,638,638,638
BEGIN DESCRIPTION:
A19659
END DESCRIPTION:
XS GIS Cut Line= 4
       2506189.6     13830789.84      2505189.56     13831331.52
       2505085.4     13831670.07      2504127.07      13832696.1
#Sta/Elev= 30
  3764.6  400.92  4097.4  391.79  4501.6  388.74  4583.4  385.39  4665.2  385.16
    4855  388.35  4938.3  384.92  4978.8  377.47  4989.3  377.21  4994.8  372.15
  4995.3  371.65  5012.6  372.15  5020.6  378.89    5052   377.6  5146.2  381.03
  5201.1  381.02    5243  381.12  5266.9   383.1  5316.7  381.17  5670.4  387.76
  5853.8  386.78  5995.7  384.79  6031.6  380.68  6073.4  385.13  6257.6  392.09
  6295.7     392  6335.3  390.96  6406.5  392.62  6547.8  397.72  6660.1  403.92
#Mann= 9 ,-1 , 0
  3764.6     .05       0    4855     .07       0  4994.8     .05       0
  5012.6     .07       0  5201.1     .05       0  5853.8    .035       0
  6031.6     .05       0  6295.7    .035       0  6406.5     .05       0
Bank Sta=4994.8,5012.6
XS Rating Curve= 0 ,0
Exp/Cntr=0.3,0.1

Type RM Length L Ch R = 1 ,6871    ,818,818,818
BEGIN DESCRIPTION:
A19658
END DESCRIPTION:
XS GIS Cut Line= 4
      2505069.76     13831211.75      2504918.73     13831425.27
      2504616.65      13831690.9      2503981.26     13832409.62
#Sta/Elev= 30
  4424.1  389.57    4616  390.36    4772  384.89  4829.8   380.7  4886.7   380.2
    4936  374.85  4992.9  377.68  5004.9  373.48  5005.4  372.98  5022.7  373.48
  5028.1  377.64  5070.7  376.78    5085   378.5  5087.2  379.95  5184.3  381.28
  5219.4  378.27  5247.9   381.3  5354.1  384.25  5382.6  379.22  5467.1  380.35
    5503  379.19  5509.7  381.15  5517.2  380.44  5523.9  382.36  5531.5  381.39
  5538.1   383.3  5580.8  382.83  5644.4  386.68  5807.5  391.43  6047.2  403.52
#Mann= 4 ,-1 , 0
  4424.1     .05       0    4772      .1       0  5004.9     .05       0
  5022.7     .05       0
Bank Sta=5004.9,5022.7
XS Rating Curve= 0 ,0
Exp/Cntr=0.3,0.1

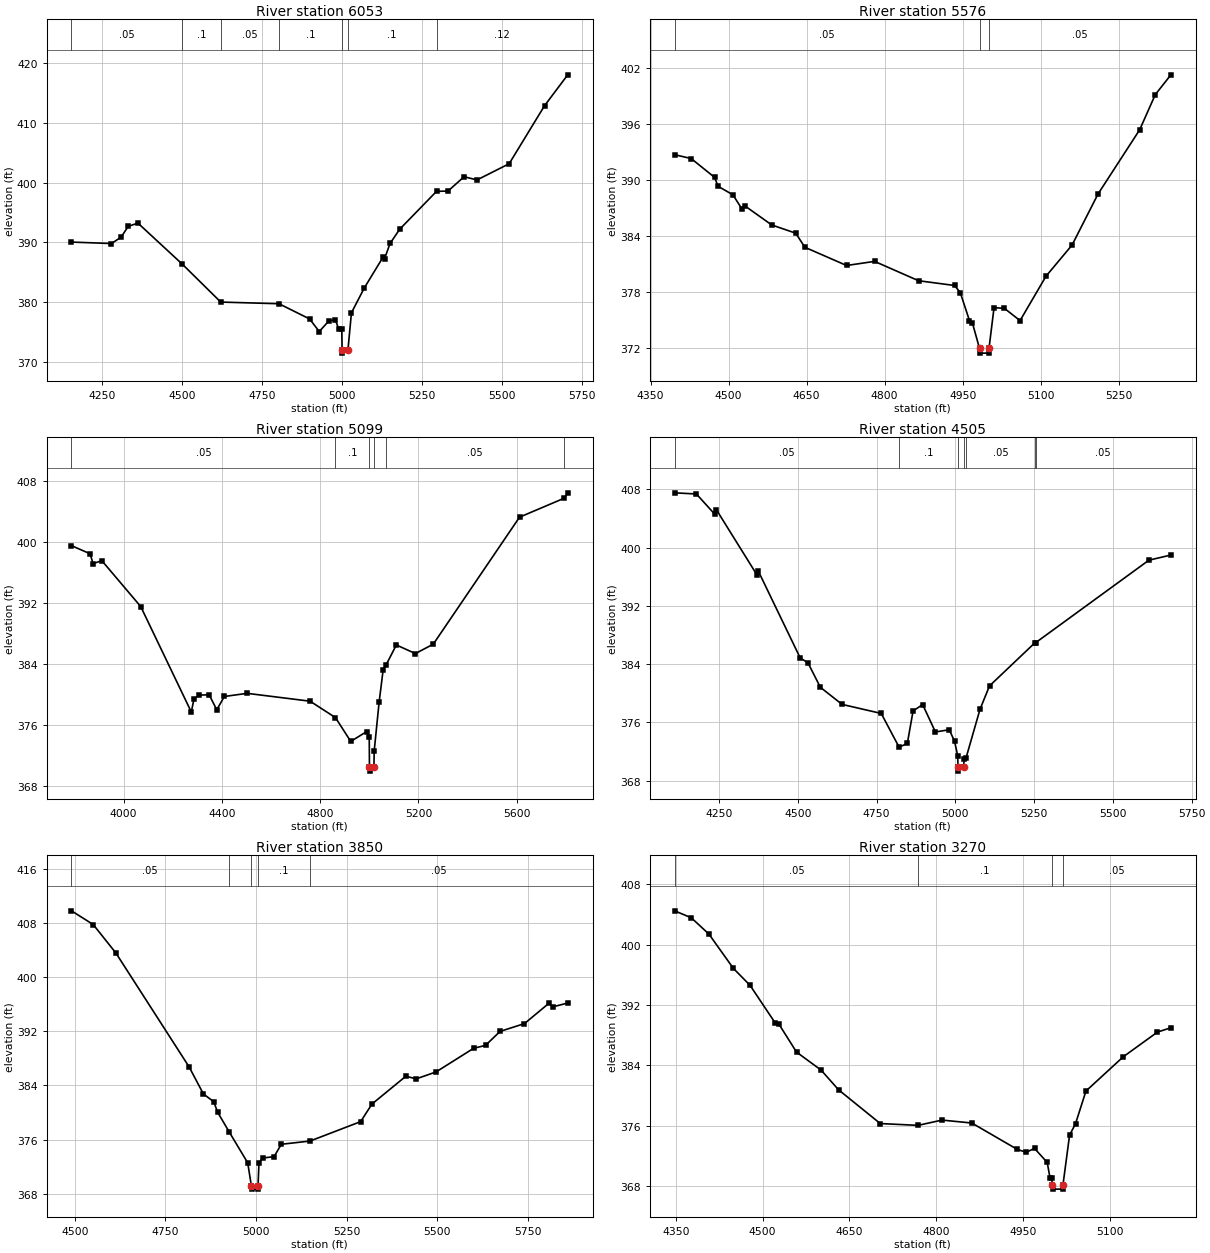
Type RM Length L Ch R = 1 ,6053    ,477,477,477
BEGIN DESCRIPTION:
A19657
END DESCRIPTION:
XS GIS Cut Line= 4
       2505012.5     13831253.39      2504731.23     13831399.23
      2504423.94     13831513.82      2503522.95     13831612.77
#Sta/Elev= 30
  4154.7  390.05  4279.6  389.81  4309.6  390.86  4332.1  392.68  4362.4  393.22
  4501.3  386.35  4621.3  380.03  4803.4  379.75    4899  377.21  4929.2  375.11
  4959.4  376.89  4979.5   377.1  4989.6  375.57  4999.6  375.46  5000.6     372
  5001.1   371.5  5018.8     372  5029.8  378.24    5070  382.39  5128.2   387.5
  5133.2  387.25  5150.5  389.82  5180.7   392.2  5295.9  398.53  5331.6  398.57
  5381.9  400.97  5422.2  400.43  5522.8  403.14  5633.4  412.83  5705.9  417.99
#Mann= 7 ,-1 , 0
  4154.7     .05       0  4501.3      .1       0  4621.3     .05       0
  4803.4      .1       0  5000.6     .05       0  5018.8      .1       0
  5295.9     .12       0
Bank Sta=5000.6,5018.8
XS Rating Curve= 0 ,0
Exp/Cntr=0.3,0.1

Type RM Length L Ch R = 1 ,5576    ,477,477,477
BEGIN DESCRIPTION:
Little Cooperas Creek 5.0
END DESCRIPTION:
XS GIS Cut Line= 3
      2504824.97     13831324.99        2504275.       13831075.
      2503925.02       13831075.
#Sta/Elev= 30
  4396.3  392.68  4428.1  392.27  4473.2  390.25  4479.8   389.3  4508.3  388.39
  4525.9  386.86  4531.4   387.2    4583  385.16  4629.1  384.28  4646.7  382.77
  4726.9  380.82  4780.7  381.26  4865.3  379.19  4934.5  378.68  4945.5  377.92
  4963.1  374.93  4968.6  374.71  4982.5  371.94    4983  371.44  5000.2  371.44
  5000.7  371.94  5010.4  376.31  5030.4  376.23  5060.4  374.92  5110.4  379.68
  5160.4  383.01  5210.4  388.48  5290.4  395.35  5320.4  399.11  5350.4  401.23
#Mann= 3 ,-1 , 0
  4396.3     .05       0  4982.5     .05       0  5000.7     .05       0
Bank Sta=4982.5,5000.7
XS Rating Curve= 0 ,0
Exp/Cntr=0.3,0.1

Type RM Length L Ch R = 1 ,5099    ,594,594,594
BEGIN DESCRIPTION:
A19656
END DESCRIPTION:
XS GIS Cut Line= 3
       2505408.3     13830399.24       2504522.9     13830623.19
      2503419.32     13830706.48
#Sta/Elev= 30
  3787.9  399.52  3863.5  398.46  3875.8  397.17  3911.6  397.55  4069.8  391.54
  4275.7  377.72  4286.4  379.43  4307.1  379.94  4348.3  379.98  4379.3  378.02
  4410.2  379.76    4503  380.17  4759.2  379.14  4862.5  376.99  4924.6  373.87
  4989.9  375.17  4999.9  374.43  5000.8  370.48  5001.3  369.98  5019.1  370.48
    5020  372.59    5040  378.98  5056.3  383.19  5067.7  383.84  5110.2  386.51
  5187.9  385.38  5260.7  386.62  5611.7  403.25  5793.1  405.73  5807.9  406.44
#Mann= 6 ,-1 , 0
  3787.9     .05       0  4862.5      .1       0  5000.8     .05       0
  5019.1      .1       0  5067.7     .05       0  5793.1     .12       0
Bank Sta=5000.8,5019.1
XS Rating Curve= 0 ,0
Exp/Cntr=0.3,0.1

Type RM Length L Ch R = 1 ,4505    ,655,655,655
BEGIN DESCRIPTION:
A19655
END DESCRIPTION:
XS GIS Cut Line= 2
      2505283.29     13830279.44      2503726.02     13830045.07
#Sta/Elev= 30
  4109.3  407.51  4178.4  407.35  4236.9  404.56    4242  405.18  4369.9  396.29
  4374.9  396.76  4507.8  384.84  4532.3  384.18  4571.8  380.81  4640.8  378.46
  4764.9  377.22  4821.6  372.59  4847.7   373.1    4866  377.56  4896.4  378.44
  4936.8  374.68  4980.7  374.98  4997.5  373.42  5007.6  371.41  5008.6   369.8
  5009.1   369.3  5026.9   369.8  5027.8  371.03  5033.7  371.06  5078.4  377.79
  5108.5     381  5252.1   386.9  5254.8  386.93  5614.3  398.26  5684.1  398.97
#Mann= 7 ,-1 , 0
  4109.3     .05       0  4821.6      .1       0  5008.6     .05       0
  5026.9      .1       0  5033.7     .05       0  5252.1     .07       0
  5254.8     .05       0
Bank Sta=5008.6,5026.9
XS Rating Curve= 0 ,0
Exp/Cntr=0.3,0.1

Type RM Length L Ch R = 1 ,3850    ,580,580,580
BEGIN DESCRIPTION:
A19654
END DESCRIPTION:
XS GIS Cut Line= 2
      2505272.88     13829857.56      2503955.18     13829487.77
#Sta/Elev= 30
  4491.1  409.82  4551.1  407.79  4613.5  403.59  4815.6  386.74  4854.9  382.75
  4883.6  381.59  4894.2  380.04  4925.8  377.16  4977.1  372.57  4987.2  369.18
  4987.7  368.68  5005.1  368.68  5005.6  369.18  5008.2  372.57  5018.6  373.28
  5049.8  373.48  5069.8  375.31  5149.1  375.79  5288.6  378.66  5319.8  381.26
  5413.3  385.37  5441.8  384.98  5496.4     386  5600.2   389.5    5633  389.93
  5672.9  391.99  5740.4  393.15    5808  396.16    5819  395.63  5859.7  396.19
#Mann= 5 ,-1 , 0
  4491.1     .05       0  4925.8      .1       0  4987.2     .05       0
  5005.6      .1       0  5149.1     .05       0
Bank Sta=4987.2,5005.6
XS Rating Curve= 0 ,0
Exp/Cntr=0.3,0.1

Type RM Length L Ch R = 1 ,3270    ,472,472,472
BEGIN DESCRIPTION:
Little Cooperas Creek 4.0
END DESCRIPTION:
XS GIS Cut Line= 3
      2505225.02     13829625.01        2504675.       13829275.
        2504475.       13829225.
#Sta/Elev= 30
    4348  404.47  4376.8  403.55  4407.3  401.39  4449.6  396.85  4478.4  394.61
  4522.4  389.57  4528.4  389.46  4558.8  385.77  4601.2  383.39  4631.6  380.77
  4703.6  376.31  4768.9  376.07  4810.3  376.77  4861.9  376.38  4940.7  372.88
  4955.9  372.51  4970.3  373.02  4992.3  371.16    4997  369.15  4999.9  369.15
    5001  368.13  5001.5  367.63  5018.9  367.63  5019.4  368.13  5030.9  374.77
  5041.2  376.29  5059.2  380.61  5123.6  385.14  5182.9  388.42  5206.1  388.99
#Mann= 4 ,-1 , 0
    4348     .05       0  4768.9      .1       0    5001     .05       0
  5019.4     .05       0
Bank Sta=5001,5019.4
XS Rating Curve= 0 ,0
Exp/Cntr=0.3,0.1

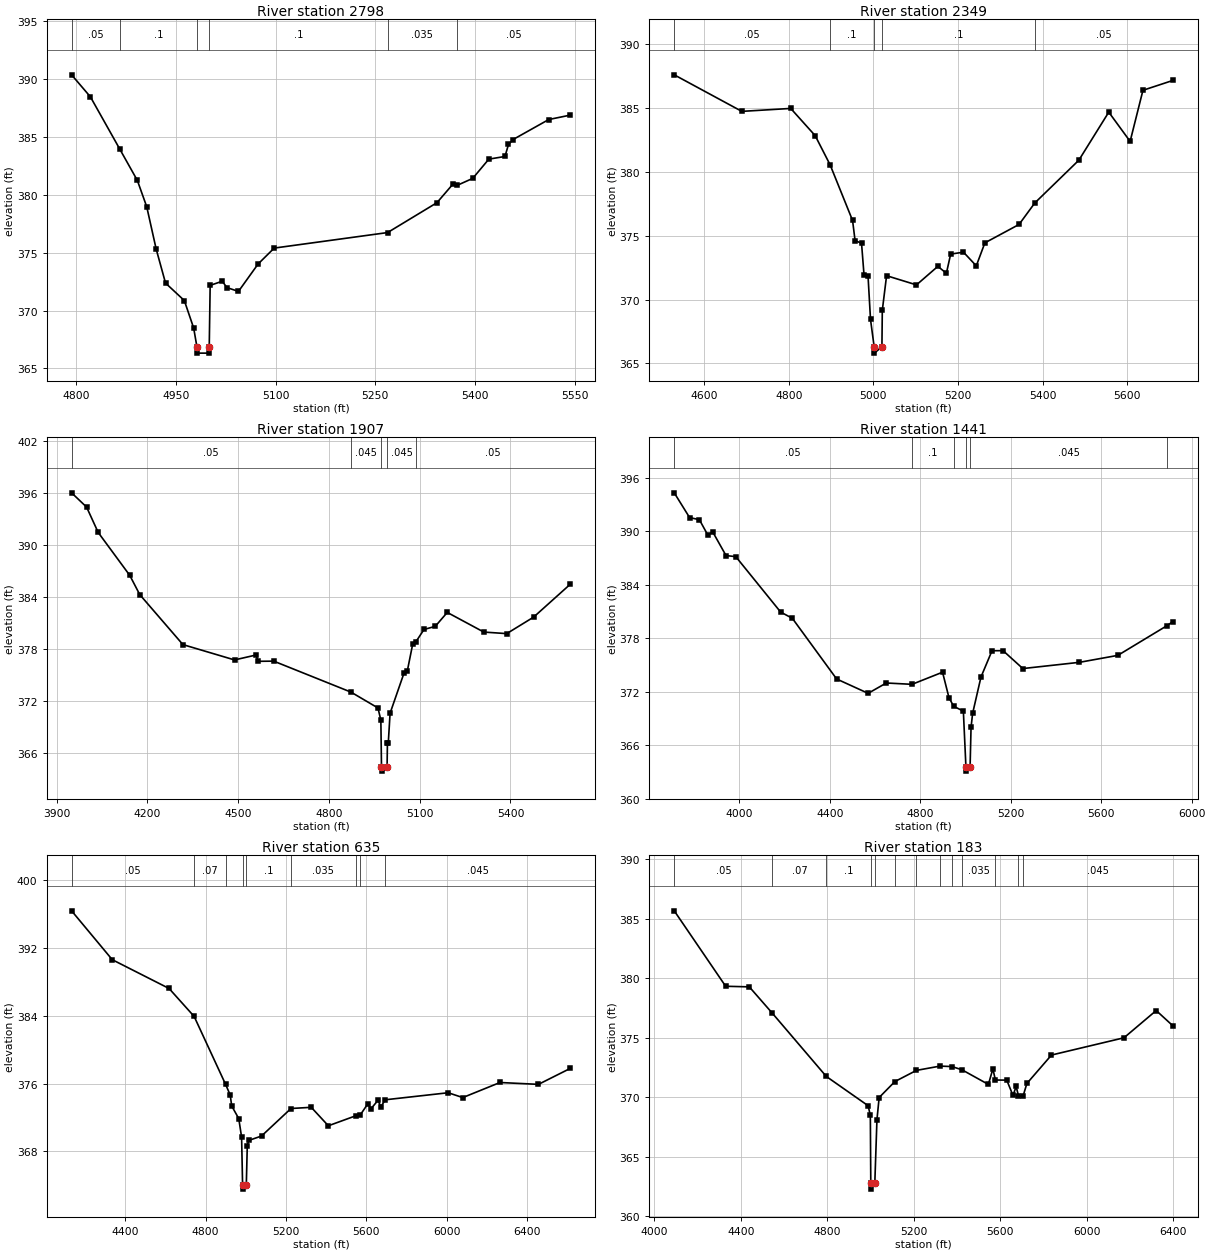
Type RM Length L Ch R = 1 ,2798    ,449,449,449
BEGIN DESCRIPTION:
Little Cooperas Creek 3.0
END DESCRIPTION:
XS GIS Cut Line= 3
      2505174.99     13829174.99        2505025.       13829025.
      2504525.04     13828825.02
#Sta/Elev= 30
  4792.7  390.35    4821  388.45  4865.4  383.92  4891.7  381.23  4905.8  378.96
    4920  375.31  4934.1  372.37  4962.4  370.86  4976.5  368.48  4981.5  366.82
    4982  366.32  4999.4  366.32  4999.9  366.82  5001.3  372.17  5019.6  372.53
  5026.4  371.98  5043.9  371.65  5073.5  374.02  5097.7  375.39  5268.4  376.73
  5342.7  379.31    5367  380.93  5373.3  380.81  5396.6  381.41  5420.8  383.07
  5445.1   383.3  5450.4  384.34  5457.2  384.76    5511  386.49  5543.3  386.87
#Mann= 6 ,-1 , 0
  4792.7     .05       0  4865.4      .1       0  4981.5     .05       0
  4999.9      .1       0  5268.4    .035       0  5373.3     .05       0
Bank Sta=4981.5,4999.9
XS Rating Curve= 0 ,0
Exp/Cntr=0.3,0.1

Type RM Length L Ch R = 1 ,2349    ,442,442,442
BEGIN DESCRIPTION:
Little Cooperas Creek 2.0
END DESCRIPTION:
XS GIS Cut Line= 3
      2505475.01     13829075.01        2505225.       13828675.
      2504525.02       13828775.
#Sta/Elev= 30
  4529.2  387.59    4689  384.73  4804.6  384.96  4862.4  382.83  4897.8  380.54
  4950.8  376.19  4956.7  374.62    4972  374.41  4977.9  371.92  4987.4  371.82
  4993.2  368.45  5001.8  366.31  5002.3  365.81  5020.2  366.31  5021.1  369.16
  5031.2  371.87  5101.9  371.15  5152.4   372.6  5172.6  372.06  5182.7  373.56
    5213  373.71  5243.3  372.64  5263.6  374.44  5344.4  375.88  5381.6  377.56
  5485.8  380.91  5556.5  384.67    5607  382.38  5637.3  386.38    5708  387.15
#Mann= 5 ,-1 , 0
  4529.2     .05       0  4897.8      .1       0  5001.8     .05       0
  5020.2      .1       0  5381.6     .05       0
Bank Sta=5001.8,5020.2
XS Rating Curve= 0 ,0
Exp/Cntr=0.3,0.1

Type RM Length L Ch R = 1 ,1907    ,466,466,466
BEGIN DESCRIPTION:
Little Cooperas Creek 1.0
END DESCRIPTION:
XS GIS Cut Line= 3
      2506075.01       13828625.        2505075.       13828325.
        2504525.       13828575.
#Sta/Elev= 30
  3949.2  396.06  3998.8  394.41  4037.1  391.48  4141.5  386.52  4174.5   384.3
  4317.2  378.52  4487.8  376.75  4559.1  377.32  4565.2  376.59  4617.4  376.61
  4872.8  373.03  4961.9   371.2  4971.5  369.79  4973.6   364.4  4974.1   363.9
  4992.1   364.4  4993.2  367.13    4996  367.13    5002  370.59  5048.2  375.25
  5059.2  375.52  5076.7  378.57  5087.4  378.85  5114.1  380.27  5151.4  380.63
    5191  382.24  5311.8  379.97  5387.6  379.79  5476.6   381.7  5597.4  385.49
#Mann= 5 ,-1 , 0
  3949.2     .05       0  4872.8    .045       0  4973.6    .045       0
  4992.1    .045       0  5087.4     .05       0
Bank Sta=4973.6,4992.1
XS Rating Curve= 0 ,0
Exp/Cntr=0.3,0.1

Type RM Length L Ch R = 1 ,1441    ,806,806,806
BEGIN DESCRIPTION:
A19653
END DESCRIPTION:
XS GIS Cut Line= 4
      2506317.97     13828374.38      2505397.94     13827846.31
      2504902.51      13827955.2      2504457.31     13828411.26
#Sta/Elev= 30
  3711.4  394.33  3779.4  391.55  3822.5  391.32  3859.9  389.59  3881.5  389.95
  3940.4  387.29  3983.6  387.17    4182  380.95  4233.7  380.25  4429.7  373.44
  4568.9  371.83  4649.4  372.99  4763.1  372.84  4898.1   374.2  4926.4  371.36
  4947.1  370.38  4990.2  369.83  5001.5   363.6    5002   363.1    5020   363.6
  5024.2  368.02  5031.2  369.58    5068  373.65  5116.9  376.61  5165.7  376.62
  5253.3  374.61  5503.8  375.31  5673.5  376.09    5892  379.44  5916.8  379.88
#Mann= 6 ,-1 , 0
  3711.4     .05       0  4763.1      .1       0  4947.1    .045       0
  5001.5    .045       0    5020    .045       0    5892     .05       0
Bank Sta=5001.5,5020
XS Rating Curve= 0 ,0
Exp/Cntr=0.3,0.1

Type RM Length L Ch R = 1 ,635     ,452,452,452
BEGIN DESCRIPTION:
A19652
END DESCRIPTION:
XS GIS Cut Line= 3
      2506367.03     13828309.09      2505425.16     13827421.66
      2504479.15     13828139.32
#Sta/Elev= 30
  4133.1  396.41  4335.5  390.64  4618.3  387.24    4743  383.94  4899.1  375.94
  4922.6  374.66  4929.9  373.37    4965  371.88  4979.2  369.69  4984.1  364.05
  4984.6  363.55  5002.6  364.05  5007.5   368.7  5014.8   369.3  5078.3  369.82
    5225  373.07  5325.9  373.21  5410.9  371.03  5546.3   372.2    5568  372.25
  5607.9  373.64  5622.5  373.02  5657.8  374.03  5672.4  373.28  5694.3   374.1
  6007.3  374.93    6080  374.36  6265.2  376.14  6456.6  375.92  6614.6   377.8
#Mann= 9 ,-1 , 0
  4133.1     .05       0    4743     .07       0  4899.1      .1       0
  4984.1     .05       0  5002.6      .1       0    5225    .035       0
  5546.3      .1       0    5568     .05       0  5694.3    .045       0
Bank Sta=4984.1,5002.6
XS Rating Curve= 0 ,0
Exp/Cntr=0.3,0.1

Type RM Length L Ch R = 1 ,183     ,0,0,0
BEGIN DESCRIPTION:
A19651
END DESCRIPTION:
XS GIS Cut Line= 4
      2506416.03      13827889.9       2506094.8     13827345.44
      2505550.37     13827236.56      2504669.23     13827927.33
#Sta/Elev= 30
  4092.4  385.66  4330.3  379.32  4439.7  379.27  4546.5  377.05    4796  371.74
  4989.5  369.28  4999.7  368.46  5001.8  362.77  5002.3  362.27  5020.4  362.77
  5030.3  368.11  5040.5  369.97  5113.2  371.31  5213.1  372.25  5322.3  372.61
  5377.3  372.57  5423.7   372.3  5545.9  371.07  5566.7  372.38  5578.3  371.44
  5630.9  371.43  5659.8  370.14  5674.3   370.9  5685.2  370.11  5706.3  370.08
    5724  371.15  5837.9  373.54  6173.3  374.99  6322.4  377.28  6399.4     376
#Mann= 13 ,-1 , 0
  4092.4     .05       0  4546.5     .07       0    4796      .1       0
  5001.8     .05       0  5020.4      .1       0  5113.2    .035       0
  5213.1     .05       0  5322.3    .035       0  5377.3      .1       0
  5423.7    .035       0  5578.3    .045       0  5685.2     .05       0
  5706.3    .045       0
Bank Sta=5001.8,5020.4
XS Rating Curve= 0 ,0
Exp/Cntr=0.3,0.1

Chan Stop Cuts=-1
Use User Specified Reach Order=0
Composite Channel Slope=5