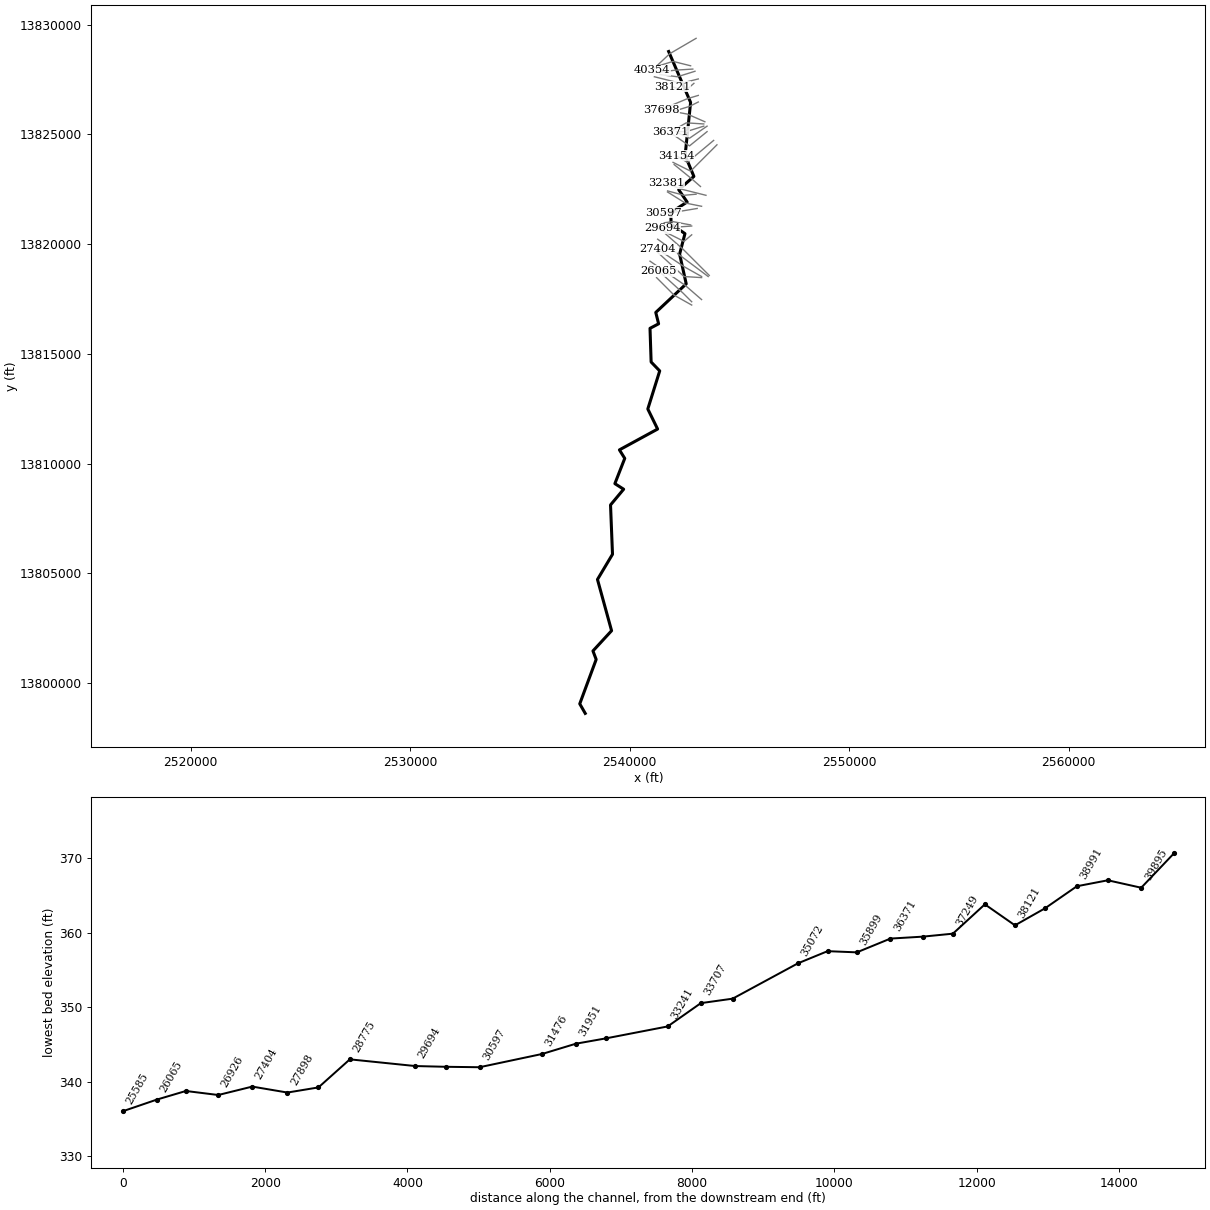
--- Little Fivemile Creek.prj (project) ---

Proj Title=Little Fivemile Creek Base Level Engineering
Current Plan=p01
Default Exp/Contr=0.3,0.1
English Units
Geom File=g01
Flow File=f01
Plan File=p01
Y Axis Title=Elevation
X Axis Title(PF)=Main Channel Distance
X Axis Title(XS)=Station
BEGIN DESCRIPTION:
Little Fivemile Creek
END DESCRIPTION:
DSS Export Rating Curves= 0
DSS Export Rating Curve Sorted= 0
DSS Export Volume Flow Curves= 0
DXF OffsetX= 0
DXF OffsetY= 0
DXF ScaleX= 1
DXF ScaleY= 10

--- Little Fivemile Creek.p01 (plan) ---

Plan Title=Multiple Run
Short Identifier=Multiple
Geom File=g01
Flow File=f01
Subcritical Flow
K Sum by GR= 0
Std Step Tol= 0.01
Critical Tol= 0.01
Num of Std Step Trials= 20
Max Error Tol= 0.3
Flow Tol Ratio= 0.001
Split Flow NTrial= 30
Split Flow Tol= 0.02
Split Flow Ratio= 0.02
Log Output Level= 0
Friction Slope Method= 1
Unsteady Friction Slope Method= 2
Unsteady Bridges Friction Slope Method= 1
Parabolic Critical Depth
Global Vel Dist=  1 , 1 , 1
Global Log Level= 0
CheckData=True
Encroach Param= -1, 0, 0, 0
BEGIN DESCRIPTION:
Multiple Run
END DESCRIPTION:

--- Little Fivemile Creek.f01 (steady flow) ---

Flow Title=Multiple
Number of Profiles=7
Profile Names=10-year,25-year,50-year,1pct_min,100-year,1pct_plu,500-year
River Rch & RM= Little Fivemile ,Reach-1,40354
     849    1375    1853    1209    2413    4814    4046
River Rch & RM= Little Fivemile ,Reach-1,39426
    1150    1882    2552    1674    3339    6663    5657
River Rch & RM= Little Fivemile ,Reach-1,35072
    1487    2464    3369    2225    4439    8856    7628
River Rch & RM= Little Fivemile ,Reach-1,32381
    1572    2604    3559    2348    4686    9349    8042
River Rch & RM= Little Fivemile ,Reach-1,28334
    1798    2989    4097    2708    5404   10783    9313
River Rch & RM= Little Fivemile ,Reach-1,24650
    1762    2917    3985    2626    5239   10453    8967
River Rch & RM= Little Fivemile ,Reach-1,21864
    2231    3719    5106    3377    6737   13443   11620
River Rch & RM= Little Fivemile ,Reach-1,17428
    2294    3812    5220    3443    6870   13707   11785
River Rch & RM= Little Fivemile ,Reach-1,11635
    2299    3812    5212    3432    6848   13663   11706
River Rch & RM= Little Fivemile ,Reach-1,7941
    2635    4381    6002    3957    7894   15751   13528
Boundary for River Rch & Prof#=Little Fivemile ,Reach-1,1
Up Type=0
Dn Type=3
Dn Slope=0.0012
Boundary for River Rch & Prof#=Little Fivemile ,Reach-1,2
Up Type=0
Dn Type=3
Dn Slope=0.0012
Boundary for River Rch & Prof#=Little Fivemile ,Reach-1,3
Up Type=0
Dn Type=3
Dn Slope=0.0012
Boundary for River Rch & Prof#=Little Fivemile ,Reach-1,4
Up Type=0
Dn Type=3
Dn Slope=0.0012
Boundary for River Rch & Prof#=Little Fivemile ,Reach-1,5
Up Type=0
Dn Type=3
Dn Slope=0.0012
Boundary for River Rch & Prof#=Little Fivemile ,Reach-1,6
Up Type=0
Dn Type=3
Dn Slope=0.0012
Boundary for River Rch & Prof#=Little Fivemile ,Reach-1,7
Up Type=0
Dn Type=3
Dn Slope=0.0012

--- Little Fivemile Creek.g01 (geometry) ---

Geom Title=Existing Conditions
Program Version=4.10

River Reach=Little Fivemile ,Reach-1
Reach XY= 30
        2541775.       13828775.      2542775.11     13826455.11
      2542524.64     13824045.21      2542924.12     13823085.34
      2542232.79     13822478.03      2542617.38      13821918.5
      2541874.53     13821445.17      2541885.96       13820915.
      2542517.41     13820478.35       2542274.6     13819545.13
      2542574.61     13818190.16      2541188.19     13816888.73
      2541317.33      13816371.3      2540925.92     13816164.52
      2540976.63     13814631.04      2541367.72     13814224.89
      2540824.95     13812490.34      2541271.93     13811576.34
      2539532.58     13810628.34      2539774.69     13810240.04
      2539325.08     13809090.39      2539724.32     13808835.75
      2539127.06     13808119.15      2539216.92      13805871.7
      2538532.56       13804725.      2539174.81     13802390.09
      2538326.61     13801469.36      2538473.12     13801080.69
      2537725.38     13799059.72        2537975.       13798625.

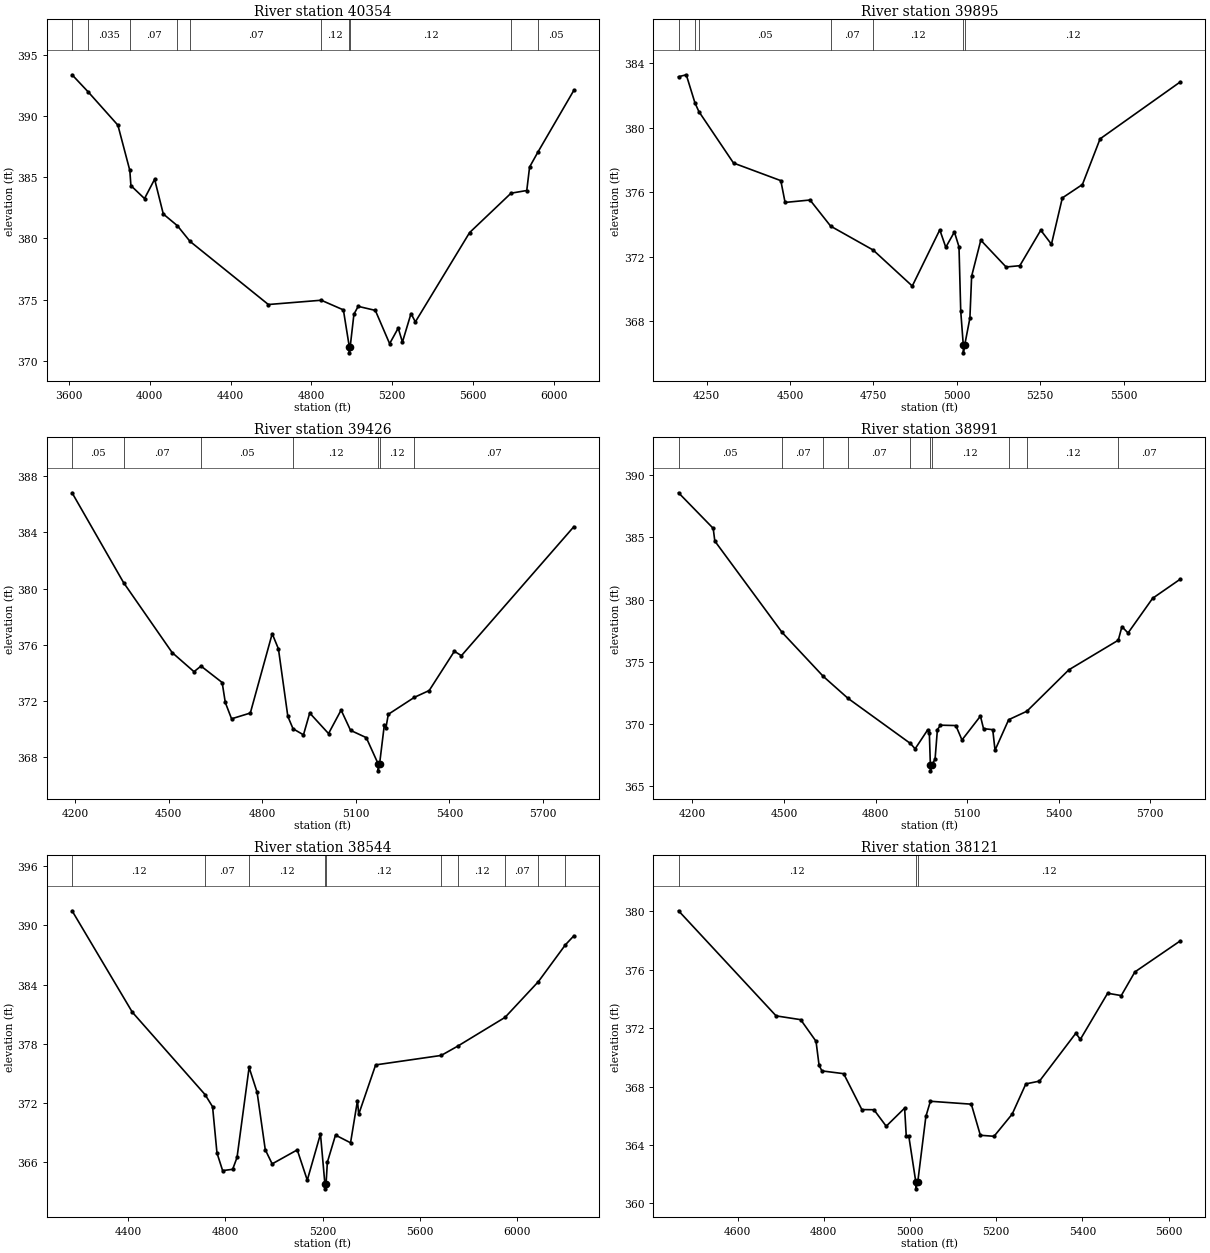
Type RM Length L Ch R = 1 ,40354   ,459,459,459
BEGIN DESCRIPTION:
Little Fivemile Creek 68.0
END DESCRIPTION:
XS GIS Cut Line= 3
      2543024.97     13829374.99        2541825.       13828675.
        2541025.       13827925.
#Sta/Elev= 30
    3615  393.38    3696  391.96    3842  389.26  3901.1  385.56  3906.5  384.32
  3973.9  383.26  4023.9  384.84  4066.9     382  4136.8  381.04  4199.4  379.76
  4587.4   374.6  4849.4  374.95  4959.1  374.16  4988.3  371.15  4988.7  370.65
  4992.8  371.15  5011.3  373.81  5032.3  374.45  5117.3  374.12  5188.1   371.4
  5230.6  372.67  5251.6  371.53  5294.1  373.86  5315.6  373.18  5584.3  380.48
  5789.6   383.7  5867.5  383.92  5881.5  385.84  5922.7  387.06  6100.8  392.11
#Mann= 10 ,-1 , 0
    3615     .07       0    3696    .035       0  3901.1     .07       0
  4136.8     .05       0  4199.4     .07       0  4849.4     .12       0
  4988.3     .05       0  4992.8     .12       0  5789.6    .035       0
  5922.7     .05       0
Bank Sta=4988.3,4992.8
XS Rating Curve= 0 ,0
Exp/Cntr=0.3,0.1

Type RM Length L Ch R = 1 ,39895   ,469,469,469
BEGIN DESCRIPTION:
Little Fivemile Creek 67.0
END DESCRIPTION:
XS GIS Cut Line= 3
        2542775.       13828125.        2541975.       13828325.
      2541324.99       13828125.
#Sta/Elev= 30
  4165.5  383.15  4188.7  383.27  4214.7  381.53  4226.5  380.99  4330.4   377.8
  4472.2  376.71    4485  375.36  4559.8  375.51  4621.7  373.89  4749.1  372.41
  4866.4  370.18  4948.9  373.66  4966.9  372.58  4992.7  373.53  5006.5  372.61
  5011.7  368.63  5019.3  366.54  5019.6  366.04  5023.8  366.54  5039.2  368.19
  5044.4  370.79  5071.9  373.02  5147.7  371.36  5188.9  371.44  5251.7  373.64
  5283.7  372.77  5316.4  375.64  5376.6  376.47  5429.6   379.3  5670.2  382.83
#Mann= 7 ,-1 , 0
  4165.5     .05       0  4214.7     .07       0  4226.5     .05       0
  4621.7     .07       0  4749.1     .12       0  5019.3     .05       0
  5023.8     .12       0
Bank Sta=5019.3,5023.8
XS Rating Curve= 0 ,0
Exp/Cntr=0.3,0.1

Type RM Length L Ch R = 1 ,39426   ,435,435,435
BEGIN DESCRIPTION:
Little Fivemile Creek 66.0
END DESCRIPTION:
XS GIS Cut Line= 3
      2542874.96       13827975.        2542075.       13827925.
      2541275.05     13827825.01
#Sta/Elev= 30
    4191  386.81  4355.8  380.43  4511.6  375.45  4581.7  374.09  4604.1  374.49
  4671.9  373.32  4681.9   371.9    4702  370.74  4762.1  371.15  4832.2  376.79
  4852.2  375.71  4882.3  370.91    4899  370.03  4932.4   369.6  4952.4  371.15
  5012.7  369.69    5053  371.36  5083.2  369.92  5133.6   369.4  5171.6  367.54
  5171.9  367.04  5176.3  367.54  5191.6  370.33  5196.6   370.1  5204.2  371.06
    5288  372.27  5335.2  372.75  5415.8  375.54  5438.5  375.23  5798.7   384.4
#Mann= 7 ,-1 , 0
    4191     .05       0  4355.8     .07       0  4604.1     .05       0
    4899     .12       0  5171.6     .05       0  5176.3     .12       0
    5288     .07       0
Bank Sta=5171.6,5176.3
XS Rating Curve= 0 ,0
Exp/Cntr=0.3,0.1

Type RM Length L Ch R = 1 ,38991   ,447,447,447
BEGIN DESCRIPTION:
Little Fivemile Creek 65.0
END DESCRIPTION:
XS GIS Cut Line= 3
      2542974.96     13827874.99        2542175.       13827625.
      2541375.04       13827725.
#Sta/Elev= 30
  4154.4  388.59    4268  385.73  4273.3  384.71  4493.3  377.38  4628.8  373.83
  4709.6  372.07  4914.2  368.44  4929.7  368.01    4971  369.54  4976.3  369.26
  4979.6  366.74    4980  366.24  4984.4  366.74    4995  367.17  5002.6  369.54
  5012.7  369.91  5063.1  369.88  5083.2  368.72  5143.7  370.64  5153.8  369.63
    5184  369.55  5191.5   367.9  5236.2  370.35  5295.8  371.03  5433.4  374.36
  5595.4  376.74  5607.3  377.83  5627.4  377.32    5708  380.11  5798.7  381.65
#Mann= 10 ,-1 , 0
  4154.4     .05       0  4493.3     .07       0  4628.8     .05       0
  4709.6     .07       0  4914.2     .12       0  4979.6     .05       0
  4984.4     .12       0  5236.2     .07       0  5295.8     .12       0
  5595.4     .07       0
Bank Sta=4979.6,4984.4
XS Rating Curve= 0 ,0
Exp/Cntr=0.3,0.1

Type RM Length L Ch R = 1 ,38544   ,423,423,423
BEGIN DESCRIPTION:
Little Fivemile Creek 64.0
END DESCRIPTION:
XS GIS Cut Line= 3
      2543124.99       13827525.        2542325.       13827325.
      2541125.04     13827624.99
#Sta/Elev= 30
  4170.1  391.48  4417.5   381.2  4716.4  372.84  4747.3  371.61  4765.4  366.92
  4788.6  365.13  4829.8  365.26  4847.8  366.46  4897.4  375.59  4930.3  373.07
  4963.8  367.25  4992.1  365.81  5095.2  367.23  5136.4  364.16  5190.6  368.84
  5208.8  363.78  5209.1  363.28  5213.6  363.78  5218.9  365.98  5252.4  368.73
  5314.2  367.95  5342.6  372.23  5347.7  370.84  5417.3  375.85  5686.7  376.81
    5755  377.76  5948.9  380.67    6086   384.3  6196.9  388.03  6231.6  388.94
#Mann= 10 ,-1 , 0
  4170.1     .12       0  4716.4     .07       0  4897.4     .12       0
  5208.8     .05       0  5213.6     .12       0  5686.7     .07       0
    5755     .12       0  5948.9     .07       0    6086    .035       0
  6196.9     .05       0
Bank Sta=5208.8,5213.6
XS Rating Curve= 0 ,0
Exp/Cntr=0.3,0.1

Type RM Length L Ch R = 1 ,38121   ,423,423,423
BEGIN DESCRIPTION:
Little Fivemile Creek 63.0
END DESCRIPTION:
XS GIS Cut Line= 3
      2542924.98     13827324.99        2542525.       13826975.
      2541925.04     13827174.99
#Sta/Elev= 30
  4463.1  380.04  4689.4  372.84  4746.4  372.58    4782   371.1  4789.1  369.45
  4795.7  369.07  4846.1  368.88  4888.3  366.42  4916.3  366.41  4944.8  365.28
  4987.5  366.52  4991.3   364.6  4997.2   364.6  5013.3  361.49  5013.6  360.99
  5018.1  361.49  5036.8  365.95  5047.3  366.99  5142.2  366.79  5163.2  364.66
  5194.9  364.59    5237  366.11  5268.7  368.18  5300.3  368.37  5384.6  371.65
  5395.1  371.23  5458.4  374.39    5490  374.23  5521.6  375.85    5627  377.98
#Mann= 3 ,-1 , 0
  4463.1     .12       0  5013.3     .05       0  5018.1     .12       0
Bank Sta=5013.3,5018.1
XS Rating Curve= 0 ,0
Exp/Cntr=0.3,0.1

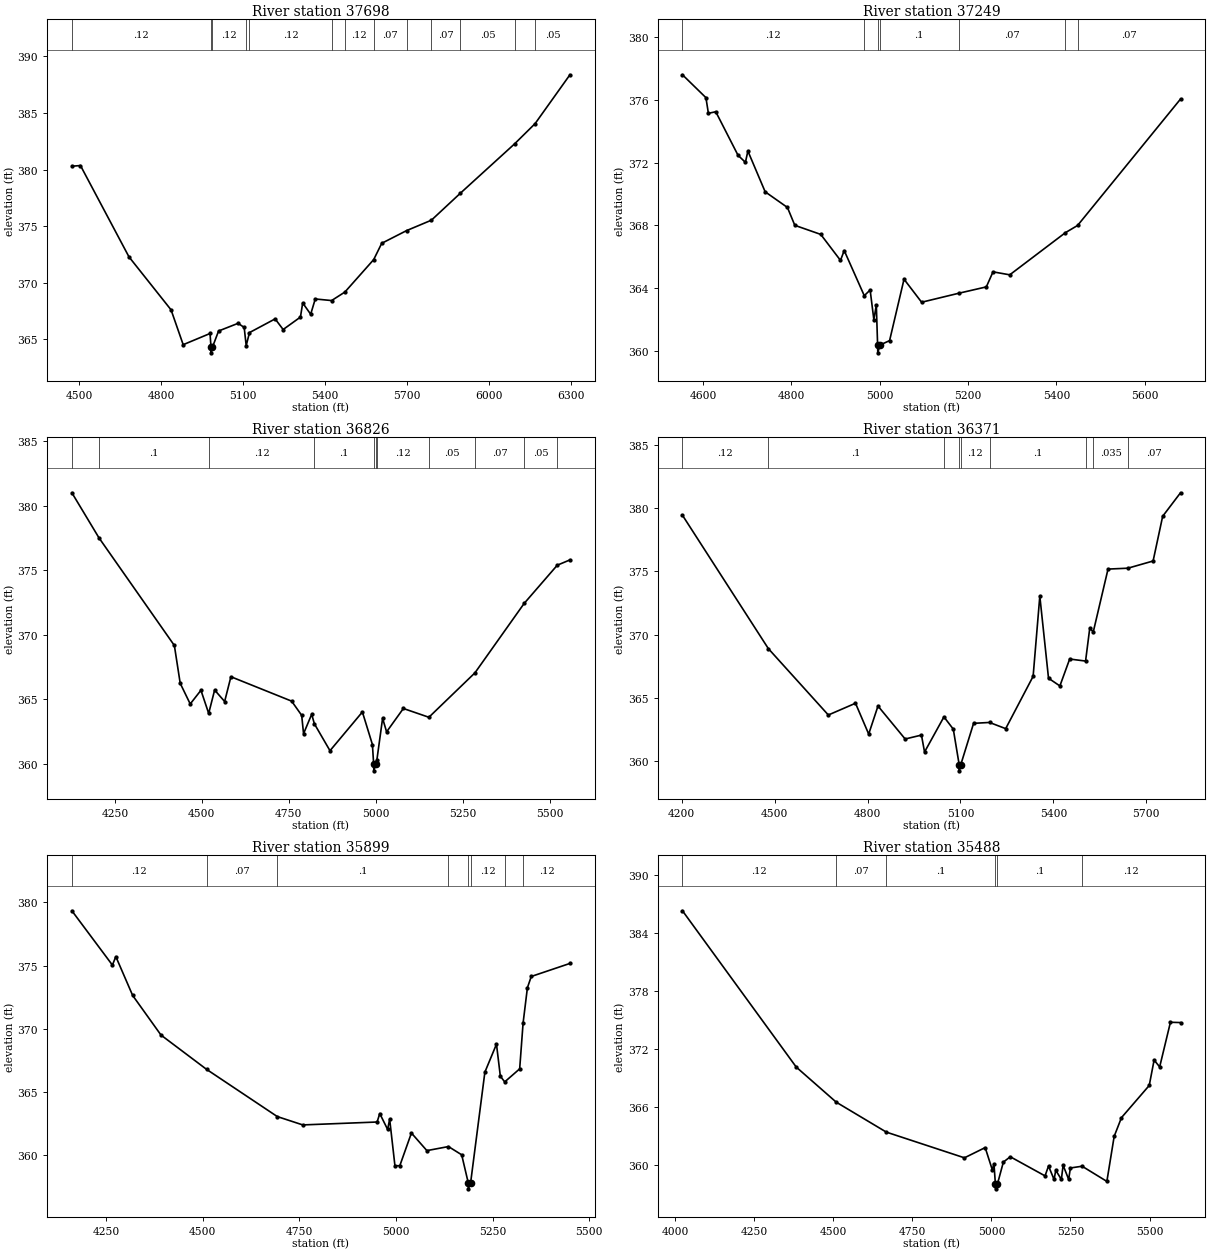
Type RM Length L Ch R = 1 ,37698   ,449,449,449
BEGIN DESCRIPTION:
Little Fivemile Creek 62.0
END DESCRIPTION:
XS GIS Cut Line= 3
      2543125.04     13826775.01        2542625.       13826625.
      2541424.97     13826124.99
#Sta/Elev= 30
  4473.6   380.3    4505  380.36  4682.5  372.29  4836.4  367.61  4880.8  364.53
  4979.1  365.52  4982.5  364.31    4983  363.81  4987.9  364.31  5010.3  365.74
  5081.8  366.42    5104  366.05  5111.3  364.45  5123.4   365.6  5217.2  366.81
  5246.5  365.87  5309.8  366.97    5318  368.22  5347.2  367.22    5364  368.57
  5423.8  368.43  5472.3  369.18  5577.8  372.05  5607.2  373.49    5698  374.61
  5788.8  375.53  5894.2   377.9  6093.4  382.28  6168.1  384.06  6295.7  388.38
#Mann= 13 ,-1 , 0
  4473.6     .12       0  4982.5     .05       0  4987.9     .12       0
  5111.3     .07       0  5123.4     .12       0  5423.8     .07       0
  5472.3     .12       0  5577.8     .07       0    5698     .12       0
  5788.8     .07       0  5894.2     .05       0  6093.4     .07       0
  6168.1     .05       0
Bank Sta=4982.5,4987.9
XS Rating Curve= 0 ,0
Exp/Cntr=0.3,0.1

Type RM Length L Ch R = 1 ,37249   ,423,423,423
BEGIN DESCRIPTION:
Little Fivemile Creek 61.0
END DESCRIPTION:
XS GIS Cut Line= 3
      2543124.97     13826474.99        2542725.       13826275.
      2542074.96     13826074.99
#Sta/Elev= 30
  4553.6  377.62  4606.7  376.16  4612.3  375.16    4629  375.26  4679.4  372.48
  4696.1  372.03  4701.7  372.75  4740.8  370.15  4791.2  369.15  4807.9  368.01
  4866.6  367.43  4911.3  365.77  4919.7   366.4  4965.1  363.52  4978.4  363.88
  4986.8  361.99  4992.4  362.92  4995.3  360.37  4995.7  359.87  5000.7  360.37
  5022.4  360.65  5055.1  364.57  5094.9   363.1  5178.4  363.67  5241.4  364.08
  5256.5  365.04  5294.4  364.85  5420.3  367.54  5447.9     368  5680.9  376.07
#Mann= 7 ,-1 , 0
  4553.6     .12       0  4965.1      .1       0  4995.3     .05       0
  5000.7      .1       0  5178.4     .07       0  5420.3     .05       0
  5447.9     .07       0
Bank Sta=4995.3,5000.7
XS Rating Curve= 0 ,0
Exp/Cntr=0.3,0.1

Type RM Length L Ch R = 1 ,36826   ,455,455,455
BEGIN DESCRIPTION:
Little Fivemile Creek 60.0
END DESCRIPTION:
XS GIS Cut Line= 3
      2543424.99       13825575.        2542625.       13825925.
      2542075.02       13826025.
#Sta/Elev= 30
  4126.4  381.01  4204.3  377.52  4421.1  369.18  4437.9  366.25  4466.7  364.65
  4497.5  365.71  4519.8  363.92  4536.9  365.73  4565.7  364.84  4583.7  366.76
  4758.3  364.87  4787.2  363.77  4792.6  362.35    4816  363.85  4823.8  363.11
  4868.6  361.03  4961.8  364.03  4990.6  361.51  4994.2  359.97  4994.6  359.47
  4999.6  359.97  5003.6  360.34  5019.9  363.54  5031.4  362.49  5079.6   364.3
    5153  363.62  5285.4  367.06    5427  372.44  5522.2   375.4  5558.6  375.81
#Mann= 11 ,-1 , 0
  4126.4     .12       0  4204.3      .1       0  4519.8     .12       0
  4823.8      .1       0  4994.2     .05       0  4999.6      .1       0
  5003.6     .12       0    5153     .05       0  5285.4     .07       0
    5427     .05       0  5522.2     .07       0
Bank Sta=4994.2,4999.6
XS Rating Curve= 0 ,0
Exp/Cntr=0.3,0.1

Type RM Length L Ch R = 1 ,36371   ,472,472,472
BEGIN DESCRIPTION:
Little Fivemile Creek 59.0
END DESCRIPTION:
XS GIS Cut Line= 3
      2543375.01       13825475.        2542575.       13825525.
        2541875.       13825125.
#Sta/Elev= 30
  4202.5  379.44  4479.9  368.88  4673.4  363.63  4761.1  364.56  4803.7  362.12
  4833.7  364.34  4921.4  361.73    4974  362.04    4984   360.7  5046.6  363.48
  5076.8  362.51  5095.7  359.71  5096.1  359.21  5101.1  359.71  5142.3  362.97
  5193.7  363.04  5245.9  362.55  5334.5  366.69  5356.1  373.04  5384.2  366.54
  5420.9  365.93  5452.5  368.06  5503.8   367.9  5517.3   370.5  5528.7  370.21
  5576.3  375.18  5640.4  375.25  5721.8  375.82  5752.7  379.36  5810.3  381.22
#Mann= 9 ,-1 , 0
  4202.5     .12       0  4479.9      .1       0  5046.6     .12       0
  5095.7     .05       0  5101.1     .12       0  5193.7      .1       0
  5503.8     .07       0  5528.7    .035       0  5640.4     .07       0
Bank Sta=5095.7,5101.1
XS Rating Curve= 0 ,0
Exp/Cntr=0.3,0.1

Type RM Length L Ch R = 1 ,35899   ,411,411,411
BEGIN DESCRIPTION:
Little Fivemile Creek 58.0
END DESCRIPTION:
XS GIS Cut Line= 3
      2543375.02     13825375.01        2542575.       13825125.
      2542124.97       13825125.
#Sta/Elev= 30
  4161.7  379.33  4266.5  375.04  4275.4  375.71  4318.9  372.64  4392.2  369.51
  4510.1   366.8    4693  363.07  4758.9  362.41  4951.2  362.64    4958  363.31
  4978.4  362.05  4983.6  362.87  4997.3  359.18  5009.9  359.19  5039.9  361.77
  5079.9  360.38  5135.7   360.7  5169.9  360.05  5186.7  357.86  5187.2  357.36
  5193.1  357.86  5229.9  366.58  5259.9  368.79  5269.9  366.26  5281.2  365.81
  5319.9  366.84  5328.7  370.45  5339.9  373.25  5349.9  374.14  5449.9  375.17
#Mann= 8 ,-1 , 0
  4161.7     .12       0  4510.1     .07       0    4693      .1       0
  5135.7     .12       0  5186.7     .05       0  5193.1     .12       0
  5281.2      .1       0  5328.7     .12       0
Bank Sta=5186.7,5193.1
XS Rating Curve= 0 ,0
Exp/Cntr=0.3,0.1

Type RM Length L Ch R = 1 ,35488   ,416,416,416
BEGIN DESCRIPTION:
Little Fivemile Creek 57.0
END DESCRIPTION:
XS GIS Cut Line= 3
      2543525.01     13825375.01        2542725.       13824825.
      2542174.99       13825075.
#Sta/Elev= 30
    4023   386.3  4382.9  370.12  4509.3  366.49  4667.8  363.39  4914.7  360.73
  4980.3  361.79  5002.6  359.51  5008.1  360.08  5012.6  358.02  5013.1  357.52
  5019.1  358.02  5037.8  360.29  5059.7  360.84  5169.6  358.86  5180.6  359.88
  5198.1  358.49  5203.6  359.44  5221.2  358.49  5226.7  359.96  5244.3   358.5
  5249.8  359.68  5286.8  359.86  5365.1  358.29  5388.2  362.95  5411.3  364.89
  5499.1  368.22  5514.5  370.85  5532.1  370.14  5566.1  374.76    5598  374.73
#Mann= 6 ,-1 , 0
    4023     .12       0  4509.3     .07       0  4667.8      .1       0
  5012.6     .05       0  5019.1      .1       0  5286.8     .12       0
Bank Sta=5012.6,5019.1
XS Rating Curve= 0 ,0
Exp/Cntr=0.3,0.1

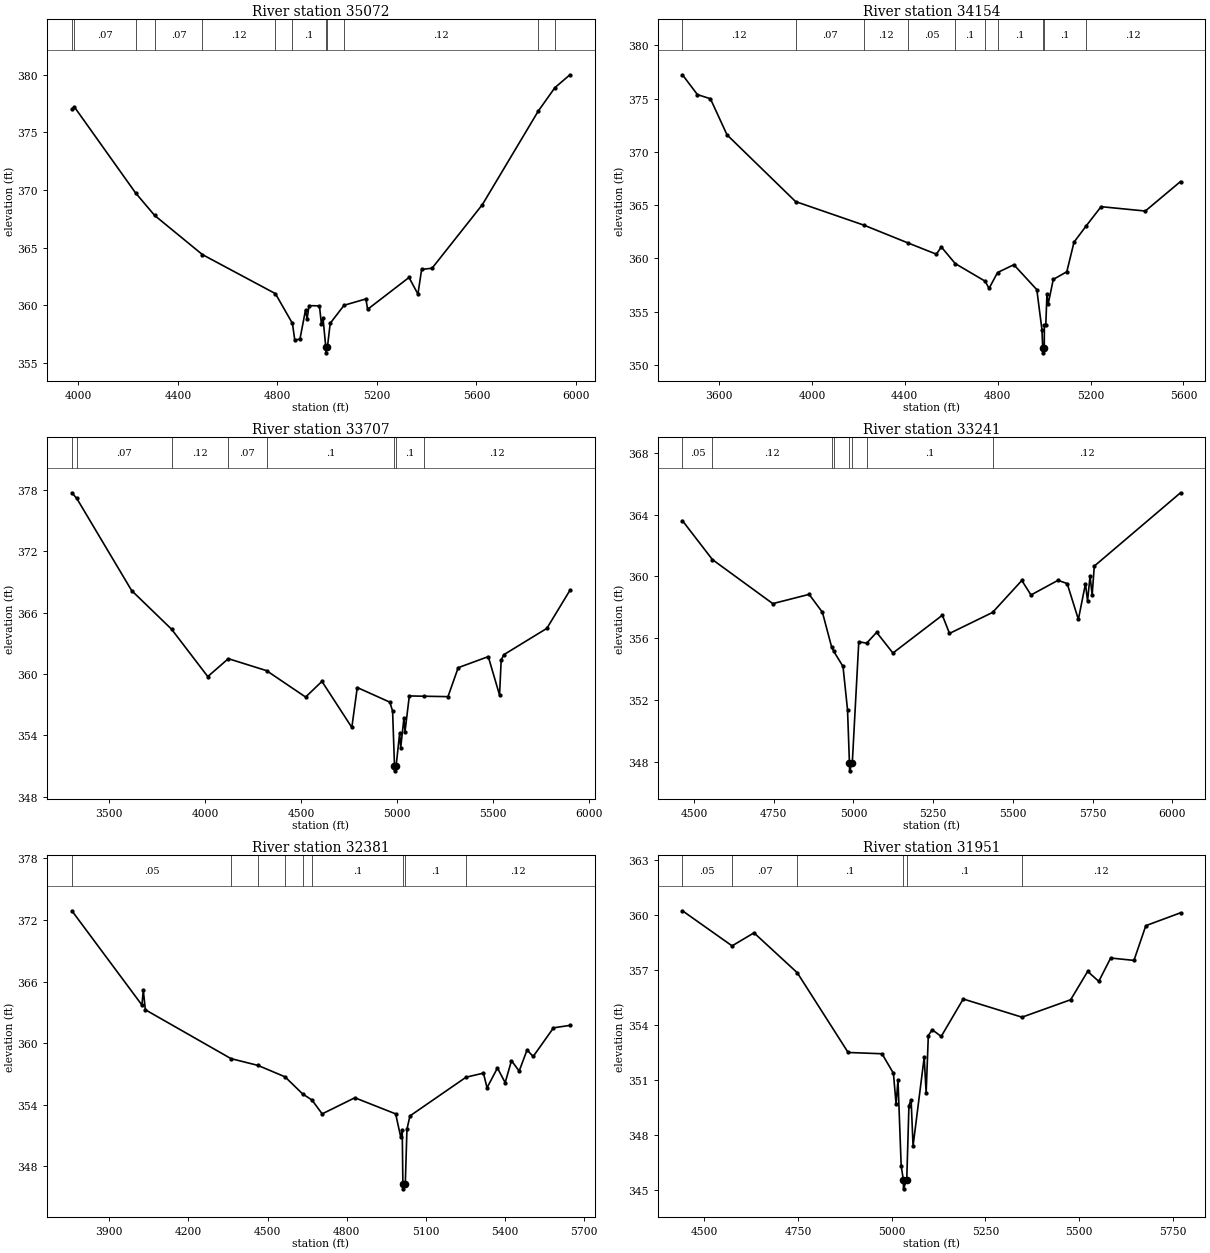
Type RM Length L Ch R = 1 ,35072   ,918,918,918
BEGIN DESCRIPTION:
Little Fivemile Creek 56.0
END DESCRIPTION:
XS GIS Cut Line= 3
      2543525.01     13825125.01        2542725.       13824475.
      2541925.01     13825024.99
#Sta/Elev= 30
  3974.1  376.98  3983.9   377.2  4230.2  369.74  4306.9  367.79  4498.8   364.4
    4792  361.02  4860.5  358.44  4869.8     357  4890.7  357.08    4913   359.6
  4919.4  358.82  4927.3  359.98    4969  359.96  4976.9  358.39  4983.3  358.92
  4994.4  356.39  4994.9  355.89  5001.1  356.39  5012.3  358.45    5068  360.01
  5155.8  360.56  5162.6  359.66    5329  362.42  5364.8  360.98  5379.7  363.12
  5421.6  363.22  5623.8  368.73  5848.6  376.84  5915.1  378.86  5975.7  379.98
#Mann= 12 ,-1 , 0
  3974.1     .12       0  3983.9     .07       0  4230.2     .12       0
  4306.9     .07       0  4498.8     .12       0    4792     .07       0
  4860.5      .1       0  4994.4     .05       0  5001.1      .1       0
    5068     .12       0  5848.6     .05       0  5915.1     .07       0
Bank Sta=4994.4,5001.1
XS Rating Curve= 0 ,0
Exp/Cntr=0.3,0.1

Type RM Length L Ch R = 1 ,34154   ,447,447,447
BEGIN DESCRIPTION:
Little Fivemile Creek 55.0
END DESCRIPTION:
XS GIS Cut Line= 3
      2543824.98     13824724.98        2542625.       13823725.
      2542125.02     13824024.99
#Sta/Elev= 30
  3442.4  377.24  3506.8  375.38  3562.8  374.99  3634.4   371.6  3929.5  365.34
  4223.4  363.13  4414.3  361.45  4535.8   360.4  4557.3  361.08  4617.1  359.52
  4745.6  357.87    4763  357.19  4799.5  358.68  4869.7  359.41  4968.6  357.07
  4990.8   353.3  4993.9  351.64  4994.4  351.14  5000.7  351.64  5001.2  353.77
  5007.3  353.77  5012.2  356.64    5018  355.76  5039.4  358.03  5097.7  358.75
  5128.8  361.53  5181.1  363.05  5245.4  364.86  5435.9  364.45  5587.5  367.22
#Mann= 10 ,-1 , 0
  3442.4     .12       0  3929.5     .07       0  4223.4     .12       0
  4414.3     .05       0  4617.1      .1       0  4745.6     .07       0
  4799.5      .1       0  4993.9     .05       0  5000.7      .1       0
  5181.1     .12       0
Bank Sta=4993.9,5000.7
XS Rating Curve= 0 ,0
Exp/Cntr=0.3,0.1

Type RM Length L Ch R = 1 ,33707   ,466,466,466
BEGIN DESCRIPTION:
Little Fivemile Creek 54.0
END DESCRIPTION:
XS GIS Cut Line= 3
      2543975.01     13824525.01        2542775.       13823325.
        2541975.       13823725.
#Sta/Elev= 30
  3307.7  377.71  3333.1  377.16  3618.8  368.15  3826.4  364.38  4014.8  359.75
  4121.7   361.5  4320.6  360.33  4523.9  357.75  4608.8  359.28  4764.4  354.78
  4792.6  358.68  4962.3  357.25  4976.5  356.37  4986.3  351.04  4986.8  350.54
  4994.9  351.04  5013.2  354.22  5018.7  352.82  5035.5  355.69  5041.1  354.38
  5063.5  357.86    5140  357.83  5264.7  357.79  5317.8  360.62  5474.3   361.7
    5533  357.94  5541.4  361.36  5555.4  361.89    5779  364.46  5899.2  368.18
#Mann= 8 ,-1 , 0
  3307.7     .12       0  3333.1     .07       0  3826.4     .12       0
  4121.7     .07       0  4320.6      .1       0  4986.3     .05       0
  4994.9      .1       0    5140     .12       0
Bank Sta=4986.3,4994.9
XS Rating Curve= 0 ,0
Exp/Cntr=0.3,0.1

Type RM Length L Ch R = 1 ,33241   ,860,860,860
BEGIN DESCRIPTION:
Little Fivemile Creek 53.0
END DESCRIPTION:
XS GIS Cut Line= 3
      2543225.04     13822624.97        2542825.       13822975.
      2542025.02     13823624.98
#Sta/Elev= 30
  4463.7  363.61  4557.8  361.09  4747.1  358.24    4861  358.84  4902.7  357.68
  4931.6  355.43  4938.6  355.14  4967.3  354.17  4981.5  351.36  4987.5  347.91
    4988  347.41  4996.4  347.91  5016.8  355.77  5041.5  355.68  5072.8  356.38
  5123.9  355.04    5279  357.49  5301.3  356.31  5436.5  357.67  5528.2  359.74
    5557   358.8  5641.7  359.75  5670.5  359.54  5705.6  357.22  5727.9  359.53
  5734.4  358.41  5742.3  360.04  5748.8  358.79  5755.5  360.67    6026  365.42
#Mann= 8 ,-1 , 0
  4463.7     .05       0  4557.8     .12       0  4931.6      .1       0
  4938.6     .12       0  4987.5     .05       0  4996.4     .12       0
  5041.5      .1       0  5436.5     .12       0
Bank Sta=4987.5,4996.4
XS Rating Curve= 0 ,0
Exp/Cntr=0.3,0.1

Type RM Length L Ch R = 1 ,32381   ,430,430,430
BEGIN DESCRIPTION:
Little Fivemile Creek 52.0
END DESCRIPTION:
XS GIS Cut Line= 3
      2543474.99       13822225.        2542275.       13822525.
      2541675.02     13822774.99
#Sta/Elev= 30
  3758.7   372.9  4024.1  363.72  4029.3  365.17    4037  363.26  4361.6   358.5
  4463.8  357.84  4566.1  356.73  4633.1  355.06  4668.3  354.47    4707  353.12
  4830.7  354.69  4985.3  353.12  5004.8  350.84  5010.2  351.57  5012.7  346.32
  5013.2  345.82  5021.9  346.32  5028.1  351.62  5039.5  352.92  5251.9  356.69
  5317.9  357.09  5331.5  355.66    5371  357.59  5400.2  356.16  5424.1   358.3
  5453.3  357.29  5483.1  359.34  5506.4  358.71  5583.3   361.5  5645.6  361.74
#Mann= 9 ,-1 , 0
  3758.7     .05       0  4361.6     .07       0  4463.8     .05       0
  4566.1      .1       0  4633.1     .05       0  4668.3      .1       0
  5012.7     .05       0  5021.9      .1       0  5251.9     .12       0
Bank Sta=5012.7,5021.9
XS Rating Curve= 0 ,0
Exp/Cntr=0.3,0.1

Type RM Length L Ch R = 1 ,31951   ,475,475,475
BEGIN DESCRIPTION:
Little Fivemile Creek 51.0
END DESCRIPTION:
XS GIS Cut Line= 3
      2543025.04       13822275.        2542475.       13822225.
      2541725.02       13822425.
#Sta/Elev= 30
  4441.7  360.22  4574.1  358.31  4632.5  359.02  4747.9  356.85  4883.6  352.51
  4973.9  352.44  5004.4  351.38  5011.5   349.7  5016.6  351.01  5025.1  346.34
  5030.8  345.59  5031.3  345.09    5040  345.59  5045.8  349.62  5051.6  349.94
  5056.8  347.42  5086.5  352.25  5091.7   350.3  5097.5  353.43  5107.9  353.75
  5131.8  353.38  5190.6  355.42  5347.4  354.43  5477.2  355.38  5522.5  356.92
  5552.2  356.38  5583.9  357.65    5646  357.52  5677.7  359.41  5770.2  360.11
#Mann= 6 ,-1 , 0
  4441.7     .05       0  4574.1     .07       0  4747.9      .1       0
  5030.8     .05       0    5040      .1       0  5347.4     .12       0
Bank Sta=5030.8,5040
XS Rating Curve= 0 ,0
Exp/Cntr=0.3,0.1

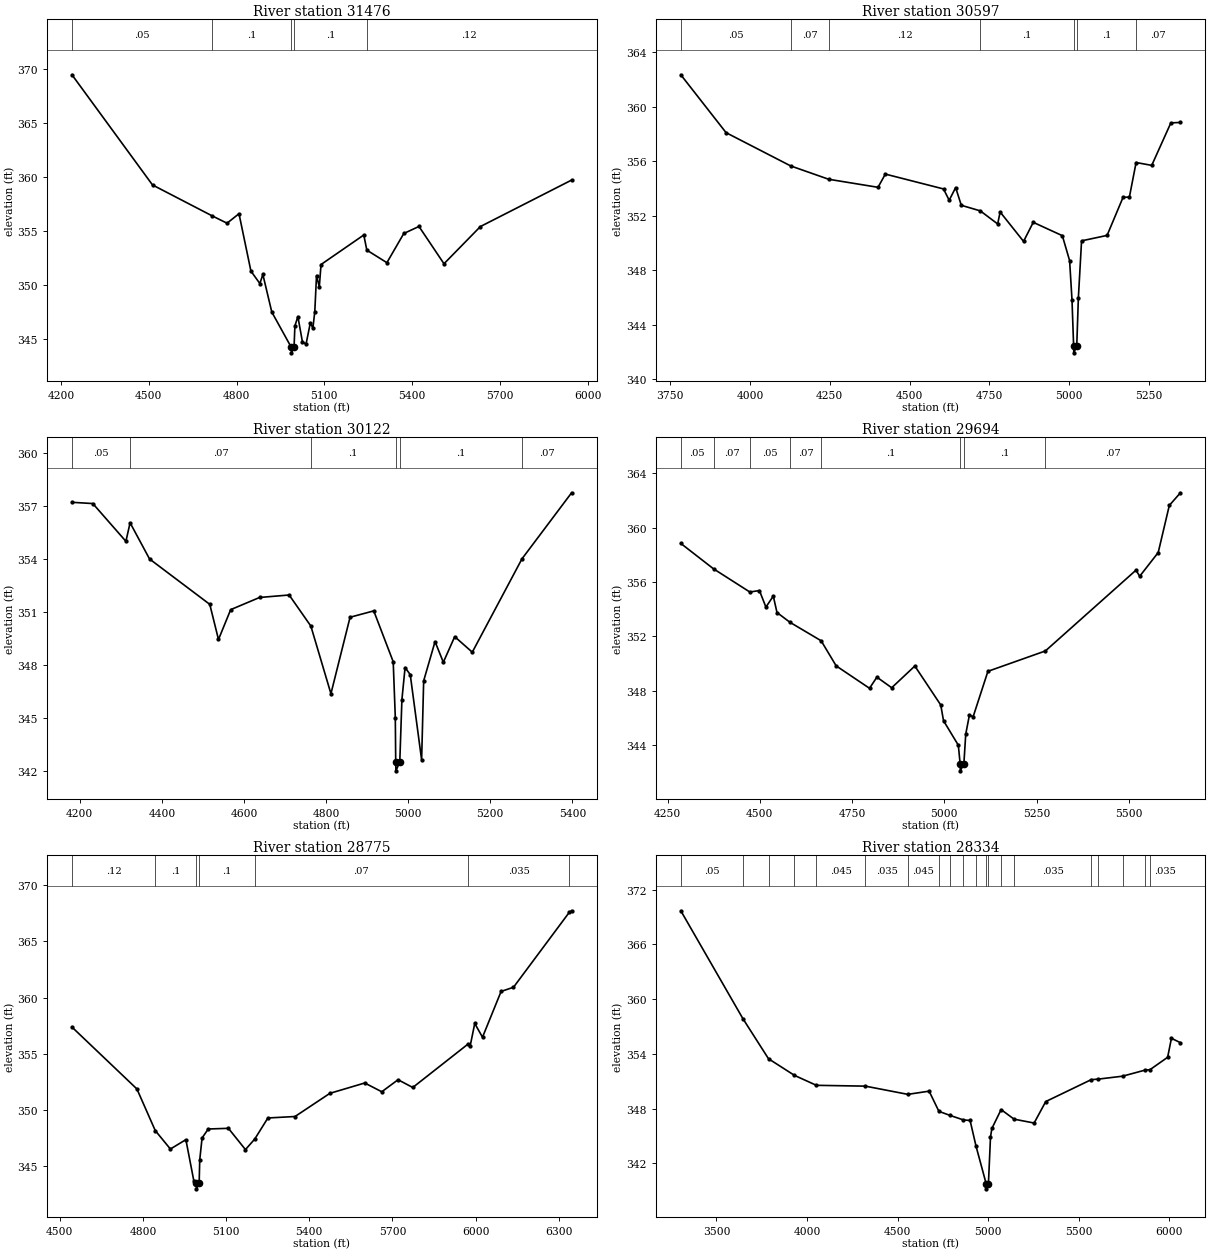
Type RM Length L Ch R = 1 ,31476   ,879,879,879
BEGIN DESCRIPTION:
Little Fivemile Creek 50.0
END DESCRIPTION:
XS GIS Cut Line= 3
      2543275.03     13821724.99        2542525.       13821875.
      2541724.98     13822375.01
#Sta/Elev= 30
  4237.1  369.43  4512.5  359.24  4714.3  356.41  4767.4   355.7  4808.2  356.58
    4849  351.27  4879.6  350.12  4889.8  350.96  4920.4  347.48  4987.2  344.21
  4987.7  343.71  4996.4  344.21  4999.4  346.21  5009.6  347.06    5025  344.74
  5037.4  344.51  5052.1  346.48  5060.9  346.01  5067.4  347.53  5073.3  350.86
  5082.8  349.81  5088.7  351.88  5234.9  354.61  5245.3  353.21  5313.9  352.05
  5371.7  354.75  5423.6   355.4  5509.1  351.95  5633.5  355.39  5945.4  359.69
#Mann= 5 ,-1 , 0
  4237.1     .05       0  4714.3      .1       0  4987.2     .05       0
  4996.4      .1       0  5245.3     .12       0
Bank Sta=4987.2,4996.4
XS Rating Curve= 0 ,0
Exp/Cntr=0.3,0.1

Type RM Length L Ch R = 1 ,30597   ,475,475,475
BEGIN DESCRIPTION:
Little Fivemile Creek 49.0
END DESCRIPTION:
XS GIS Cut Line= 3
      2543075.03     13821625.01        2541875.       13821425.
      2541524.99       13821425.
#Sta/Elev= 30
  3782.9  362.34  3924.9  358.09  4127.4  355.65  4246.6  354.67  4401.3  354.08
  4424.2  355.05  4606.6  353.96  4624.4  353.13  4644.7  354.06  4662.4  352.76
    4722  352.35  4776.5  351.39  4784.1  352.27  4857.6  350.11    4888  351.51
  4979.2  350.53    5002   348.7  5009.5  345.82  5014.6  342.43  5015.1  341.93
  5024.4  342.43  5029.5  345.98  5039.5  350.15  5119.5  350.55  5169.5  353.34
  5189.5  353.37  5210.5   355.9  5259.5  355.69  5319.5  358.81  5349.5  358.84
#Mann= 7 ,-1 , 0
  3782.9     .05       0  4127.4     .07       0  4246.6     .12       0
    4722      .1       0  5014.6     .05       0  5024.4      .1       0
  5210.5     .07       0
Bank Sta=5014.6,5024.4
XS Rating Curve= 0 ,0
Exp/Cntr=0.3,0.1

Type RM Length L Ch R = 1 ,30122   ,428,428,428
BEGIN DESCRIPTION:
Little Fivemile Creek 48.0
END DESCRIPTION:
XS GIS Cut Line= 3
      2542774.96     13820875.01        2541975.       13821025.
      2541575.02       13820975.
#Sta/Elev= 30
    4181   357.2  4231.8  357.13  4312.4  354.99  4322.6  356.04    4370  353.99
  4516.7  351.42  4537.9  349.43  4567.6  351.12    4638  351.81    4710  351.95
  4762.9  350.19  4811.8  346.36  4858.4  350.69  4916.1  351.05  4963.5  348.17
  4968.6  345.01  4969.6  342.49  4970.1  341.99  4979.5  342.49  4984.7  346.03
  4992.4  347.84    5005  347.44  5032.7  342.61  5037.7  347.09  5065.4  349.31
  5085.6  348.14  5113.3  349.59  5156.1  348.71  5277.2     354    5398  357.74
#Mann= 6 ,-1 , 0
    4181     .05       0  4322.6     .07       0  4762.9      .1       0
  4969.6     .05       0  4979.5      .1       0  5277.2     .07       0
Bank Sta=4969.6,4979.5
XS Rating Curve= 0 ,0
Exp/Cntr=0.3,0.1

Type RM Length L Ch R = 1 ,29694   ,919,919,919
BEGIN DESCRIPTION:
Little Fivemile Creek 47.0
END DESCRIPTION:
XS GIS Cut Line= 3
      2542824.97       13820825.        2542125.       13820775.
      2541474.97       13820725.
#Sta/Elev= 30
    4286  358.84  4374.6  356.97  4473.1  355.26    4499  355.37  4516.6  354.15
  4536.6  354.96  4546.6  353.75  4581.8  353.03  4666.2  351.67    4707  349.82
  4797.3  348.17  4817.3  348.99  4857.4  348.21  4920.1  349.81  4990.3  346.94
  4997.8  345.78  5037.9  343.98  5042.9  342.59  5043.4  342.09  5052.9  342.59
    5058  344.79    5068  346.21    5078  346.07  5118.1  349.42  5273.8  350.92
  5519.3  356.87  5529.3  356.42  5579.5  358.17  5609.6  361.64  5639.7  362.57
#Mann= 8 ,-1 , 0
    4286     .05       0  4374.6     .07       0  4473.1     .05       0
  4581.8     .07       0  4666.2      .1       0  5042.9     .05       0
  5052.9      .1       0  5273.8     .07       0
Bank Sta=5042.9,5052.9
XS Rating Curve= 0 ,0
Exp/Cntr=0.3,0.1

Type RM Length L Ch R = 1 ,28775   ,441,441,441
BEGIN DESCRIPTION:
Little Fivemile Creek 46.0
END DESCRIPTION:
XS GIS Cut Line= 3
        2542825.       13820425.        2542475.       13820125.
      2541275.01     13820724.99
#Sta/Elev= 30
  4543.9  357.37  4778.2  351.87  4844.4  348.17    4899  346.53  4954.9  347.36
  4983.5  343.71  4992.7  343.49  4993.2  342.99  5002.8  343.49  5004.9  345.56
  5013.3  347.51  5035.6  348.31  5108.3  348.37  5169.8  346.48  5203.5  347.42
  5250.8  349.29  5348.7  349.42  5474.4  351.48  5600.2   352.4  5661.7  351.62
  5720.4  352.69  5773.5     352  5971.8  355.84  5980.4  355.67  5997.1  357.69
  6025.1  356.47  6092.2  360.54  6136.9  360.91  6338.4  367.58  6346.5  367.71
#Mann= 7 ,-1 , 0
  4543.9     .12       0  4844.4      .1       0  4992.7     .05       0
  5002.8      .1       0  5203.5     .07       0  5971.8    .035       0
  6338.4     .07       0
Bank Sta=4992.7,5002.8
XS Rating Curve= 0 ,0
Exp/Cntr=0.3,0.1

Type RM Length L Ch R = 1 ,28334   ,436,436,436
BEGIN DESCRIPTION:
Little Fivemile Creek 45.0
END DESCRIPTION:
XS GIS Cut Line= 3
      2543625.02     13818574.98        2542425.       13819775.
        2541625.       13820475.
#Sta/Elev= 30
  3302.9  369.68  3645.7  357.87  3787.4  353.47  3930.8  351.65  4051.8  350.56
  4322.6  350.47    4557  349.57  4674.7  349.92  4728.7  347.71  4790.7  347.26
  4864.1  346.77    4901  346.71    4934  343.88  4990.6  339.72  4991.1  339.22
  5002.2  339.72  5013.7  344.89  5021.3  345.83  5072.4   347.9  5144.2  346.85
  5254.8  346.43  5318.9  348.78  5570.1  351.18  5609.1  351.24  5743.3  351.56
  5868.2  352.23  5893.9  352.26  5992.3  353.63  6013.2  355.71    6063  355.23
#Mann= 20 ,-1 , 0
  3302.9     .05       0  3645.7     .07       0  3787.4     .05       0
  3930.8     .05       0  4051.8    .045       0  4322.6    .035       0
    4557    .045       0  4728.7    .035       0  4790.7      .1       0
  4864.1    .035       0    4934      .1       0  4990.6    .035       0
  5002.2      .1       0  5072.4      .1       0  5144.2    .035       0
  5570.1     .07       0  5609.1    .035       0  5743.3    .035       0
  5868.2     .07       0  5893.9    .035       0
Bank Sta=4990.6,5002.2
XS Rating Curve= 0 ,0
Exp/Cntr=0.3,0.1

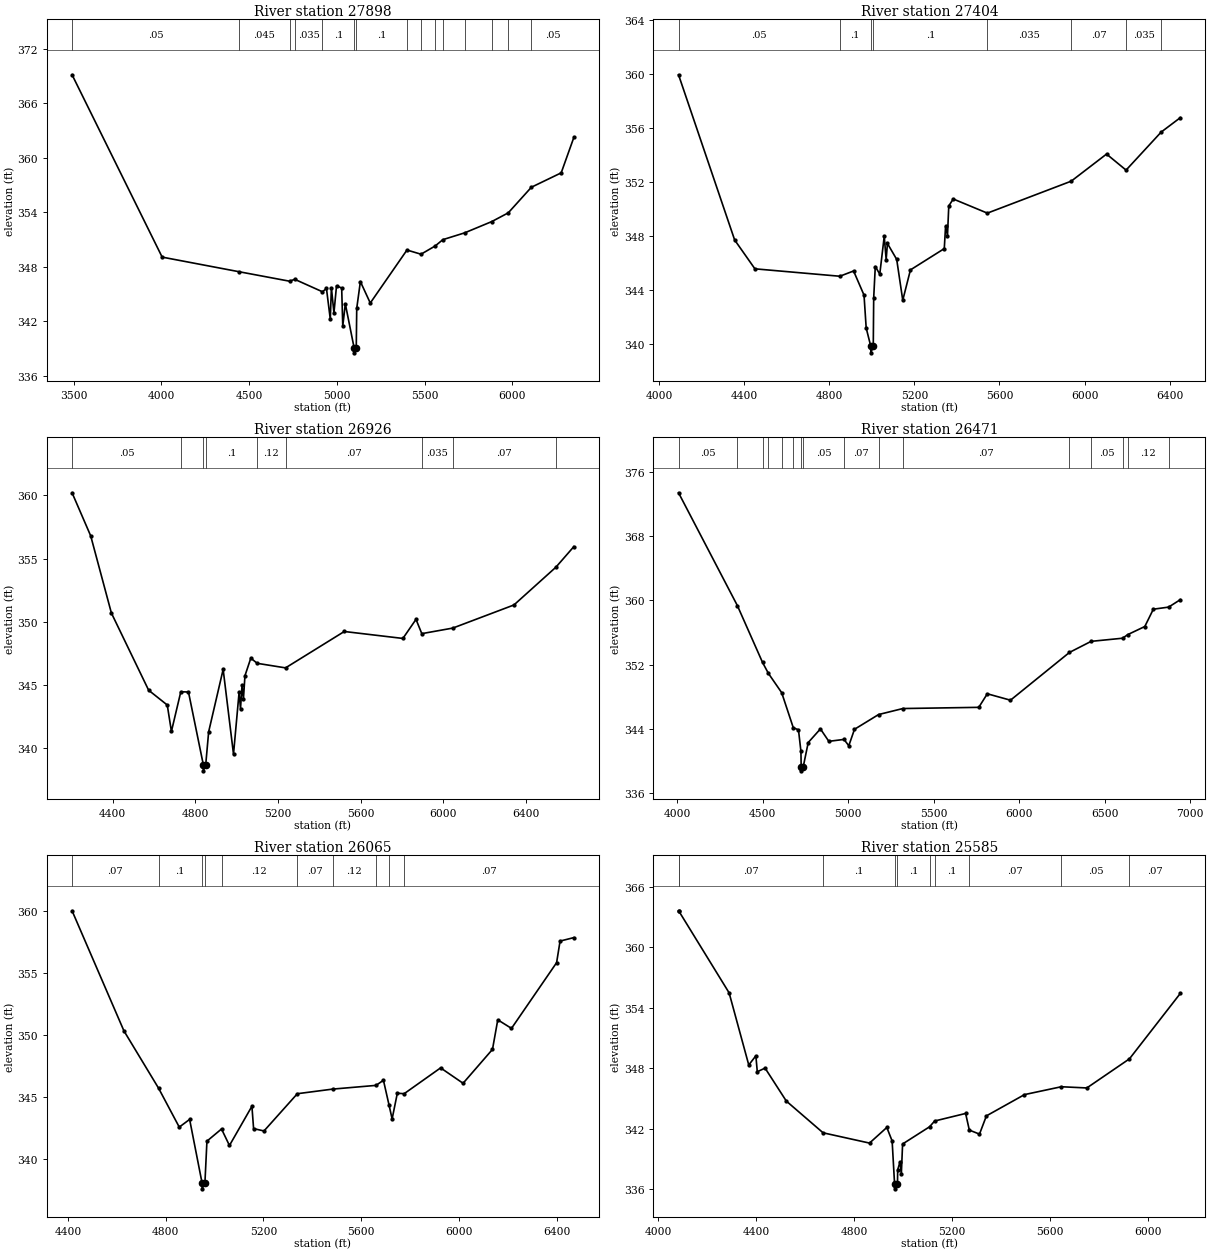
Type RM Length L Ch R = 1 ,27898   ,494,494,494
BEGIN DESCRIPTION:
Little Fivemile Creek 44.0
END DESCRIPTION:
XS GIS Cut Line= 3
      2543574.98     13818525.02        2542375.       13819425.
      2541275.01     13820224.99
#Sta/Elev= 30
  3490.9  369.12  4004.4  349.06  4443.6  347.45  4730.8  346.41  4759.8  346.62
  4917.9  345.25  4940.9  345.61  4962.7  342.23    4969  345.68  4983.6  342.93
  4998.2  345.91  5027.6  345.66  5033.8  341.47  5048.4  343.92    5099  339.03
  5099.5  338.53  5110.7  339.03  5113.4  343.42  5134.2  346.37  5190.6  344.01
  5399.8  349.84  5479.8  349.38  5560.9  350.29  5604.1  350.98  5728.5  351.73
  5883.1  352.97  5977.1  353.93    6109  356.75  6278.8  358.33    6351  362.23
#Mann= 15 ,-1 , 0
  3490.9     .05       0  4443.6    .045       0  4730.8      .1       0
  4759.8    .035       0  4917.9      .1       0    5099     .05       0
  5110.7      .1       0  5399.8     .07       0  5479.8    .035       0
  5560.9     .07       0  5604.1     .05       0  5728.5    .035       0
  5883.1     .05       0  5977.1    .035       0    6109     .05       0
Bank Sta=5099,5110.7
XS Rating Curve= 0 ,0
Exp/Cntr=0.3,0.1

Type RM Length L Ch R = 1 ,27404   ,478,478,478
BEGIN DESCRIPTION:
Little Fivemile Creek 43.0
END DESCRIPTION:
XS GIS Cut Line= 3
      2543275.04     13818524.98        2542475.       13818975.
      2541275.04     13819774.97
#Sta/Elev= 30
  4090.5  359.95  4354.4   347.7  4449.7  345.56  4849.1  345.01  4913.8   345.4
  4962.9  343.61  4973.1  341.17  4994.5  339.83    4995  339.33  5006.4  339.83
  5008.4  343.41  5015.9  345.73    5037  345.17    5058  347.97    5067  346.25
    5073  347.44  5116.6  346.26  5145.1  343.23  5181.2  345.48  5340.4  347.06
  5346.4   348.7  5355.5  348.03  5361.5  350.22  5382.5  350.74    5543  349.69
  5937.4  352.06  6103.6  354.07  6195.4  352.88  6360.5   355.7  6450.6  356.77
#Mann= 8 ,-1 , 0
  4090.5     .05       0  4849.1      .1       0  4994.5     .05       0
  5006.4      .1       0    5543    .035       0  5937.4     .07       0
  6195.4    .035       0  6360.5     .05       0
Bank Sta=4994.5,5006.4
XS Rating Curve= 0 ,0
Exp/Cntr=0.3,0.1

Type RM Length L Ch R = 1 ,26926   ,455,455,455
BEGIN DESCRIPTION:
Little Fivemile Creek 42.0
END DESCRIPTION:
XS GIS Cut Line= 3
      2543275.05       13818475.        2542475.       13818525.
      2541274.99     13819625.01
#Sta/Elev= 30
  4202.8  360.21    4293   356.8  4393.2  350.69  4573.6  344.58  4663.7  343.41
  4683.8  341.32  4729.3  344.46  4766.4  344.44  4838.1   338.7  4838.6   338.2
    4850   338.7  4864.1  341.29  4934.3  346.23  4984.4  339.52  5011.5  344.42
  5018.3  343.11  5025.7  344.97  5032.5   343.9  5039.9  345.73  5068.2  347.12
  5099.3  346.71  5236.4  346.35  5520.8  349.23  5804.5  348.68    5868  350.19
  5896.1  349.06  6046.1   349.5  6342.2  351.33  6545.4  354.32  6632.3  355.95
#Mann= 9 ,-1 , 0
  4202.8     .05       0  4729.3      .1       0  4838.1     .05       0
    4850      .1       0  5099.3     .12       0  5236.4     .07       0
  5896.1    .035       0  6046.1     .07       0  6545.4    .035       0
Bank Sta=4838.1,4850
XS Rating Curve= 0 ,0
Exp/Cntr=0.3,0.1

Type RM Length L Ch R = 1 ,26471   ,406,406,406
BEGIN DESCRIPTION:
Little Fivemile Creek 41.0
END DESCRIPTION:
XS GIS Cut Line= 3
      2543274.97     13817475.03        2542525.       13818125.
      2540924.98     13819225.01
#Sta/Elev= 30
  4007.6  373.42  4351.6  359.35  4498.8  352.26  4533.2  350.89  4610.7  348.49
  4678.7  344.11  4708.9  343.86  4723.2  341.18  4724.8  339.24  4725.3  338.74
  4736.7  339.24  4765.9  342.27  4837.2  343.97  4886.5  342.42  4975.1  342.66
  5003.1  341.87  5036.4  343.92  5177.2  345.76  5319.1  346.51  5763.2  346.66
  5813.1  348.35  5948.5  347.55  6293.5  353.51  6420.2  354.89  6603.7  355.28
  6634.3  355.73    6734  356.74  6783.9   358.9  6873.2  359.16  6941.7  360.09
#Mann= 16 ,-1 , 0
  4007.6     .05       0  4351.6     .07       0  4498.8      .1       0
  4533.2     .07       0  4610.7      .1       0  4678.7     .05       0
  4724.8     .05       0  4736.7     .05       0  4975.1     .07       0
  5177.2     .12       0  5319.1     .07       0  6293.5    .035       0
  6420.2     .05       0  6603.7     .07       0  6634.3     .12       0
  6873.2     .05       0
Bank Sta=4724.8,4736.7
XS Rating Curve= 0 ,0
Exp/Cntr=0.3,0.1

Type RM Length L Ch R = 1 ,26065   ,480,480,480
BEGIN DESCRIPTION:
Little Fivemile Creek 40.0
END DESCRIPTION:
XS GIS Cut Line= 3
      2542825.01     13817374.99        2542425.       13817775.
        2541325.       13818775.
#Sta/Elev= 30
  4417.3  359.98  4629.4  350.31  4771.2  345.69  4855.7  342.56  4898.1  343.18
  4948.7  338.09  4949.2  337.59  4960.7  338.09  4968.9  341.43  5028.5  342.41
    5061  341.08  5152.9  344.24  5159.7  342.44  5202.3  342.25  5338.7  345.25
  5482.7  345.62  5660.2  345.92  5690.8  346.33  5713.2  344.38  5726.3  343.22
  5747.6  345.29  5775.5  345.25  5924.6  347.33  6016.5  346.09  6136.8  348.82
  6158.4   351.2  6214.5  350.51    6399   355.8  6413.2  357.54  6469.6  357.82
#Mann= 10 ,-1 , 0
  4417.3     .07       0  4771.2      .1       0  4948.7     .05       0
  4960.7      .1       0  5028.5     .12       0  5338.7     .07       0
  5482.7     .12       0  5660.2     .07       0  5713.2     .12       0
  5775.5     .07       0
Bank Sta=4948.7,4960.7
XS Rating Curve= 0 ,0
Exp/Cntr=0.3,0.1

Type RM Length L Ch R = 1 ,25585   ,471,471,471
BEGIN DESCRIPTION:
Little Fivemile Creek 39.0
END DESCRIPTION:
XS GIS Cut Line= 3
      2542824.98     13817225.01        2542025.       13817675.
      2541225.02     13818474.98
#Sta/Elev= 30
  4082.1  363.61  4082.6  363.61  4288.6  355.47  4368.9  348.31  4397.9  349.22
  4403.7  347.64  4435.5     348  4522.2  344.73  4672.4  341.58    4862  340.56
  4932.7  342.11  4954.4  340.77  4964.3  336.52  4964.8  336.02  4976.3  336.52
    4977   337.9  4986.3  338.68    4992   337.5  4997.1  340.47  5107.4  342.18
    5128  342.75  5254.5   343.5  5269.6  341.85  5311.1  341.45  5339.4  343.26
  5494.9  345.37  5645.2  346.15  5749.5  346.03  5923.6  348.92  6131.3  355.41
#Mann= 10 ,-1 , 0
  4082.1     .05       0  4082.6     .07       0  4672.4      .1       0
  4964.3     .05       0  4976.3      .1       0  5107.4     .07       0
    5128      .1       0  5269.6     .07       0  5645.2     .05       0
  5923.6     .07       0
Bank Sta=4964.3,4976.3
XS Rating Curve= 0 ,0
Exp/Cntr=0.3,0.1