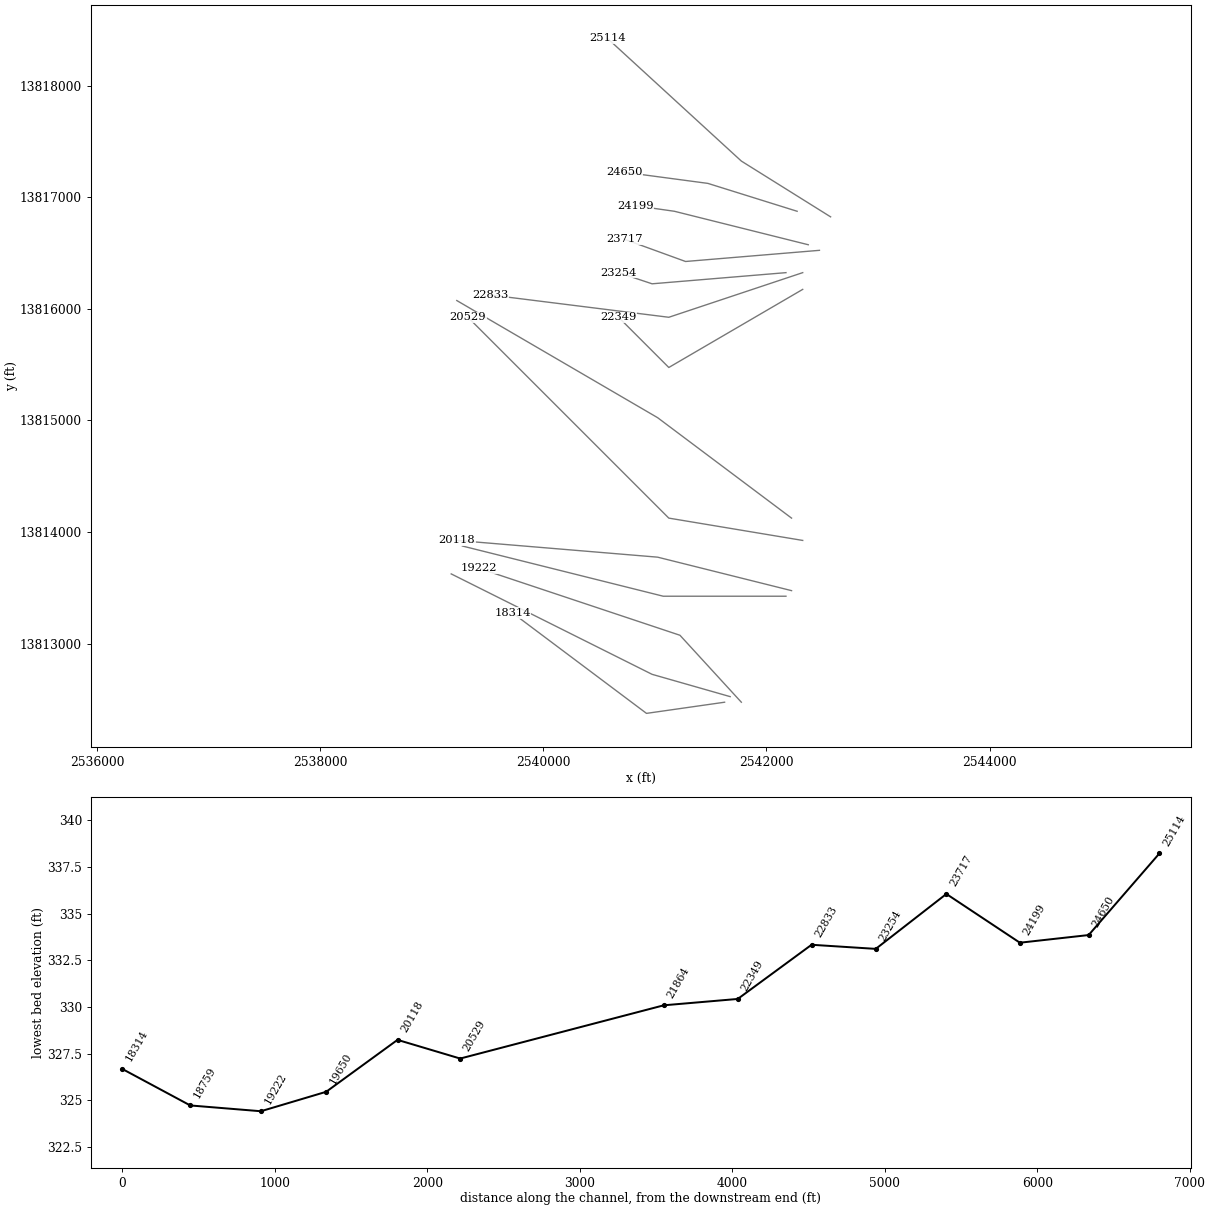
HEC-RAS study Little Fivemile Creek.prj: Little Fivemile Creek Base Level Engineering

--- Little Fivemile Creek.g01 (geometry) --- (continued)

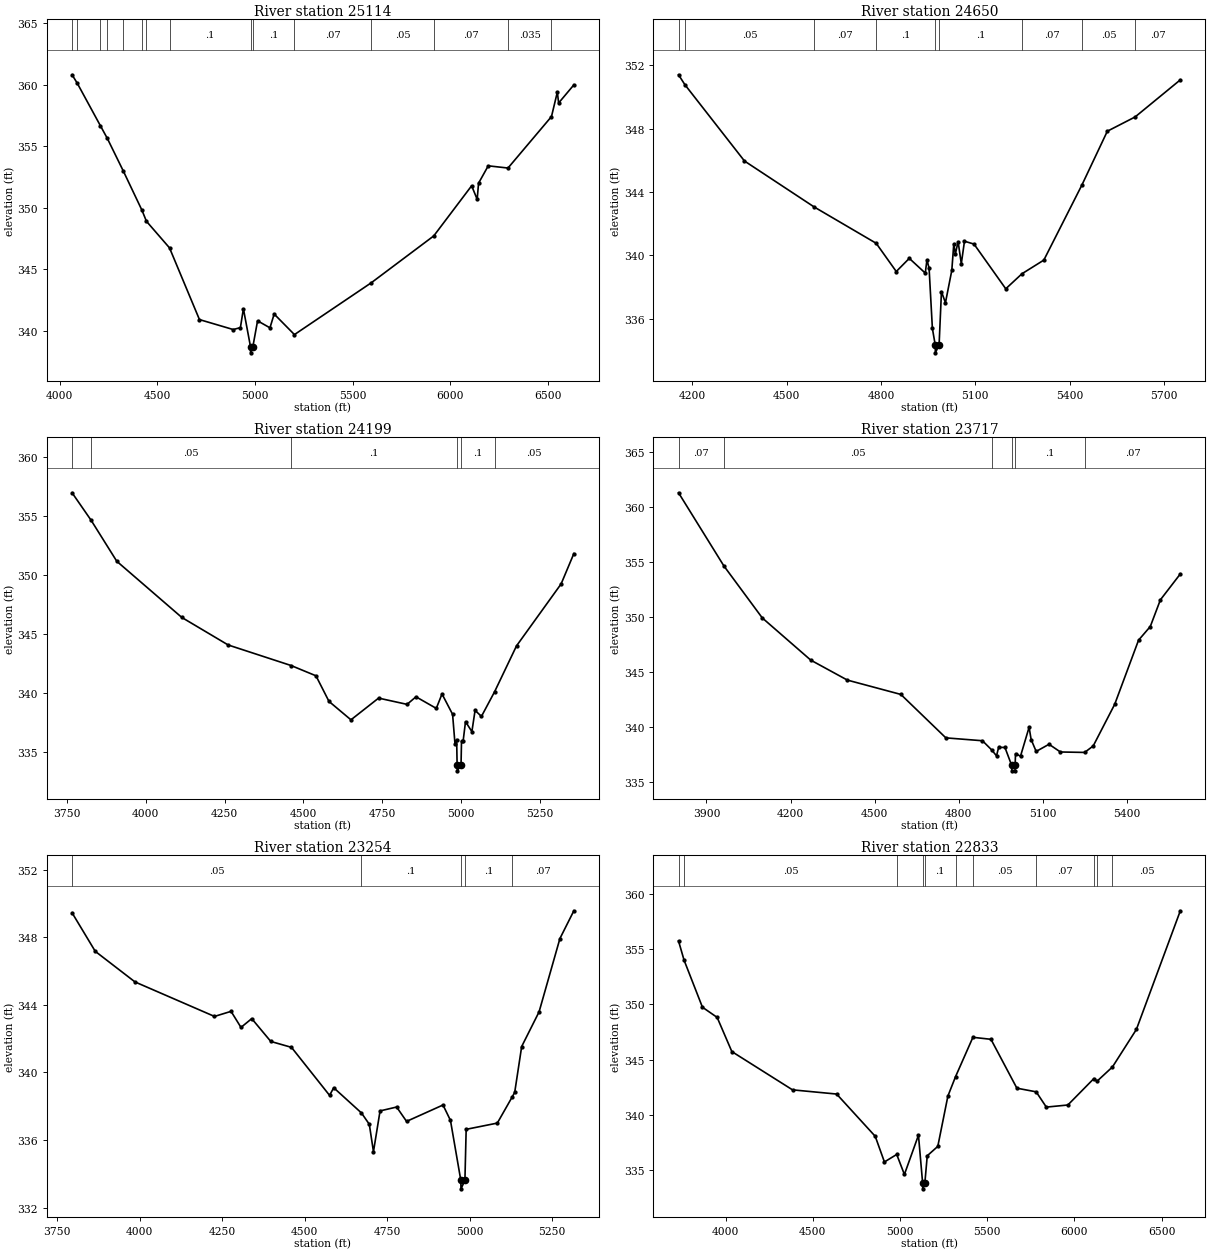
Type RM Length L Ch R = 1 ,25114   ,464,464,464
BEGIN DESCRIPTION:
Little Fivemile Creek 38.0
END DESCRIPTION:
XS GIS Cut Line= 3
      2542574.97     13816825.02        2541775.       13817325.
      2540575.03     13818424.97
#Sta/Elev= 30
  4062.5  360.79  4088.9  360.11  4207.1  356.67  4243.3  355.62  4325.3  352.97
    4421  349.78  4443.5   348.9  4561.8  346.74  4715.2  340.92  4888.5  340.11
  4925.1  340.27  4940.4   341.8  4976.8  338.72  4977.3  338.22  4988.9  338.72
    5013  340.82  5076.5  340.25    5098  341.37  5201.9   339.7  5595.9  343.91
  5915.8  347.71  6109.9  351.78  6138.3  350.68  6145.4  351.99    6195   353.4
  6296.2  353.22  6519.1   357.4    6549  359.38  6555.7   358.5  6633.7  359.97
#Mann= 15 ,-1 , 0
  4062.5     .07       0  4088.9    .035       0  4207.1     .07       0
  4243.3    .035       0  4325.3     .07       0    4421      .1       0
  4443.5     .07       0  4561.8      .1       0  4976.8     .05       0
  4988.9      .1       0  5201.9     .07       0  5595.9     .05       0
  5915.8     .07       0  6296.2    .035       0  6519.1     .07       0
Bank Sta=4976.8,4988.9
XS Rating Curve= 0 ,0
Exp/Cntr=0.3,0.1

Type RM Length L Ch R = 1 ,24650   ,451,451,451
BEGIN DESCRIPTION:
Little Fivemile Creek 37.0
END DESCRIPTION:
XS GIS Cut Line= 3
      2542275.04     13816874.99        2541475.       13817125.
      2540725.03       13817225.
#Sta/Elev= 30
  4156.7  351.39  4176.7  350.77  4366.3  345.95  4587.9  343.05  4784.9  340.76
  4848.7  338.98  4890.1  339.81  4940.9  338.88  4946.2  339.72    4953  339.19
  4963.5  335.39  4972.5  334.35    4973  333.85  4984.8  334.35  4992.3  337.71
    5005  337.01  5025.2  339.05  5031.5  340.72  5036.5  340.09  5045.3  340.86
  5055.4  339.47  5065.5  340.89  5095.8  340.71  5196.7  337.89  5248.3  338.84
  5317.7   339.7  5438.8  344.44  5519.5  347.83  5607.8  348.73  5751.5  351.07
#Mann= 9 ,-1 , 0
  4156.7    .035       0  4176.7     .05       0  4587.9     .07       0
  4784.9      .1       0  4972.5     .05       0  4984.8      .1       0
  5248.3     .07       0  5438.8     .05       0  5607.8     .07       0
Bank Sta=4972.5,4984.8
XS Rating Curve= 0 ,0
Exp/Cntr=0.3,0.1

Type RM Length L Ch R = 1 ,24199   ,482,482,482
BEGIN DESCRIPTION:
Little Fivemile Creek 36.0
END DESCRIPTION:
XS GIS Cut Line= 3
      2542374.97     13816575.01        2541175.       13816875.
      2540825.05     13816924.99
#Sta/Elev= 30
  3766.8  356.99  3827.2  354.66  3908.5  351.19  4114.7  346.43  4261.5   344.1
  4460.9  342.36  4539.8  341.49  4581.1  339.32  4650.7  337.76  4738.3   339.6
  4828.5  339.07  4856.8  339.71  4921.2  338.73  4939.3  339.95  4972.8  338.23
  4980.5  335.71  4985.7  336.09  4987.2  333.94  4987.7  333.44  4999.6  333.94
  5001.1  335.95  5006.2  335.95  5013.8  337.61    5034  336.76  5044.1  338.56
  5064.3  338.05    5106  340.14  5175.4  344.02  5316.8  349.27  5357.2  351.84
#Mann= 6 ,-1 , 0
  3766.8     .07       0  3827.2     .05       0  4460.9      .1       0
  4987.2     .05       0  4999.6      .1       0    5106     .05       0
Bank Sta=4987.2,4999.6
XS Rating Curve= 0 ,0
Exp/Cntr=0.3,0.1

Type RM Length L Ch R = 1 ,23717   ,463,463,463
BEGIN DESCRIPTION:
Little Fivemile Creek 35.0
END DESCRIPTION:
XS GIS Cut Line= 3
      2542475.02       13816525.        2541275.       13816425.
      2540725.01     13816624.99
#Sta/Elev= 30
  3800.5  361.27  3962.1  354.64  4099.1  349.92  4272.1  346.09  4402.6  344.28
  4593.3  342.98  4753.8  339.04  4884.3  338.78  4917.1  337.95  4934.4  337.41
    4942  338.18  4964.5  338.17  4988.4  336.55  4988.9  336.05  5000.3  336.05
  5000.8  336.55  5002.2  337.61    5020  337.38  5050.6     340  5057.9  338.89
  5075.8  337.81  5121.7  338.46  5162.3  337.76  5248.7  337.72  5279.3  338.31
  5355.8  342.08  5440.9   347.9  5482.8  349.14  5518.8  351.56  5589.9  353.91
#Mann= 6 ,-1 , 0
  3800.5     .07       0  3962.1     .05       0  4917.1      .1       0
  4988.4     .05       0  5000.8      .1       0  5248.7     .07       0
Bank Sta=4988.4,5000.8
XS Rating Curve= 0 ,0
Exp/Cntr=0.3,0.1

Type RM Length L Ch R = 1 ,23254   ,421,421,421
BEGIN DESCRIPTION:
Little Fivemile Creek 34.0
END DESCRIPTION:
XS GIS Cut Line= 3
      2542175.02       13816325.        2540975.       13816225.
      2540675.01       13816325.
#Sta/Elev= 30
  3795.3  349.44  3865.6  347.16    3986  345.35  4226.8  343.31    4277  343.61
  4307.1  342.66  4339.7  343.18  4397.4  341.83  4460.1  341.48  4575.5  338.64
  4588.1  339.09  4672.1   337.6  4695.9  336.93  4708.5  335.31  4728.5  337.72
  4778.7  337.95  4808.8   337.1  4919.2  338.07  4941.8  337.16  4973.2  333.61
  4973.7  333.11  4985.6  333.61  4989.4  336.63  5083.8     337  5128.1  338.52
  5136.5  338.82  5157.6  341.53  5210.3  343.58  5273.5  347.92  5315.7  349.56
#Mann= 5 ,-1 , 0
  3795.3     .05       0  4672.1      .1       0  4973.2     .05       0
  4985.6      .1       0  5128.1     .07       0
Bank Sta=4973.2,4985.6
XS Rating Curve= 0 ,0
Exp/Cntr=0.3,0.1

Type RM Length L Ch R = 1 ,22833   ,484,484,484
BEGIN DESCRIPTION:
Little Fivemile Creek 33.0
END DESCRIPTION:
XS GIS Cut Line= 3
      2542325.03     13816325.01        2541125.       13815925.
        2539525.       13816125.
#Sta/Elev= 30
  3730.5  355.74  3762.1  354.01  3867.6  349.75  3951.9  348.83  4036.2  345.74
  4384.1  342.28  4637.1   341.9  4858.4  338.08  4911.1  335.76  4981.6  336.44
  5025.7  334.63  5106.3  338.18  5130.3  333.83  5130.8  333.33  5142.8  333.83
  5156.7  336.32  5217.2  337.17  5275.1  341.72  5318.9  343.47  5418.5  347.03
    5522  346.85  5670.7  342.43  5781.4   342.1  5839.5  340.72  5962.9  340.91
  6112.2   343.3  6130.3  343.06  6218.7  344.35  6355.9  347.74  6607.9  358.47
#Mann= 11 ,-1 , 0
  3730.5     .07       0  3762.1     .05       0  4981.6      .1       0
  5130.3     .05       0  5142.8      .1       0  5318.9     .07       0
  5418.5     .05       0  5781.4     .07       0  6112.2     .05       0
  6130.3     .12       0  6218.7     .05       0
Bank Sta=5130.3,5142.8
XS Rating Curve= 0 ,0
Exp/Cntr=0.3,0.1

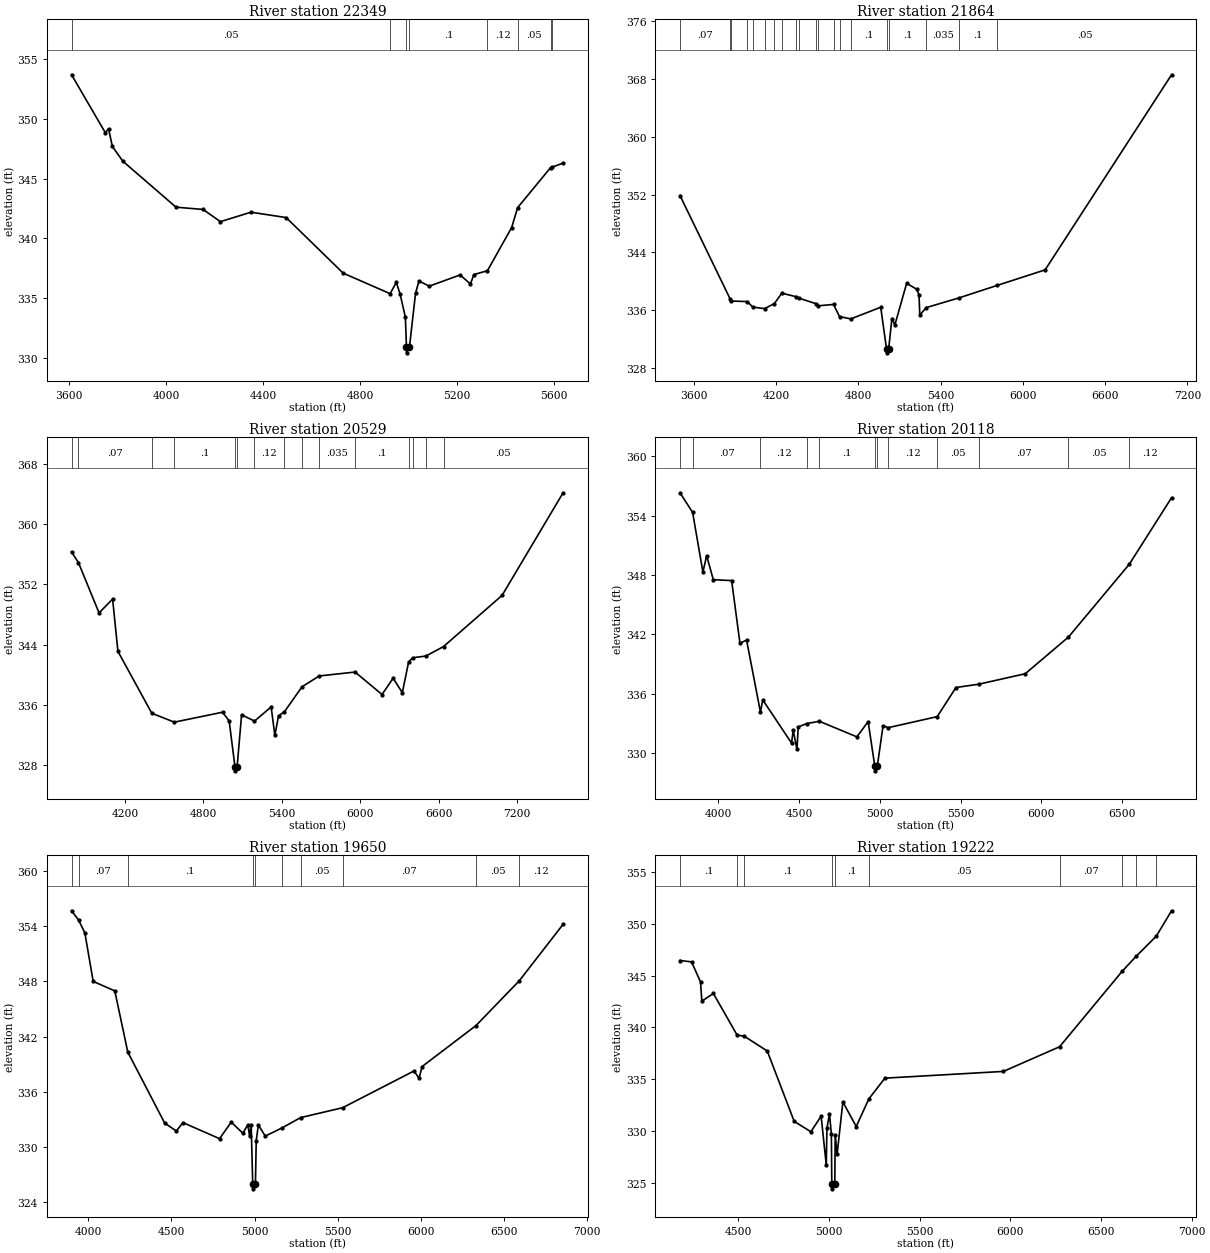
Type RM Length L Ch R = 1 ,22349   ,485,485,485
BEGIN DESCRIPTION:
Little Fivemile Creek 32.0
END DESCRIPTION:
XS GIS Cut Line= 3
      2542324.96     13816174.98        2541125.       13815475.
        2540675.       13815925.
#Sta/Elev= 30
  3610.9   353.7  3749.8  348.86  3763.4  349.18  3779.1   347.7  3822.1  346.47
  4041.3  342.62  4152.9  342.43  4224.4  341.41  4350.5   342.2  4495.3  341.75
  4730.1   337.1  4923.8  335.38  4949.2  336.33    4965  335.33  4986.5  333.42
    4991  330.93  4991.5  330.43  5003.5  330.93  5028.4  335.41  5042.5  336.44
    5085  336.01  5212.2  336.95  5254.7  336.19  5268.8  336.98  5324.6   337.3
  5424.4  340.91  5449.1  342.58  5585.4  345.94  5590.4  345.96  5636.5  346.31
#Mann= 8 ,-1 , 0
  3610.9     .05       0  4923.8      .1       0    4991     .05       0
  5003.5      .1       0  5324.6     .12       0  5449.1     .05       0
  5585.4     .07       0  5590.4     .05       0
Bank Sta=4991,5003.5
XS Rating Curve= 0 ,0
Exp/Cntr=0.3,0.1

Type RM Length L Ch R = 1 ,21864   ,1335,1335,1335
BEGIN DESCRIPTION:
Little Fivemile Creek 31.0
END DESCRIPTION:
XS GIS Cut Line= 3
        2542225.       13814125.        2541025.       13815025.
      2539224.97     13816075.02
#Sta/Elev= 30
  3499.9  351.87  3866.3  337.52  3872.4  337.26  3990.6  337.19  4030.5  336.43
  4116.4  336.21  4188.6  336.92  4242.2  338.35  4346.7  337.86  4367.9  337.66
  4493.7  336.88  4504.8   336.6  4619.5  336.79  4662.9  335.11  4745.2  334.79
  4963.4   336.4  5006.1  330.59  5006.6  330.09    5021  330.59    5045  334.84
  5066.5  333.95  5152.5  339.72  5226.9  338.88  5242.6  338.11  5248.4  335.31
  5294.8  336.35  5534.4   337.7    5813  339.43  6162.1  341.58  7083.8  368.59
#Mann= 20 ,-1 , 0
  3499.9     .07       0  3866.3     .12       0  3872.4     .07       0
  3990.6      .1       0  4030.5    .035       0  4116.4     .07       0
  4188.6    .035       0  4242.2     .07       0  4346.7    .035       0
  4367.9     .07       0  4493.7    .035       0  4504.8     .07       0
  4619.5     .12       0  4662.9     .07       0  4745.2      .1       0
  5006.1     .05       0    5021      .1       0  5294.8    .035       0
  5534.4      .1       0    5813     .05       0
Bank Sta=5006.1,5021
XS Rating Curve= 0 ,0
Exp/Cntr=0.3,0.1

Type RM Length L Ch R = 1 ,20529   ,411,411,411
BEGIN DESCRIPTION:
Little Fivemile Creek 30.0
END DESCRIPTION:
XS GIS Cut Line= 3
        2542325.       13813925.        2541125.       13814125.
      2539325.03     13815924.97
#Sta/Elev= 30
  3791.3  356.29  3843.9  354.88  4001.7   348.2  4105.6  350.03  4146.1   343.1
  4405.6  334.88  4577.5   333.7    4947  335.02  4997.7  333.86  5042.2  327.74
  5042.7  327.24  5058.3  327.74  5092.7  334.68  5191.4  333.84    5319  335.72
  5347.3  331.93  5375.5  334.55  5419.8  335.06  5555.1  338.39  5686.4  339.83
  5961.3  340.35  6167.5  337.37  6252.4  339.53  6323.1  337.61  6371.1  341.69
    6403  342.25  6502.8  342.47  6638.1  343.73  7086.7  350.53  7553.4  364.14
#Mann= 15 ,-1 , 0
  3791.3    .035       0  3843.9     .07       0  4405.6     .12       0
  4577.5      .1       0  5042.2     .05       0  5058.3      .1       0
  5191.4     .12       0  5419.8    .035       0  5555.1     .07       0
  5686.4    .035       0  5961.3      .1       0  6371.1    .035       0
    6403     .07       0  6502.8    .035       0  6638.1     .05       0
Bank Sta=5042.2,5058.3
XS Rating Curve= 0 ,0
Exp/Cntr=0.3,0.1

Type RM Length L Ch R = 1 ,20118   ,468,468,468
BEGIN DESCRIPTION:
Little Fivemile Creek 29.0
END DESCRIPTION:
XS GIS Cut Line= 3
      2542225.04     13813474.99        2541025.       13813775.
      2539225.01       13813925.
#Sta/Elev= 30
  3762.5   356.3  3840.6  354.32  3904.3   348.3  3927.5  349.95  3968.7  347.53
  4082.1  347.44  4133.6  341.12  4174.8  341.43  4260.3  334.18  4275.3  335.39
  4453.2  331.04  4463.5  332.32  4486.7   330.4  4494.4  332.67  4546.8  333.01
  4625.2  333.24  4857.7  331.67  4927.3  333.21  4968.2  328.74  4968.7  328.24
  4984.4  328.74  5019.5  332.79  5052.6   332.6  5354.7  333.71  5471.1  336.65
  5611.3  336.98  5900.1  338.04  6167.5  341.74  6544.2  349.09  6805.7   355.8
#Mann= 12 ,-1 , 0
  3762.5    .035       0  3840.6     .07       0  4260.3     .12       0
  4546.8     .07       0  4625.2      .1       0  4968.2     .05       0
  4984.4      .1       0  5052.6     .12       0  5354.7     .05       0
  5611.3     .07       0  6167.5     .05       0  6544.2     .12       0
Bank Sta=4968.2,4984.4
XS Rating Curve= 0 ,0
Exp/Cntr=0.3,0.1

Type RM Length L Ch R = 1 ,19650   ,428,428,428
BEGIN DESCRIPTION:
Little Fivemile Creek 28.0
END DESCRIPTION:
XS GIS Cut Line= 3
      2542175.05       13813425.        2541075.       13813425.
      2539275.05     13813874.99
#Sta/Elev= 30
  3899.8  355.66  3942.2  354.65  3979.8  353.26  4029.8  347.99  4159.8  346.96
  4237.9  340.31  4459.8   332.6  4529.8  331.74  4569.8  332.65  4789.8  330.91
  4859.8   332.7  4929.8   331.5  4959.8  332.42  4969.8  331.24  4979.8  332.37
  4989.2  325.96  4989.7  325.46  5005.4  325.96  5010.2  330.71    5023   332.4
  5064.3  331.19  5165.7  332.08  5277.3   333.2  5529.7  334.27  5958.5  338.26
  5989.4  337.47  6007.4  338.74  6331.9   343.2  6592.4  348.07  6855.2  354.19
#Mann= 10 ,-1 , 0
  3899.8    .035       0  3942.2     .07       0  4237.9      .1       0
  4989.2     .05       0  5005.4      .1       0  5165.7     .12       0
  5277.3     .05       0  5529.7     .07       0  6331.9     .05       0
  6592.4     .12       0
Bank Sta=4989.2,5005.4
XS Rating Curve= 0 ,0
Exp/Cntr=0.3,0.1

Type RM Length L Ch R = 1 ,19222   ,463,463,463
BEGIN DESCRIPTION:
Little Fivemile Creek 27.0
END DESCRIPTION:
XS GIS Cut Line= 3
        2541775.       13812475.        2541225.       13813075.
        2539425.       13813675.
#Sta/Elev= 30
  4177.7  346.45  4241.5  346.32  4290.8  344.39  4298.2  342.53  4361.8  343.27
  4493.5  339.23  4530.3  339.17    4659  337.72  4807.6  330.93  4899.5  329.93
  4956.2  331.43  4984.5  326.73  4988.2  330.29  5002.2  331.64  5012.7  329.71
    5015  324.92  5015.5  324.42  5031.5  324.92  5033.8  329.66  5044.3  327.74
    5076  332.81  5149.7  330.43  5219.4   333.1  5307.9   335.1  5961.4  335.75
  6271.6  338.13  6617.6  345.43    6694  346.86  6805.2  348.81    6889  351.25
#Mann= 10 ,-1 , 0
  4177.7      .1       0  4493.5     .07       0  4530.3      .1       0
    5015     .05       0  5031.5      .1       0  5219.4     .05       0
  6271.6     .07       0  6617.6     .05       0    6694     .07       0
  6805.2     .12       0
Bank Sta=5015,5031.5
XS Rating Curve= 0 ,0
Exp/Cntr=0.3,0.1

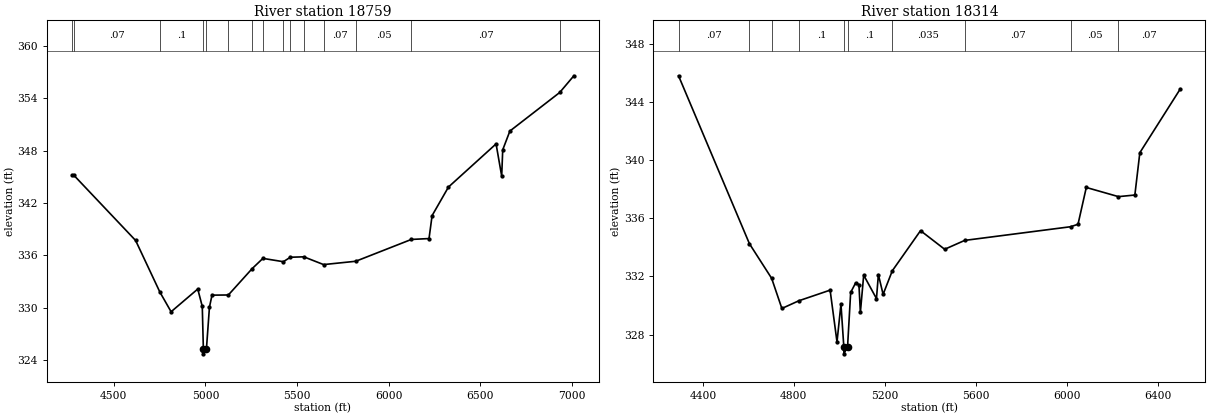
Type RM Length L Ch R = 1 ,18759   ,445,445,445
BEGIN DESCRIPTION:
Little Fivemile Creek 26.0
END DESCRIPTION:
XS GIS Cut Line= 3
      2541674.95     13812525.01        2540975.       13812725.
      2539175.02     13813624.99
#Sta/Elev= 30
  4271.8  345.19  4279.7  345.22  4618.9  337.71  4751.4   331.8  4812.6  329.55
  4958.2  332.15  4982.9  330.16  4988.9  325.23  4989.4  324.73  5005.4  325.23
  5022.1  330.08  5036.1  331.45  5125.4  331.47  5255.4  334.49    5314  335.66
  5425.7  335.28  5463.8  335.79  5537.3  335.84  5645.5  334.95  5820.9  335.33
  6124.8  337.83  6221.2  337.93    6238  340.56  6327.4  343.83  6587.4  348.77
  6618.1  345.08  6623.7  348.09  6662.8  350.24  6935.1  354.66  7012.2  356.57
#Mann= 15 ,-1 , 0
  4271.8      .1       0  4279.7     .07       0  4751.4      .1       0
  4988.9     .05       0  5005.4      .1       0  5125.4    .035       0
  5255.4     .05       0    5314     .07       0  5425.7    .035       0
  5463.8     .07       0  5537.3    .035       0  5645.5     .07       0
  5820.9     .05       0  6124.8     .07       0  6935.1     .12       0
Bank Sta=4988.9,5005.4
XS Rating Curve= 0 ,0
Exp/Cntr=0.3,0.1

Type RM Length L Ch R = 1 ,18314   ,886,886,886
BEGIN DESCRIPTION:
Little Fivemile Creek 25.0
END DESCRIPTION:
XS GIS Cut Line= 3
      2541624.98       13812475.        2540925.       13812375.
      2539724.99     13813275.01
#Sta/Elev= 30
  4293.2   345.8  4605.1  334.25  4702.8  331.87  4747.7   329.8  4822.5  330.33
  4959.9  331.06  4990.2   327.5  5007.6   330.1  5020.1  327.18  5020.6  326.68
  5036.7  327.18  5050.3   330.9  5072.2  331.56  5086.7  331.44    5093  329.53
  5107.6  332.09  5163.8  330.48  5172.2  332.13    5193  330.77  5233.4  332.39
  5357.6  335.15  5463.8  333.87  5551.9  334.48  6017.6  335.42  6050.3  335.59
  6086.7  338.12  6228.1  337.49  6300.3   337.6  6322.2  340.51  6500.3   344.9
#Mann= 10 ,-1 , 0
  4293.2     .07       0  4605.1      .1       0  4702.8     .07       0
  4822.5      .1       0  5020.1     .05       0  5036.7      .1       0
  5233.4    .035       0  5551.9     .07       0  6017.6     .05       0
  6228.1     .07       0
Bank Sta=5020.1,5036.7
XS Rating Curve= 0 ,0
Exp/Cntr=0.3,0.1