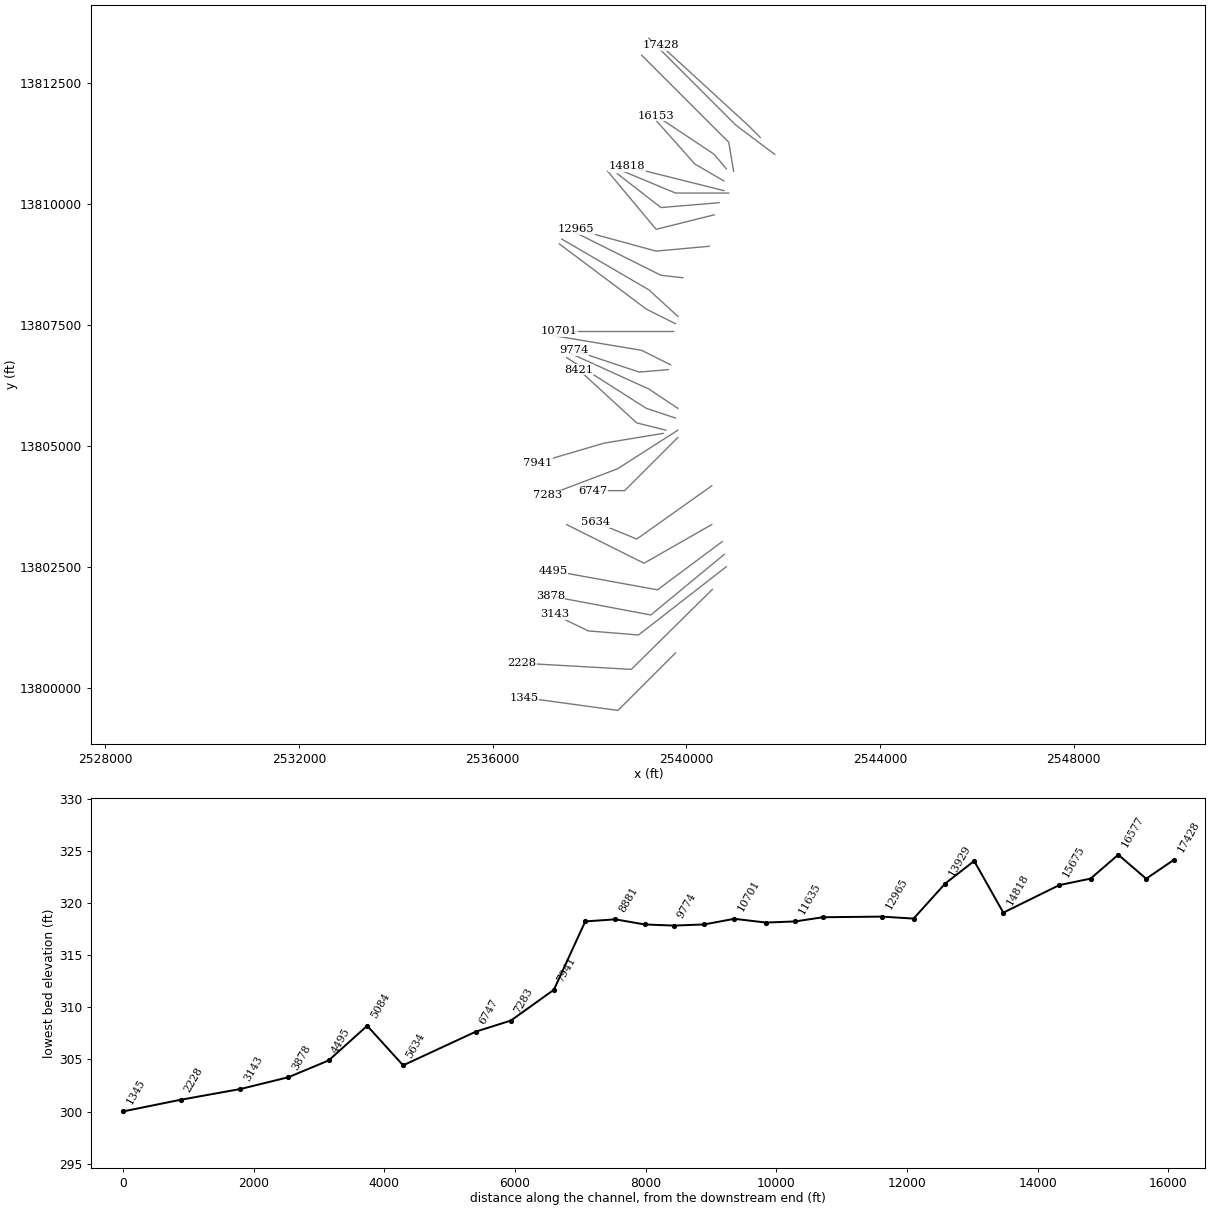
HEC-RAS study Little Fivemile Creek.prj: Little Fivemile Creek Base Level Engineering

--- Little Fivemile Creek.g01 (geometry) --- (continued)

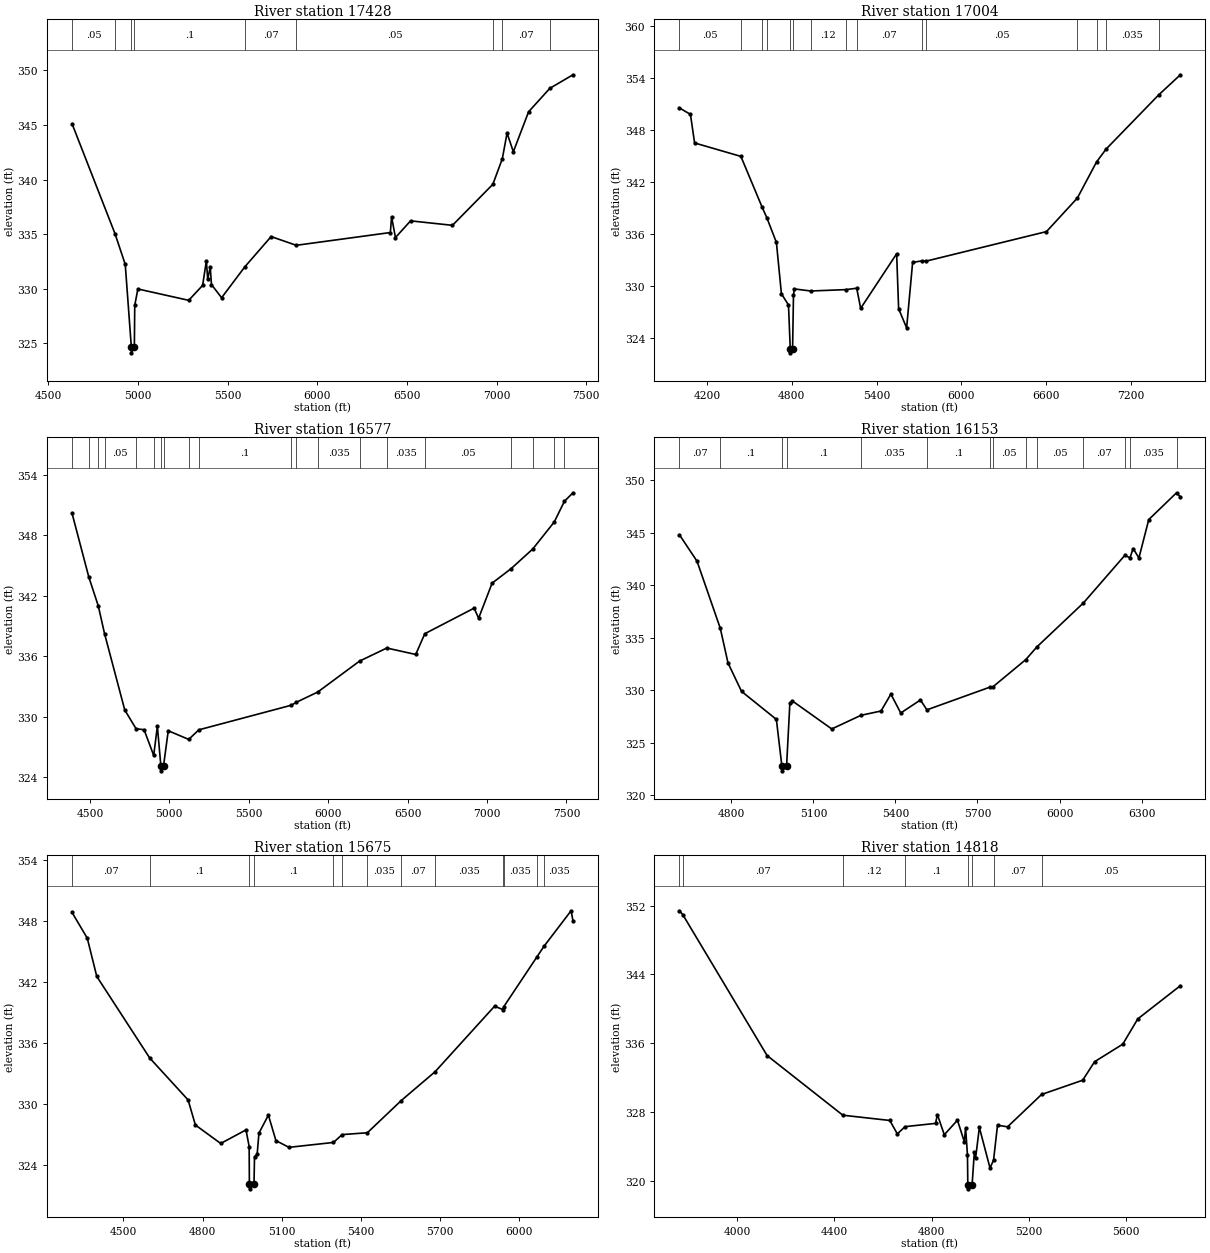
Type RM Length L Ch R = 1 ,17428   ,424,424,424
BEGIN DESCRIPTION:
Little Fivemile Creek 24.0
END DESCRIPTION:
XS GIS Cut Line= 3
        2541525.       13811375.        2541275.       13811625.
      2539474.98     13813275.02
#Sta/Elev= 30
  4631.3  345.12  4871.2  335.04  4928.3  332.23  4962.4  324.63  4962.9  324.13
  4979.1  324.63  4981.3  328.48  4998.7  329.98  5282.4  328.94  5360.1  330.31
    5381  332.56  5388.4  330.88  5402.6  331.99  5409.4  330.38  5466.1  329.18
  5595.2     332  5742.4  334.78  5882.6  333.98  6407.7  335.15  6414.5  336.59
  6436.1  334.69  6520.5  336.22  6754.2  335.81  6979.7  339.57  7032.5  341.91
  7058.9  344.26    7094  342.55  7179.1  346.21  7297.7  348.36  7426.7   349.6
#Mann= 9 ,-1 , 0
  4631.3     .05       0  4871.2      .1       0  4962.4     .05       0
  4979.1      .1       0  5595.2     .07       0  5882.6     .05       0
  6979.7    .035       0  7032.5     .07       0  7297.7    .035       0
Bank Sta=4962.4,4979.1
XS Rating Curve= 0 ,0
Exp/Cntr=0.3,0.1

Type RM Length L Ch R = 1 ,17004   ,427,427,427
BEGIN DESCRIPTION:
Little Fivemile Creek 23.0
END DESCRIPTION:
XS GIS Cut Line= 3
      2541824.98     13811025.01        2541025.       13811625.
      2539224.97     13813425.03
#Sta/Elev= 30
  4004.4  350.56  4082.5  349.81  4111.7  346.52  4439.4  344.97  4587.8  339.19
  4623.7  337.87  4690.8  335.05  4726.3  329.13  4776.3  327.84  4788.7  322.82
  4789.2  322.32  4805.4  322.82  4811.7  328.98  4817.9  329.69  4933.4  329.45
  5183.6  329.61  5259.2  329.77  5287.2  327.45  5541.8  333.74  5555.9   327.4
  5612.5   325.2  5654.9  332.74  5722.1  332.93  5752.2   332.9  6602.4   336.3
    6821  340.17  6956.4  344.32  7024.1  345.81  7397.2  352.07    7550  354.38
#Mann= 15 ,-1 , 0
  4004.4     .05       0  4439.4    .035       0  4587.8     .05       0
  4623.7      .1       0  4788.7     .05       0  4805.4      .1       0
  4933.4     .12       0  5183.6      .1       0  5259.2     .07       0
  5722.1      .1       0  5752.2     .05       0    6821    .035       0
  6956.4     .07       0  7024.1    .035       0  7397.2     .07       0
Bank Sta=4788.7,4805.4
XS Rating Curve= 0 ,0
Exp/Cntr=0.3,0.1

Type RM Length L Ch R = 1 ,16577   ,424,424,424
BEGIN DESCRIPTION:
Little Fivemile Creek 22.0
END DESCRIPTION:
XS GIS Cut Line= 3
        2540975.     13810674.98        2540875.       13811275.
      2539074.98     13813075.02
#Sta/Elev= 30
  4387.5  350.19  4492.7  343.88    4553  340.98    4592  338.25  4719.5  330.66
  4790.6   328.8  4841.2   328.7  4901.7  326.15  4924.8  329.04  4946.8  325.12
  4947.3  324.62  4963.7  325.12  4993.3   328.6  5122.2  327.74  5185.8  328.69
  5767.6  331.13    5799  331.42  5934.4  332.44  6197.5  335.51  6369.3  336.81
  6551.4  336.17  6608.5  338.23  6919.1  340.77  6947.4  339.77  7032.3  343.25
  7152.8   344.7  7288.2  346.64  7423.5  349.32  7487.4  351.37  7541.4  352.22
#Mann= 20 ,-1 , 0
  4387.5     .05       0  4492.7     .05       0    4553     .07       0
    4592     .05       0  4790.6      .1       0  4901.7    .035       0
  4946.8    .035       0  4963.7    .035       0  5122.2     .12       0
  5185.8      .1       0  5767.6     .07       0    5799    .035       0
  5934.4    .035       0  6197.5     .05       0  6369.3    .035       0
  6608.5     .05       0  7152.8    .035       0  7288.2     .05       0
  7423.5     .07       0  7487.4    .035       0
Bank Sta=4946.8,4963.7
XS Rating Curve= 0 ,0
Exp/Cntr=0.3,0.1

Type RM Length L Ch R = 1 ,16153   ,478,478,478
BEGIN DESCRIPTION:
Little Fivemile Creek 21.0
END DESCRIPTION:
XS GIS Cut Line= 3
        2540825.     13810724.99        2540575.       13811025.
      2539375.03     13811824.98
#Sta/Elev= 30
  4609.5  344.82  4673.9   342.3  4759.1   335.9  4787.2  332.61  4836.7   329.9
  4964.2  327.23  4984.1  322.83  4984.6  322.33  5001.6  322.83  5013.5  328.75
  5022.6  328.99  5166.8  326.32  5273.7  327.62  5347.1  328.03  5383.1  329.64
  5419.2  327.84  5491.3  329.08  5514.9  328.14  5747.2  330.32  5756.2  330.33
  5876.8  332.93  5917.4  334.14  6087.7  338.33  6238.7  342.85  6257.9  342.63
  6269.5  343.51  6290.5  342.61  6326.6  346.27  6428.2  348.82  6442.2  348.42
#Mann= 14 ,-1 , 0
  4609.5     .07       0  4759.1      .1       0  4984.1     .05       0
  5001.6      .1       0  5273.7    .035       0  5514.9      .1       0
  5747.2     .07       0  5756.2     .05       0  5876.8     .07       0
  5917.4     .05       0  6087.7     .07       0  6238.7     .05       0
  6257.9    .035       0  6428.2     .12       0
Bank Sta=4984.1,5001.6
XS Rating Curve= 0 ,0
Exp/Cntr=0.3,0.1

Type RM Length L Ch R = 1 ,15675   ,857,857,857
BEGIN DESCRIPTION:
Little Fivemile Creek 20.0
END DESCRIPTION:
XS GIS Cut Line= 3
      2540774.96     13810475.02        2540175.       13810825.
      2539375.02     13811724.97
#Sta/Elev= 30
  4305.4  348.82  4363.2  346.29  4399.2  342.54  4599.9  334.54  4745.3  330.43
    4773  327.97  4868.9  326.16  4964.8  327.49  4976.8  325.86  4977.6  322.21
  4978.1  321.71  4995.1  322.21  4997.1  324.86  5007.1   325.1  5013.8  327.17
  5049.7  328.94  5078.2  326.44  5127.5  325.78  5296.3  326.26  5329.2  327.03
  5424.8  327.21  5553.3  330.37  5681.7   333.2  5906.9  339.62  5938.7  339.29
  5941.5  339.56  6067.1  344.44  6094.6  345.51    6197  348.98  6204.1     348
#Mann= 13 ,-1 , 0
  4305.4     .07       0  4599.9      .1       0  4977.6     .05       0
  4995.1      .1       0  5296.3    .035       0  5329.2     .07       0
  5424.8    .035       0  5553.3     .07       0  5681.7    .035       0
  5938.7     .05       0  5941.5    .035       0  6067.1     .05       0
  6094.6    .035       0
Bank Sta=4977.6,4995.1
XS Rating Curve= 0 ,0
Exp/Cntr=0.3,0.1

Type RM Length L Ch R = 1 ,14818   ,446,446,446
BEGIN DESCRIPTION:
Little Fivemile Creek 19.0
END DESCRIPTION:
XS GIS Cut Line= 3
      2540774.95     13810275.01        2539575.       13810575.
      2538775.01       13810775.
#Sta/Elev= 30
    3762   351.4  3775.6  350.96  4122.7  334.57  4434.5  327.63  4627.8  327.02
  4658.7  325.46  4690.6   326.3  4815.9  326.68  4823.7   327.7    4852  325.36
  4906.1  327.05  4934.5  324.54  4939.6  326.15  4947.3  323.04  4948.8  319.57
  4949.3  319.07  4966.5  319.57  4975.7  323.34  4980.8  322.64  4996.3  326.21
  5040.1  321.49  5054.8  322.41    5071  326.47  5112.3  326.28  5252.3  330.04
  5421.5   331.7  5470.5  333.85  5586.4  335.89  5648.3  338.83  5823.5  342.69
#Mann= 8 ,-1 , 0
    3762     .05       0  3775.6     .07       0  4434.5     .12       0
  4690.6      .1       0  4948.8     .05       0  4966.5      .1       0
  5054.8     .07       0  5252.3     .05       0
Bank Sta=4948.8,4966.5
XS Rating Curve= 0 ,0
Exp/Cntr=0.3,0.1

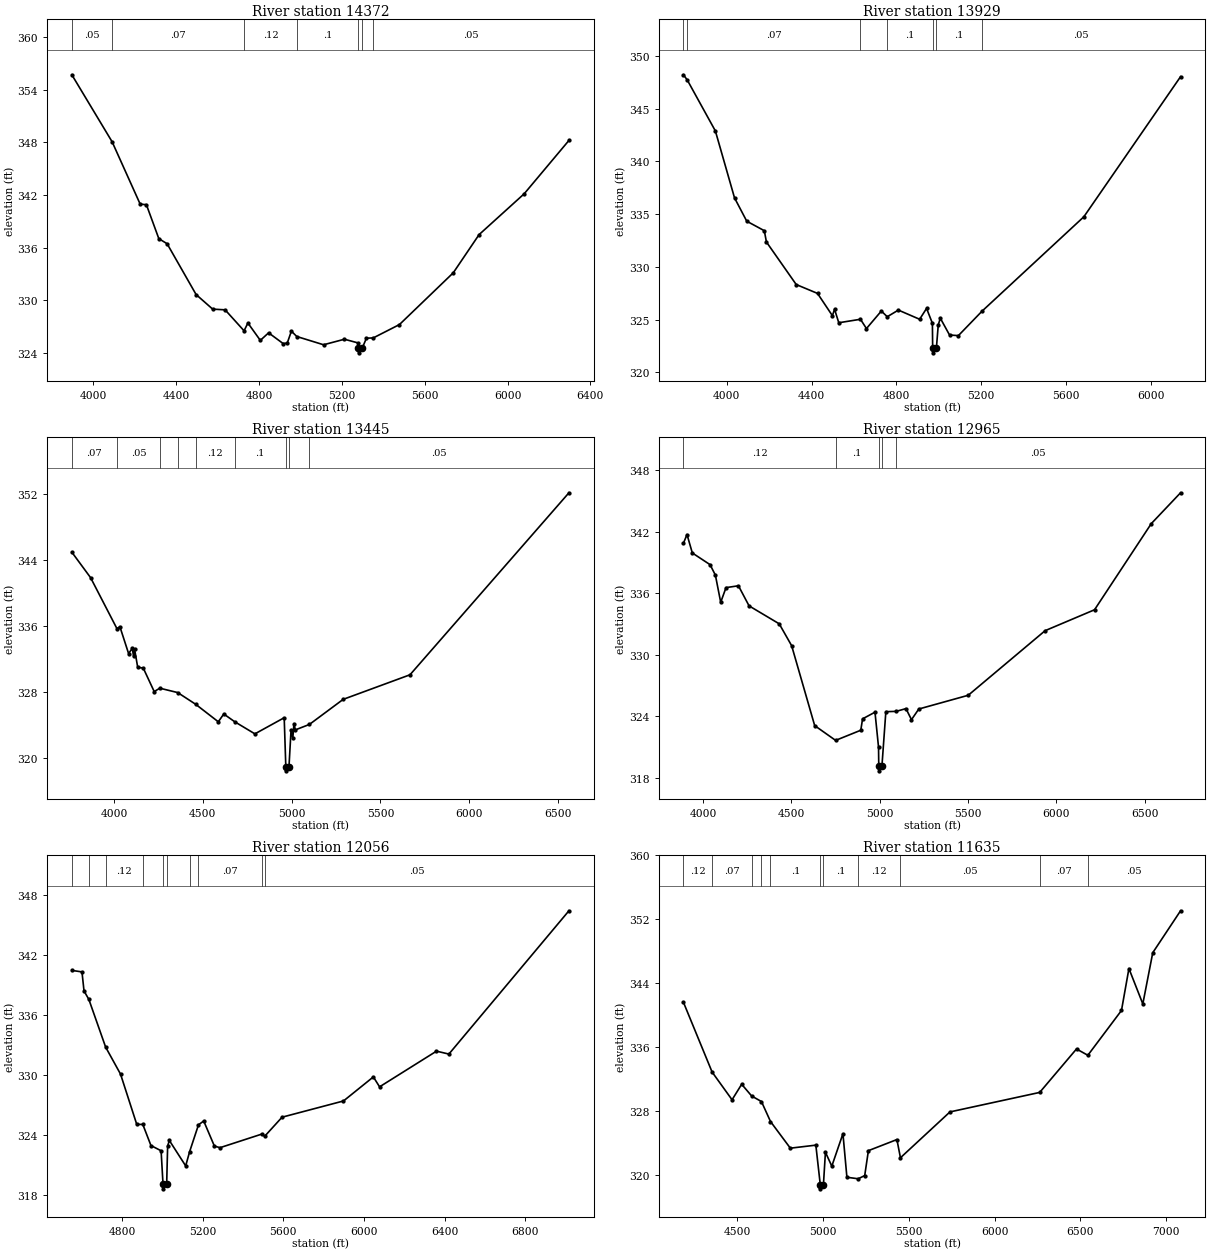
Type RM Length L Ch R = 1 ,14372   ,443,443,443
BEGIN DESCRIPTION:
Little Fivemile Creek 18.0
END DESCRIPTION:
XS GIS Cut Line= 3
      2540875.03       13810225.        2539775.       13810225.
      2538575.03     13810724.99
#Sta/Elev= 30
  3896.3   355.7  4090.9  348.06  4226.3  340.96  4256.3   340.9  4316.3  337.03
  4356.3  336.45  4496.3  330.66  4576.3     329  4636.3  328.92  4727.9  326.53
  4746.3  327.42  4806.3  325.44  4846.3   326.3  4916.3  325.08  4936.3  325.13
  4956.3  326.49  4982.4  325.88  5111.7  324.94  5212.5  325.57    5278  325.15
    5280  324.52  5280.5  324.02  5297.7  324.52  5318.6  325.69  5351.5  325.72
  5477.9  327.24  5737.9  333.14  5862.5  337.49  6080.2  342.14  6296.3  348.22
#Mann= 7 ,-1 , 0
  3896.3     .05       0  4090.9     .07       0  4727.9     .12       0
  4982.4      .1       0    5280     .05       0  5297.7      .1       0
  5351.5     .05       0
Bank Sta=5280,5297.7
XS Rating Curve= 0 ,0
Exp/Cntr=0.3,0.1

Type RM Length L Ch R = 1 ,13929   ,484,484,484
BEGIN DESCRIPTION:
Little Fivemile Creek 17.0
END DESCRIPTION:
XS GIS Cut Line= 3
      2540674.99       13810025.        2539475.       13809925.
      2538575.02     13810624.98
#Sta/Elev= 30
  3795.6   348.2  3813.7   347.7  3946.1  342.88  4036.4  336.54  4094.1  334.33
  4176.9  333.43  4186.9  332.36  4327.4  328.33  4427.8  327.49    4498  325.38
  4508.1  325.99  4528.1  324.71  4630.3  325.04  4658.6  324.16  4728.8  325.82
  4756.7  325.28  4809.1  325.91  4909.4  325.04  4942.1  326.07  4969.6  324.66
  4970.8  322.36  4971.3  321.86  4988.6  322.36  4997.2   324.5    5007  325.14
  5050.4  323.55  5092.1  323.49  5203.3   325.8  5683.9  334.75  6139.9  348.02
#Mann= 7 ,-1 , 0
  3795.6     .05       0  3813.7     .07       0  4630.3     .12       0
  4756.7      .1       0  4970.8     .05       0  4988.6      .1       0
  5203.3     .05       0
Bank Sta=4970.8,4988.6
XS Rating Curve= 0 ,0
Exp/Cntr=0.3,0.1

Type RM Length L Ch R = 1 ,13445   ,480,480,480
BEGIN DESCRIPTION:
Little Fivemile Creek 16.0
END DESCRIPTION:
XS GIS Cut Line= 3
      2540574.96     13809774.99        2539375.       13809475.
      2538375.03     13810674.97
#Sta/Elev= 30
  3762.5  344.93  3868.1  341.85  4016.7  335.68    4033  335.93    4082  332.68
  4102.6   333.3  4110.3  332.35  4115.5  333.23  4133.5     331  4164.5  330.93
  4226.3  328.08  4257.8  328.49  4358.6  327.96  4459.4  326.55  4587.1  324.43
    4618  325.37  4679.2  324.44  4793.2  322.97  4958.2  324.92  4967.3     319
  4967.8   318.5  4985.1     319  4996.8  323.44  5006.6  322.42  5013.1  324.21
  5020.9  323.45  5100.2  324.11  5290.3  327.14  5666.5  330.11  6561.4  352.11
#Mann= 9 ,-1 , 0
  3762.5     .07       0  4016.7     .05       0  4257.8      .1       0
  4358.6     .05       0  4459.4     .12       0  4679.2      .1       0
  4967.3     .05       0  4985.1      .1       0  5100.2     .05       0
Bank Sta=4967.3,4985.1
XS Rating Curve= 0 ,0
Exp/Cntr=0.3,0.1

Type RM Length L Ch R = 1 ,12965   ,909,909,909
BEGIN DESCRIPTION:
Little Fivemile Creek 15.0
END DESCRIPTION:
XS GIS Cut Line= 3
      2540475.02       13809125.        2539375.       13809025.
      2537725.02     13809474.99
#Sta/Elev= 30
  3889.3  340.89  3909.4  341.74  3939.5  339.94  4039.9   338.8  4070.1  337.78
  4100.2  335.13  4130.3  336.56  4200.6  336.74  4260.8  334.78  4431.5  333.03
  4501.8   330.9  4632.4   323.1  4750.9  321.66  4893.4  322.65  4903.5  323.76
  4973.8  324.41  4993.9     321  4995.2  319.19  4995.7  318.69  5013.3  319.19
  5035.3  324.46  5093.7  324.49  5149.3  324.76  5180.4  323.68  5221.9  324.72
  5501.8  326.06  5937.1  332.36    6217   334.4  6538.3   342.8  6704.1  345.81
#Mann= 5 ,-1 , 0
  3889.3     .12       0  4750.9      .1       0  4995.2     .05       0
  5013.3      .1       0  5093.7     .05       0
Bank Sta=4995.2,5013.3
XS Rating Curve= 0 ,0
Exp/Cntr=0.3,0.1

Type RM Length L Ch R = 1 ,12056   ,421,421,421
BEGIN DESCRIPTION:
Little Fivemile Creek 14.0
END DESCRIPTION:
XS GIS Cut Line= 3
        2539925.       13808475.        2539475.       13808525.
      2537675.03     13809424.98
#Sta/Elev= 30
  4551.8  340.43  4602.1  340.28  4612.2  338.38  4636.3  337.53  4719.5  332.77
  4793.3  330.08  4873.8  325.06  4903.7  325.06  4944.2  322.95  4994.5  322.43
  5003.9  319.13  5004.4  318.63  5022.1  319.13  5026.9   322.9  5035.3  323.46
  5116.4  320.92  5136.1  322.35  5179.9  325.02  5205.8   325.4  5258.9  322.89
  5286.9  322.74  5494.8   324.1  5508.4  323.88  5594.3  325.78    5899   327.4
  6047.1   329.8  6077.9  328.81  6360.2  332.37  6421.7  332.08    7017  346.38
#Mann= 10 ,-1 , 0
  4551.8     .12       0  4636.3     .07       0  4719.5     .12       0
  4903.7      .1       0  5003.9     .05       0  5022.1      .1       0
  5136.1     .05       0  5179.9     .07       0  5494.8     .12       0
  5508.4     .05       0
Bank Sta=5003.9,5022.1
XS Rating Curve= 0 ,0
Exp/Cntr=0.3,0.1

Type RM Length L Ch R = 1 ,11635   ,448,448,448
BEGIN DESCRIPTION:
Little Fivemile Creek 13.0
END DESCRIPTION:
XS GIS Cut Line= 3
      2539824.98     13807675.02        2539225.       13808225.
      2537424.98     13809275.01
#Sta/Elev= 30
  4186.3  341.58  4353.3  332.85  4469.6  329.38  4525.7  331.32    4584  329.85
  4640.9  329.16  4693.7  326.66  4809.4  323.32    4958   323.7    4984  318.73
  4984.5  318.23  5002.2  318.73  5013.9  322.81  5051.1  321.07    5116  325.13
  5139.1  319.68  5204.9  319.49  5242.9  319.89  5264.4  323.01  5430.6   324.4
  5451.2  322.12  5739.9  327.86  6262.9   330.3  6477.5  335.74  6543.6  334.95
  6739.7  340.56  6783.1  345.81  6864.1  341.38    6922  347.79  7084.1  353.04
#Mann= 11 ,-1 , 0
  4186.3     .12       0  4353.3     .07       0    4584      .1       0
  4640.9     .07       0  4693.7      .1       0    4984     .05       0
  5002.2      .1       0  5204.9     .12       0  5451.2     .05       0
  6262.9     .07       0  6543.6     .05       0
Bank Sta=4984,5002.2
XS Rating Curve= 0 ,0
Exp/Cntr=0.3,0.1

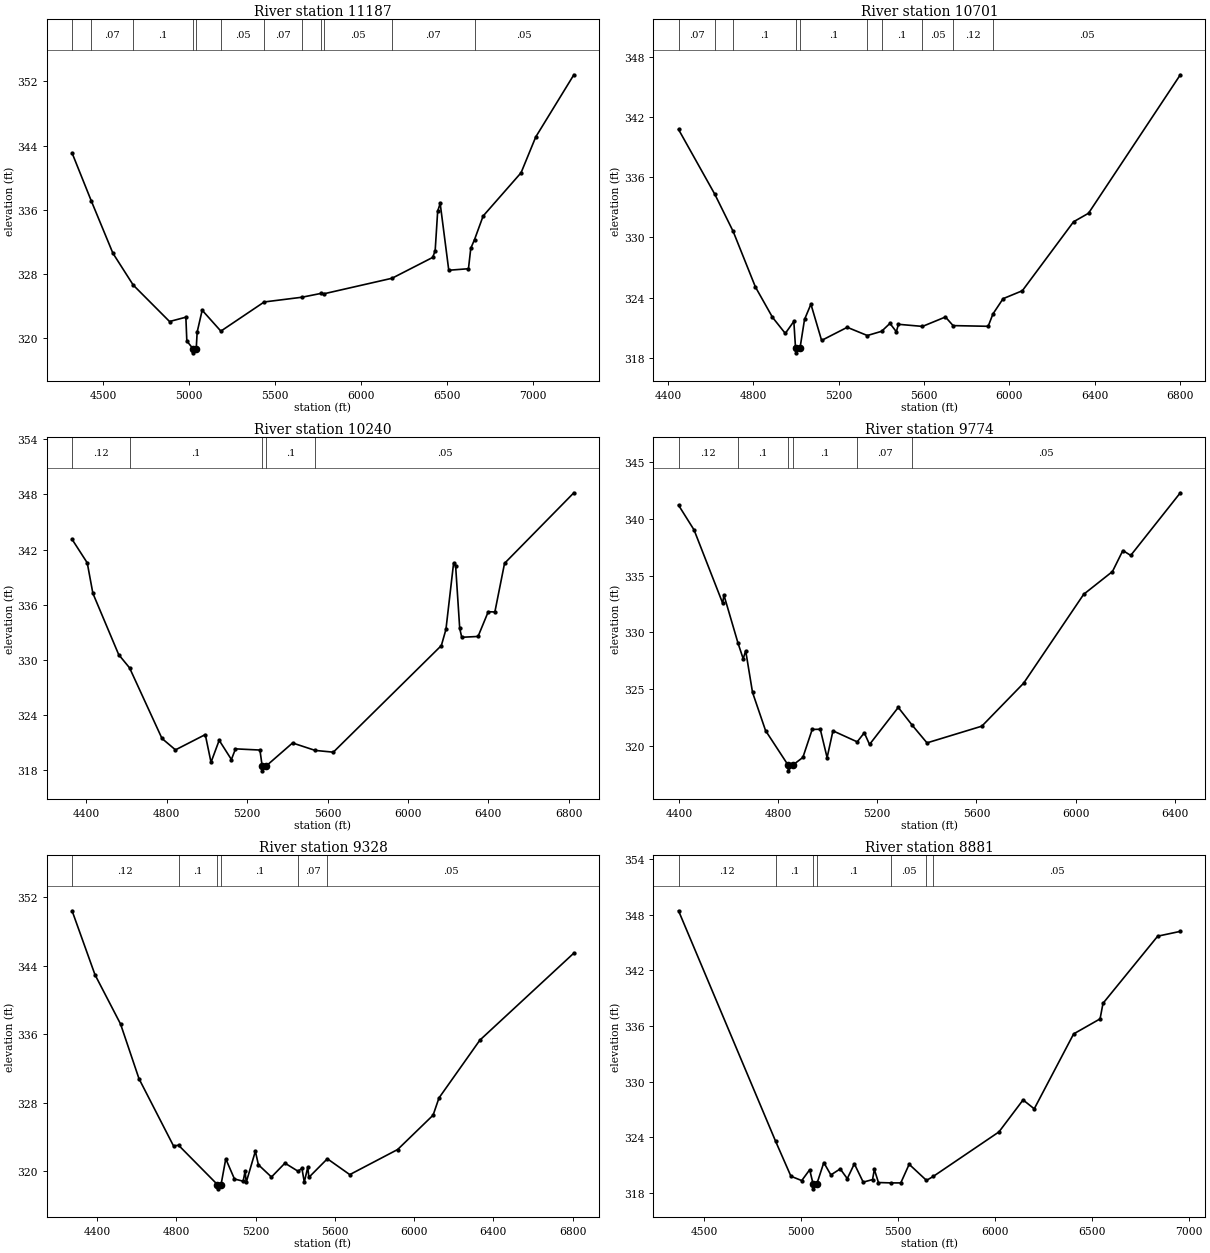
Type RM Length L Ch R = 1 ,11187   ,486,486,486
BEGIN DESCRIPTION:
Little Fivemile Creek 12.0
END DESCRIPTION:
XS GIS Cut Line= 3
      2539775.01       13807525.        2539175.       13807825.
      2537375.02     13809174.98
#Sta/Elev= 30
  4318.7  343.07  4429.9  337.12  4556.3  330.56  4674.7  326.58  4886.1  322.03
  4981.1  322.57  4986.7   319.6  5023.1  318.62  5023.6  318.12  5041.4  318.62
  5046.8  320.71    5076  323.44  5184.8  320.83  5437.1  324.47  5656.4  325.06
  5765.7  325.53  5786.6   325.5  6181.1  327.43  6417.7  330.03  6432.2  330.87
  6446.8  335.81  6461.4  336.77  6511.4  328.43    6626  328.62  6639.5  331.17
  6661.2  332.25  6711.4   335.2  6932.2   340.6  7017.7  345.07  7239.5  352.83
#Mann= 12 ,-1 , 0
  4318.7    .035       0  4429.9     .07       0  4674.7      .1       0
  5023.1     .05       0  5041.4      .1       0  5184.8     .05       0
  5437.1     .07       0  5656.4     .05       0  5765.7     .07       0
  5786.6     .05       0  6181.1     .07       0  6661.2     .05       0
Bank Sta=5023.1,5041.4
XS Rating Curve= 0 ,0
Exp/Cntr=0.3,0.1

Type RM Length L Ch R = 1 ,10701   ,461,461,461
BEGIN DESCRIPTION:
Little Fivemile Creek 11.0
END DESCRIPTION:
XS GIS Cut Line= 3
      2539724.98       13807375.        2539175.       13807375.
      2537374.98       13807375.
#Sta/Elev= 30
  4450.1  340.79  4619.7  334.33  4706.1   330.6  4810.1  325.06  4890.1  322.03
  4950.1  320.42  4990.1  321.62  4997.6   319.1  5000.9  318.98  5001.4  318.48
  5019.2  318.98  5040.1  321.81  5070.1  323.34  5120.1  319.72  5240.1  321.03
  5334.2  320.21  5401.1  320.63  5440.1  321.42  5470.1  320.59  5480.1  321.33
  5592.6  321.12  5700.1  322.06  5735.9   321.2  5900.1  321.13  5922.7  322.37
  5970.1  323.89  6060.1  324.68  6300.1  331.57  6370.1  332.42  6800.1  346.25
#Mann= 10 ,-1 , 0
  4450.1     .07       0  4619.7     .12       0  4706.1      .1       0
  5000.9     .05       0  5019.2      .1       0  5334.2     .12       0
  5401.1      .1       0  5592.6     .05       0  5735.9     .12       0
  5922.7     .05       0
Bank Sta=5000.9,5019.2
XS Rating Curve= 0 ,0
Exp/Cntr=0.3,0.1

Type RM Length L Ch R = 1 ,10240   ,466,466,466
BEGIN DESCRIPTION:
Little Fivemile Creek 10.0
END DESCRIPTION:
XS GIS Cut Line= 3
      2539675.03     13806674.98        2539075.       13806975.
      2537274.98       13807275.
#Sta/Elev= 30
  4329.5  343.11    4405  340.55    4433  337.24  4561.5  330.57  4615.3  329.14
  4776.7  321.46  4843.8  320.22    4992  321.88  5020.6  318.87  5061.2  321.26
    5122  319.17  5142.3  320.33  5263.9   320.2  5275.1  318.44  5275.6  317.94
  5293.4  318.44  5426.1  320.97  5538.7  320.16  5628.9  319.97  6166.2  331.56
    6189  333.32    6227  340.51  6237.2   340.2  6257.5  333.42  6267.6  332.46
  6348.7  332.55  6399.4  335.24  6432.3  335.21  6480.5   340.5  6825.2  348.17
#Mann= 5 ,-1 , 0
  4329.5     .12       0  4615.3      .1       0  5275.1     .05       0
  5293.4      .1       0  5538.7     .05       0
Bank Sta=5275.1,5293.4
XS Rating Curve= 0 ,0
Exp/Cntr=0.3,0.1

Type RM Length L Ch R = 1 ,9774    ,446,446,446
BEGIN DESCRIPTION:
Little Fivemile Creek 9.0
END DESCRIPTION:
XS GIS Cut Line= 3
      2539625.03       13806575.        2539025.       13806525.
      2537675.03     13806974.99
#Sta/Elev= 30
  4397.8   341.2  4460.5  339.02  4575.9  332.58    4581  333.29  4637.9  329.06
  4658.7  327.69  4668.8  328.39  4696.4  324.73    4749  321.37  4840.1  318.33
  4840.6  317.83  4858.6  318.33  4899.6  319.01  4937.2  321.47  4969.8  321.49
  4997.4  318.99    5021  321.35  5118.9  320.38  5147.5  321.18  5168.6  320.15
  5284.5  323.41  5340.6  321.85  5400.5  320.29  5621.8  321.76  5790.5  325.54
  6032.9  333.36  6148.9  335.36    6191  337.21  6222.7  336.78  6422.9  342.29
#Mann= 6 ,-1 , 0
  4397.8     .12       0  4637.9      .1       0  4840.1     .05       0
  4858.6      .1       0  5118.9     .07       0  5340.6     .05       0
Bank Sta=4840.1,4858.6
XS Rating Curve= 0 ,0
Exp/Cntr=0.3,0.1

Type RM Length L Ch R = 1 ,9328    ,447,447,447
BEGIN DESCRIPTION:
Little Fivemile Creek 8.0
END DESCRIPTION:
XS GIS Cut Line= 3
      2539824.96     13805775.03        2539225.       13806175.
      2537575.02     13806924.99
#Sta/Elev= 30
  4273.3   350.4  4388.9  342.94  4518.1  337.18  4611.3  330.79  4785.5  322.95
    4811  323.03  5007.1  318.44  5007.6  317.94  5025.6  318.44  5049.3  321.44
  5093.2  319.09  5137.2  318.83  5147.1  320.03  5152.5  318.69  5198.7  322.33
  5214.1  320.75    5280  319.32  5348.1  320.94  5414.6  319.99  5433.7  320.34
  5445.8  318.73  5463.4  320.47  5468.9  319.28  5562.2  321.45  5675.4   319.6
  5917.1  322.53  6096.1  326.54  6125.8  328.55  6332.3   335.3  6806.8  345.46
#Mann= 6 ,-1 , 0
  4273.3     .12       0    4811      .1       0  5007.1     .05       0
  5025.6      .1       0  5414.6     .07       0  5562.2     .05       0
Bank Sta=5007.1,5025.6
XS Rating Curve= 0 ,0
Exp/Cntr=0.3,0.1

Type RM Length L Ch R = 1 ,8881    ,460,460,460
BEGIN DESCRIPTION:
Little Fivemile Creek 7.0
END DESCRIPTION:
XS GIS Cut Line= 3
      2539774.99       13805575.        2539175.       13805775.
        2537525.       13806825.
#Sta/Elev= 30
  4367.2  348.42  4867.7  323.57  4946.9  319.79  5002.6  319.32  5043.7  320.49
  5061.5  318.93    5062  318.43    5080  318.93  5116.5  321.26  5152.9  319.93
  5201.1  320.58  5237.6  319.53    5274  321.13  5319.7  319.15  5367.9  319.43
  5377.2  320.52  5398.4  319.11  5464.4  319.07  5513.6  319.07  5556.7  321.08
  5646.1  319.34  5681.1  319.77  6019.9  324.57  6144.3  328.02  6201.9  327.06
  6405.1  335.14  6541.4  336.76  6556.6  338.44  6838.6  345.68  6955.4   346.2
#Mann= 7 ,-1 , 0
  4367.2     .12       0  4867.7      .1       0  5061.5     .05       0
    5080      .1       0  5464.4     .05       0  5646.1     .07       0
  5681.1     .05       0
Bank Sta=5061.5,5080
XS Rating Curve= 0 ,0
Exp/Cntr=0.3,0.1

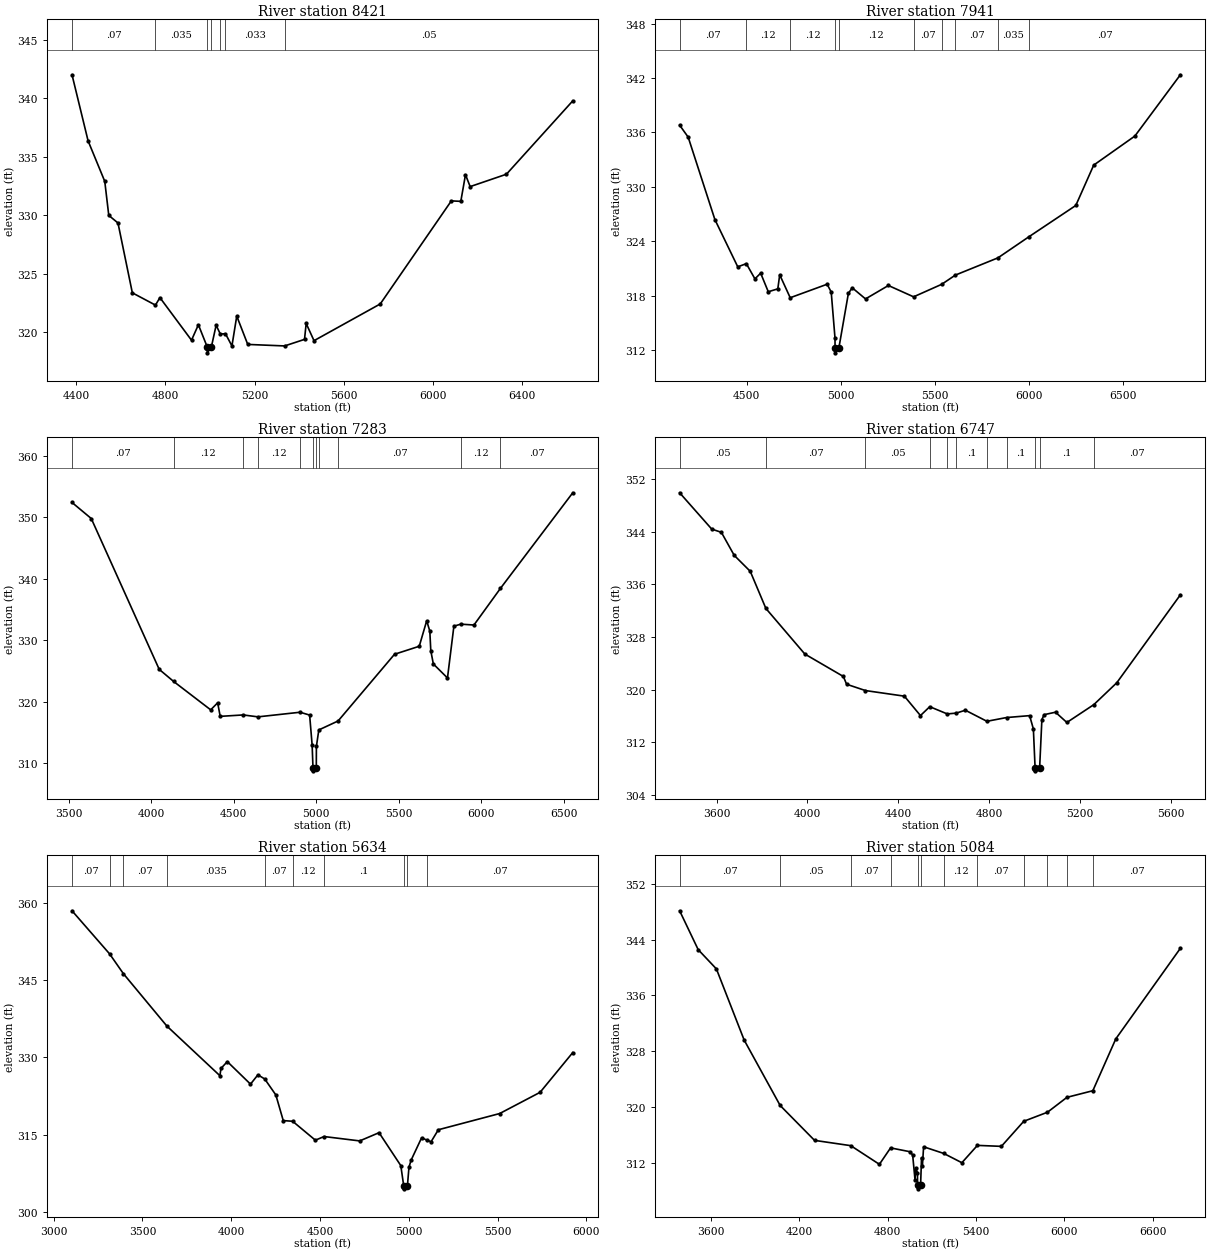
Type RM Length L Ch R = 1 ,8421    ,480,480,480
BEGIN DESCRIPTION:
Little Fivemile Creek 6.0
END DESCRIPTION:
XS GIS Cut Line= 3
        2539575.       13805325.        2538975.       13805475.
      2537775.03     13806574.97
#Sta/Elev= 30
  4381.2     342  4453.3  336.35  4528.1  332.89  4546.1  329.98  4587.4  329.33
  4651.8  323.36  4755.5  322.31  4775.5  322.95  4917.2  319.31  4948.1  320.63
  4987.8  318.73  4988.3  318.23  5006.3  318.73  5027.7  320.59  5046.4  319.84
  5069.7  319.86  5098.6  318.82  5120.2  321.37  5169.5  318.95  5334.9  318.82
  5424.2  319.38  5431.6  320.74  5466.8  319.27    5764  322.41  6082.8  331.22
  6125.3  331.18  6146.3  333.46  6167.2  332.44    6330   333.5  6627.5  339.77
#Mann= 7 ,-1 , 0
  4381.2     .07       0  4755.5    .035       0  4987.8    .035       0
  5006.3    .035       0  5046.4      .1       0  5069.7    .033       0
  5334.9     .05       0
Bank Sta=4987.8,5006.3
XS Rating Curve= 0 ,0
Exp/Cntr=0.3,0.1

Type RM Length L Ch R = 1 ,7941    ,658,658,658
BEGIN DESCRIPTION:
A19693
END DESCRIPTION:
XS GIS Cut Line= 3
       2539519.8     13805258.38      2538300.64     13805056.95
      2536933.03     13804654.09
#Sta/Elev= 30
  4143.9   336.8  4189.3  335.48  4331.2  326.39  4452.8  321.17  4498.5  321.52
  4544.1  319.84  4574.5  320.47    4615  318.42  4665.7  318.74  4675.8  320.29
  4731.6  317.76  4927.8  319.25  4949.5  318.39  4969.7   313.3  4969.9  312.18
  4970.4  311.68  4989.9  312.18  5040.7  318.23    5061  318.86  5131.9  317.63
  5253.5  319.11  5387.4  317.86  5536.6  319.24  5609.6  320.26  5835.7  322.16
  6000.5  324.49  6249.5  327.94  6344.6  332.39  6563.5   335.6  6805.3  342.36
#Mann= 10 ,-1 , 0
  4143.9     .07       0  4498.5     .12       0  4731.6     .12       0
  4969.9     .05       0  4989.9     .12       0  5387.4     .07       0
  5536.6    .035       0  5609.6     .07       0  5835.7    .035       0
  6000.5     .07       0
Bank Sta=4969.9,4989.9
XS Rating Curve= 0 ,0
Exp/Cntr=0.3,0.1

Type RM Length L Ch R = 1 ,7283    ,536,536,536
BEGIN DESCRIPTION:
Little Fivemile Creek 5.0
END DESCRIPTION:
XS GIS Cut Line= 3
      2539824.96     13805324.97        2538575.       13804525.
      2537125.04     13803975.01
#Sta/Elev= 30
  3520.2  352.42  3636.8  349.81  4048.7  325.25  4136.1  323.28  4360.7  318.66
    4403  319.81  4418.2   317.6  4557.7  317.83  4647.2  317.52  4902.3  318.27
  4960.3  317.81  4975.5  312.92  4980.6  309.23  4981.1  308.73  5000.7  309.23
  5001.3  312.71    5016  315.39  5132.9  316.85  5474.8  327.71  5624.6  329.01
  5669.8  333.16  5688.7  331.47  5694.6  328.29  5710.1  326.13  5795.7  323.85
  5834.6  332.28  5876.3  332.61  5956.1  332.47  6116.6  338.43    6555     354
#Mann= 11 ,-1 , 0
  3520.2     .07       0  4136.1     .12       0  4557.7    .035       0
  4647.2     .12       0  4902.3    .035       0  4980.6    .035       0
  5000.7    .035       0    5016      .1       0  5132.9     .07       0
  5876.3     .12       0  6116.6     .07       0
Bank Sta=4980.6,5000.7
XS Rating Curve= 0 ,0
Exp/Cntr=0.3,0.1

Type RM Length L Ch R = 1 ,6747    ,1113,1113,1113
BEGIN DESCRIPTION:
Little Fivemile Creek 4.0
END DESCRIPTION:
XS GIS Cut Line= 3
      2539824.99     13805174.99        2538725.       13804075.
      2538075.03       13804075.
#Sta/Elev= 30
    3437  349.93  3578.4  344.41  3620.8  343.92  3677.4  340.42  3748.1  337.99
  3816.9  332.35  3988.5  325.42  4158.2  322.01  4172.4  320.83  4255.6  319.87
  4426.9  319.02  4497.7  316.07  4538.7  317.42  4615.8  316.32  4654.9  316.44
  4695.6  316.88  4790.4   315.2  4876.9  315.77  4978.5  316.06  4995.1  314.04
  5002.6  308.17  5003.1  307.67  5022.7  308.17  5032.6  315.47  5042.6  316.21
  5092.6  316.58  5142.6  315.02  5261.3  317.73  5362.6  321.06  5642.6  334.42
#Mann= 11 ,-1 , 0
    3437     .05       0  3816.9     .07       0  4255.6     .05       0
  4538.7     .12       0  4615.8     .05       0  4654.9      .1       0
  4790.4    .035       0  4876.9      .1       0  5002.6     .05       0
  5022.7      .1       0  5261.3     .07       0
Bank Sta=5002.6,5022.7
XS Rating Curve= 0 ,0
Exp/Cntr=0.3,0.1

Type RM Length L Ch R = 1 ,5634    ,550,550,550
BEGIN DESCRIPTION:
Little Fivemile Creek 2.0
END DESCRIPTION:
XS GIS Cut Line= 3
      2540524.99     13804174.99        2538975.       13803075.
      2538124.98     13803425.01
#Sta/Elev= 30
  3103.7  358.51  3315.5  350.12  3393.2  346.27    3638  336.09  3936.5  326.44
  3942.7  327.86  3978.3  329.18  4108.8   324.8  4150.6  326.61    4189   325.8
  4251.5   322.7  4293.3  317.71  4346.1  317.58  4474.1   313.9  4523.1  314.61
  4723.8  313.76  4832.7  315.36  4955.2  308.96    4972  304.94  4972.5  304.44
  4992.3  304.94  5001.3  308.67  5013.6  310.04  5072.3  314.36  5102.5  313.92
  5125.6  313.59  5166.6  315.93  5511.9  319.08  5739.7  323.21  5923.6  330.94
#Mann= 10 ,-1 , 0
  3103.7     .07       0  3315.5     .05       0  3393.2     .07       0
    3638    .035       0    4189     .07       0  4346.1     .12       0
  4523.1      .1       0    4972     .05       0  4992.3      .1       0
  5102.5     .07       0
Bank Sta=4972,4992.3
XS Rating Curve= 0 ,0
Exp/Cntr=0.3,0.1

Type RM Length L Ch R = 1 ,5084    ,589,589,589
BEGIN DESCRIPTION:
Little Fivemile Creek 1.0
END DESCRIPTION:
XS GIS Cut Line= 3
        2540525.       13803375.        2539125.       13802575.
      2537525.01       13803375.
#Sta/Elev= 30
  3387.1  348.16  3513.1  342.58  3636.9  339.81  3825.5  329.59  4069.9   320.2
  4303.5  315.19  4549.6  314.43    4744  311.75  4819.9  314.11  4954.2  313.55
    4970  313.06  4985.9  309.54  4991.6  311.24  5002.4  310.51  5003.3  308.73
  5003.8  308.23  5023.7  308.73  5030.3  312.71  5035.9  311.47  5044.3  314.27
  5181.5  313.31  5304.2  311.98  5409.8  314.47  5572.5  314.33  5724.5  317.93
  5885.6  319.23  6017.9  321.37  6193.8  322.32  6349.6  329.76  6788.4  342.77
#Mann= 12 ,-1 , 0
  3387.1     .07       0  4069.9     .05       0  4549.6     .07       0
  4819.9      .1       0  5003.3     .05       0  5023.7      .1       0
  5181.5     .12       0  5409.8     .07       0  5724.5     .05       0
  5885.6     .07       0  6017.9     .05       0  6193.8     .07       0
Bank Sta=5003.3,5023.7
XS Rating Curve= 0 ,0
Exp/Cntr=0.3,0.1

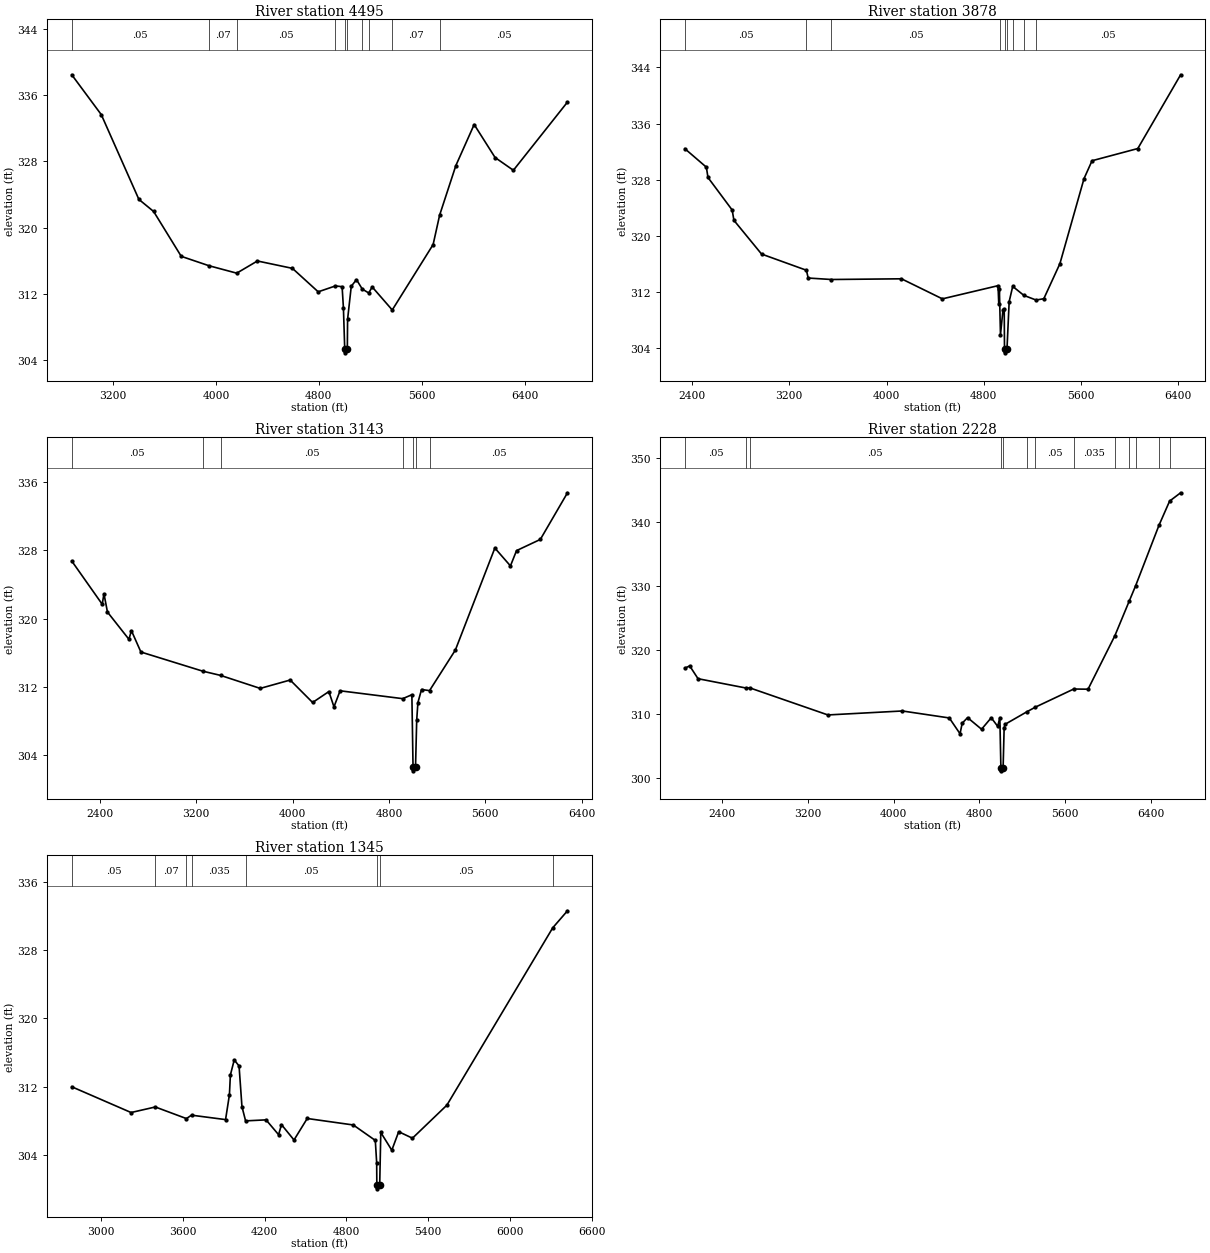
Type RM Length L Ch R = 1 ,4495    ,617,617,617
BEGIN DESCRIPTION:
A19692
END DESCRIPTION:
XS GIS Cut Line= 3
      2540738.99     13803021.42      2539403.21     13802024.88
      2537251.12     13802417.14
#Sta/Elev= 30
  2879.3  338.45  3108.9  333.64  3401.1  323.42  3515.8  321.96  3730.5  316.55
  3945.5  315.42  4161.8  314.52  4322.6  315.99  4594.9   315.1  4795.3  312.27
  4929.2  312.98  4981.1  312.89  4991.3  310.35  5001.4  305.41  5001.9  304.91
  5021.8  305.41  5023.7  308.95  5052.3  312.94  5092.9  313.74    5138   312.6
  5188.1  312.13  5214.9  312.86  5370.9  310.08  5688.7  317.97  5739.5  321.53
  5865.5   327.5  6007.8  332.45  6170.4  328.47  6312.7  326.93  6733.4  335.16
#Mann= 10 ,-1 , 0
  2879.3     .05       0  3945.5     .07       0  4161.8     .05       0
  4929.2     .12       0  5001.4     .05       0  5021.8     .12       0
    5138     .07       0  5188.1     .12       0  5370.9     .07       0
  5739.5     .05       0
Bank Sta=5001.4,5021.8
XS Rating Curve= 0 ,0
Exp/Cntr=0.3,0.1

Type RM Length L Ch R = 1 ,3878    ,735,735,735
BEGIN DESCRIPTION:
A19691
END DESCRIPTION:
XS GIS Cut Line= 3
      2540781.42      13802756.4      2539265.39      13801505.4
      2537188.71     13801897.43
#Sta/Elev= 30
  2341.1  332.41  2517.7  329.78  2530.9  328.31  2730.1  323.67  2744.4   322.2
  2971.8  317.39  3340.9  315.08  3355.5  313.97  3546.3  313.76  4122.9  313.86
  4459.7     311  4917.6  312.88  4923.6  310.29  4928.7  312.35  4937.7  305.88
  4958.3  309.43  4968.5  309.53  4970.8   303.8  4971.3   303.3  4991.2   303.8
  5009.2  310.61  5038.4  312.78  5129.7   311.5  5230.5  310.83  5294.2  311.02
  5426.5  316.01  5625.1  328.15  5691.1   330.7  6067.6  332.44    6420  342.96
#Mann= 9 ,-1 , 0
  2341.1     .05       0  3340.9     .07       0  3546.3     .05       0
  4937.7     .07       0  4970.8     .05       0  4991.2     .07       0
  5038.4     .12       0  5129.7     .07       0  5230.5     .05       0
Bank Sta=4970.8,4991.2
XS Rating Curve= 0 ,0
Exp/Cntr=0.3,0.1

Type RM Length L Ch R = 1 ,3143    ,915,915,915
BEGIN DESCRIPTION:
A19690
END DESCRIPTION:
XS GIS Cut Line= 4
      2540823.82     13802501.95      2539010.95     13801091.94
      2537971.99     13801176.75      2537272.27     13801516.01
#Sta/Elev= 30
  2166.4  326.73  2419.3  321.67  2433.7   322.9  2462.7  320.76    2641  317.57
  2661.8  318.58  2740.5  316.08  3253.4  313.84  3402.7  313.34  3731.4  311.82
  3980.2   312.8  4166.5  310.17  4301.5  311.45  4343.9  309.66  4394.6  311.54
  4914.8  310.62  4990.8  311.08  5000.4  302.67  5000.9  302.17  5021.2  302.67
  5030.9   308.1  5040.9  310.16    5071  311.69  5137.4  311.56    5352  316.31
  5679.9  328.25  5809.3  326.16    5860  327.95  6057.6  329.26  6283.1  334.72
#Mann= 7 ,-1 , 0
  2166.4     .05       0  3253.4     .07       0  3402.7     .05       0
  4914.8     .07       0  5000.4     .05       0  5021.2     .07       0
  5137.4     .05       0
Bank Sta=5000.4,5021.2
XS Rating Curve= 0 ,0
Exp/Cntr=0.3,0.1

Type RM Length L Ch R = 1 ,2228    ,883,883,883
BEGIN DESCRIPTION:
A19689
END DESCRIPTION:
XS GIS Cut Line= 3
      2540537.55     13802035.46      2538862.53     13800381.63
      2536604.41     13800508.85
#Sta/Elev= 30
  2057.6  317.18  2102.2  317.53  2179.9  315.53  2630.9  314.06  2661.6   314.1
  3389.1  309.87  4082.1  310.49  4519.2   309.4  4619.4  306.93  4639.4  308.58
  4689.5  309.45  4819.7  307.64  4909.8  309.43  4969.9  308.09  4989.9  309.46
  4999.6  301.64  5000.1  301.14  5020.4  301.64    5030  307.87    5040  308.42
  5245.5   310.4    5321  311.09  5678.1  313.92  5811.2  313.89  6061.1  322.25
  6193.5  327.61    6254  330.04  6471.8   339.5  6570.6  343.27  6673.2  344.57
#Mann= 13 ,-1 , 0
  2057.6     .05       0  2630.9     .07       0  2661.6     .05       0
  4999.6     .05       0  5020.4     .05       0  5245.5    .035       0
    5321     .05       0  5678.1    .035       0  6061.1     .05       0
  6193.5    .035       0    6254     .05       0  6471.8     .07       0
  6570.6    .035       0
Bank Sta=4999.6,5020.4
XS Rating Curve= 0 ,0
Exp/Cntr=0.3,0.1

Type RM Length L Ch R = 1 ,1345    ,0,0,0
BEGIN DESCRIPTION:
A19688
END DESCRIPTION:
XS GIS Cut Line= 3
       2539774.3     13800720.91      2538586.88      13799533.5
      2536648.35     13799798.33
#Sta/Elev= 30
  2785.4  311.99  3220.4  308.97  3398.1  309.62  3626.2  308.26  3663.6  308.66
  3913.4  308.14  3941.7  311.05  3948.7  313.37    3977  315.14  4012.4  314.43
  4033.6  309.66  4060.3  307.99  4210.4  308.11  4302.3  306.37  4323.5  307.55
  4415.4  305.75  4512.3  308.27  4850.1  307.51  5011.6   305.7  5021.7  303.08
  5022.8  300.52  5023.3  300.02  5043.9  300.52  5051.9  306.63  5132.7  304.55
  5183.2  306.72  5284.1  305.96  5536.4  309.83  6313.3  330.64  6421.2  332.63
#Mann= 8 ,-1 , 0
  2785.4     .05       0  3398.1     .07       0  3626.2     .05       0
  3663.6    .035       0  4060.3     .05       0  5022.8     .05       0
  5043.9     .05       0  6313.3    .035       0
Bank Sta=5022.8,5043.9
XS Rating Curve= 0 ,0
Exp/Cntr=0.3,0.1

Chan Stop Cuts=-1
Use User Specified Reach Order=0
Composite Channel Slope=5