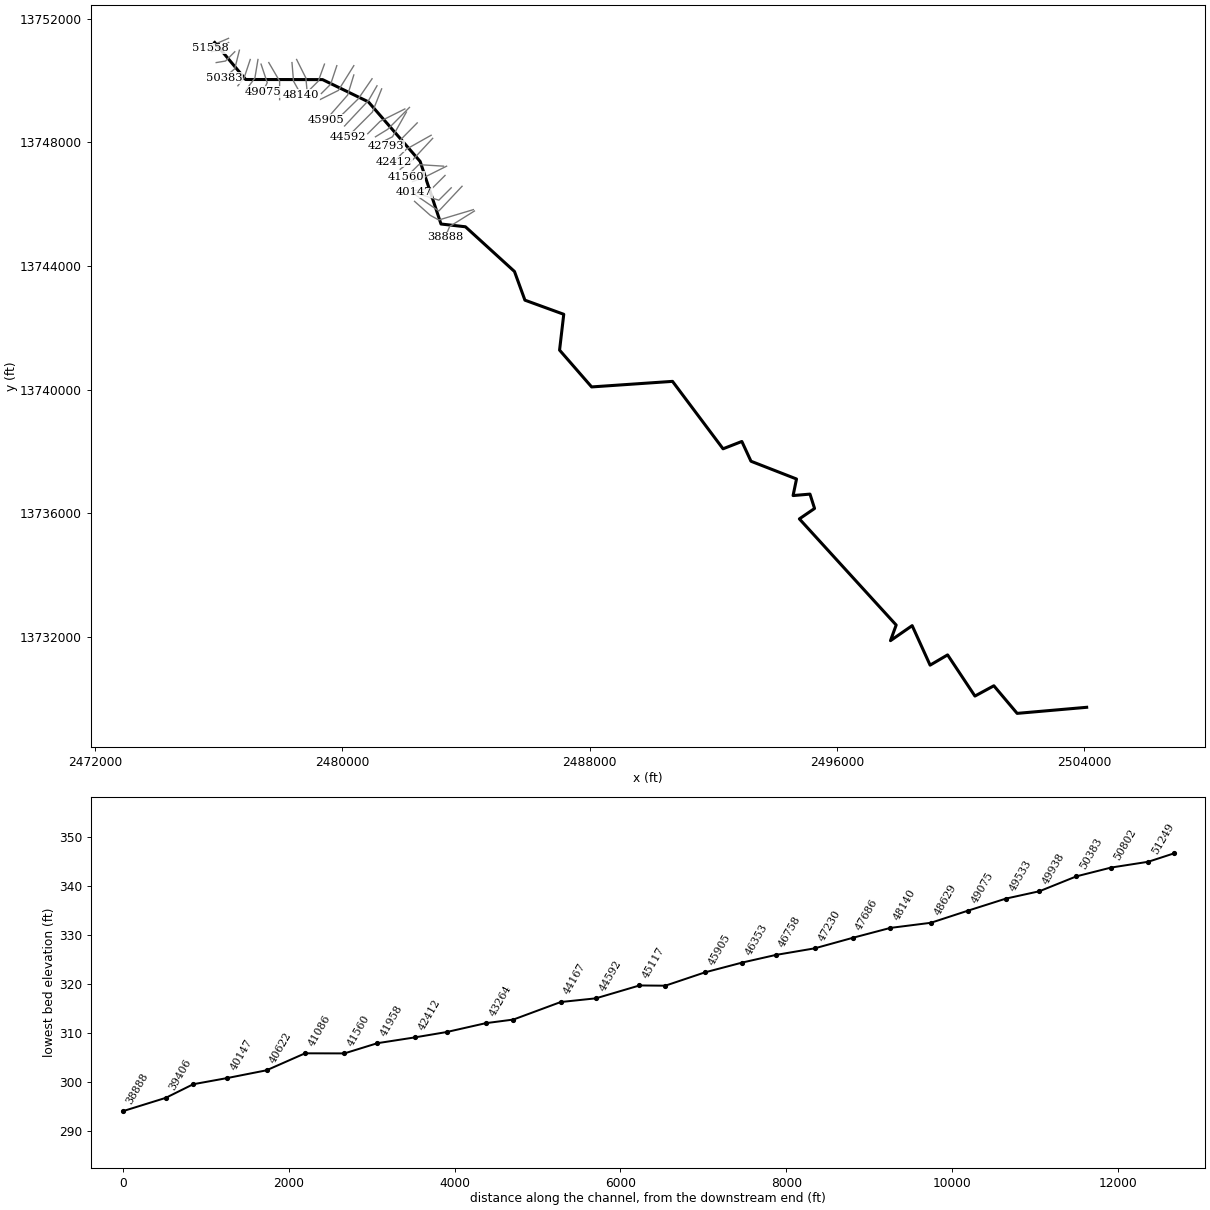
--- MITCHELL CREEK.prj (project) ---

Proj Title=MITCHELL CREEK Base Level Engineering
Current Plan=p01
Default Exp/Contr=0.3,0.1
English Units
Geom File=g01
Flow File=f01
Plan File=p01
Y Axis Title=Elevation
X Axis Title(PF)=Main Channel Distance
X Axis Title(XS)=Station
BEGIN DESCRIPTION:
MITCHELL CREEK
END DESCRIPTION:
DSS Export Rating Curves= 0
DSS Export Rating Curve Sorted= 0
DSS Export Volume Flow Curves= 0
DXF OffsetX= 0
DXF OffsetY= 0
DXF ScaleX= 1
DXF ScaleY= 10

--- MITCHELL CREEK.p01 (plan) ---

Plan Title=Multiple Run
Short Identifier=Multiple
Geom File=g01
Flow File=f01
Subcritical Flow
K Sum by GR= 0
Std Step Tol= 0.01
Critical Tol= 0.01
Num of Std Step Trials= 20
Max Error Tol= 0.3
Flow Tol Ratio= 0.001
Split Flow NTrial= 30
Split Flow Tol= 0.02
Split Flow Ratio= 0.02
Log Output Level= 0
Friction Slope Method= 1
Unsteady Friction Slope Method= 2
Unsteady Bridges Friction Slope Method= 1
Parabolic Critical Depth
Global Vel Dist=  1 , 1 , 1
Global Log Level= 0
CheckData=True
Encroach Param= -1, 0, 0, 0
BEGIN DESCRIPTION:
Multiple Run
END DESCRIPTION:

--- MITCHELL CREEK.f01 (steady flow) ---

Flow Title=Multiple
Number of Profiles=7
Profile Names=10-year,25-year,50-year,1pct_min,100-year,1pct_plu,500-year
River Rch & RM= MITCHELL CREEK,Reach-1,51558
     620     988    1317     851    1697    3386    2787
River Rch & RM= MITCHELL CREEK,Reach-1,46353
     831    1340    1800    1168    2331    4652    3875
River Rch & RM= MITCHELL CREEK,Reach-1,38888
    1168    1921    2612    1715    3422    6829    5823
River Rch & RM= MITCHELL CREEK,Reach-1,37578
    1434    2377    3251    2145    4279    8539    7352
River Rch & RM= MITCHELL CREEK,Reach-1,33667
    1474    2443    3340    2203    4395    8769    7543
River Rch & RM= MITCHELL CREEK,Reach-1,31453
    1920    3213    4420    2931    5848   11669   10148
River Rch & RM= MITCHELL CREEK,Reach-1,25406
    1968    3291    4525    2999    5983   11938   10367
River Rch & RM= MITCHELL CREEK,Reach-1,22625
    2156    3616    4982    3307    6599   13166   11473
River Rch & RM= MITCHELL CREEK,Reach-1,18127
    2242    3757    5172    3429    6842   13651   11869
River Rch & RM= MITCHELL CREEK,Reach-1,13109
    2316    3872    5323    3523    7030   14027   12155
River Rch & RM= MITCHELL CREEK,Reach-1,3973
    2805    4722    6521    4334    8647   17253   15071
Boundary for River Rch & Prof#=MITCHELL CREEK,Reach-1,1
Up Type=0
Dn Type=3
Dn Slope=0.005
Boundary for River Rch & Prof#=MITCHELL CREEK,Reach-1,2
Up Type=0
Dn Type=3
Dn Slope=0.005
Boundary for River Rch & Prof#=MITCHELL CREEK,Reach-1,3
Up Type=0
Dn Type=3
Dn Slope=0.005
Boundary for River Rch & Prof#=MITCHELL CREEK,Reach-1,4
Up Type=0
Dn Type=3
Dn Slope=0.005
Boundary for River Rch & Prof#=MITCHELL CREEK,Reach-1,5
Up Type=0
Dn Type=3
Dn Slope=0.005
Boundary for River Rch & Prof#=MITCHELL CREEK,Reach-1,6
Up Type=0
Dn Type=3
Dn Slope=0.005
Boundary for River Rch & Prof#=MITCHELL CREEK,Reach-1,7
Up Type=0
Dn Type=3
Dn Slope=0.005

--- MITCHELL CREEK.g01 (geometry) ---

Geom Title=Existing Conditions
Program Version=4.10

River Reach=MITCHELL CREEK  ,Reach-1
Reach XY= 30
        2475875.       13751225.      2476876.65     13750028.16
      2479364.37     13750024.39      2480845.73     13749305.27
      2482519.99     13747377.54      2483194.21     13745354.61
        2483985.     13745264.94      2485570.28     13743819.38
      2485908.32     13742891.64      2487164.26      13742434.7
      2487028.75     13741276.55      2488065.32     13740085.76
      2490681.62     13740265.61      2492315.27     13738084.93
       2492923.6     13738322.01      2493218.81     13737682.75
      2494691.74     13737108.37      2494580.52     13736572.57
      2495127.46      13736619.6      2495275.11      13736154.9
      2494784.11     13735818.27       2497914.7      13732385.1
      2497730.38     13731880.18      2498431.73     13732365.89
      2499011.68     13731088.37      2499577.57     13731420.05
      2500461.64     13730088.34      2501073.53     13730421.47
      2501826.47     13729528.53        2504075.       13729725.

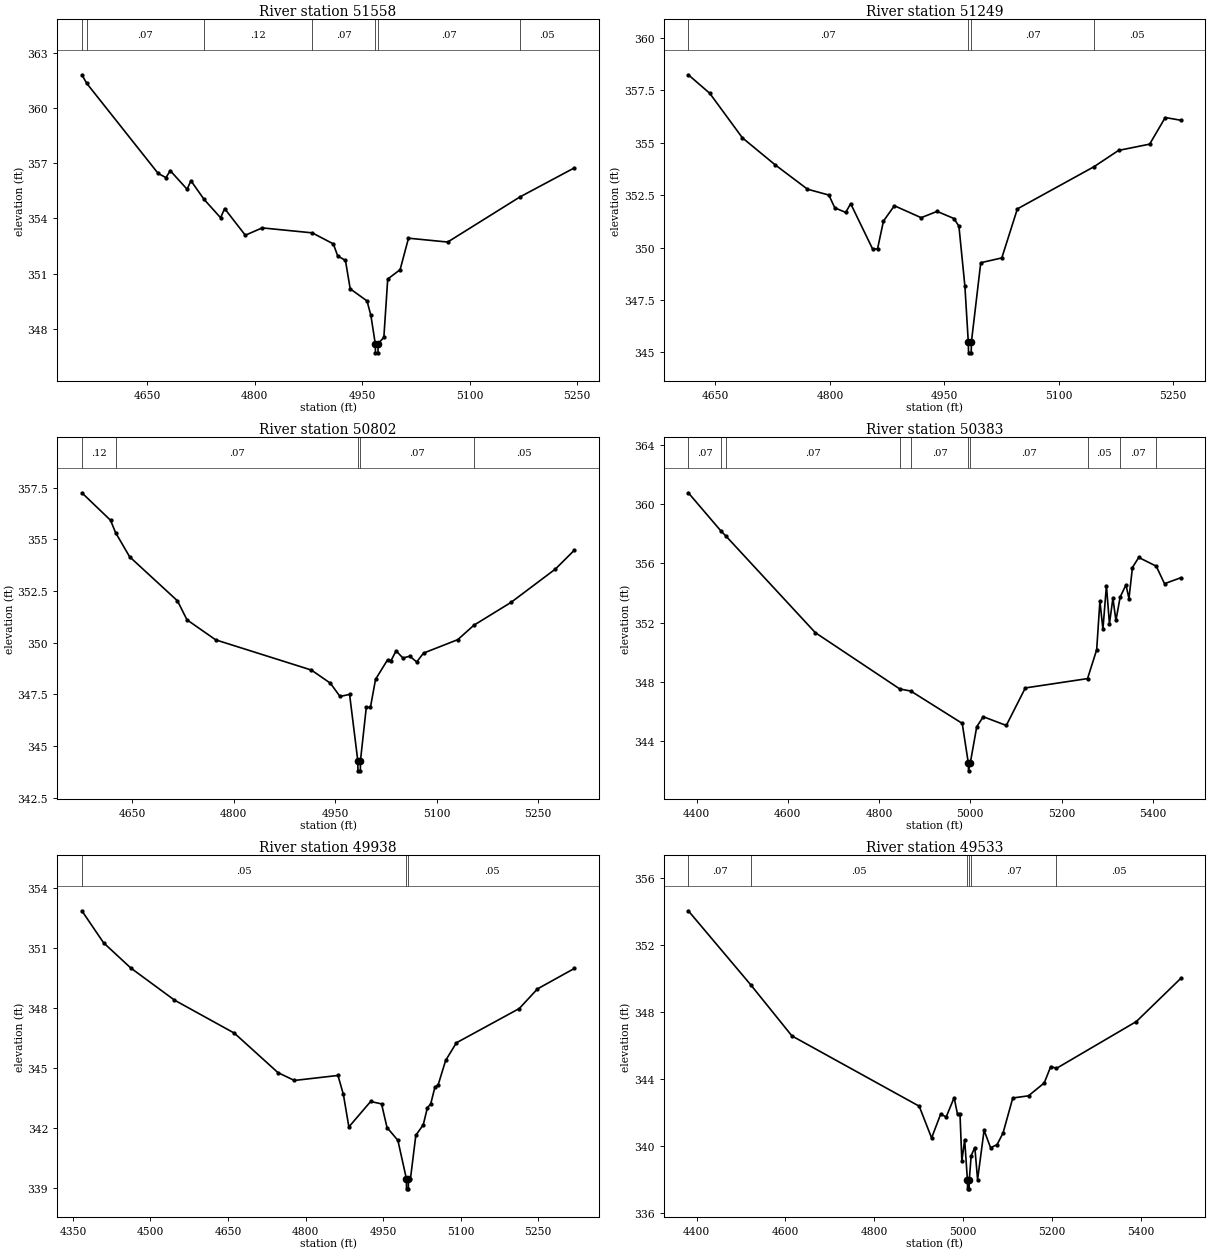
Type RM Length L Ch R = 1 ,51558   ,309,309,309
BEGIN DESCRIPTION:
B19616
END DESCRIPTION:
XS GIS Cut Line= 3
      2476322.77      13751359.2      2475864.75     13751161.02
      2475721.06      13751039.1
#Sta/Elev= 30
  4558.5   361.8  4565.4  361.33    4665  356.44  4675.9  356.21  4681.9  356.59
  4705.4  355.58  4710.8  356.04  4729.1  355.03  4752.2  354.03  4757.8  354.53
  4786.7  353.08  4810.2  353.48  4880.1  353.21  4909.6  352.61  4915.6  351.96
  4926.5  351.71  4933.1  350.17  4956.6  349.51    4962  348.72  4968.1  347.19
  4968.4  346.69  4971.9  346.69  4972.1  347.19  4980.1  347.53  4985.5   350.7
  5002.8  351.21  5014.5  352.92  5069.2  352.71    5170  355.16    5246  356.74
#Mann= 7 ,-1 , 0
  4558.5     .12       0  4565.4     .07       0  4729.1     .12       0
  4880.1     .07       0  4968.1     .05       0  4972.1     .07       0
    5170     .05       0
Bank Sta=4968.1,4972.1
XS Rating Curve= 0 ,0
Exp/Cntr=0.3,0.1

Type RM Length L Ch R = 1 ,51249   ,447,447,447
BEGIN DESCRIPTION:
MITCHELL CREEK 81.0
END DESCRIPTION:
XS GIS Cut Line= 3
        2476325.       13751225.        2476025.       13750975.
      2475774.96     13750924.99
#Sta/Elev= 30
  4614.4  358.25  4642.4  357.37  4685.3  355.24  4728.3  353.95  4770.6  352.79
  4798.6  352.51  4806.4   351.9  4820.7  351.68  4827.2   352.1  4855.9  349.94
  4862.4  349.94  4870.2  351.27  4884.5     352  4919.6  351.43  4940.5  351.73
  4962.6  351.39  4969.1  351.02  4976.9  348.17  4981.4  345.48  4981.7  344.98
  4985.2  344.98  4985.4  345.48  4997.7  349.28  5025.3  349.51  5045.7  351.85
    5146  353.86  5178.3  354.64  5219.1  354.94  5239.5  356.21  5259.9  356.08
#Mann= 4 ,-1 , 0
  4614.4     .07       0  4981.4     .05       0  4985.4     .07       0
    5146     .05       0
Bank Sta=4981.4,4985.4
XS Rating Curve= 0 ,0
Exp/Cntr=0.3,0.1

Type RM Length L Ch R = 1 ,50802   ,419,419,419
BEGIN DESCRIPTION:
MITCHELL CREEK 80.0
END DESCRIPTION:
XS GIS Cut Line= 3
      2476524.99     13750924.99        2476225.       13750625.
      2475924.99       13750575.
#Sta/Elev= 30
  4575.4  357.26  4617.8  355.93  4625.3  355.33  4646.1  354.16  4716.8  352.03
  4730.9  351.11  4773.4  350.14  4914.8  348.68  4943.1  348.04  4957.2   347.4
  4971.4   347.5  4983.5   344.3  4983.8   343.8  4987.3   343.8  4987.5   344.3
  4996.1  346.87  5002.2  346.87  5009.8  348.23  5027.5  349.17  5032.6  349.13
  5040.2  349.61  5050.3  349.26  5060.5  349.35  5070.6  349.07  5080.8   349.5
  5131.4  350.15  5155.3  350.85    5210  351.95  5275.9  353.57  5303.8  354.48
#Mann= 5 ,-1 , 0
  4575.4     .12       0  4625.3     .07       0  4983.5     .05       0
  4987.5     .07       0  5155.3     .05       0
Bank Sta=4983.5,4987.5
XS Rating Curve= 0 ,0
Exp/Cntr=0.3,0.1

Type RM Length L Ch R = 1 ,50383   ,445,445,445
BEGIN DESCRIPTION:
MITCHELL CREEK 79.0
END DESCRIPTION:
XS GIS Cut Line= 3
        2476675.     13750975.02        2476525.       13750375.
      2476174.97     13750074.97
#Sta/Elev= 30
  4381.8  360.75  4452.6   358.2  4464.9  357.81  4660.1  351.32  4845.4  347.52
  4869.5  347.38  4982.2   345.2  4995.7   342.5    4996     342  4999.7   342.5
    5014  344.97  5028.3  345.65  5078.8  345.06  5120.5  347.59  5256.9  348.22
  5276.9  350.16    5284  353.44  5290.6  351.55  5298.3  354.49  5304.9  351.92
  5312.5  353.64  5319.1  352.14  5328.4  353.72  5341.1  354.54  5347.7  353.62
  5355.3  355.71  5369.1  356.39  5407.5   355.8  5425.6  354.62  5461.3  355.02
#Mann= 10 ,-1 , 0
  4381.8     .07       0  4452.6     .12       0  4464.9     .07       0
  4845.4     .05       0  4869.5     .07       0  4995.7     .05       0
  4999.7     .07       0  5256.9     .05       0  5328.4     .07       0
  5407.5     .05       0
Bank Sta=4995.7,4999.7
XS Rating Curve= 0 ,0
Exp/Cntr=0.3,0.1

Type RM Length L Ch R = 1 ,49938   ,405,405,405
BEGIN DESCRIPTION:
MITCHELL CREEK 78.0
END DESCRIPTION:
XS GIS Cut Line= 3
      2477024.99     13750674.96        2476825.       13750075.
      2476624.98     13749824.98
#Sta/Elev= 30
  4367.3  352.84  4409.4  351.24  4462.1  349.98  4546.5  348.38  4662.4  346.73
  4746.7  344.76  4778.4  344.37  4862.7  344.62  4873.2  343.67  4883.8  342.05
  4925.9  343.32    4947   343.2  4957.6  342.02  4978.6  341.38  4995.1  339.46
  4995.3  338.96  4998.8  338.96  4999.1  339.46  5002.9  339.46  5013.3  341.63
  5027.7  342.16  5035.7  343.01  5042.1   343.2  5050.1  344.02  5056.5  344.15
    5071  345.37  5091.8  346.25  5213.4  347.96  5248.6  348.94  5319.9  349.96
#Mann= 3 ,-1 , 0
  4367.3     .05       0  4995.1     .05       0  4999.1     .05       0
Bank Sta=4995.1,4999.1
XS Rating Curve= 0 ,0
Exp/Cntr=0.3,0.1

Type RM Length L Ch R = 1 ,49533   ,458,458,458
BEGIN DESCRIPTION:
MITCHELL CREEK 77.0
END DESCRIPTION:
XS GIS Cut Line= 3
      2477275.01     13750675.04        2477175.       13750075.
      2476875.01     13749675.01
#Sta/Elev= 30
  4381.4  354.07    4522  349.64  4614.6  346.59    4901  342.39  4928.9  340.49
  4949.2  341.91  4961.8  341.75  4979.6   342.9  4987.2  341.91  4992.8  341.91
    4997  339.11  5003.3  340.39  5009.6  337.95  5009.8  337.45  5013.3  337.45
  5013.6  337.95    5018  339.44  5026.2  339.92  5032.4     338    5047  340.95
  5061.6  339.91  5076.2  340.09  5089.7  340.79  5111.6  342.88    5147  343.01
  5182.4  343.78    5197  344.76  5209.9  344.65  5389.7  347.45  5489.7  350.03
#Mann= 6 ,-1 , 0
  4381.4     .07       0    4522     .05       0  5009.6     .05       0
  5013.6     .05       0    5018     .07       0  5209.9     .05       0
Bank Sta=5009.6,5013.6
XS Rating Curve= 0 ,0
Exp/Cntr=0.3,0.1

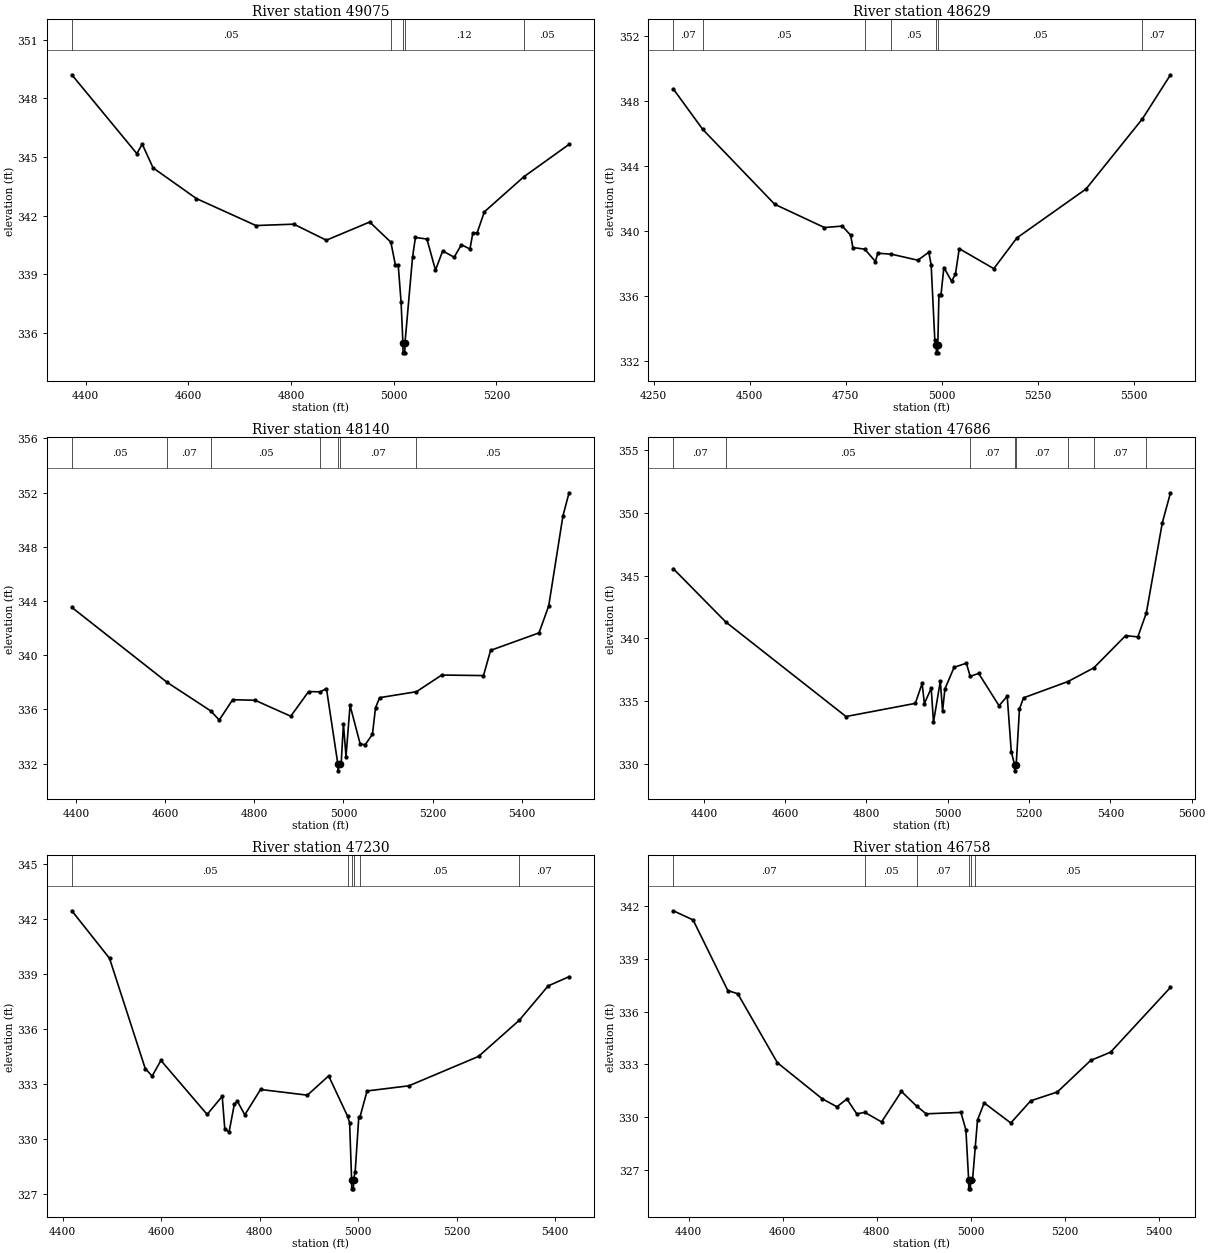
Type RM Length L Ch R = 1 ,49075   ,446,446,446
BEGIN DESCRIPTION:
MITCHELL CREEK 76.0
END DESCRIPTION:
XS GIS Cut Line= 3
      2477374.99     13750525.02        2477575.       13749925.
        2477425.     13749624.99
#Sta/Elev= 30
  4373.4   349.2  4499.9  345.17  4510.5  345.65  4531.5  344.44  4615.9  342.87
  4731.8  341.49  4805.6  341.56  4868.8  340.74  4953.2  341.67  4994.4  340.64
  5003.2  339.48  5008.7  339.48  5014.3  337.58  5017.9  335.48  5018.1  334.98
  5021.6  334.98  5021.9  335.48  5036.6  339.86  5042.2  340.88  5064.6   340.8
  5081.3  339.21  5095.3  340.19  5117.7  339.87  5131.7  340.51  5148.4  340.29
    5154  341.11  5162.4  341.12  5176.4  342.19  5253.1  343.98  5341.3  345.64
#Mann= 5 ,-1 , 0
  4373.4     .05       0  4994.4     .12       0  5017.9     .05       0
  5021.9     .12       0  5253.1     .05       0
Bank Sta=5017.9,5021.9
XS Rating Curve= 0 ,0
Exp/Cntr=0.3,0.1

Type RM Length L Ch R = 1 ,48629   ,489,489,489
BEGIN DESCRIPTION:
MITCHELL CREEK 75.0
END DESCRIPTION:
XS GIS Cut Line= 3
        2477625.       13750575.        2477975.       13749975.
        2477975.     13749375.02
#Sta/Elev= 30
  4300.8  348.75  4377.5  346.26    4565  341.65  4694.4  340.22  4740.7  340.31
  4762.6  339.75  4768.4  338.99  4799.4  338.89  4827.1  338.13  4833.3  338.64
  4868.9  338.58  4937.5  338.21  4966.1   338.7  4972.3  337.91  4981.8  333.28
  4985.6  333.01  4985.8  332.51  4989.3  332.51  4989.6  333.01  4992.5  336.09
  4997.9  336.09  5005.4  337.76  5025.4  336.92  5035.4  337.34  5045.4  338.92
  5135.4  337.69  5195.4  339.58  5375.4  342.59  5522.4  346.91  5595.4  349.62
#Mann= 7 ,-1 , 0
  4300.8     .07       0  4377.5     .05       0  4799.4     .07       0
  4868.9     .05       0  4985.6     .05       0  4989.6     .05       0
  5522.4     .07       0
Bank Sta=4985.6,4989.6
XS Rating Curve= 0 ,0
Exp/Cntr=0.3,0.1

Type RM Length L Ch R = 1 ,48140   ,454,454,454
BEGIN DESCRIPTION:
MITCHELL CREEK 74.0
END DESCRIPTION:
XS GIS Cut Line= 3
        2478375.     13750574.96        2478425.       13749975.
      2478674.99     13749525.02
#Sta/Elev= 30
  4389.9  343.52  4604.3  337.98    4702  335.88    4721  335.21  4751.1  336.71
  4801.3  336.67  4881.6  335.49  4921.7  337.31  4947.8  337.29  4961.8  337.53
  4987.4  331.96  4987.7  331.46  4991.4  331.96  4994.8  331.96  4999.9  334.93
  5005.7  332.51  5014.8  336.29  5037.7  333.42  5049.1   333.4  5065.1  334.16
    5072  336.11  5081.2  336.86    5164   337.3  5220.7  338.53  5314.5  338.49
  5330.5  340.35  5439.2  341.64    5461  343.63    5493  350.28  5506.7  351.98
#Mann= 7 ,-1 , 0
  4389.9     .05       0  4604.3     .07       0    4702     .05       0
  4947.8     .07       0  4987.4     .05       0  4991.4     .07       0
    5164     .05       0
Bank Sta=4987.4,4991.4
XS Rating Curve= 0 ,0
Exp/Cntr=0.3,0.1

Type RM Length L Ch R = 1 ,47686   ,456,456,456
BEGIN DESCRIPTION:
MITCHELL CREEK 73.0
END DESCRIPTION:
XS GIS Cut Line= 3
      2478524.98     13750675.03        2478825.       13750075.
        2478875.     13749525.02
#Sta/Elev= 30
  4324.8  345.55  4454.2  341.29  4749.7  333.76  4920.2  334.81    4937   336.4
  4942.5  334.79  4959.3  336.02  4964.9  333.31  4981.7  336.57  4987.3  334.19
  4992.9  335.95  5015.7  337.69  5045.9  338.01  5055.2  336.96    5076   337.2
  5126.2  334.62  5146.3  335.38  5156.3  330.94  5164.4  329.93  5164.6  329.43
  5168.4  329.93  5176.4  334.36  5186.4  335.25  5295.7  336.55  5359.3  337.64
  5437.5  340.21  5467.6  340.11  5488.5  342.02  5527.8  349.21  5547.9   351.6
#Mann= 8 ,-1 , 0
  4324.8     .07       0  4454.2     .05       0  5055.2     .07       0
  5164.4     .05       0  5168.4     .07       0  5295.7     .05       0
  5359.3     .07       0  5488.5     .05       0
Bank Sta=5164.4,5168.4
XS Rating Curve= 0 ,0
Exp/Cntr=0.3,0.1

Type RM Length L Ch R = 1 ,47230   ,472,472,472
BEGIN DESCRIPTION:
MITCHELL CREEK 72.0
END DESCRIPTION:
XS GIS Cut Line= 3
      2479425.02     13750525.04        2479225.       13749975.
      2478925.03     13749675.03
#Sta/Elev= 30
  4418.7  342.43  4495.2  339.84  4567.7  333.84  4581.7  333.43  4599.6  334.28
  4693.4  331.34    4724  332.33  4729.3  330.53    4738  330.39  4748.6   331.9
  4754.6  332.07  4769.9  331.32  4801.8   332.7  4896.9  332.39  4940.1  333.44
  4978.6  331.24  4982.7  330.88  4986.7  327.79  4986.9  327.29  4990.4  327.29
  4990.7  327.79    4994  328.23  5001.3   331.2  5003.7   331.2  5018.1  332.62
    5103   332.9  5244.4   334.5  5326.8  336.46  5385.8  338.34  5428.2  338.84
#Mann= 6 ,-1 , 0
  4418.7     .05       0  4978.6     .07       0  4986.7     .05       0
  4990.7     .07       0  5003.7     .05       0  5326.8     .07       0
Bank Sta=4986.7,4990.7
XS Rating Curve= 0 ,0
Exp/Cntr=0.3,0.1

Type RM Length L Ch R = 1 ,46758   ,405,405,405
BEGIN DESCRIPTION:
MITCHELL CREEK 71.0
END DESCRIPTION:
XS GIS Cut Line= 3
      2479824.99     13750474.98        2479625.       13749875.
        2479325.       13749575.
#Sta/Elev= 30
  4367.6  341.72  4409.7   341.2  4483.5  337.19  4504.6  337.01  4588.9  333.09
  4683.8  331.05  4715.4  330.59  4736.5  331.03  4757.6  330.19  4774.8  330.27
  4810.3  329.73  4852.5  331.46  4884.6  330.63  4905.2  330.19  4978.9  330.27
  4989.5  329.28  4995.4  326.43  4995.6  325.93  4999.1  325.93  4999.4  326.43
  5003.6  326.43  5009.4   328.3  5014.2  329.84  5028.3  330.81  5084.9  329.67
  5127.3  330.93  5183.9  331.43  5254.6  333.22    5297  333.69  5424.3  337.37
#Mann= 6 ,-1 , 0
  4367.6     .07       0  4774.8     .05       0  4884.6     .07       0
  4995.4     .05       0  4999.4     .07       0  5009.4     .05       0
Bank Sta=4995.4,4999.4
XS Rating Curve= 0 ,0
Exp/Cntr=0.3,0.1

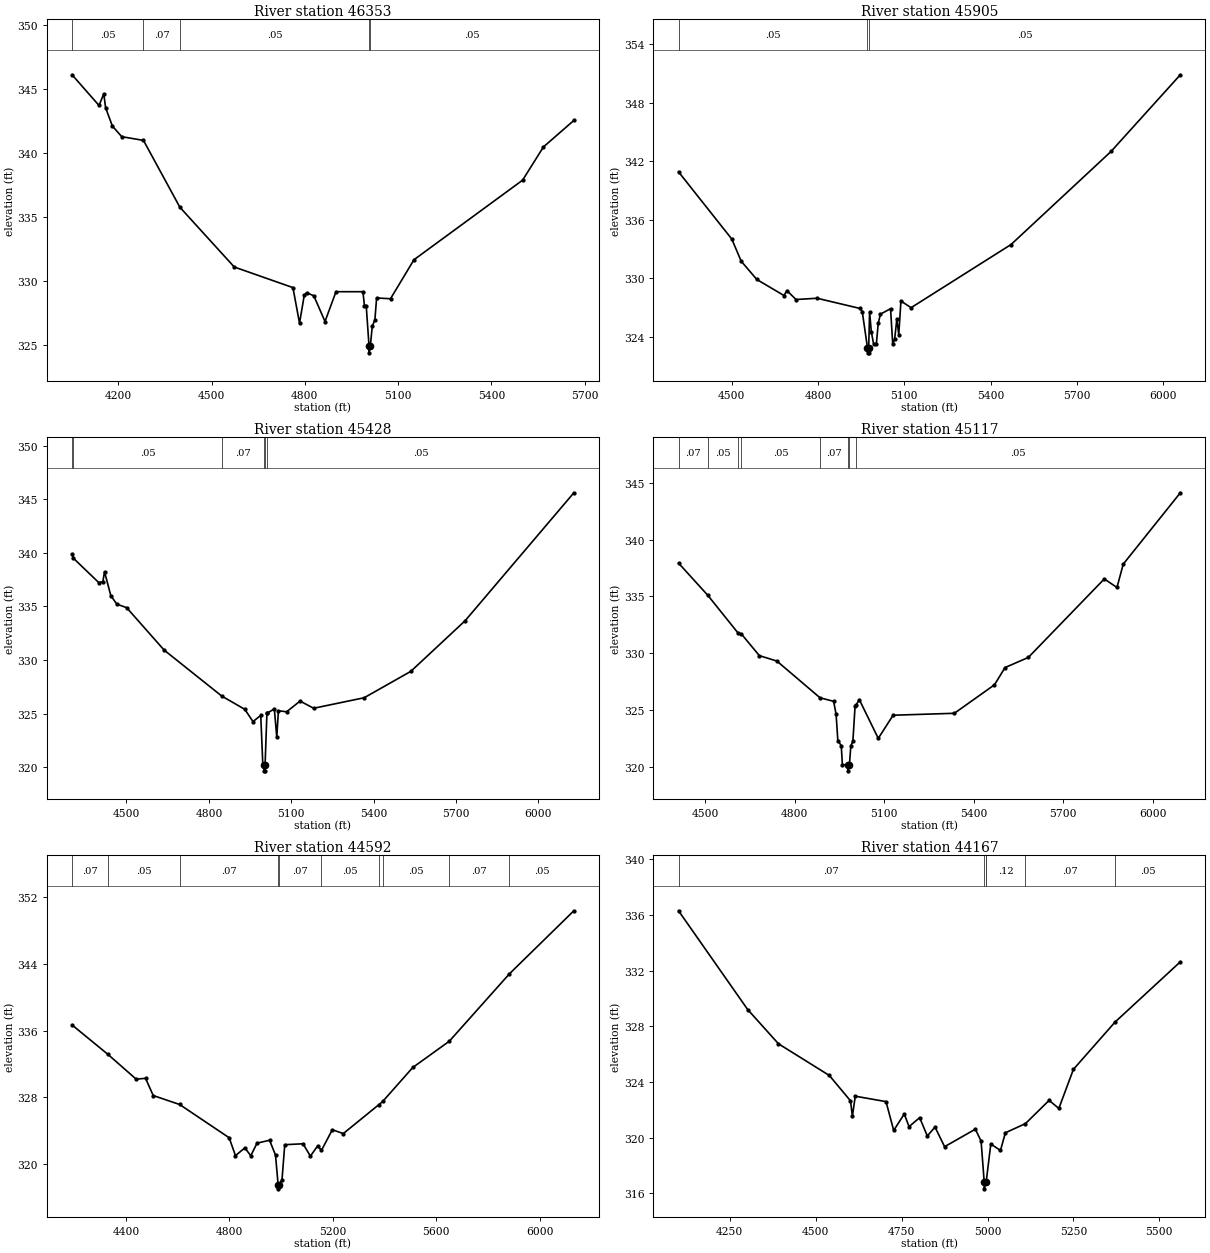
Type RM Length L Ch R = 1 ,46353   ,448,448,448
BEGIN DESCRIPTION:
MITCHELL CREEK 70.0
END DESCRIPTION:
XS GIS Cut Line= 3
      2480374.99     13750474.99        2479875.       13749675.
      2479275.01       13749375.
#Sta/Elev= 30
  4051.3  346.11    4138  343.71  4153.3  344.62  4159.2  343.53    4181   342.1
  4211.1  341.27    4281  340.98  4398.2  335.75  4573.1  331.08  4761.8  329.47
    4783  326.69  4798.3  328.88    4806  329.07    4829  328.83    4865  326.82
  4900.3  329.15    4987  329.15  4991.7  328.07  4997.5  328.07  5006.7  324.87
  5006.9  324.37  5010.7  324.87    5017  326.46  5025.4  326.94    5031  328.66
  5075.7   328.6  5151.2  331.65  5500.6  337.87  5567.7  340.47  5665.5  342.54
#Mann= 5 ,-1 , 0
  4051.3     .05       0    4281     .07       0  4398.2     .05       0
  5006.7     .05       0  5010.7     .05       0
Bank Sta=5006.7,5010.7
XS Rating Curve= 0 ,0
Exp/Cntr=0.3,0.1

Type RM Length L Ch R = 1 ,45905   ,477,477,477
BEGIN DESCRIPTION:
MITCHELL CREEK 69.0
END DESCRIPTION:
XS GIS Cut Line= 3
        2480375.     13750174.99        2480175.       13749525.
      2479474.98     13748724.98
#Sta/Elev= 30
  4315.8   340.9  4500.8  334.02  4533.5  331.75  4587.8  329.88    4682  328.24
  4692.4  328.74  4723.8  327.83  4797.1  327.96  4946.8  326.91    4954   326.6
  4972.2  322.87  4972.5  322.37  4976.1  322.37  4976.3  322.87  4979.5  326.56
  4985.4  324.55  4993.2   323.3    5003  323.28  5009.6  325.42  5017.2  326.33
  5052.3  326.89  5059.9  323.24  5066.6   323.8  5074.2  325.83  5080.8  324.22
  5088.4  327.68  5123.5  326.99  5470.9  333.46  5818.3  342.99  6058.9  350.84
#Mann= 3 ,-1 , 0
  4315.8     .05       0  4972.2     .05       0  4976.3     .05       0
Bank Sta=4972.2,4976.3
XS Rating Curve= 0 ,0
Exp/Cntr=0.3,0.1

Type RM Length L Ch R = 1 ,45428   ,311,311,311
BEGIN DESCRIPTION:
MITCHELL CREEK 68.0
END DESCRIPTION:
XS GIS Cut Line= 3
      2480964.27     13750051.28      2480519.49     13749403.93
      2479775.03     13748675.03
#Sta/Elev= 30
  4301.8  339.91  4306.7  339.49    4399  337.22  4413.9  337.29    4420  338.23
  4442.9     336  4464.7  335.21  4500.5  334.88    4637  330.92  4846.8  326.63
  4930.8  325.39  4960.6  324.25  4988.9  324.82  4996.5  320.17  5000.4  320.15
  5000.7  319.65  5004.4  319.65  5004.6  320.15  5011.4  325.06  5013.4  325.05
  5038.4  325.43  5047.2   322.8  5053.3  325.26  5083.1  325.16  5132.1  326.16
  5181.5  325.49  5365.4  326.47  5535.2  328.93  5733.2  333.66  6129.1   345.6
#Mann= 6 ,-1 , 0
  4301.8     .07       0  4306.7     .05       0  4846.8     .07       0
  5000.4     .05       0  5004.6     .07       0  5013.4     .05       0
Bank Sta=5000.4,5004.6
XS Rating Curve= 0 ,0
Exp/Cntr=0.3,0.1

Type RM Length L Ch R = 1 ,45117   ,525,525,525
BEGIN DESCRIPTION:
MITCHELL CREEK 67.0
END DESCRIPTION:
XS GIS Cut Line= 3
        2481125.     13749824.99      2480854.17     13749355.49
        2480075.       13748525.
#Sta/Elev= 30
  4411.4  337.93  4509.2  335.11    4610  331.82  4621.9  331.71  4682.1  329.81
    4741  329.33  4885.3  326.11  4930.9   325.8  4939.2  324.66    4945  322.36
  4956.5  321.91  4960.2  320.25  4979.4   320.2  4979.7   319.7  4983.7   320.2
  4988.6   321.9  4995.4  322.29  5002.7  325.37  5005.3  325.44  5016.9  325.95
  5080.4  322.55  5130.2  324.58  5335.3  324.75  5469.7  327.25  5504.9  328.76
    5583  329.65  5837.5  336.54    5880  335.79    5901  337.84  6092.2   344.1
#Mann= 8 ,-1 , 0
  4411.4     .07       0  4509.2     .05       0    4610     .07       0
  4621.9     .05       0  4885.3     .07       0  4979.4     .05       0
  4983.7     .07       0  5005.3     .05       0
Bank Sta=4979.4,4983.7
XS Rating Curve= 0 ,0
Exp/Cntr=0.3,0.1

Type RM Length L Ch R = 1 ,44592   ,425,425,425
BEGIN DESCRIPTION:
MITCHELL CREEK 66.0
END DESCRIPTION:
XS GIS Cut Line= 3
      2481274.98     13749724.96        2480975.       13748975.
        2480175.       13748175.
#Sta/Elev= 30
  4192.3  336.67  4330.2  333.17    4440  330.19  4476.3  330.29  4505.9  328.23
  4607.9  327.16  4799.4  323.18  4823.7  321.04    4860  321.97  4882.9  321.03
  4907.1  322.54  4955.6  322.88  4978.5   321.1  4988.5  317.57  4988.7  317.07
  4992.8  317.57  5003.6  318.17  5014.2  322.35  5084.9  322.46  5113.2  320.98
  5141.4  322.21    5156  321.67    5198  324.14  5240.4  323.68  5378.3  327.15
  5392.7  327.52  5509.1  331.59  5650.2  334.73  5882.4  342.79  6131.4  350.33
#Mann= 10 ,-1 , 0
  4192.3     .07       0  4330.2     .05       0  4607.9     .07       0
  4988.5     .05       0  4992.8     .07       0    5156     .05       0
  5378.3     .07       0  5392.7     .05       0  5650.2     .07       0
  5882.4     .05       0
Bank Sta=4988.5,4992.8
XS Rating Curve= 0 ,0
Exp/Cntr=0.3,0.1

Type RM Length L Ch R = 1 ,44167   ,570,570,570
BEGIN DESCRIPTION:
MITCHELL CREEK 65.0
END DESCRIPTION:
XS GIS Cut Line= 3
      2482024.99       13749075.        2481225.       13748675.
        2480825.       13748275.
#Sta/Elev= 30
  4100.9   336.3  4302.1   329.2  4391.6  326.74  4539.7  324.46  4601.2  322.64
  4606.8  321.54  4615.2  322.97  4704.6  322.58    4727  320.51  4757.7  321.69
  4771.7  320.78  4802.5  321.43  4824.8  320.11  4847.2  320.75  4875.1  319.34
  4964.6   320.6  4981.3  319.74  4990.3  316.81  4990.6  316.31  4994.8  316.81
  4996.1  316.81  5009.5  319.53  5037.7  319.07  5051.9  320.34  5110.4     321
  5179.2  322.67  5207.5  322.09  5249.9   324.9  5371.1   328.3    5561  332.63
#Mann= 6 ,-1 , 0
  4100.9     .07       0  4990.3     .05       0  4994.8     .07       0
  4996.1     .12       0  5110.4     .07       0  5371.1     .05       0
Bank Sta=4990.3,4994.8
XS Rating Curve= 0 ,0
Exp/Cntr=0.3,0.1

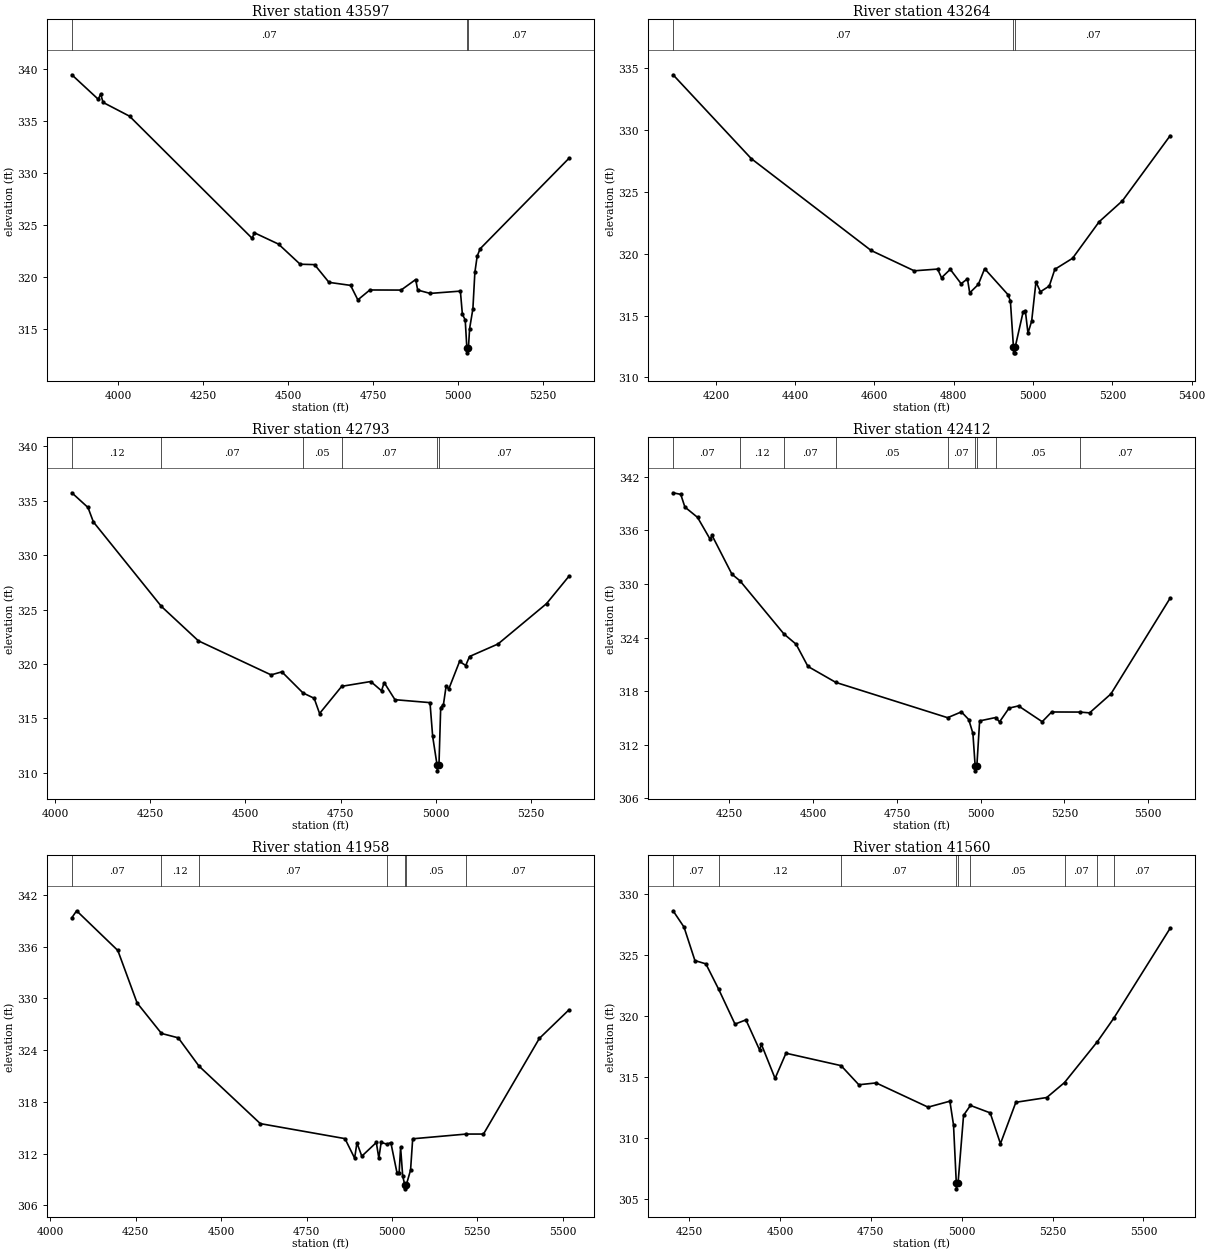
Type RM Length L Ch R = 1 ,43597   ,333,333,333
BEGIN DESCRIPTION:
MITCHELL CREEK 64.0
END DESCRIPTION:
XS GIS Cut Line= 3
      2482174.99     13749124.99      2481470.69     13748417.49
      2481074.98     13748174.99
#Sta/Elev= 30
  3863.9   339.4  3941.7  337.05  3948.7  337.56  3955.8  336.75  4033.6  335.43
  4394.2  323.72  4401.3  324.24    4472  323.16  4535.6  321.23  4578.1  321.19
  4620.5  319.49  4684.1   319.2  4705.4  317.81  4740.7  318.76  4832.6  318.75
  4875.6  319.76  4881.5  318.75  4918.2  318.43  5007.1  318.65    5013  316.42
  5021.3  315.89  5026.1  313.23  5026.4  312.73  5030.8  313.23  5034.3  315.06
  5043.9  316.95  5049.7  320.44  5056.5     322  5065.2  322.71  5326.3  331.38
#Mann= 3 ,-1 , 0
  3863.9     .07       0  5026.1     .05       0  5030.8     .07       0
Bank Sta=5026.1,5030.8
XS Rating Curve= 0 ,0
Exp/Cntr=0.3,0.1

Type RM Length L Ch R = 1 ,43264   ,471,471,471
BEGIN DESCRIPTION:
MITCHELL CREEK 63.0
END DESCRIPTION:
XS GIS Cut Line= 3
        2482075.       13748975.        2481625.       13748175.
      2481324.99     13748024.99
#Sta/Elev= 30
  4092.2  334.43  4289.5  327.66  4591.6  320.25  4700.3  318.61  4759.3  318.75
  4769.1  318.05  4791.1  318.73  4818.5  317.57  4834.5  317.96  4840.2  316.83
  4861.9  317.51  4877.8  318.78  4937.1  316.67  4942.8  316.15  4950.4  312.49
  4950.7  311.99  4954.7  311.99  4955.1  312.49  4974.7  315.27  4980.4   315.4
  4987.1  313.58  4996.4  314.55  5007.2  317.71  5018.5  316.92  5040.8  317.38
  5054.8  318.73  5099.5  319.62  5166.6  322.57  5225.3  324.26  5345.5  329.51
#Mann= 3 ,-1 , 0
  4092.2     .07       0  4950.4     .05       0  4955.1     .07       0
Bank Sta=4950.4,4955.1
XS Rating Curve= 0 ,0
Exp/Cntr=0.3,0.1

Type RM Length L Ch R = 1 ,42793   ,381,381,381
BEGIN DESCRIPTION:
MITCHELL CREEK 62.0
END DESCRIPTION:
XS GIS Cut Line= 3
      2482425.02     13748625.02      2481708.49     13747897.85
      2481424.99       13747875.
#Sta/Elev= 30
  4044.3  335.74  4086.7  334.39  4100.9  333.06  4279.6  325.29  4376.7  322.13
  4567.6     319  4595.9  319.28  4651.4  317.34  4680.7  316.85  4694.9  315.45
  4753.1  317.95  4829.3  318.39  4857.6  317.54  4864.6  318.29  4892.9  316.72
  4984.9  316.45  4991.9  313.35  5003.6  310.68    5004  310.18  5008.4  310.68
    5013     316  5020.2  316.27  5027.2  317.96  5034.3  317.71  5062.6  320.24
  5078.7  319.86  5088.7  320.69  5163.5  321.84  5290.9  325.55  5349.6  328.06
#Mann= 6 ,-1 , 0
  4044.3     .12       0  4279.6     .07       0  4651.4     .05       0
  4753.1     .07       0  5003.6     .05       0  5008.4     .07       0
Bank Sta=5003.6,5008.4
XS Rating Curve= 0 ,0
Exp/Cntr=0.3,0.1

Type RM Length L Ch R = 1 ,42412   ,454,454,454
BEGIN DESCRIPTION:
MITCHELL CREEK 61.0
END DESCRIPTION:
XS GIS Cut Line= 3
      2482874.97     13748224.98        2482075.       13747775.
      2481675.02     13747375.02
#Sta/Elev= 30
    4082  340.22  4104.9  340.04  4117.3  338.62    4155  337.47  4192.6  335.02
  4198.3  335.45  4257.6  331.11  4281.8  330.36    4413  324.41  4449.1  323.27
  4484.5  320.78  4567.8  318.99  4901.4  315.04  4942.5  315.69  4964.5  314.83
  4976.9  313.28  4983.7  309.59  4984.1  309.09  4988.6  309.59    4997  314.68
    5045  315.06  5056.4  314.57  5084.7  316.11    5113  316.36  5183.7  314.59
    5212  315.68  5295.9  315.67  5325.1  315.58  5388.8   317.7  5565.5  328.42
#Mann= 9 ,-1 , 0
    4082     .07       0  4281.8     .12       0    4413     .07       0
  4567.8     .05       0  4901.4     .07       0  4983.7     .05       0
  4988.6     .07       0    5045     .05       0  5295.9     .07       0
Bank Sta=4983.7,4988.6
XS Rating Curve= 0 ,0
Exp/Cntr=0.3,0.1

Type RM Length L Ch R = 1 ,41958   ,398,398,398
BEGIN DESCRIPTION:
MITCHELL CREEK 60.0
END DESCRIPTION:
XS GIS Cut Line= 3
      2482925.03     13748125.04        2482275.       13747425.
        2481875.       13747125.
#Sta/Elev= 30
  4062.9  339.37  4076.9  340.18  4197.6  335.57    4254  329.48  4325.4  325.94
  4374.5  325.43  4435.2  322.15  4614.8  315.47  4862.6  313.73  4890.9  311.46
  4897.7  313.24  4911.9  311.69  4954.4  313.28  4961.8  311.46  4968.6  313.29
  4986.1  313.08  4996.9  313.27  5014.8  309.79  5021.3  309.79  5025.5  312.71
  5031.7  309.37  5037.6   308.4    5038   307.9  5042.5   308.4  5054.7  310.08
  5060.9  313.71  5217.6  314.26  5268.2  314.26  5431.7  325.36  5518.2  328.67
#Mann= 7 ,-1 , 0
  4062.9     .07       0  4325.4     .12       0  4435.2     .07       0
  4986.1     .05       0  5037.6     .05       0  5042.5     .05       0
  5217.6     .07       0
Bank Sta=5037.6,5042.5
XS Rating Curve= 0 ,0
Exp/Cntr=0.3,0.1

Type RM Length L Ch R = 1 ,41560   ,474,474,474
BEGIN DESCRIPTION:
MITCHELL CREEK 59.0
END DESCRIPTION:
XS GIS Cut Line= 3
      2483275.02       13747225.        2482475.       13747275.
      2482074.98     13746874.98
#Sta/Elev= 30
  4206.1  328.65  4236.2  327.31  4266.2  324.56  4296.3  324.29  4331.6   322.2
  4376.5  319.34  4406.5  319.69  4444.1  317.22  4449.1  317.68  4486.7  314.88
  4516.7  316.95  4668.2  315.93  4717.1  314.36  4764.7  314.51  4907.5  312.52
  4967.6  313.01  4977.6  311.05  4985.2  306.31  4985.5  305.81  4990.1  306.31
  5005.2  311.85  5024.1  312.66  5078.4  312.05  5106.7  309.52  5149.1  312.92
    5234  313.31  5282.9  314.54  5373.6  317.91  5418.3  319.82  5573.4  327.21
#Mann= 9 ,-1 , 0
  4206.1     .07       0  4331.6     .12       0  4668.2     .07       0
  4985.2     .05       0  4990.1     .07       0  5024.1     .05       0
  5282.9     .07       0  5373.6     .05       0  5418.3     .07       0
Bank Sta=4985.2,4990.1
XS Rating Curve= 0 ,0
Exp/Cntr=0.3,0.1

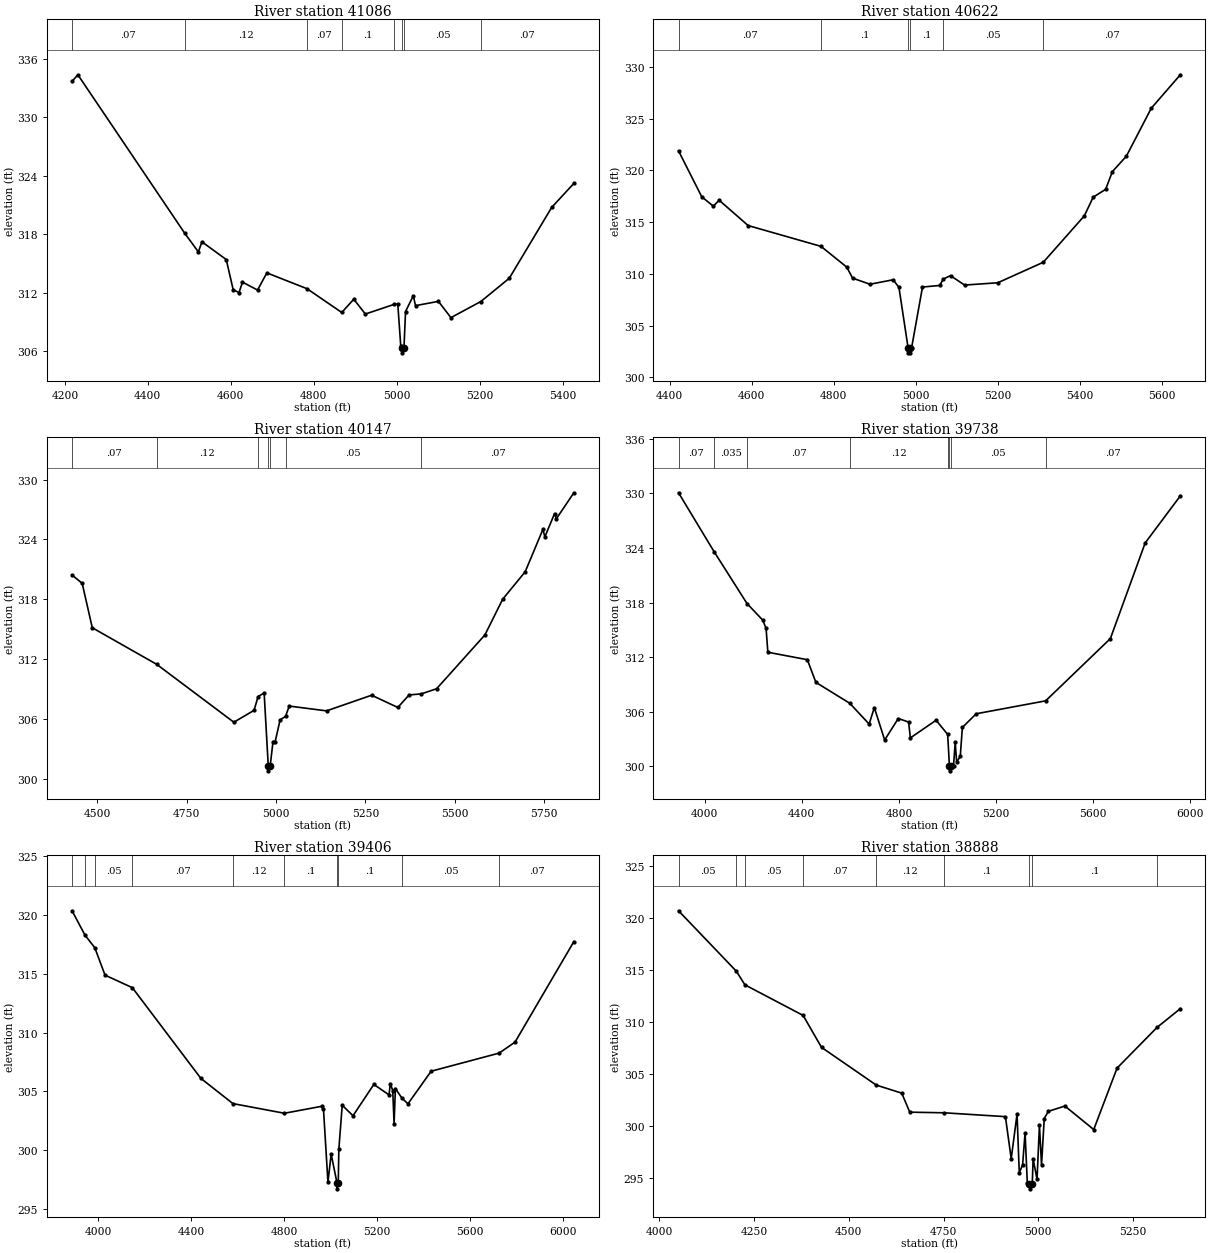
Type RM Length L Ch R = 1 ,41086   ,464,464,464
BEGIN DESCRIPTION:
MITCHELL CREEK 58.0
END DESCRIPTION:
XS GIS Cut Line= 3
      2483374.99     13747224.99        2482675.       13746875.
      2482275.01       13746725.
#Sta/Elev= 30
  4217.4  333.68  4231.4  334.35  4489.1  318.09    4522  316.18  4530.4  317.22
  4589.1   315.4  4605.9   312.3  4619.9  312.01  4628.3  313.08  4664.6  312.27
    4687  314.03  4783.8  312.41  4867.6  309.97  4896.6  311.33  4924.5  309.81
  4994.5  310.81  5002.7  310.83  5009.8  306.56  5012.6  306.33    5013  305.83
  5017.6  306.33  5021.4  310.07  5040.1  311.69  5045.4  310.67  5100.6  311.11
  5130.8  309.44  5202.8  311.09  5271.5  313.48  5373.8  320.75  5427.2  323.21
#Mann= 8 ,-1 , 0
  4217.4     .07       0  4489.1     .12       0  4783.8     .07       0
  4867.6      .1       0  4994.5     .05       0  5012.6     .05       0
  5017.6     .05       0  5202.8     .07       0
Bank Sta=5012.6,5017.6
XS Rating Curve= 0 ,0
Exp/Cntr=0.3,0.1

Type RM Length L Ch R = 1 ,40622   ,475,475,475
BEGIN DESCRIPTION:
MITCHELL CREEK 57.0
END DESCRIPTION:
XS GIS Cut Line= 3
      2483325.03     13746925.03        2482925.       13746525.
      2482274.97       13746425.
#Sta/Elev= 30
  4421.8  321.88  4478.4  317.44  4506.7  316.53  4520.8  317.11  4591.5  314.66
  4769.1  312.65    4832  310.64  4846.1  309.58  4888.5  308.99  4945.1  309.42
  4959.2  308.68  4981.4  302.86  4981.8  302.36  4986.2  302.36  4986.6  302.86
  4990.1  302.86  5016.6  308.72  5058.4  308.87  5067.3  309.49  5084.9  309.82
  5119.1  308.91    5200  309.13    5311  311.11  5411.2   315.6  5432.7   317.4
  5463.1  318.16  5479.5  319.87  5513.6  321.36  5574.4     326  5645.2  329.23
#Mann= 6 ,-1 , 0
  4421.8     .07       0  4769.1      .1       0  4981.4     .05       0
  4986.6      .1       0  5067.3     .05       0    5311     .07       0
Bank Sta=4981.4,4986.6
XS Rating Curve= 0 ,0
Exp/Cntr=0.3,0.1

Type RM Length L Ch R = 1 ,40147   ,409,409,409
BEGIN DESCRIPTION:
MITCHELL CREEK 56.0
END DESCRIPTION:
XS GIS Cut Line= 3
      2483525.01     13746525.01        2483125.       13746125.
      2482324.95     13746375.01
#Sta/Elev= 30
  4429.1  320.42  4457.4  319.59  4485.7  315.13  4665.9  311.46  4881.7  305.65
  4938.2  306.84  4949.6  308.23  4966.5  308.58    4978  301.27  4978.4  300.77
  4983.4  301.27  4991.3  303.71  4997.4  303.71    5011  305.87  5026.3  306.24
  5036.7  307.27    5141  306.79  5267.2  308.36  5340.5  307.13    5372  308.39
  5405.8  308.49    5449  309.01  5584.1  314.41  5633.9     318  5696.8  320.75
  5746.5  325.01  5751.8  324.25    5779  326.59  5784.2  326.08    5833  328.68
#Mann= 7 ,-1 , 0
  4429.1     .07       0  4665.9     .12       0  4949.6     .07       0
    4978     .05       0  4983.4     .07       0  5026.3     .05       0
  5405.8     .07       0
Bank Sta=4978,4983.4
XS Rating Curve= 0 ,0
Exp/Cntr=0.3,0.1

Type RM Length L Ch R = 1 ,39738   ,332,332,332
BEGIN DESCRIPTION:
MITCHELL CREEK 55.0
END DESCRIPTION:
XS GIS Cut Line= 3
      2483874.99     13746574.99        2483125.       13745775.
        2482325.       13746325.
#Sta/Elev= 30
  3892.1  330.06  4038.8  323.58  4174.8  317.87  4238.7  316.08  4252.8  315.17
  4260.1  312.54  4422.8  311.72    4458  309.23  4597.7  306.93  4677.3  304.65
  4698.8  306.46  4741.3   302.9  4797.5  305.26    4840  304.87  4847.3  303.13
  4953.3  305.07  5000.9  303.51  5008.3  300.01  5008.8  299.51  5013.7  300.01
  5025.1  300.08    5032  302.63    5038  300.45  5052.9  301.12  5061.5  304.28
  5118.6  305.78  5404.6   307.2  5671.3  314.04  5814.7  324.55  5959.5  329.72
#Mann= 8 ,-1 , 0
  3892.1     .07       0  4038.8    .035       0  4174.8     .07       0
  4597.7     .12       0  5000.9     .05       0  5008.3     .05       0
  5013.7     .05       0  5404.6     .07       0
Bank Sta=5008.3,5013.7
XS Rating Curve= 0 ,0
Exp/Cntr=0.3,0.1

Type RM Length L Ch R = 1 ,39406   ,518,518,518
BEGIN DESCRIPTION:
B19615
END DESCRIPTION:
XS GIS Cut Line= 4
      2484240.66      13745819.3      2483122.09     13745484.61
      2482849.06     13745634.34      2482339.13     13746087.12
#Sta/Elev= 30
  3887.8  320.34  3943.4  318.27  3985.5  317.21  4029.8  314.87  4147.3  313.81
  4442.6   306.1  4580.6  303.96  4802.1  303.14  4965.2  303.74  4970.4  303.51
  4989.7  297.28  5003.5  299.67  5028.7  297.22  5029.1  296.72  5034.1  297.22
  5036.6  300.08  5051.2  303.82  5097.7  302.93  5187.3  305.59  5252.7   304.7
  5258.4  305.66  5268.7  305.07  5274.5  302.27  5280.2  305.24  5307.4  304.45
  5334.2  303.94    5434  306.71  5726.9  308.25  5795.2  309.18  6048.7  317.72
#Mann= 10 ,-1 , 0
  3887.8     .07       0  3943.4    .035       0  3985.5     .05       0
  4147.3     .07       0  4580.6     .12       0  4802.1      .1       0
  5028.7     .05       0  5034.1      .1       0  5307.4     .05       0
  5726.9     .07       0
Bank Sta=5028.7,5034.1
XS Rating Curve= 0 ,0
Exp/Cntr=0.3,0.1

Type RM Length L Ch R = 1 ,38888   ,422,422,422
BEGIN DESCRIPTION:
MITCHELL CREEK 54.0
END DESCRIPTION:
XS GIS Cut Line= 3
      2484274.98     13745774.99        2483475.       13745275.
      2483324.99     13744924.97
#Sta/Elev= 30
  4050.7  320.72    4203  314.92  4225.9   313.6  4379.5  310.66    4428  307.59
  4572.7  303.96  4639.7  303.19  4660.9  301.36  4751.9   301.3  4913.3  300.93
  4928.6  296.89    4944  301.16  4949.9  295.52  4958.7  296.31  4965.2  299.37
  4971.1  294.55  4976.8  294.49  4977.3  293.99  4984.2  294.49  4986.4  296.87
  4996.8  294.91  5003.1  300.11  5008.6  296.29  5015.8  300.75  5026.7  301.44
  5070.2  301.95  5146.4  299.69    5208   305.6  5313.8  309.52  5374.9  311.31
#Mann= 9 ,-1 , 0
  4050.7     .05       0    4203    .035       0  4225.9     .05       0
  4379.5     .07       0  4572.7     .12       0  4751.9      .1       0
  4976.8     .05       0  4984.2      .1       0  5313.8     .12       0
Bank Sta=4976.8,4984.2
XS Rating Curve= 0 ,0
Exp/Cntr=0.3,0.1