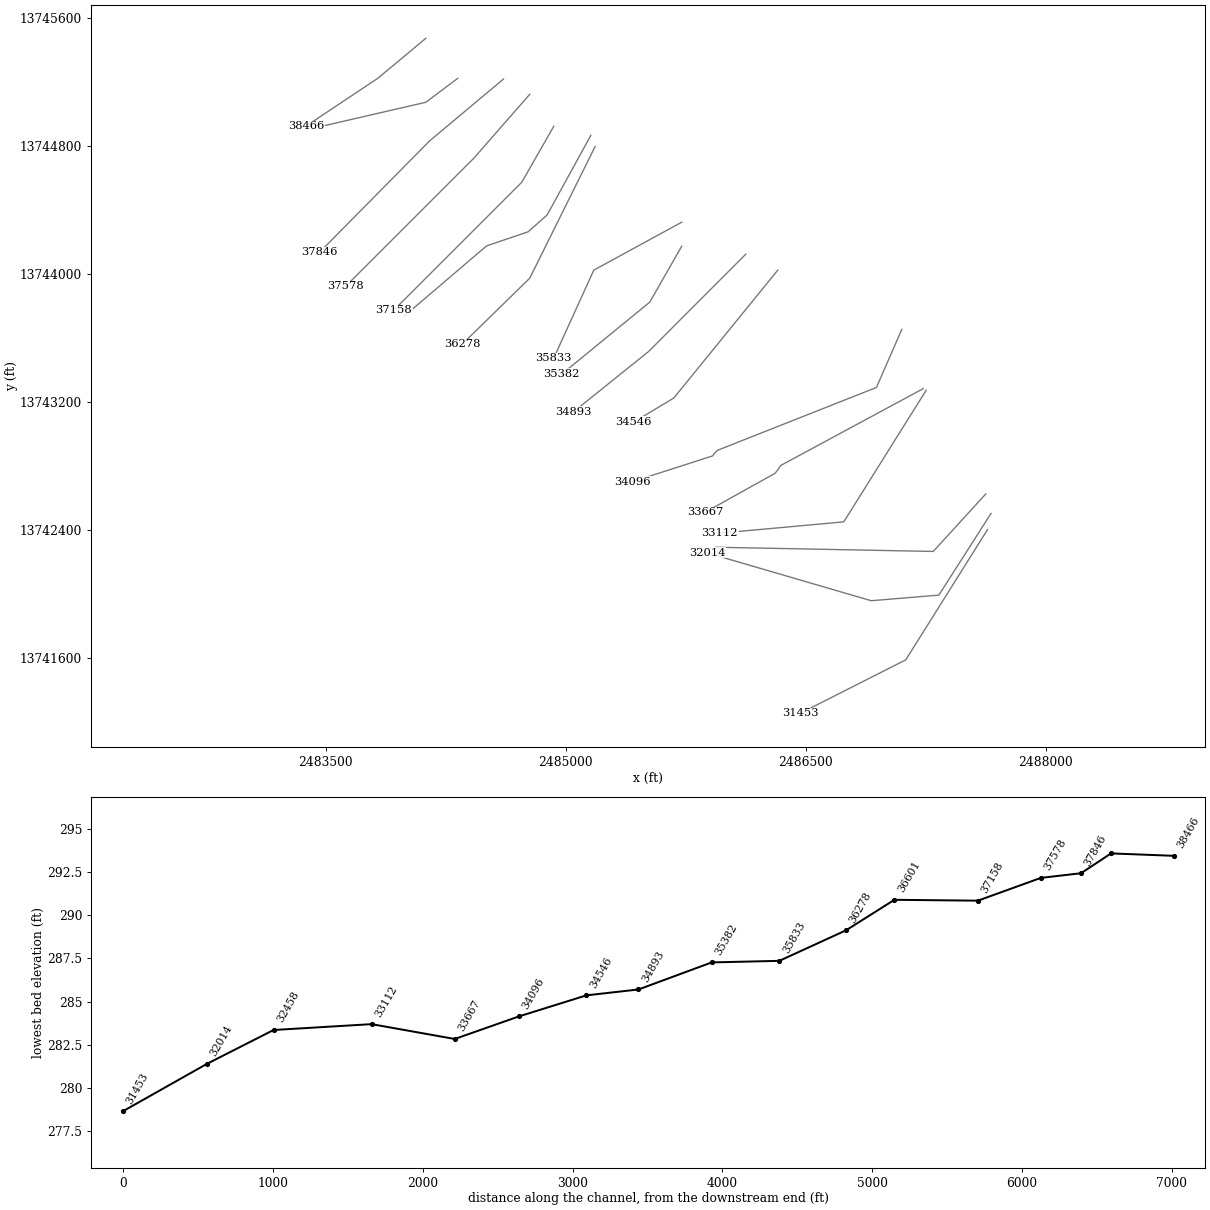
HEC-RAS study MITCHELL CREEK.prj: MITCHELL CREEK Base Level Engineering

--- MITCHELL CREEK.g01 (geometry) --- (continued)

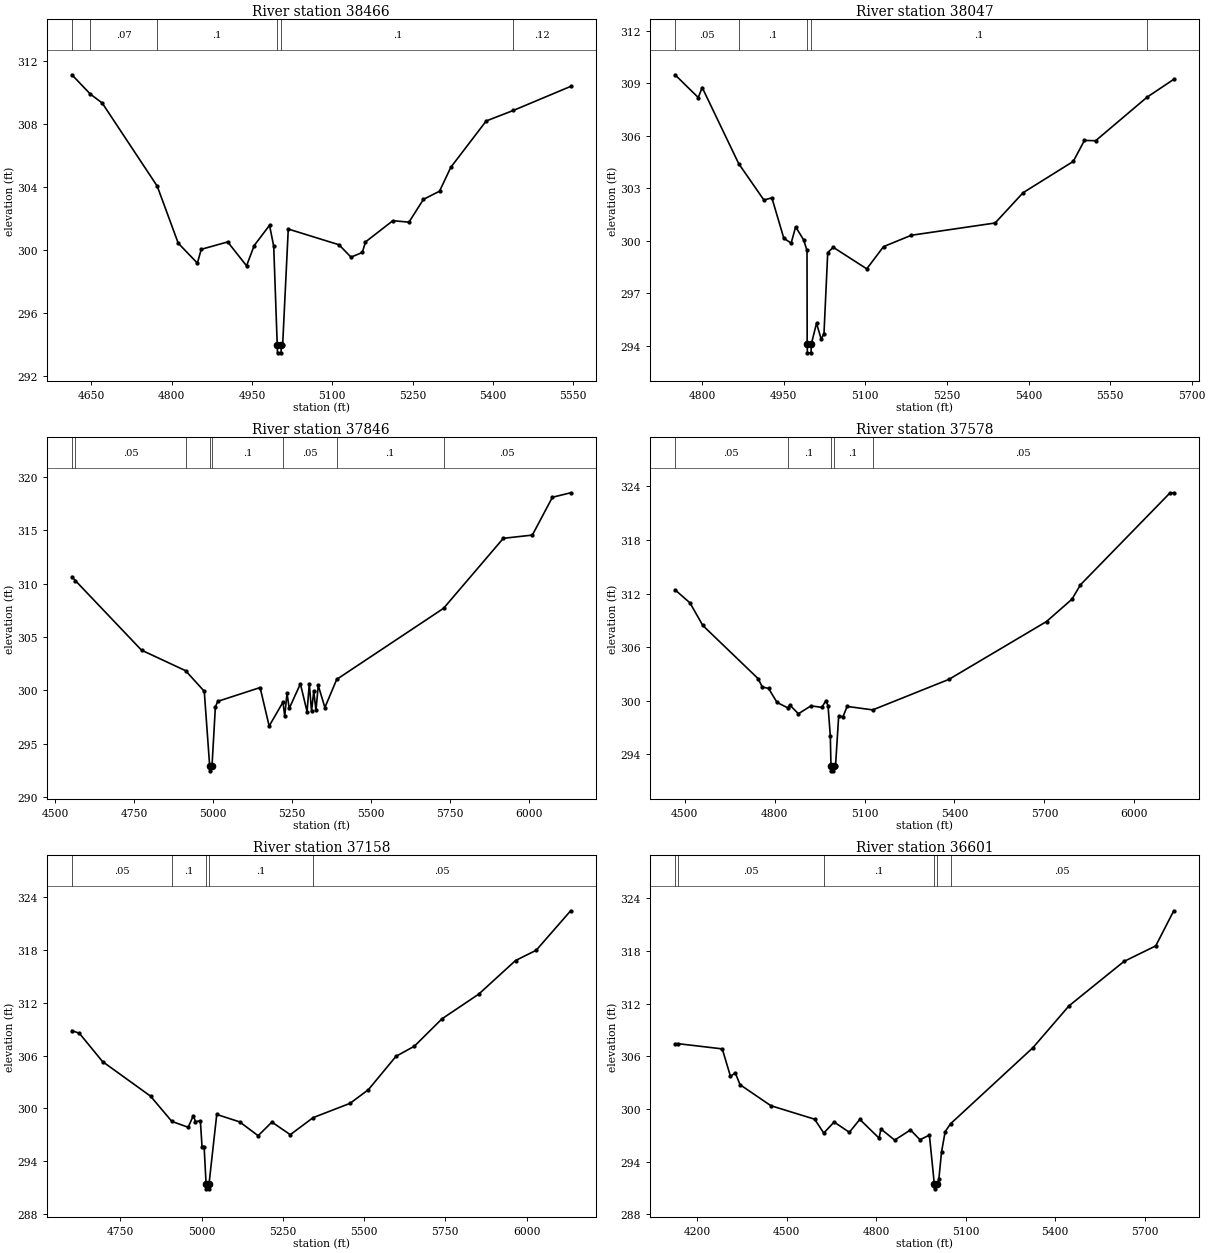
Type RM Length L Ch R = 1 ,38466   ,419,419,419
BEGIN DESCRIPTION:
MITCHELL CREEK 53.0
END DESCRIPTION:
XS GIS Cut Line= 3
      2484124.99     13745474.99        2483825.       13745225.
      2483375.03     13744925.02
#Sta/Elev= 30
  4613.9  311.15    4648  309.93  4670.5  309.35  4773.2  304.06  4812.4  300.43
  4848.2  299.16  4855.4  300.04  4904.8  300.51    4940  298.99  4954.3  300.28
  4982.9  301.57  4990.7  300.24  4997.3  293.95  4997.8  293.45  5004.4  293.45
  5004.9  293.95  5007.4  293.95  5017.9  301.33  5112.6  300.33  5135.1  299.54
  5156.1  299.84  5162.1  300.51  5213.2  301.86  5243.3  301.77  5270.3  303.22
  5300.4  303.74  5321.4  305.26  5387.5  308.21  5438.2  308.88  5545.2  310.41
#Mann= 6 ,-1 , 0
  4613.9    .035       0    4648     .07       0  4773.2      .1       0
  4997.3     .05       0  5004.9      .1       0  5438.2     .12       0
Bank Sta=4997.3,5004.9
XS Rating Curve= 0 ,0
Exp/Cntr=0.3,0.1

Type RM Length L Ch R = 1 ,38047   ,201,201,201
BEGIN DESCRIPTION:
MITCHELL CREEK 52.0
END DESCRIPTION:
XS GIS Cut Line= 3
      2484324.98     13745224.98        2484125.       13745075.
      2483474.96     13744924.99
#Sta/Elev= 30
    4750  309.48  4792.7  308.18    4800  308.75  4867.1   304.4  4913.5  302.32
  4928.1  302.45    4950  300.14  4963.5  299.86  4971.8  300.79  4986.4  300.05
  4992.7  299.44    4993  294.09  4993.5  293.59  5000.1  293.59  5000.6  294.09
  5010.2  295.28  5018.8  294.37  5023.9  294.69  5030.8  299.32    5041  299.62
  5102.6  298.39  5133.4  299.66  5184.7  300.31  5338.6  301.01    5390  302.74
  5482.3  304.53  5502.9  305.73  5523.4  305.71    5618   308.2  5667.1  309.22
#Mann= 5 ,-1 , 0
    4750     .05       0  4867.1      .1       0    4993     .05       0
  5000.6      .1       0    5618     .12       0
Bank Sta=4993,5000.6
XS Rating Curve= 0 ,0
Exp/Cntr=0.3,0.1

Type RM Length L Ch R = 1 ,37846   ,268,268,268
BEGIN DESCRIPTION:
B19614
END DESCRIPTION:
XS GIS Cut Line= 3
      2484610.57      13745220.4      2484148.16     13744832.86
      2483461.19     13744137.08
#Sta/Elev= 30
  4552.3  310.65    4563  310.29  4772.9  303.76  4912.8  301.83  4971.9   299.9
  4988.9  292.94  4989.4  292.44  4996.5  292.94  5007.1  298.44  5014.8  298.96
  5148.9  300.25  5177.6  296.64  5221.4  298.88    5227  297.58  5234.2  299.71
  5241.2  298.29  5276.6   300.6  5297.8  297.99  5304.9  300.62  5311.9  298.03
    5319   299.9    5326  298.11  5333.2  300.45  5354.3  298.38  5391.8  301.02
  5730.4  307.68    5920  314.25  6011.9  314.55  6075.6   318.1  6133.4  318.52
#Mann= 8 ,-1 , 0
  4552.3    .035       0    4563     .05       0  4912.8      .1       0
  4988.9     .05       0  4996.5      .1       0  5221.4     .05       0
  5391.8      .1       0  5730.4     .05       0
Bank Sta=4988.9,4996.5
XS Rating Curve= 0 ,0
Exp/Cntr=0.3,0.1

Type RM Length L Ch R = 1 ,37578   ,420,420,420
BEGIN DESCRIPTION:
MITCHELL CREEK 51.0
END DESCRIPTION:
XS GIS Cut Line= 3
      2484775.01     13745125.01        2484425.       13744725.
        2483625.       13743925.
#Sta/Elev= 30
  4468.2  312.43    4518  310.97  4560.8  308.44  4744.9   302.5  4759.1  301.56
    4780  301.39  4808.5  299.82  4843.4  299.23  4851.2  299.52  4879.7  298.56
  4921.4  299.44  4957.5  299.28  4971.7  300.03  4978.4  299.45    4986  296.05
  4988.2  292.67  4988.7  292.17  4996.5  292.17    4997  292.67  5003.3   292.7
  5013.9  298.33    5028  298.21  5042.1  299.38  5127.3  298.99  5381.6  302.41
  5706.8  308.88  5791.7  311.38    5820  312.99    6117  323.22  6131.1  323.29
#Mann= 5 ,-1 , 0
  4468.2     .05       0  4843.4      .1       0  4988.2     .05       0
    4997      .1       0  5127.3     .05       0
Bank Sta=4988.2,4997
XS Rating Curve= 0 ,0
Exp/Cntr=0.3,0.1

Type RM Length L Ch R = 1 ,37158   ,557,557,557
BEGIN DESCRIPTION:
MITCHELL CREEK 50.0
END DESCRIPTION:
XS GIS Cut Line= 3
      2484925.02     13744925.04        2484725.       13744575.
      2483925.02     13743775.02
#Sta/Elev= 30
  4601.1  308.85  4624.2  308.53  4695.4  305.32    4843  301.39  4908.5  298.52
  4958.9  297.85  4974.7  299.18  4981.2   298.5  4996.3  298.59  5001.4  295.66
  5007.8  295.66    5014  291.35  5014.5  290.85  5022.3  290.85  5022.8  291.35
  5046.7  299.31  5117.4  298.46    5174  296.89  5216.4  298.44    5273  297.01
  5343.4  298.95  5456.8  300.57  5513.4  302.13  5598.2  305.92  5654.8  307.07
  5739.6  310.18  5852.8  312.99  5965.9  316.81  6029.6  317.98  6135.6  322.47
#Mann= 5 ,-1 , 0
  4601.1     .05       0  4908.5      .1       0    5014     .05       0
  5022.8      .1       0  5343.4     .05       0
Bank Sta=5014,5022.8
XS Rating Curve= 0 ,0
Exp/Cntr=0.3,0.1

Type RM Length L Ch R = 1 ,36601   ,323,323,323
BEGIN DESCRIPTION:
B19613
END DESCRIPTION:
XS GIS Cut Line= 5
      2485156.62     13744868.09      2484883.58     13744370.47
      2484764.68     13744264.78      2484504.86      13744176.7
      2483994.04     13743740.74
#Sta/Elev= 30
  4125.3   307.4  4133.8  307.44  4283.7  306.84  4311.3  303.71  4327.3  304.11
  4343.4  302.76  4446.7  300.37  4593.6  298.83  4624.1  297.25  4658.8  298.51
  4709.9  297.34    4745  298.81  4809.4  296.68  4816.1  297.71  4861.9  296.45
    4915  297.61  4946.7  296.49  4978.4  297.02    4995   291.4  4995.5   290.9
  5003.9   291.4    5010  291.98    5019  295.08  5031.2  297.41  5049.3  298.31
  5325.7  306.98  5446.5  311.74  5630.9   316.8  5737.4  318.57  5797.9  322.57
#Mann= 6 ,-1 , 0
  4125.3     .07       0  4133.8     .05       0  4624.1      .1       0
    4995     .05       0  5003.9      .1       0  5049.3     .05       0
Bank Sta=4995,5003.9
XS Rating Curve= 0 ,0
Exp/Cntr=0.3,0.1

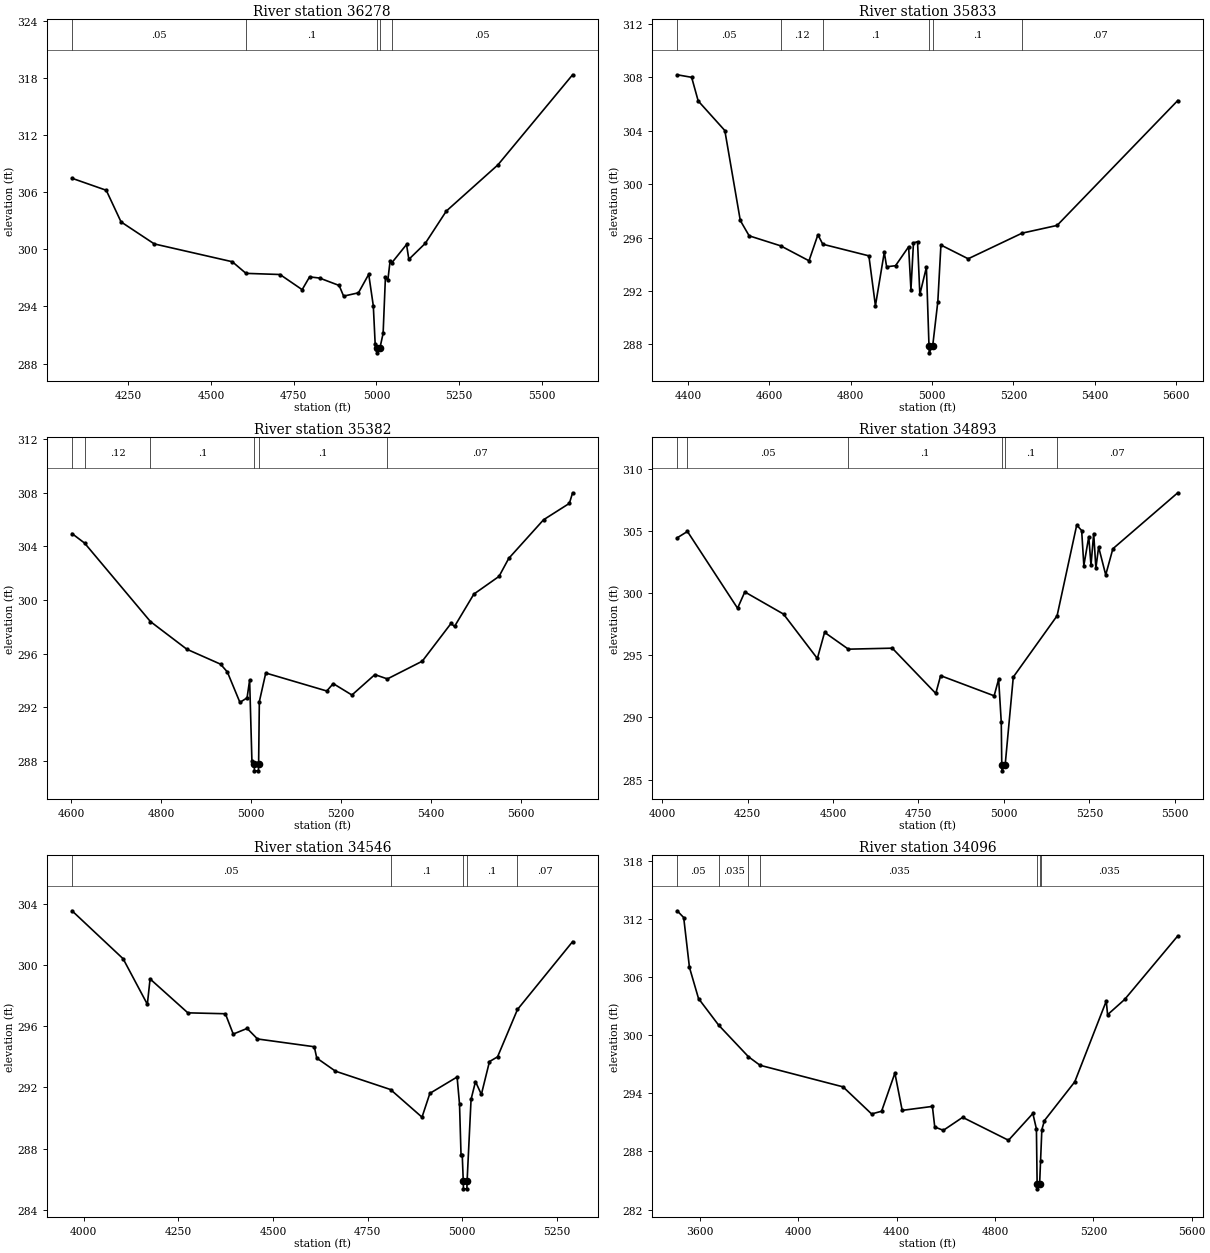
Type RM Length L Ch R = 1 ,36278   ,445,445,445
BEGIN DESCRIPTION:
MITCHELL CREEK 49.0
END DESCRIPTION:
XS GIS Cut Line= 3
      2485183.05     13744797.65        2484775.       13743975.
       2484350.7     13743560.15
#Sta/Elev= 30
  4080.5  307.45  4183.9  306.19  4228.6  302.87    4329  300.56  4564.5  298.69
  4605.9  297.47  4708.6  297.35  4775.5  295.76  4797.9   297.1  4827.9  296.98
  4887.2   296.2  4900.7  295.08  4945.5  295.43  4976.5  297.37  4990.4  294.06
    4996  290.05  5001.4  289.63  5001.9  289.13  5010.3  289.63    5020  291.18
    5027  297.12  5034.2  296.74  5041.1  298.78  5046.5  298.59  5090.7   300.5
  5097.7  298.94  5147.3  300.62  5210.9  304.01  5366.5  308.85  5592.2  318.31
#Mann= 5 ,-1 , 0
  4080.5     .05       0  4605.9      .1       0  5001.4     .05       0
  5010.3      .1       0  5046.5     .05       0
Bank Sta=5001.4,5010.3
XS Rating Curve= 0 ,0
Exp/Cntr=0.3,0.1

Type RM Length L Ch R = 1 ,35833   ,451,451,451
BEGIN DESCRIPTION:
MITCHELL CREEK 48.0
END DESCRIPTION:
XS GIS Cut Line= 3
      2485724.98     13744324.99        2485175.       13744025.
      2484925.01     13743475.02
#Sta/Elev= 30
  4373.2   308.2  4408.8  308.01  4424.9  306.24  4490.4  304.02  4528.4  297.28
  4550.2  296.13  4627.6  295.38  4697.3  294.26  4719.2  296.21  4731.2   295.5
  4844.5  294.63  4860.6  290.89  4882.4   294.9  4888.1  293.81    4910  293.89
  4942.2  295.31  4947.9  292.09  4954.1   295.6  4964.1  295.69  4969.8  291.74
  4985.9  293.77  4992.3  287.86  4992.8  287.36  5001.3  287.86    5014   291.2
  5021.6  295.44  5088.6  294.41  5221.1  296.33  5307.2  296.91  5603.8  306.27
#Mann= 6 ,-1 , 0
  4373.2     .05       0  4627.6     .12       0  4731.2      .1       0
  4992.3     .05       0  5001.3      .1       0  5221.1     .07       0
Bank Sta=4992.3,5001.3
XS Rating Curve= 0 ,0
Exp/Cntr=0.3,0.1

Type RM Length L Ch R = 1 ,35382   ,489,489,489
BEGIN DESCRIPTION:
MITCHELL CREEK 47.0
END DESCRIPTION:
XS GIS Cut Line= 3
      2485725.02     13744175.04        2485525.       13743825.
      2484974.99     13743374.99
#Sta/Elev= 30
  4601.8  304.95  4629.8  304.24  4776.4  298.39  4857.4  296.33  4932.2  295.22
  4947.4  294.64  4975.4  292.37  4991.3  292.71    4997  294.03  5002.1     288
  5007.2  287.77  5007.7  287.27  5016.5  287.27    5017  287.77  5018.6  292.43
  5032.9  294.56  5168.6  293.22    5183  293.77  5224.6  292.92  5275.6  294.44
  5303.5  294.12  5381.1  295.44    5445  298.25  5452.9  298.03  5495.9  300.44
  5551.9  301.76  5573.5   303.1    5651  305.98  5708.4   307.2  5715.6  307.99
#Mann= 6 ,-1 , 0
  4601.8     .05       0  4629.8     .12       0  4776.4      .1       0
  5007.2     .05       0    5017      .1       0  5303.5     .07       0
Bank Sta=5007.2,5017
XS Rating Curve= 0 ,0
Exp/Cntr=0.3,0.1

Type RM Length L Ch R = 1 ,34893   ,347,347,347
BEGIN DESCRIPTION:
MITCHELL CREEK 46.0
END DESCRIPTION:
XS GIS Cut Line= 3
      2486124.97     13744124.97      2485517.72     13743516.14
      2485046.54     13743137.44
#Sta/Elev= 30
  4044.1  304.43  4074.2  304.94  4220.8  298.77    4242  300.08  4355.2   298.3
  4454.2  294.73  4475.4  296.83    4545  295.48  4673.4  295.56  4800.7  291.92
  4814.8  293.35  4971.4  291.73  4984.5  293.07  4992.2  289.62  4993.7   286.2
  4994.2   285.7  5003.7   286.2  5027.4  293.24  5155.5  298.16    5213  305.46
  5227.4  305.01  5233.8   302.2  5248.2  304.52  5254.7  302.22  5262.6  304.77
    5269  301.99    5277  303.69  5297.8  301.45  5318.7  303.55  5508.5  308.05
#Mann= 6 ,-1 , 0
  4044.1    .035       0  4074.2     .05       0    4545      .1       0
  4993.7     .05       0  5003.7      .1       0  5155.5     .07       0
Bank Sta=4993.7,5003.7
XS Rating Curve= 0 ,0
Exp/Cntr=0.3,0.1

Type RM Length L Ch R = 1 ,34546   ,450,450,450
BEGIN DESCRIPTION:
MITCHELL CREEK 45.0
END DESCRIPTION:
XS GIS Cut Line= 3
        2486325.       13744025.        2485675.       13743225.
      2485425.02     13743075.01
#Sta/Elev= 30
    3969  303.56    4104  300.42    4168  297.44  4175.2   299.1    4275  296.88
  4374.1  296.82  4394.9  295.49  4431.6  295.86  4458.9  295.17    4609  294.66
  4615.5  293.92    4665  293.06  4810.3  291.86  4893.5  290.05  4914.3  291.61
  4986.2  292.68  4992.6   290.9  4996.6  287.57  4999.8  287.57  5002.5  285.86
    5003  285.36  5012.1  285.36  5012.6  285.86  5023.1  291.22  5034.8  292.38
  5050.3  291.54  5071.7  293.69  5093.1     294  5145.7   297.1  5291.3  301.54
#Mann= 5 ,-1 , 0
    3969     .05       0  4810.3      .1       0  5002.5     .05       0
  5012.6      .1       0  5145.7     .07       0
Bank Sta=5002.5,5012.6
XS Rating Curve= 0 ,0
Exp/Cntr=0.3,0.1

Type RM Length L Ch R = 1 ,34096   ,429,429,429
BEGIN DESCRIPTION:
MITCHELL CREEK 44.0
END DESCRIPTION:
XS GIS Cut Line= 6
      2487100.52     13743654.66      2486941.71     13743291.14
      2485948.01     13742898.01        2485925.       13742875.
      2485919.33     13742863.66      2485418.65     13742702.28
#Sta/Elev= 30
  3506.9  312.88  3533.5  312.18  3556.9  307.03  3593.8  303.81  3675.7  301.06
  3797.1  297.79  3844.2  296.91  4181.8  294.68    4298  291.88  4338.6  292.16
  4392.7   296.1  4422.4  292.25  4545.3  292.66  4554.9  290.53    4590  290.19
  4668.4  291.53  4854.9  289.16    4954  291.93  4968.5  290.33  4971.4  284.64
  4971.9  284.14  4981.5  284.64  4985.3  286.99  4990.6  290.26  5001.2   291.2
  5124.5   295.2  5252.7  303.55    5258  302.14  5327.3  303.71  5543.5  310.28
#Mann= 7 ,-1 , 0
  3506.9     .05       0  3675.7    .035       0  3797.1     .05       0
  3844.2    .035       0  4971.4    .035       0  4981.5    .035       0
  4985.3    .035       0
Bank Sta=4971.4,4981.5
XS Rating Curve= 0 ,0
Exp/Cntr=0.3,0.1

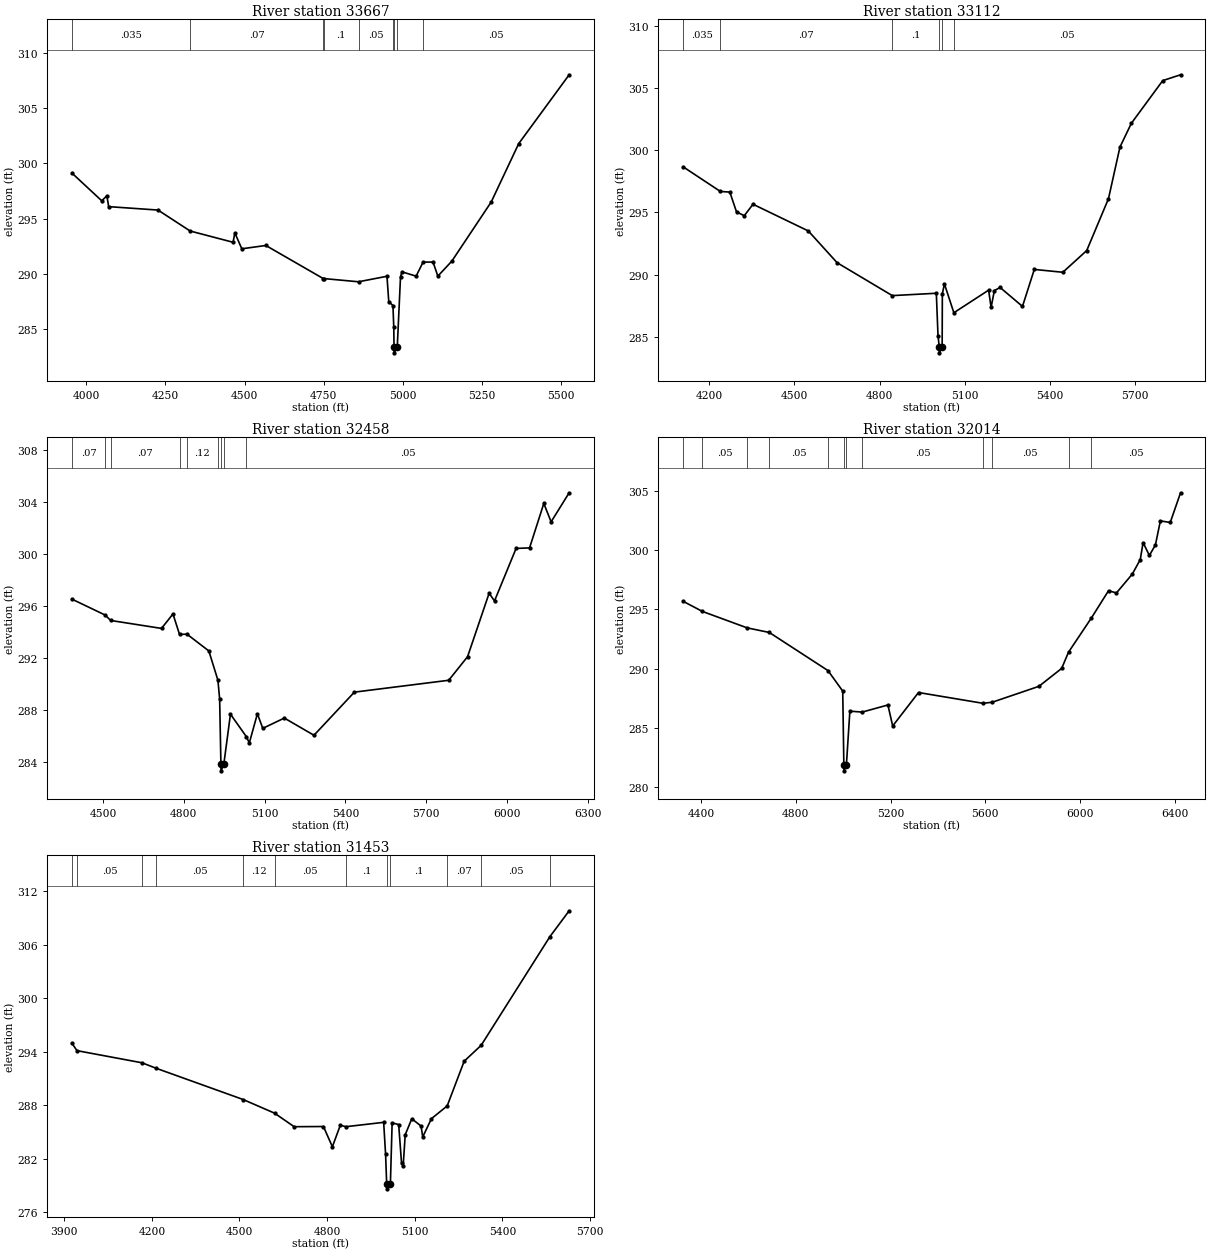
Type RM Length L Ch R = 1 ,33667   ,555,555,555
BEGIN DESCRIPTION:
MITCHELL CREEK 43.0
END DESCRIPTION:
XS GIS Cut Line= 5
      2487234.61     13743284.09      2486342.23     13742802.57
        2486325.       13742775.      2486307.47     13742753.96
      2485872.49     13742511.28
#Sta/Elev= 30
    3954  299.13  4048.5  296.61  4064.7  297.06  4070.4  296.08  4226.3  295.77
    4328  293.87  4463.6  292.85  4469.3   293.7  4491.2  292.26  4567.2  292.56
  4749.4  289.55    4751  289.56  4860.2  289.27  4950.1  289.77  4955.8  287.46
    4969  287.12  4971.6  285.13  4972.4  283.33  4972.9  282.83  4982.6  283.33
  4992.9  289.72  4997.6  290.17  5042.2  289.78  5064.2  291.05  5095.7  291.06
  5110.9  289.78  5155.1  291.14  5279.6   296.5  5366.5  301.79    5526  308.03
#Mann= 9 ,-1 , 0
    3954    .035       0    4328     .07       0  4749.4    .035       0
    4751      .1       0  4860.2     .05       0    4969      .1       0
  4972.4     .05       0  4982.6      .1       0  5064.2     .05       0
Bank Sta=4972.4,4982.6
XS Rating Curve= 0 ,0
Exp/Cntr=0.3,0.1

Type RM Length L Ch R = 1 ,33112   ,654,654,654
BEGIN DESCRIPTION:
B19612
END DESCRIPTION:
XS GIS Cut Line= 3
      2487252.81     13743273.96      2486737.55     13742450.44
      2485962.58     13742379.99
#Sta/Elev= 30
  4109.5  298.67  4240.2  296.69  4273.4  296.64    4297  295.04  4324.3  294.74
    4355  295.66  4549.5  293.51  4650.9  290.95    4845   288.3  4999.9  288.49
  5005.8  285.08  5010.1  284.19  5010.6  283.69  5020.4  284.19  5021.1  288.45
  5028.4  289.24  5061.6  286.92  5183.9  288.74  5192.6  287.35    5204   288.7
  5224.1  288.96    5303  287.43  5344.6  290.41    5445  290.18    5529  291.93
  5605.6  296.11  5645.8  300.26    5686  302.18  5796.4  305.62  5859.1  306.09
#Mann= 6 ,-1 , 0
  4109.5    .035       0  4240.2     .07       0    4845      .1       0
  5010.1     .05       0  5020.4      .1       0  5061.6     .05       0
Bank Sta=5010.1,5020.4
XS Rating Curve= 0 ,0
Exp/Cntr=0.3,0.1

Type RM Length L Ch R = 1 ,32458   ,444,444,444
BEGIN DESCRIPTION:
MITCHELL CREEK 42.0
END DESCRIPTION:
XS GIS Cut Line= 3
      2487625.02     13742625.02      2487296.83     13742265.48
      2485937.99     13742291.87
#Sta/Elev= 30
  4384.3  296.53  4507.5  295.31  4528.6  294.89  4717.1  294.28  4759.6  295.39
    4784  293.82  4811.5  293.84  4892.9  292.55  4926.5   290.3  4932.9  288.86
  4937.6  283.85  4938.1  283.35  4948.3  283.85    4973   287.7  5032.1  285.97
    5043  285.49    5073  287.73    5093  286.61    5173   287.4    5283  286.08
    5433  289.39  5783.1   290.3  5853.1  292.11  5933.1  296.98  5953.1  296.39
  6033.2  300.42  6083.2  300.46  6136.1  303.87  6163.2  302.46  6230.2  304.69
#Mann= 9 ,-1 , 0
  4384.3     .07       0  4507.5     .05       0  4528.6     .07       0
    4784     .05       0  4811.5     .12       0  4926.5      .1       0
  4937.6     .05       0  4948.3      .1       0  5032.1     .05       0
Bank Sta=4937.6,4948.3
XS Rating Curve= 0 ,0
Exp/Cntr=0.3,0.1

Type RM Length L Ch R = 1 ,32014   ,561,561,561
BEGIN DESCRIPTION:
B19611
END DESCRIPTION:
XS GIS Cut Line= 4
      2487657.94     13742503.29      2487332.06     13741992.45
       2486909.3     13741957.22      2485883.26     13742256.67
#Sta/Elev= 30
    4325  295.67  4406.2  294.82  4594.3  293.44  4688.3  293.05  4935.8  289.84
  4998.2  288.11  5002.9  281.89  5003.4  281.39  5013.7  281.89  5028.3  286.42
  5080.2  286.34  5188.9  286.94    5209  285.17    5318  287.99  5590.3  287.08
  5628.9  287.17  5826.1  288.51  5922.2  290.02  5951.2  291.39    6048  294.28
  6120.1  296.57  6153.4  296.38  6220.4  297.97  6253.9  299.19  6265.9  300.62
  6292.5  299.54    6318  300.43  6338.8  302.45  6380.5  302.32    6424  304.82
#Mann= 12 ,-1 , 0
    4325     .07       0  4406.2     .05       0  4594.3     .07       0
  4688.3     .05       0  4935.8     .12       0  5002.9     .05       0
  5013.7     .12       0  5080.2     .05       0  5590.3      .1       0
  5628.9     .05       0  5951.2     .12       0    6048     .05       0
Bank Sta=5002.9,5013.7
XS Rating Curve= 0 ,0
Exp/Cntr=0.3,0.1

Type RM Length L Ch R = 1 ,31453   ,562,562,562
BEGIN DESCRIPTION:
B19610
END DESCRIPTION:
XS GIS Cut Line= 3
      2487635.91     13742401.99      2487125.08     13741587.31
      2486464.52     13741252.62
#Sta/Elev= 30
  3926.2  294.98  3943.9  294.14  4166.2  292.78  4214.2  292.17  4512.4  288.66
  4619.9  287.13  4687.1  285.61  4787.3  285.63  4817.9  283.36    4845  285.77
  4864.4  285.61  4993.4   286.1    5000  282.51  5003.8  279.14  5004.3  278.64
  5016.4  279.14  5022.4  286.04  5044.8  285.85  5054.6  281.52  5060.2  281.22
  5067.2  284.71  5089.7   286.5  5121.5  285.68  5127.1  284.46  5156.9  286.51
  5210.8  287.94    5269  292.96  5326.9  294.73  5562.2  306.92  5628.3  309.83
#Mann= 12 ,-1 , 0
  3926.2     .07       0  3943.9     .05       0  4166.2     .07       0
  4214.2     .05       0  4512.4     .12       0  4619.9     .05       0
  4864.4      .1       0  5003.8     .05       0  5016.4      .1       0
  5210.8     .07       0  5326.9     .05       0  5562.2     .07       0
Bank Sta=5003.8,5016.4
XS Rating Curve= 0 ,0
Exp/Cntr=0.3,0.1