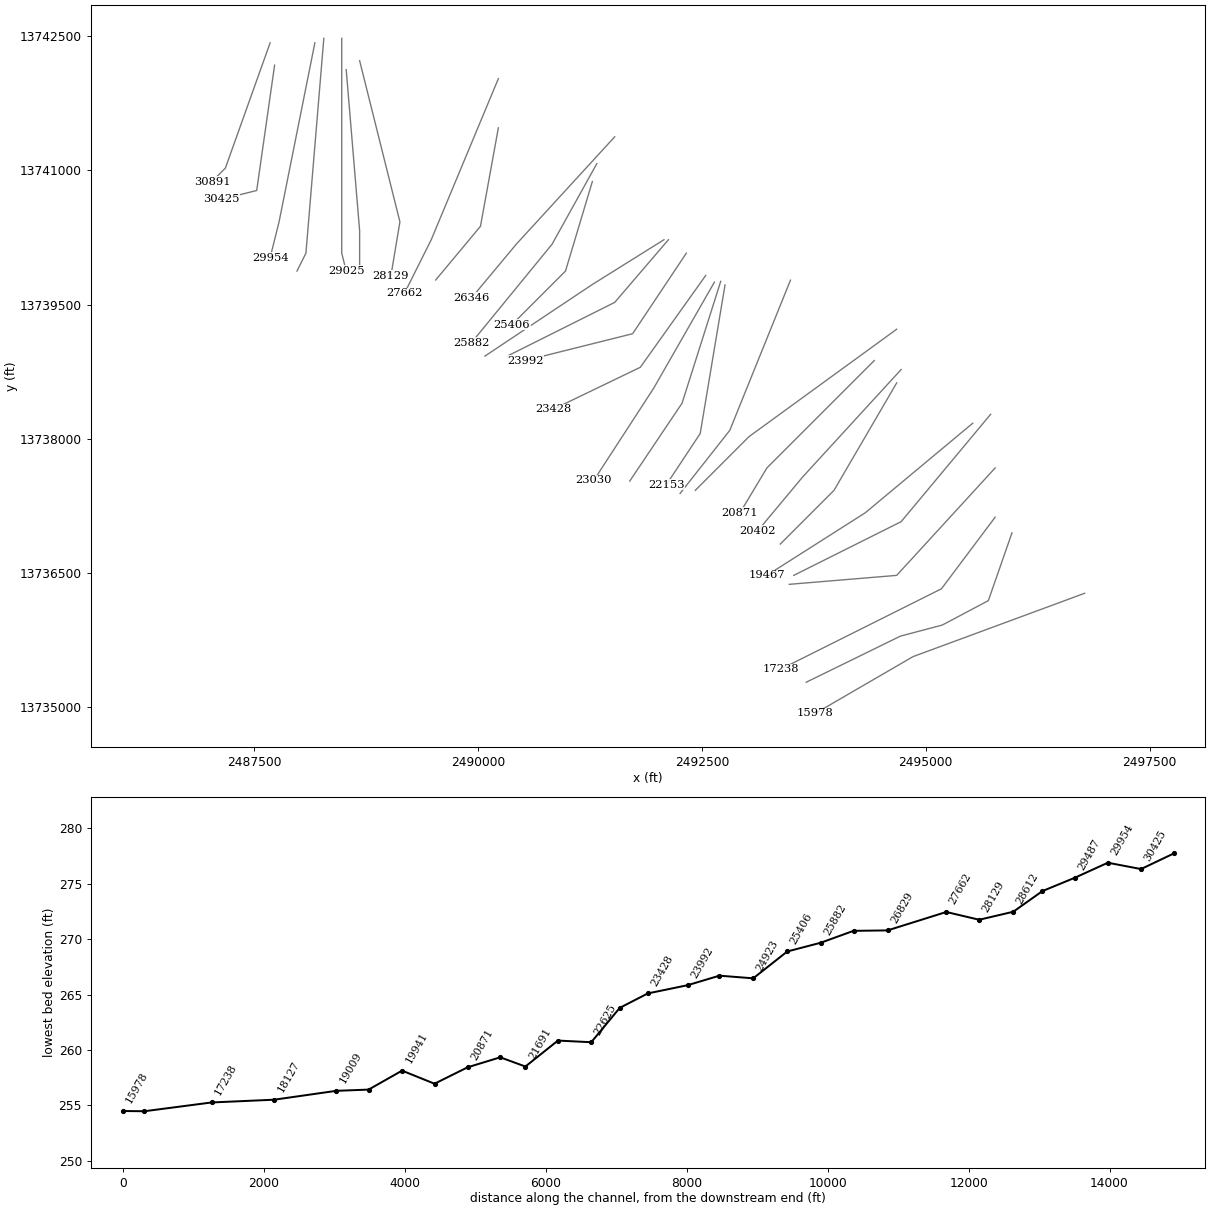
HEC-RAS study MITCHELL CREEK.prj: MITCHELL CREEK Base Level Engineering

--- MITCHELL CREEK.g01 (geometry) --- (continued)

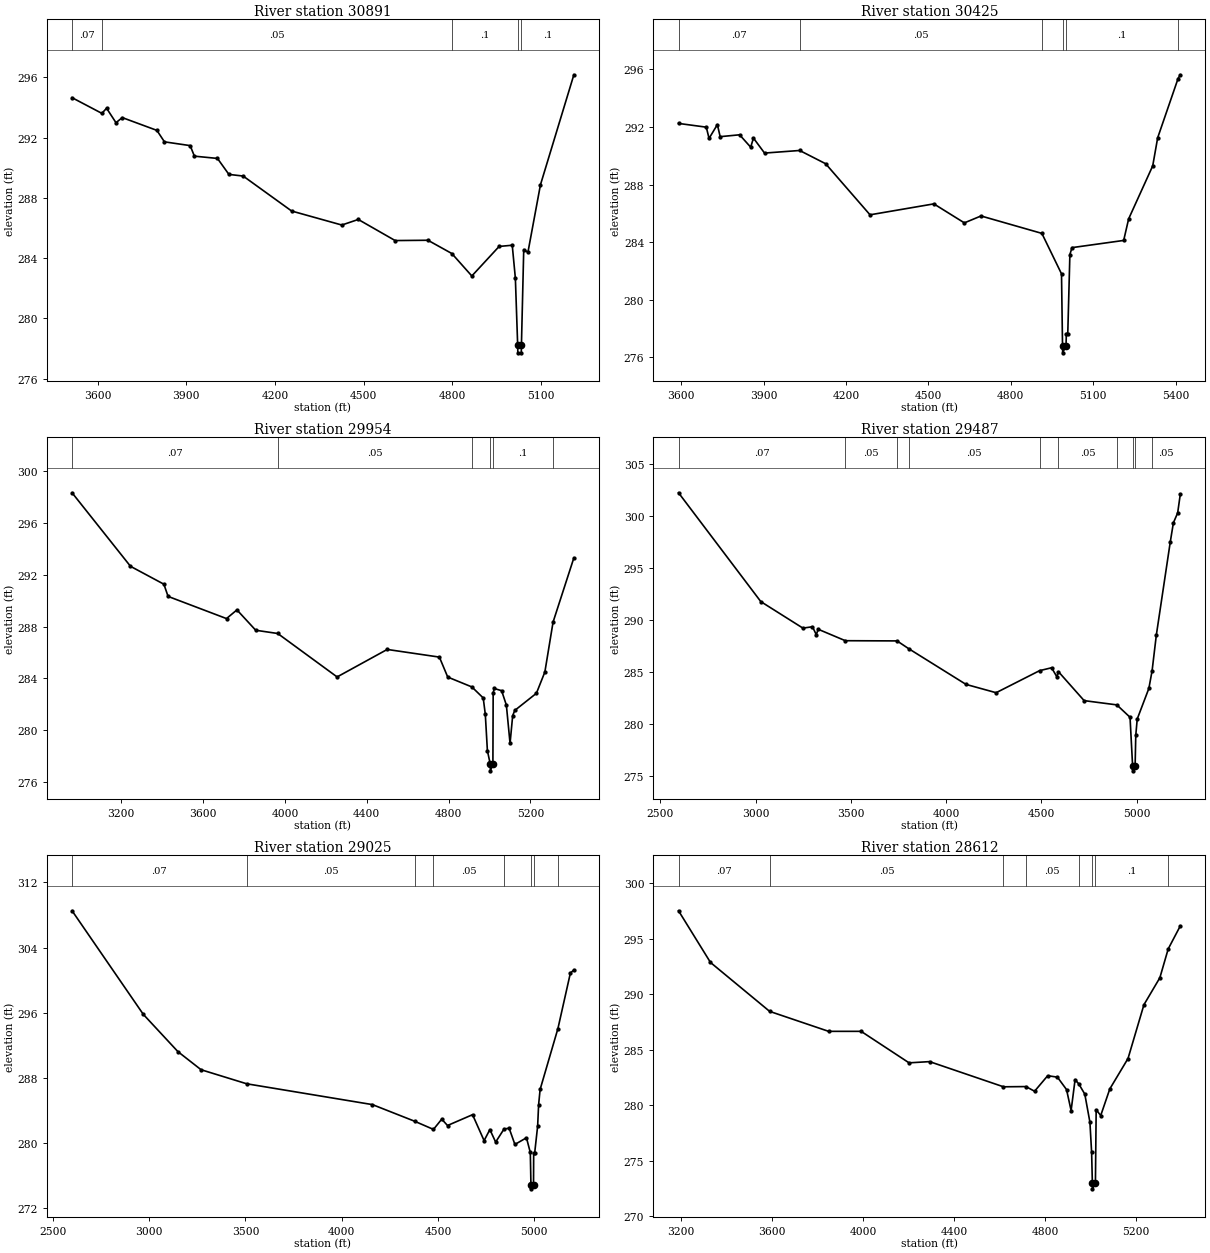
Type RM Length L Ch R = 1 ,30891   ,466,466,466
BEGIN DESCRIPTION:
MITCHELL CREEK 41.0
END DESCRIPTION:
XS GIS Cut Line= 3
        2487675.     13742424.99        2487175.       13741025.
      2487025.02     13740875.02
#Sta/Elev= 30
  3513.4  294.65  3614.3  293.61  3630.2  293.95  3662.1  292.99  3683.3  293.33
  3800.6  292.48  3826.1  291.72  3913.2  291.47  3927.5  290.77  4005.6  290.62
  4044.3  289.56  4092.6  289.45  4256.7  287.13  4426.6   286.2  4482.3  286.57
  4607.1  285.17  4718.1  285.19    4799  284.31  4866.7  282.82  4959.1  284.78
  5003.5  284.86  5014.1  282.67  5021.9  278.22  5022.4  277.72  5034.1  277.72
  5034.6  278.22  5042.4  284.57  5056.6  284.39    5099  288.87  5212.1  296.17
#Mann= 5 ,-1 , 0
  3513.4     .07       0  3614.3     .05       0    4799      .1       0
  5021.9     .05       0  5034.6      .1       0
Bank Sta=5021.9,5034.6
XS Rating Curve= 0 ,0
Exp/Cntr=0.3,0.1

Type RM Length L Ch R = 1 ,30425   ,471,471,471
BEGIN DESCRIPTION:
MITCHELL CREEK 40.0
END DESCRIPTION:
XS GIS Cut Line= 3
        2487725.     13742174.98        2487525.       13740775.
        2487125.       13740675.
#Sta/Elev= 30
  3590.6  292.25  3691.6  291.99  3701.7  291.21    3732  292.17  3742.1  291.33
  3812.8  291.46  3853.2   290.6  3863.3  291.23  3903.7  290.19  4031.5  290.37
    4126  289.45  4287.6   285.9  4519.9  286.66    4631  285.34  4691.6  285.82
  4913.1  284.61  4984.6   281.8  4988.3  276.81  4988.8  276.31    5001  276.81
  5002.3  277.65  5007.4  277.65  5015.1  283.14  5022.8  283.62  5210.9  284.12
    5229  285.62  5316.6   289.3  5334.6  291.25  5408.9  295.37  5417.1  295.63
#Mann= 6 ,-1 , 0
  3590.6     .07       0  4031.5     .05       0  4913.1      .1       0
  4988.3     .05       0    5001      .1       0  5408.9     .07       0
Bank Sta=4988.3,5001
XS Rating Curve= 0 ,0
Exp/Cntr=0.3,0.1

Type RM Length L Ch R = 1 ,29954   ,467,467,467
BEGIN DESCRIPTION:
MITCHELL CREEK 39.0
END DESCRIPTION:
XS GIS Cut Line= 3
        2488175.     13742424.99        2487775.       13740425.
        2487675.     13740025.01
#Sta/Elev= 30
  2960.1  298.32  3245.6  292.65  3408.8  291.27  3429.2  290.33  3714.7  288.62
  3765.7  289.29  3857.5  287.72    3965  287.47  4255.2  284.12    4500  286.24
  4754.9  285.65  4795.7  284.11  4913.5  283.35  4969.1   282.5  4979.3  281.24
  4989.5  278.44  5003.7  277.38  5004.2  276.88  5016.4  277.38  5017.7  282.88
  5022.9  283.23    5059  283.06  5082.2  281.95  5100.2     279  5113.1  281.14
  5123.4  281.54    5229  282.86  5270.3   284.5  5310.4  288.35    5412   293.3
#Mann= 6 ,-1 , 0
  2960.1     .07       0    3965     .05       0  4913.5      .1       0
  5003.7     .05       0  5016.4      .1       0  5310.4     .07       0
Bank Sta=5003.7,5016.4
XS Rating Curve= 0 ,0
Exp/Cntr=0.3,0.1

Type RM Length L Ch R = 1 ,29487   ,462,462,462
BEGIN DESCRIPTION:
MITCHELL CREEK 38.0
END DESCRIPTION:
XS GIS Cut Line= 3
        2488275.     13742475.05        2488075.       13740075.
      2487974.99     13739874.97
#Sta/Elev= 30
  2596.2  302.26  3027.7   291.8  3248.5  289.25  3298.7  289.38  3318.7  288.62
  3328.8  289.14  3471.1  288.04  3742.4  288.02  3802.9  287.28    4104  283.84
    4262  283.04  4489.9  285.16    4553  285.44  4580.6  284.57    4589  285.06
  4723.6  282.28  4895.1  281.87  4964.4  280.68  4977.8  276.03  4978.3  275.53
  4991.1  276.03  4994.5  278.94  5002.1  280.51  5063.3  283.46  5080.2  285.16
  5102.4  288.59  5175.1  297.49  5191.8  299.37  5214.2  300.32  5228.2  302.14
#Mann= 10 ,-1 , 0
  2596.2     .07       0  3471.1     .05       0  3742.4    .035       0
  3802.9     .05       0  4489.9    .035       0    4589     .05       0
  4895.1      .1       0  4977.8     .05       0  4991.1      .1       0
  5080.2     .05       0
Bank Sta=4977.8,4991.1
XS Rating Curve= 0 ,0
Exp/Cntr=0.3,0.1

Type RM Length L Ch R = 1 ,29025   ,413,413,413
BEGIN DESCRIPTION:
MITCHELL CREEK 37.0
END DESCRIPTION:
XS GIS Cut Line= 3
        2488475.     13742475.02        2488475.       13740075.
      2488525.01     13739874.97
#Sta/Elev= 30
  2599.4  308.52  2969.4  295.78  3149.4  291.19  3269.4  288.97  3506.6  287.24
  4159.4  284.68    4378  282.64  4476.4  281.63  4519.4  282.89  4549.4  282.11
  4679.4  283.44  4739.4  280.25  4769.4  281.61  4799.4  280.07  4842.7  281.67
  4869.4  281.78  4899.4  279.78  4959.4   280.6  4979.4  278.79  4982.7  274.82
  4983.2  274.32  4996.1  274.82  4996.9  278.71    5002  278.71  5017.5  282.04
  5022.6  284.68  5030.3  286.54  5122.9  294.04  5187.5  300.86  5205.6  301.24
#Mann= 8 ,-1 , 0
  2599.4     .07       0  3506.6     .05       0    4378    .035       0
  4476.4     .05       0  4842.7      .1       0  4982.7     .05       0
  4996.1      .1       0  5122.9     .05       0
Bank Sta=4982.7,4996.1
XS Rating Curve= 0 ,0
Exp/Cntr=0.3,0.1

Type RM Length L Ch R = 1 ,28612   ,483,483,483
BEGIN DESCRIPTION:
MITCHELL CREEK 36.0
END DESCRIPTION:
XS GIS Cut Line= 3
        2488525.     13742125.01        2488675.       13740325.
        2488675.     13739925.05
#Sta/Elev= 30
  3189.1  297.53  3329.6  292.87  3589.7  288.46  3848.9  286.66  3991.9  286.66
  4202.6  283.82  4292.9  283.93  4617.8  281.66  4716.4  281.68  4754.5  281.26
  4812.2  282.66  4854.9  282.53    4895  281.41  4915.1  279.52  4932.6  282.31
  4948.8  281.92  4975.3     281  4997.8  278.47  5005.3  275.74  5008.6  272.96
  5009.1  272.46    5022  272.96  5025.3  279.59  5045.3  279.07  5085.3  281.47
  5165.3  284.21  5235.3  289.06  5305.3  291.49    5342  294.09  5395.3  296.17
#Mann= 8 ,-1 , 0
  3189.1     .07       0  3589.7     .05       0  4617.8    .035       0
  4716.4     .05       0  4948.8      .1       0  5008.6     .05       0
    5022      .1       0    5342     .05       0
Bank Sta=5008.6,5022
XS Rating Curve= 0 ,0
Exp/Cntr=0.3,0.1

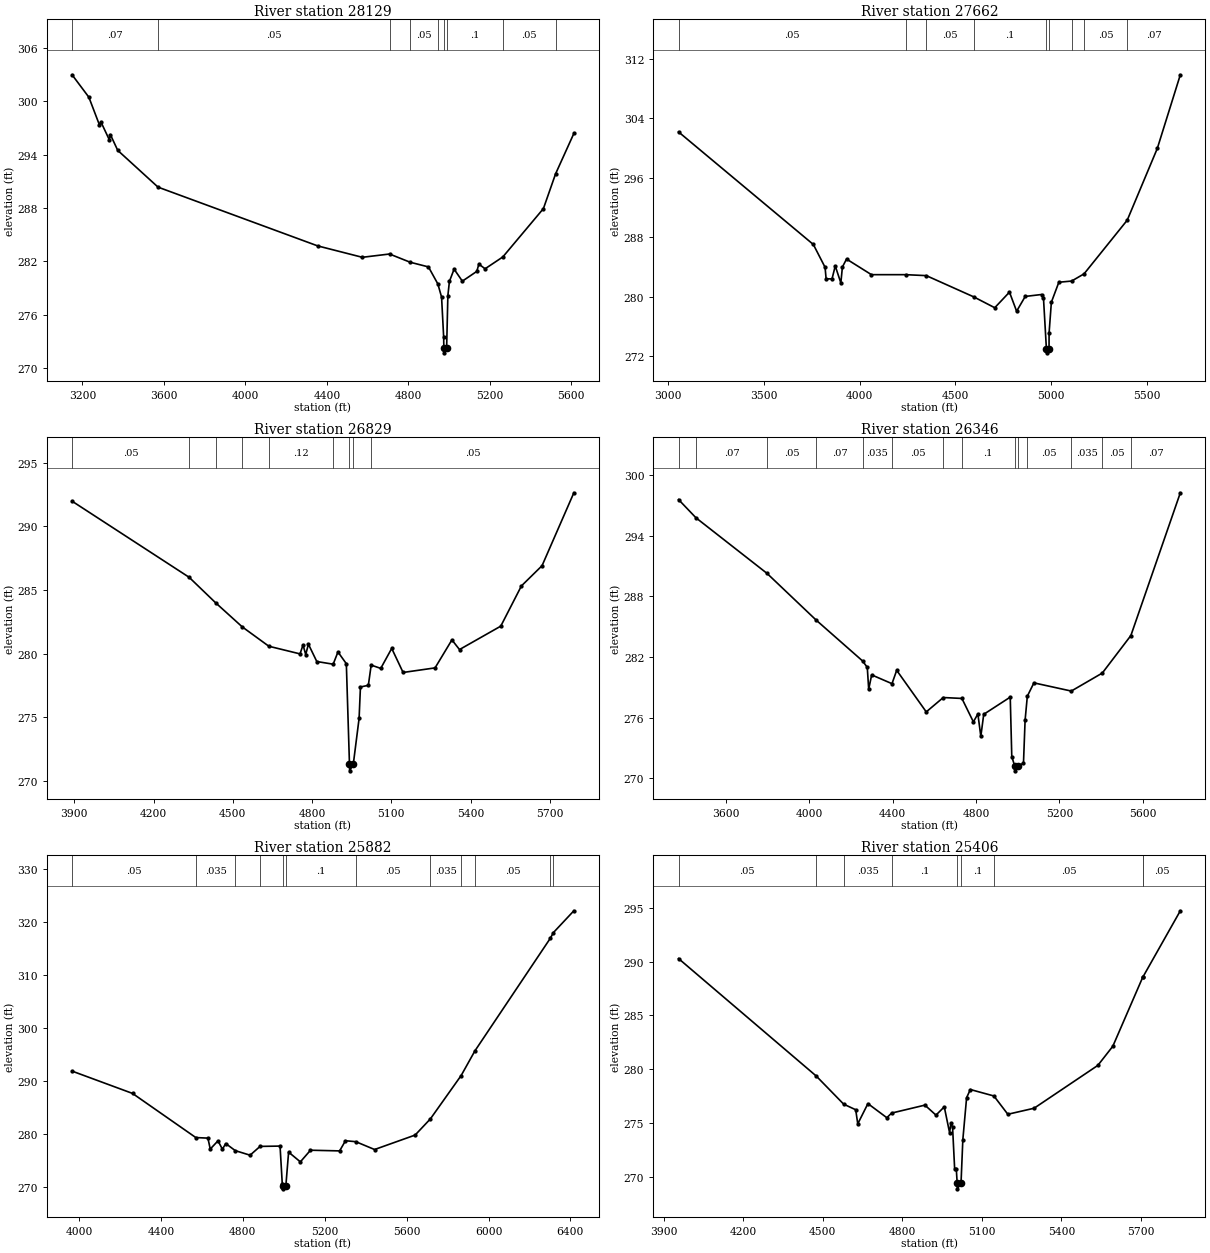
Type RM Length L Ch R = 1 ,28129   ,467,467,467
BEGIN DESCRIPTION:
MITCHELL CREEK 35.0
END DESCRIPTION:
XS GIS Cut Line= 3
        2488675.     13742225.02        2489125.       13740425.
        2489025.     13739824.99
#Sta/Elev= 30
  3148.8  302.97  3231.3  300.45  3282.8  297.36  3290.6  297.67  3331.8  295.66
  3336.9  296.25    3373  294.48  3570.9  290.35  4354.8  283.75  4573.9  282.47
  4707.5  282.84  4808.3  281.92  4898.6  281.39  4944.7  279.48    4963     278
  4973.3  273.49  4974.2  272.24  4974.7  271.74  4987.8  272.24  4993.9  278.17
  5001.6  279.77  5024.5  281.14    5065  279.79    5136  280.89  5146.1  281.71
  5176.6  281.18  5263.7  282.51    5463  287.94  5522.7  291.84  5612.5  296.38
#Mann= 9 ,-1 , 0
  3148.8     .07       0  3570.9     .05       0  4707.5    .035       0
  4808.3     .05       0  4944.7      .1       0  4974.2     .05       0
  4987.8      .1       0  5263.7     .05       0  5522.7     .07       0
Bank Sta=4974.2,4987.8
XS Rating Curve= 0 ,0
Exp/Cntr=0.3,0.1

Type RM Length L Ch R = 1 ,27662   ,833,833,833
BEGIN DESCRIPTION:
MITCHELL CREEK 34.0
END DESCRIPTION:
XS GIS Cut Line= 3
      2490225.02     13742025.04        2489475.       13740225.
      2489174.98     13739624.97
#Sta/Elev= 30
  3054.2  302.17  3758.4  287.02  3819.6  283.95    3825   282.4  3855.9  282.39
  3872.7  284.13    3902  281.85  3910.1  283.99  3931.7  285.06  4061.7  282.96
  4240.5  282.96  4348.4  282.83  4596.2  279.97  4705.8  278.51  4782.7  280.61
  4820.1  278.04    4865  280.03  4950.1  280.29  4960.4  279.78  4975.7  272.94
  4976.2  272.44  4989.4  272.94  4989.6   275.1  5001.5  279.25  5040.6  281.94
  5107.3   282.1  5172.3  283.07  5397.7  290.29  5554.9  299.95  5675.1  309.86
#Mann= 9 ,-1 , 0
  3054.2     .05       0  4240.5    .035       0  4348.4     .05       0
  4596.2      .1       0  4975.7     .05       0  4989.4      .1       0
  5107.3     .07       0  5172.3     .05       0  5397.7     .07       0
Bank Sta=4975.7,4989.4
XS Rating Curve= 0 ,0
Exp/Cntr=0.3,0.1

Type RM Length L Ch R = 1 ,26829   ,483,483,483
BEGIN DESCRIPTION:
MITCHELL CREEK 33.0
END DESCRIPTION:
XS GIS Cut Line= 3
        2490225.     13741475.02        2490025.       13740375.
      2489524.99     13739774.99
#Sta/Elev= 30
  3891.7  291.97  4334.7  285.99  4435.3  283.98  4535.9  282.09  4636.5  280.57
  4754.4  279.97  4765.8  280.67    4776  279.92  4786.2  280.73  4817.9  279.37
  4879.9  279.16    4898  280.12  4929.7   279.2  4941.6  271.28  4942.1  270.78
  4955.9  271.28    4978   274.9  4983.1  277.37    5013   277.5  5023.7  279.09
  5059.9  278.83  5101.5   280.4  5144.5  278.51  5265.5  278.87  5329.3  281.07
    5358  280.31  5514.2  282.15  5592.3  285.31  5670.4   286.9  5790.8  292.63
#Mann= 9 ,-1 , 0
  3891.7     .05       0  4334.7    .035       0  4435.3     .05       0
  4535.9      .1       0  4636.5     .12       0  4879.9      .1       0
  4941.6     .05       0  4955.9      .1       0  5023.7     .05       0
Bank Sta=4941.6,4955.9
XS Rating Curve= 0 ,0
Exp/Cntr=0.3,0.1

Type RM Length L Ch R = 1 ,26346   ,464,464,464
BEGIN DESCRIPTION:
MITCHELL CREEK 32.0
END DESCRIPTION:
XS GIS Cut Line= 3
        2491525.       13741375.        2490425.       13740175.
        2489925.       13739575.
#Sta/Elev= 30
  3371.5  297.57  3455.5  295.76  3796.2  290.27  4033.1  285.63  4254.9  281.61
  4277.6  280.97  4284.4  278.81  4298.6  280.23  4396.2  279.36  4418.8  280.68
  4560.7  276.57  4642.4  277.99  4731.8   277.9    4787  275.58  4808.5  276.37
  4822.7  274.15  4836.6  276.33  4963.9  278.03  4971.3  272.14  4985.1  271.24
  4985.6  270.74  4999.5  271.24  5027.4  271.48  5035.2  275.74  5045.9  278.12
  5077.5  279.44    5257  278.63  5405.8  280.41    5543  284.12  5780.4  298.24
#Mann= 14 ,-1 , 0
  3371.5     .05       0  3455.5     .07       0  3796.2     .05       0
  4033.1     .07       0  4254.9    .035       0  4396.2     .05       0
  4642.4     .12       0  4731.8      .1       0  4985.1     .05       0
  4999.5      .1       0  5045.9     .05       0    5257    .035       0
  5405.8     .05       0    5543     .07       0
Bank Sta=4985.1,4999.5
XS Rating Curve= 0 ,0
Exp/Cntr=0.3,0.1

Type RM Length L Ch R = 1 ,25882   ,476,476,476
BEGIN DESCRIPTION:
MITCHELL CREEK 31.0
END DESCRIPTION:
XS GIS Cut Line= 3
      2491325.01     13741075.01        2490825.       13740175.
      2489925.03     13739075.03
#Sta/Elev= 30
  3966.1  291.89  4261.3  287.68  4570.4  279.35  4629.6  279.24    4641  277.18
  4678.8  278.73  4700.5  277.14  4716.5  278.22  4763.3  276.88  4835.5  276.02
  4884.3  277.68  4981.9  277.74  4992.8  270.58  4995.7  270.17  4996.2  269.67
  5010.1  270.17  5023.7   276.6  5081.1  274.76  5130.6  276.96  5272.8  276.83
  5301.5  278.75  5351.9  278.57  5443.6  277.09  5641.7  279.82  5716.3  282.88
  5866.5  291.06  5933.5   295.7  6301.4  316.93  6317.4  318.05  6416.9  322.15
#Mann= 12 ,-1 , 0
  3966.1     .05       0  4570.4    .035       0  4763.3     .05       0
  4884.3      .1       0  4995.7     .05       0  5010.1      .1       0
  5351.9     .05       0  5716.3    .035       0  5866.5     .07       0
  5933.5     .05       0  6301.4     .07       0  6317.4     .05       0
Bank Sta=4995.7,5010.1
XS Rating Curve= 0 ,0
Exp/Cntr=0.3,0.1

Type RM Length L Ch R = 1 ,25406   ,483,483,483
BEGIN DESCRIPTION:
MITCHELL CREEK 30.0
END DESCRIPTION:
XS GIS Cut Line= 3
        2491275.     13740875.02        2490975.       13739875.
      2490374.98     13739274.98
#Sta/Elev= 30
  3955.8  290.28  4474.9  279.37  4578.6  276.75    4624  276.23  4631.8  274.92
  4670.1   276.8  4741.4  275.49  4759.5  275.92    4885  276.66  4926.8  275.73
  4958.1   276.5  4978.1   274.1  4983.3  275.02  4989.4  274.59  4997.2  270.74
  5003.4  270.74  5006.8  269.38  5007.3  268.88  5021.2  269.38  5028.1  273.45
  5042.3  277.35  5056.4  278.11  5145.2  277.51  5197.8  275.81  5296.8  276.37
  5537.2  280.35  5593.8  282.13  5707.6   288.6  5708.3  288.61  5848.4  294.72
#Mann= 9 ,-1 , 0
  3955.8     .05       0  4474.9     .12       0  4578.6    .035       0
  4759.5      .1       0  5006.8     .05       0  5021.2      .1       0
  5145.2     .05       0  5707.6    .035       0  5708.3     .05       0
Bank Sta=5006.8,5021.2
XS Rating Curve= 0 ,0
Exp/Cntr=0.3,0.1

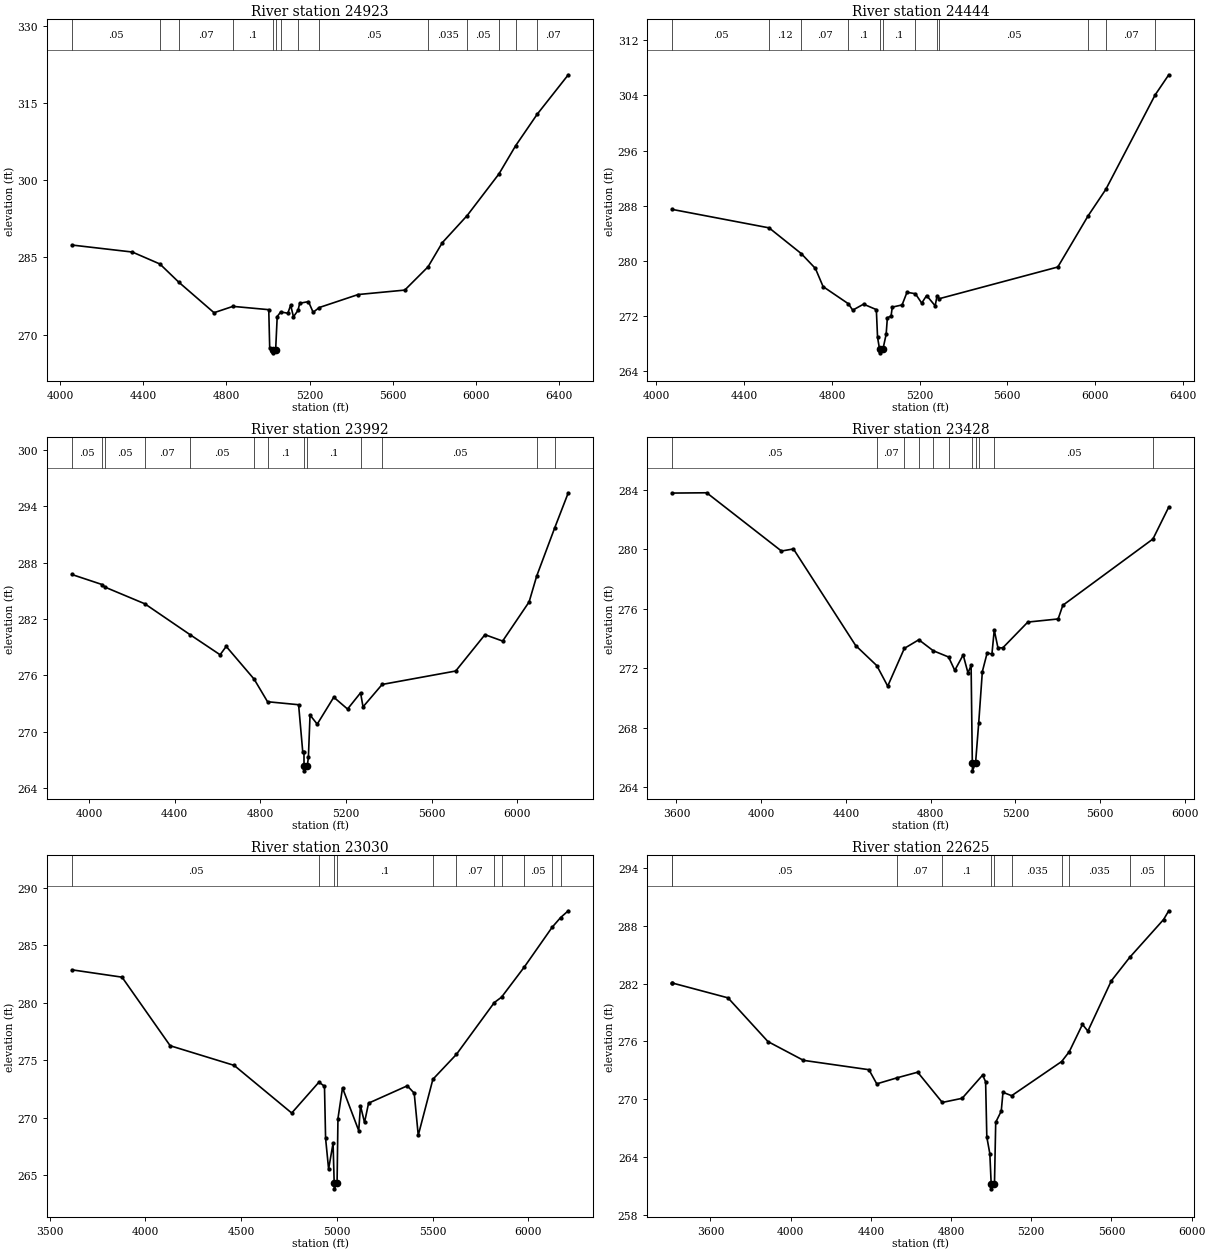
Type RM Length L Ch R = 1 ,24923   ,479,479,479
BEGIN DESCRIPTION:
MITCHELL CREEK 29.0
END DESCRIPTION:
XS GIS Cut Line= 3
      2492074.99     13740224.99        2491275.       13739725.
        2490075.       13738925.
#Sta/Elev= 30
  4057.1  287.39  4347.8  286.03  4480.3  283.71  4571.1  280.18  4740.5  274.25
  4831.3  275.48  5003.5  274.84    5008  267.47  5021.5  266.96    5022  266.46
  5036.5  266.96  5044.1  273.51    5061   274.4  5095.1  274.15  5108.7  275.71
  5122.2  273.46    5144   274.7  5152.2  276.09  5194.3   276.4  5216.8  274.33
  5246.4  275.26  5433.2  277.78    5657  278.64  5768.9  283.16  5837.3  287.84
    5957  293.12  6109.5  301.19  6189.3  306.64  6293.5  312.79  6442.7  320.44
#Mann= 14 ,-1 , 0
  4057.1     .05       0  4480.3     .12       0  4571.1     .07       0
  4831.3      .1       0  5021.5     .05       0  5036.5      .1       0
    5061     .05       0    5144    .035       0  5246.4     .05       0
  5768.9    .035       0    5957     .05       0  6109.5     .07       0
  6189.3     .05       0  6293.5     .07       0
Bank Sta=5021.5,5036.5
XS Rating Curve= 0 ,0
Exp/Cntr=0.3,0.1

Type RM Length L Ch R = 1 ,24444   ,452,452,452
BEGIN DESCRIPTION:
MITCHELL CREEK 28.0
END DESCRIPTION:
XS GIS Cut Line= 3
      2492124.99     13740224.99        2491525.       13739525.
      2490324.98     13738924.99
#Sta/Elev= 30
  4072.4  287.47  4513.7   284.8  4660.1  281.08  4724.9  278.92    4760  276.29
  4875.1  273.81    4895  272.88  4944.4  273.75  5002.7  272.96  5008.3  268.93
  5017.6   267.2  5018.1   266.7  5032.6   267.2  5047.4  269.38    5053  271.78
  5069.8  272.03  5075.4  273.32  5120.1  273.64  5142.5  275.47  5180.8  275.26
  5209.6   273.9  5231.9     275    5271  273.51  5279.7  274.98  5289.3  274.54
  5830.1  279.13  5968.2  286.54  6049.1  290.38    6274  304.06    6336  306.97
#Mann= 12 ,-1 , 0
  4072.4     .05       0  4513.7     .12       0  4660.1     .07       0
  4875.1      .1       0  5017.6     .05       0  5032.6      .1       0
  5180.8     .05       0  5279.7    .035       0  5289.3     .05       0
  5968.2    .035       0  6049.1     .07       0    6274     .05       0
Bank Sta=5017.6,5032.6
XS Rating Curve= 0 ,0
Exp/Cntr=0.3,0.1

Type RM Length L Ch R = 1 ,23992   ,564,564,564
BEGIN DESCRIPTION:
MITCHELL CREEK 27.0
END DESCRIPTION:
XS GIS Cut Line= 3
      2492325.01     13740075.02        2491725.       13739175.
      2490525.02       13738875.
#Sta/Elev= 30
  3919.7  286.75  4062.3  285.67  4072.9  285.42  4260.5  283.63    4472  280.34
  4612.3   278.2  4640.8  279.09  4771.3   275.6  4833.8   273.2  4978.9  272.88
  4998.4  267.82    5004  267.82  5004.2  266.34  5004.7  265.84  5019.2  266.34
  5024.6  267.27  5032.3  271.78  5065.8  270.81  5143.1  273.68  5207.5  272.42
  5268.3  274.15  5279.7  272.65  5369.1  275.04  5712.6  276.47  5849.2  280.34
  5931.7  279.66  6055.4  283.83  6090.9  286.59  6175.2  291.73  6238.3  295.45
#Mann= 13 ,-1 , 0
  3919.7     .05       0  4062.3     .07       0  4072.9     .05       0
  4260.5     .07       0    4472     .05       0  4771.3     .07       0
  4833.8      .1       0  5004.2     .05       0  5019.2      .1       0
  5268.3    .035       0  5369.1     .05       0  6090.9    .035       0
  6175.2     .07       0
Bank Sta=5004.2,5019.2
XS Rating Curve= 0 ,0
Exp/Cntr=0.3,0.1

Type RM Length L Ch R = 1 ,23428   ,398,398,398
BEGIN DESCRIPTION:
B19609
END DESCRIPTION:
XS GIS Cut Line= 3
      2492541.66     13739825.81      2491810.65     13738799.75
      2490834.55     13738329.29
#Sta/Elev= 30
  3580.5  283.79  3742.9  283.81  4095.7  279.89  4152.3  280.03  4446.1  273.53
  4545.8  272.18  4597.3   270.8  4675.8  273.34  4744.1  273.92  4812.4  273.18
  4884.6  272.76  4913.8  271.86  4953.5   272.9  4976.1  271.69  4990.9  272.19
  4996.7   265.6  4997.2   265.1  5011.8   265.6  5026.8  268.32    5044  271.78
  5066.6  273.03  5089.2  272.96  5100.2  274.58  5117.4  273.39    5140  273.37
  5258.6  275.11  5401.7  275.32  5423.9  276.24  5849.2   280.7  5923.9  282.85
#Mann= 11 ,-1 , 0
  3580.5     .05       0  4545.8     .07       0  4675.8     .05       0
  4744.1     .07       0  4812.4     .05       0  4884.6      .1       0
  4996.7     .05       0  5011.8      .1       0  5026.8    .035       0
  5100.2     .05       0  5849.2    .035       0
Bank Sta=4996.7,5011.8
XS Rating Curve= 0 ,0
Exp/Cntr=0.3,0.1

Type RM Length L Ch R = 1 ,23030   ,405,405,405
BEGIN DESCRIPTION:
B19608
END DESCRIPTION:
XS GIS Cut Line= 3
      2492638.56     13739750.97      2491960.38     13738566.35
      2491291.01     13737535.88
#Sta/Elev= 30
    3615  282.87  3877.4  282.23  4128.9  276.26  4463.1  274.55  4763.9   270.4
  4906.2  273.09  4935.1  272.73  4940.9   268.2  4956.7  265.52    4980  267.78
  4985.8   264.3  4986.3   263.8  5000.9   264.3  5005.5  269.92  5029.3  272.59
    5114  268.87  5123.2  271.03  5144.3  269.58  5165.4  271.26  5367.7  272.77
  5403.9  272.13    5425  268.46  5501.5  273.34  5624.5  275.51  5822.4  280.02
  5860.2  280.49  5979.8  283.13  6124.7  286.58  6168.8  287.42  6208.8  288.01
#Mann= 11 ,-1 , 0
    3615     .05       0  4906.2      .1       0  4985.8     .05       0
  5000.9      .1       0  5501.5     .12       0  5624.5     .07       0
  5822.4     .12       0  5860.2     .07       0  5979.8     .05       0
  6124.7     .07       0  6168.8     .05       0
Bank Sta=4985.8,5000.9
XS Rating Curve= 0 ,0
Exp/Cntr=0.3,0.1

Type RM Length L Ch R = 1 ,22625   ,472,472,472
BEGIN DESCRIPTION:
B19607
END DESCRIPTION:
XS GIS Cut Line= 3
      2492709.02      13739759.8      2492277.44     13738399.01
      2491692.74     13737528.55
#Sta/Elev= 30
  3409.6  282.07  3409.9  282.07  3687.4  280.53  3886.7  275.99  4063.9  274.04
  4390.3  273.07  4429.4   271.6  4531.1  272.23  4633.5  272.81  4756.2  269.67
  4855.3   270.1  4957.3  272.51  4972.3  271.82  4978.3  266.08  4993.3  264.36
  5000.1   261.2  5000.6   260.7  5016.5   261.2  5022.7  267.61  5050.3  268.77
  5058.9  270.72  5102.1  270.37  5351.6  273.92  5389.6  274.94  5455.3  277.77
  5482.4  277.08  5599.4   282.3  5690.5  284.72  5859.9  288.66  5885.8  289.57
#Mann= 11 ,-1 , 0
  3409.6    .035       0  3409.9     .05       0  4531.1     .07       0
  4756.2      .1       0  5000.1     .05       0  5016.5      .1       0
  5102.1    .035       0  5351.6     .12       0  5389.6    .035       0
  5690.5     .05       0  5859.9     .07       0
Bank Sta=5000.1,5016.5
XS Rating Curve= 0 ,0
Exp/Cntr=0.3,0.1

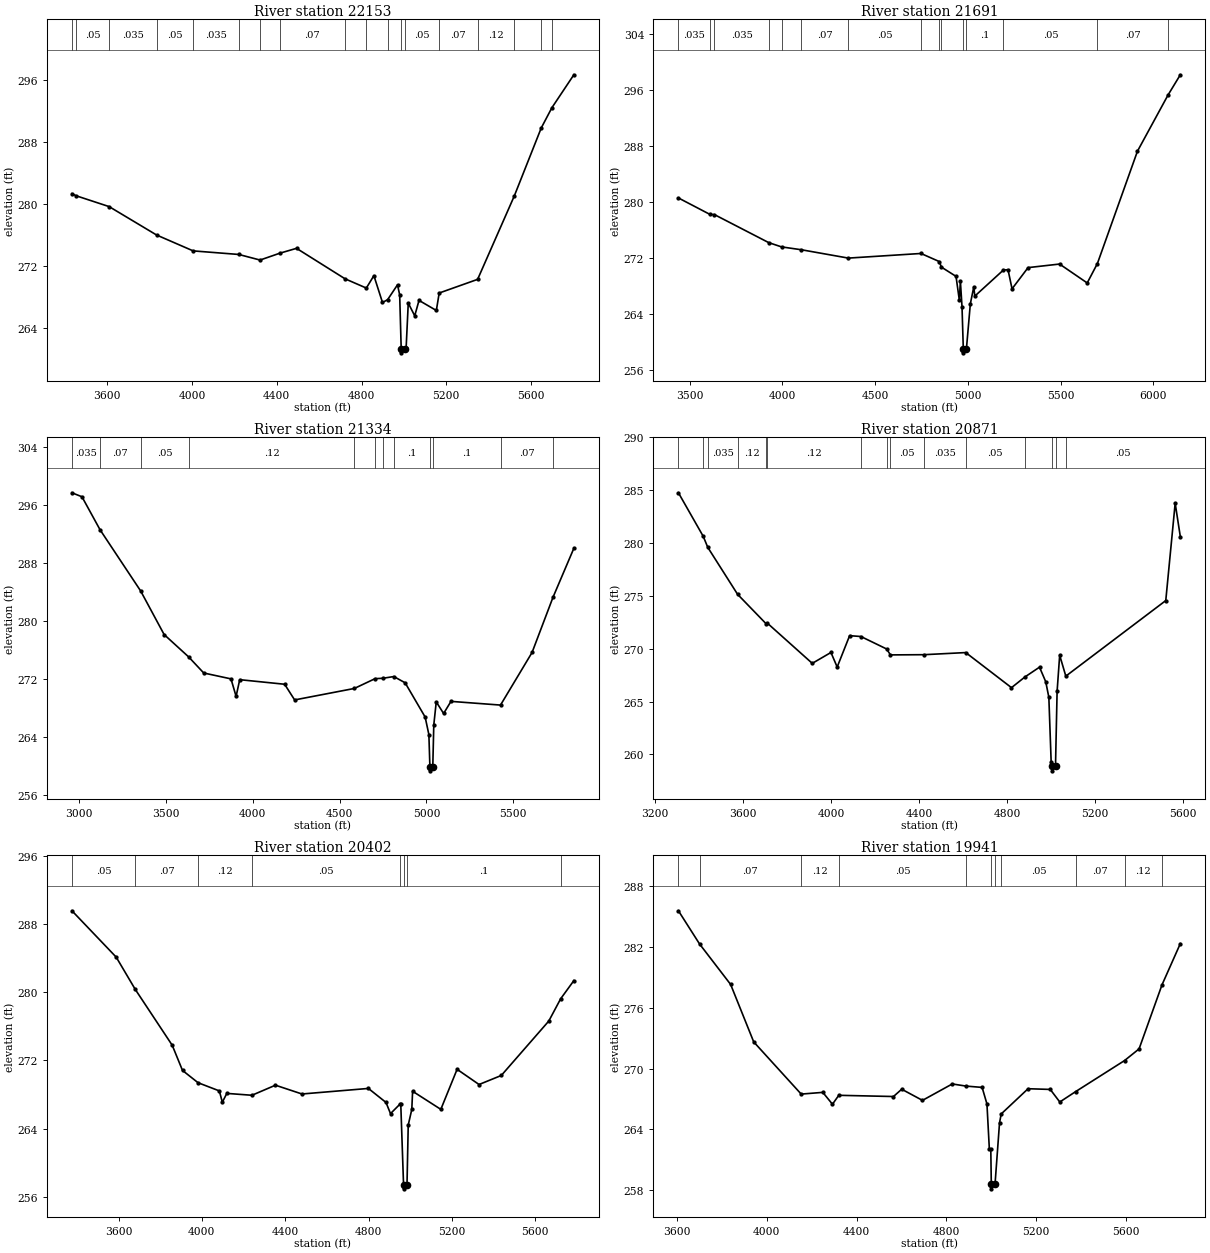
Type RM Length L Ch R = 1 ,22153   ,462,462,462
BEGIN DESCRIPTION:
B19606
END DESCRIPTION:
XS GIS Cut Line= 3
      2492757.45     13739720.14      2492480.02     13738059.92
      2492102.15     13737488.73
#Sta/Elev= 30
  3433.7  281.36    3454  281.09    3609   279.7  3832.9  276.04  4005.6  273.99
    4221  273.53  4321.3  272.81  4414.2  273.69  4493.3  274.32  4722.4  270.39
  4822.7   269.2  4858.3   270.8  4898.9  267.34    4923   267.7  4969.8  269.62
    4980  268.32  4987.2  261.35  4987.7  260.85  5003.6  261.35  5010.4  261.46
  5020.5  267.26    5051  265.62  5071.2  267.61    5153  266.31  5166.4  268.56
  5347.7  270.32  5520.8  281.07    5648  289.84  5698.3  292.45  5801.8  296.69
#Mann= 18 ,-1 , 0
  3433.7    .035       0    3454     .05       0    3609    .035       0
  3832.9     .05       0  4005.6    .035       0    4221     .07       0
  4321.3     .05       0  4414.2     .07       0  4722.4    .035       0
  4822.7     .07       0    4923     .05       0  4987.2     .05       0
  5003.6     .05       0  5166.4     .07       0  5347.7     .12       0
  5520.8     .07       0    5648     .12       0  5698.3     .07       0
Bank Sta=4987.2,5003.6
XS Rating Curve= 0 ,0
Exp/Cntr=0.3,0.1

Type RM Length L Ch R = 1 ,21691   ,357,357,357
BEGIN DESCRIPTION:
B19605
END DESCRIPTION:
XS GIS Cut Line= 3
      2493488.48       13739773.       2492810.3     13738095.15
      2492255.41     13737390.53
#Sta/Elev= 30
  3438.8  280.63  3608.8  278.28  3633.2  278.25  3925.8  274.25  3994.9  273.64
  4102.3  273.23  4355.1  272.04  4746.8   272.7  4846.1  271.54  4856.5  270.76
  4935.9  269.43  4953.9  265.99  4959.3  268.79  4968.2  265.07  4975.2  259.01
  4975.7  258.51  4991.7  259.01    5013   265.5  5031.7  267.95  5037.1  266.61
  5191.5  270.34  5216.3  270.38  5237.9  267.65  5324.3  270.68  5494.2  271.19
  5643.3  268.49  5698.2  271.26  5914.3  287.31  6079.8  295.36  6145.4  298.22
#Mann= 15 ,-1 , 0
  3438.8    .035       0  3608.8     .05       0  3633.2    .035       0
  3925.8     .07       0  3994.9    .035       0  4102.3     .07       0
  4355.1     .05       0  4746.8    .035       0  4846.1     .05       0
  4856.5      .1       0  4975.2     .05       0  4991.7      .1       0
  5191.5     .05       0  5698.2     .07       0  6079.8     .05       0
Bank Sta=4975.2,4991.7
XS Rating Curve= 0 ,0
Exp/Cntr=0.3,0.1

Type RM Length L Ch R = 1 ,21334   ,463,463,463
BEGIN DESCRIPTION:
MITCHELL CREEK 22.0
END DESCRIPTION:
XS GIS Cut Line= 3
        2494675.       13739225.        2493025.       13738025.
      2492424.97     13737424.97
#Sta/Elev= 30
  2959.5  297.65  3017.1   297.1  3121.1  292.56  3354.8  284.13    3490  278.12
  3630.6  275.05    3718  272.82  3874.9  272.01  3904.3   269.6  3925.1   271.9
  4183.6  271.27  4241.2  269.11  4584.8  270.69  4704.1  272.04    4748  272.09
  4812.1  272.33  4877.2  271.47  4992.4  266.75  5013.9  264.33  5019.8  259.84
  5020.3  259.34  5036.3  259.84  5042.1  265.66  5056.3  268.84  5098.7  267.24
  5141.1  268.91  5426.2   268.4  5607.8  275.65  5728.4  283.26  5848.3     290
#Mann= 12 ,-1 , 0
  2959.5    .035       0  3121.1     .07       0  3354.8     .05       0
  3630.6     .12       0  4584.8     .05       0  4704.1    .035       0
    4748     .05       0  4812.1      .1       0  5019.8     .05       0
  5036.3      .1       0  5426.2     .07       0  5728.4     .05       0
Bank Sta=5019.8,5036.3
XS Rating Curve= 0 ,0
Exp/Cntr=0.3,0.1

Type RM Length L Ch R = 1 ,20871   ,469,469,469
BEGIN DESCRIPTION:
MITCHELL CREEK 21.0
END DESCRIPTION:
XS GIS Cut Line= 3
      2494425.02     13738875.02        2493225.       13737675.
      2492924.99     13737174.98
#Sta/Elev= 30
  3307.1  284.75  3419.8  280.63  3440.6  279.58    3576  275.14  3706.3  272.34
  3711.4  272.41  3915.2  268.61  4000.1  269.64  4028.4  268.26  4084.9  271.23
  4136.2  271.15    4253  269.97  4270.4  269.41  4422.8  269.43  4612.5  269.63
  4820.3  266.31  4881.2  267.32  4947.6  268.25  4975.9  266.87    4990   265.4
  5000.6  259.23  5003.7  258.94  5004.2  258.44  5020.3  258.94  5027.5  265.96
  5039.2  269.38  5067.1   267.4  5521.2  274.55  5563.9  283.76  5587.3   280.6
#Mann= 15 ,-1 , 0
  3307.1    .035       0  3419.8     .05       0  3440.6    .035       0
    3576     .12       0  3706.3    .035       0  3711.4     .12       0
  4136.2     .05       0    4253     .12       0  4270.4     .05       0
  4422.8    .035       0  4612.5     .05       0  4881.2      .1       0
  5003.7     .05       0  5020.3      .1       0  5067.1     .05       0
Bank Sta=5003.7,5020.3
XS Rating Curve= 0 ,0
Exp/Cntr=0.3,0.1

Type RM Length L Ch R = 1 ,20402   ,461,461,461
BEGIN DESCRIPTION:
MITCHELL CREEK 20.0
END DESCRIPTION:
XS GIS Cut Line= 3
      2494724.98     13738774.97        2493625.       13737575.
      2493124.98     13736974.98
#Sta/Elev= 30
  3376.5  289.53  3588.9   284.1  3680.4  280.32  3857.7  273.78  3907.1  270.83
  3981.7  269.39    4084  268.43  4098.2   267.1  4119.8  268.14  4240.3  267.92
  4353.2   269.1  4480.5  268.07  4799.3  268.72  4883.8  267.08  4905.4  265.77
  4951.2  266.89  4954.7   266.9    4968  257.46  4968.5  256.96  4984.6  257.46
  4990.5  264.43  5007.6  266.26  5011.5  268.39  5146.9  266.27    5225  270.96
  5330.4  269.18  5437.2  270.24    5665  276.61    5722  279.22  5785.4  281.35
#Mann= 8 ,-1 , 0
  3376.5     .05       0  3680.4     .07       0  3981.7     .12       0
  4240.3     .05       0  4951.2      .1       0    4968     .05       0
  4984.6      .1       0    5722     .07       0
Bank Sta=4968,4984.6
XS Rating Curve= 0 ,0
Exp/Cntr=0.3,0.1

Type RM Length L Ch R = 1 ,19941   ,474,474,474
BEGIN DESCRIPTION:
MITCHELL CREEK 19.0
END DESCRIPTION:
XS GIS Cut Line= 3
        2494675.       13738625.        2493975.       13737425.
      2493374.98     13736824.98
#Sta/Elev= 30
  3605.7  285.58  3700.1   282.3  3838.5  278.31  3941.4  272.64  4153.1  267.49
  4249.5  267.66  4292.5  266.49  4320.8  267.37  4564.5  267.25  4601.3  267.97
  4693.9  266.87  4826.7  268.49  4887.8  268.28  4959.8  268.15  4981.3  266.52
  4992.1  262.04  4998.5  262.04  5000.7  258.64  5001.2  258.14  5017.5  258.64
  5037.4  264.65  5044.9  265.53  5164.7  268.02  5263.6  267.95  5306.1  266.71
  5377.1  267.74  5594.9   270.8  5659.6  271.95  5761.8  278.27  5843.5  282.34
#Mann= 11 ,-1 , 0
  3605.7     .05       0  3700.1     .07       0  4153.1     .12       0
  4320.8     .05       0  4887.8      .1       0  5000.7     .05       0
  5017.5      .1       0  5044.9     .05       0  5377.1     .07       0
  5594.9     .12       0  5761.8     .07       0
Bank Sta=5000.7,5017.5
XS Rating Curve= 0 ,0
Exp/Cntr=0.3,0.1

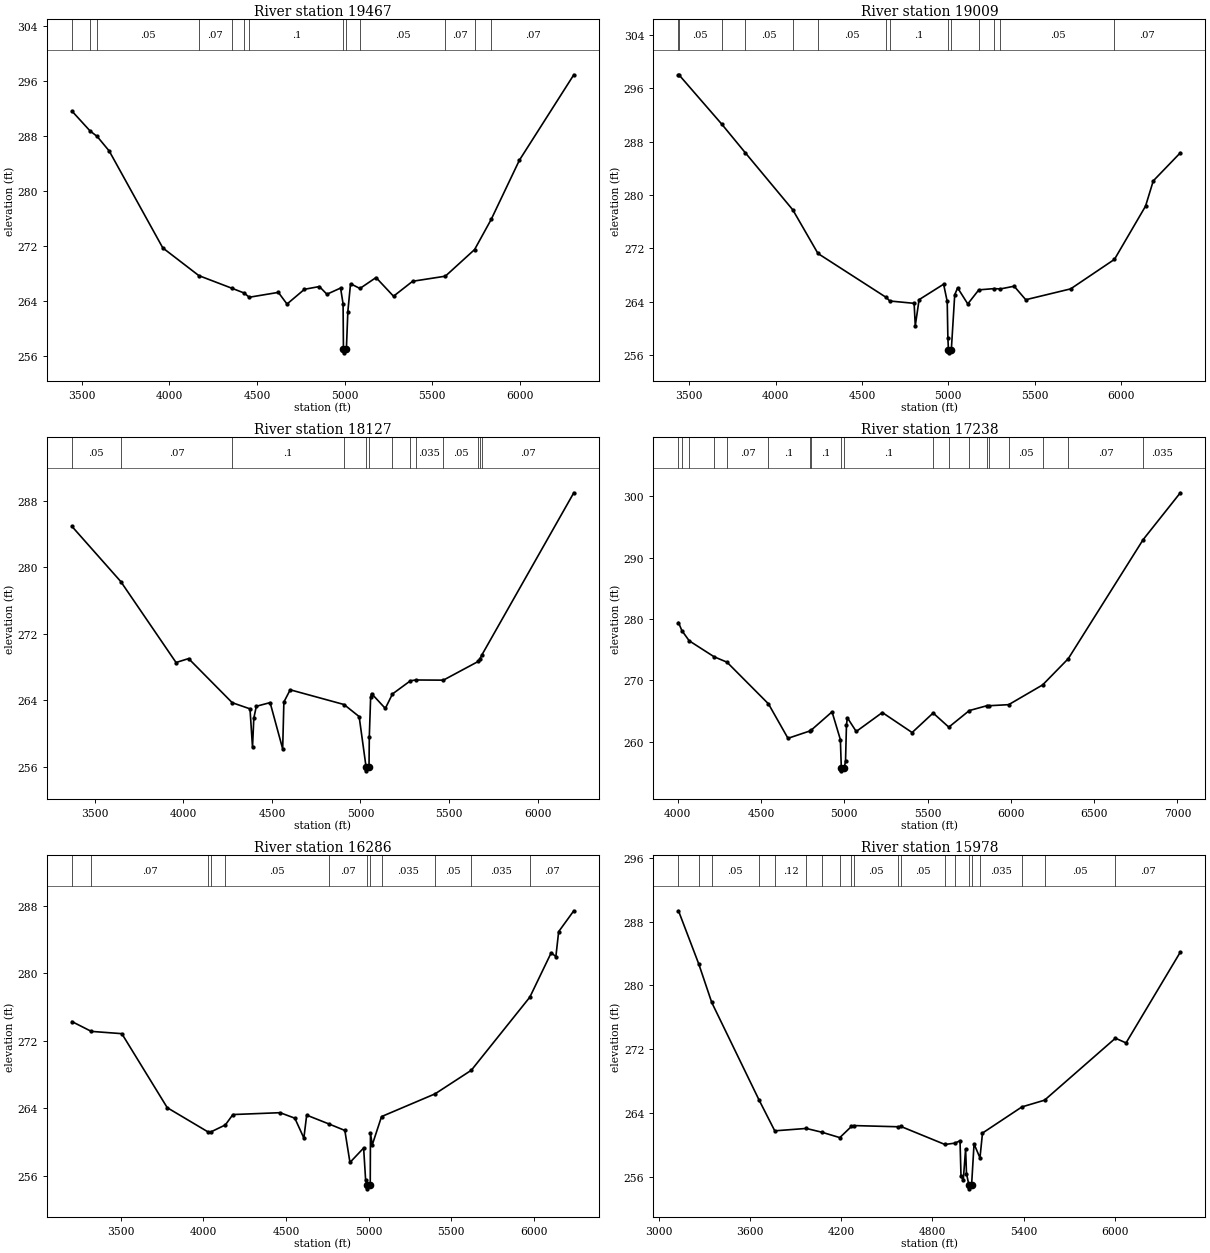
Type RM Length L Ch R = 1 ,19467   ,458,458,458
BEGIN DESCRIPTION:
MITCHELL CREEK 18.0
END DESCRIPTION:
XS GIS Cut Line= 3
      2495525.03     13738175.02        2494325.       13737175.
      2493225.02     13736475.01
#Sta/Elev= 30
  3443.2  291.66  3547.3  288.75    3587  287.97  3656.1  285.84    3962  271.72
  4168.1  267.68  4354.8  265.86  4427.3  265.14  4455.6  264.53  4621.9  265.24
  4671.4  263.54    4771  265.69  4856.2  266.09  4899.2  264.97  4977.3  265.87
  4991.6  263.56  4993.6  256.93  4994.1  256.43  5010.4  256.93  5018.8  262.45
  5034.1   266.5  5087.8  265.81  5179.7   267.4  5279.6  264.68  5388.8  266.86
  5575.6   267.6  5742.6  271.48  5837.5  275.88  5998.4   284.5  6309.1  296.95
#Mann= 13 ,-1 , 0
  3443.2     .05       0  3547.3     .07       0    3587     .05       0
  4168.1     .07       0  4354.8     .05       0  4427.3     .07       0
  4455.6      .1       0  4993.6     .05       0  5010.4      .1       0
  5087.8     .05       0  5575.6     .07       0  5742.6     .12       0
  5837.5     .07       0
Bank Sta=4993.6,5010.4
XS Rating Curve= 0 ,0
Exp/Cntr=0.3,0.1

Type RM Length L Ch R = 1 ,19009   ,882,882,882
BEGIN DESCRIPTION:
MITCHELL CREEK 17.0
END DESCRIPTION:
XS GIS Cut Line= 3
      2495725.01     13738275.01        2494725.       13737075.
        2493525.       13736475.
#Sta/Elev= 30
  3438.5  298.05  3441.1  298.05    3689  290.64  3824.1  286.38    4100  277.78
  4245.6  271.23  4640.3  264.64  4661.4   264.1    4802  263.75  4808.6  260.38
  4830.7   264.3  4972.6  266.62  4993.4  264.03  4997.3   258.5  5000.5  256.82
    5001  256.32  5017.3  256.82  5036.9  265.04  5053.7  266.07  5112.4  263.66
  5176.1  265.77  5264.9  265.96  5301.1  265.91  5380.7  266.32  5447.8  264.29
  5707.7  265.92  5961.2  270.35    6141  278.34  6185.7  282.13  6342.2  286.34
#Mann= 14 ,-1 , 0
  3438.5    .035       0  3441.1     .05       0    3689     .07       0
  3824.1     .05       0    4100     .07       0  4245.6     .05       0
  4640.3     .07       0  4661.4      .1       0  5000.5     .05       0
  5017.3      .1       0  5176.1     .05       0  5264.9      .1       0
  5301.1     .05       0  5961.2     .07       0
Bank Sta=5000.5,5017.3
XS Rating Curve= 0 ,0
Exp/Cntr=0.3,0.1

Type RM Length L Ch R = 1 ,18127   ,889,889,889
BEGIN DESCRIPTION:
MITCHELL CREEK 16.0
END DESCRIPTION:
XS GIS Cut Line= 3
      2495775.03     13737675.03        2494675.       13736475.
      2493474.99       13736375.
#Sta/Elev= 30
  3371.7   284.9  3647.3  278.27  3959.1  268.54    4030  269.01  4276.2  263.71
  4376.5  262.97  4390.7  258.35  4398.1  261.86  4412.3  263.28    4490  263.72
  4560.9  258.16  4567.7  263.79  4603.4  265.26  4907.2  263.49  4992.5  262.04
  5031.3  256.02  5031.8  255.52  5048.2  256.02  5049.8  259.62  5057.3  264.34
  5062.3  264.81  5140.1  263.02  5180.5  264.76  5281.6  266.34  5311.1  266.44
  5467.8  266.42  5664.7  268.67  5673.3  268.95  5684.8  269.44  6203.8  288.94
#Mann= 13 ,-1 , 0
  3371.7     .05       0  3647.3     .07       0  4276.2      .1       0
  4907.2     .12       0  5031.3     .05       0  5048.2     .12       0
  5180.5     .05       0  5281.6     .07       0  5311.1    .035       0
  5467.8     .05       0  5664.7     .07       0  5673.3     .05       0
  5684.8     .07       0
Bank Sta=5031.3,5048.2
XS Rating Curve= 0 ,0
Exp/Cntr=0.3,0.1

Type RM Length L Ch R = 1 ,17238   ,952,952,952
BEGIN DESCRIPTION:
MITCHELL CREEK 15.0
END DESCRIPTION:
XS GIS Cut Line= 3
      2495774.98     13737124.97        2495175.       13736325.
      2493375.02     13735425.01
#Sta/Elev= 30
  4004.9  279.43  4025.4  278.11  4069.5  276.45    4219  273.85  4296.2  272.97
  4544.8  266.19  4662.2  260.57  4795.2  261.78  4800.7  261.88  4926.7  264.88
  4976.7  260.36  4982.4  255.77  4982.9  255.27  5000.2  255.77  5007.7  256.88
  5013.3  262.76  5018.8  263.91  5071.9  261.68  5228.5  264.77  5407.4  261.51
  5533.5  264.69  5627.6  262.39  5750.6  265.09  5859.1   265.9  5870.8  265.88
    5987  266.05  6190.8  269.27  6344.6  273.54  6794.4  292.95  7017.3  300.57
#Mann= 19 ,-1 , 0
  4004.9     .07       0  4025.4     .05       0  4069.5     .07       0
    4219     .05       0  4296.2     .07       0  4544.8      .1       0
  4795.2     .05       0  4800.7      .1       0  4982.4     .05       0
  5000.2      .1       0  5533.5    .035       0  5627.6     .07       0
  5750.6    .035       0  5859.1     .05       0  5870.8    .035       0
    5987     .05       0  6190.8    .035       0  6344.6     .07       0
  6794.4    .035       0
Bank Sta=4982.4,5000.2
XS Rating Curve= 0 ,0
Exp/Cntr=0.3,0.1

Type RM Length L Ch R = 1 ,16286   ,308,308,308
BEGIN DESCRIPTION:
B19604
END DESCRIPTION:
XS GIS Cut Line= 5
      2495963.37      13736950.2      2495699.14     13736192.74
      2495183.91     13735919.71      2494717.11     13735796.41
       2493664.6     13735281.16
#Sta/Elev= 30
  3203.4  274.27  3320.7  273.11  3505.5  272.84  3780.8  264.08  4025.6  261.24
  4044.4  261.21  4132.5  262.04  4178.4  263.27  4464.3  263.49  4553.5  262.84
  4608.3  260.49  4625.3   263.2  4762.3  262.14  4856.5  261.39  4887.5   257.6
  4970.3  259.31  4982.5  255.49  4992.4  254.98  4992.9  254.48  5010.3  254.98
  5011.7  261.05  5022.7  259.69  5078.8  263.03  5403.2  265.72  5622.6  268.51
  5977.1  277.16  6106.7  282.42  6134.8  281.95  6151.7  284.91  6243.4  287.38
#Mann= 12 ,-1 , 0
  3203.4     .05       0  3320.7     .07       0  4025.6      .1       0
  4044.4     .07       0  4132.5     .05       0  4762.3     .07       0
  4992.4     .05       0  5010.3     .07       0  5078.8    .035       0
  5403.2     .05       0  5622.6    .035       0  5977.1     .07       0
Bank Sta=4992.4,5010.3
XS Rating Curve= 0 ,0
Exp/Cntr=0.3,0.1

Type RM Length L Ch R = 1 ,15978   ,471,471,471
BEGIN DESCRIPTION:
MITCHELL CREEK 14.0
END DESCRIPTION:
XS GIS Cut Line= 3
        2496775.       13736275.      2494858.03     13735567.41
      2493765.88     13734933.26
#Sta/Elev= 30
  3126.7  289.35  3260.8  282.66  3345.6  277.87  3657.2  265.65    3761  261.77
  3968.7  262.07  4072.6  261.59  4189.4  260.92  4266.3  262.32  4280.3  262.43
  4574.2  262.28  4591.9  262.32  4882.1  260.06  4948.6  260.23  4981.5  260.53
  4988.1  256.11  5002.8  255.55  5018.5  259.52  5024.1  256.42  5039.9     255
  5040.4   254.5  5057.9     255    5074  260.13    5113  258.38  5129.6  261.49
  5389.5  264.77  5538.3  265.61  6005.3  273.38  6075.4  272.79    6433  284.17
#Mann= 20 ,-1 , 0
  3126.7     .07       0  3260.8    .035       0  3345.6     .05       0
  3657.2      .1       0    3761     .12       0  3968.7     .12       0
  4072.6      .1       0  4189.4     .05       0  4266.3    .035       0
  4280.3     .05       0  4574.2    .035       0  4591.9     .05       0
  4882.1    .035       0  4948.6     .12       0  5039.9     .05       0
  5057.9     .12       0    5113    .035       0  5389.5     .07       0
  5538.3     .05       0  6005.3     .07       0
Bank Sta=5039.9,5057.9
XS Rating Curve= 0 ,0
Exp/Cntr=0.3,0.1