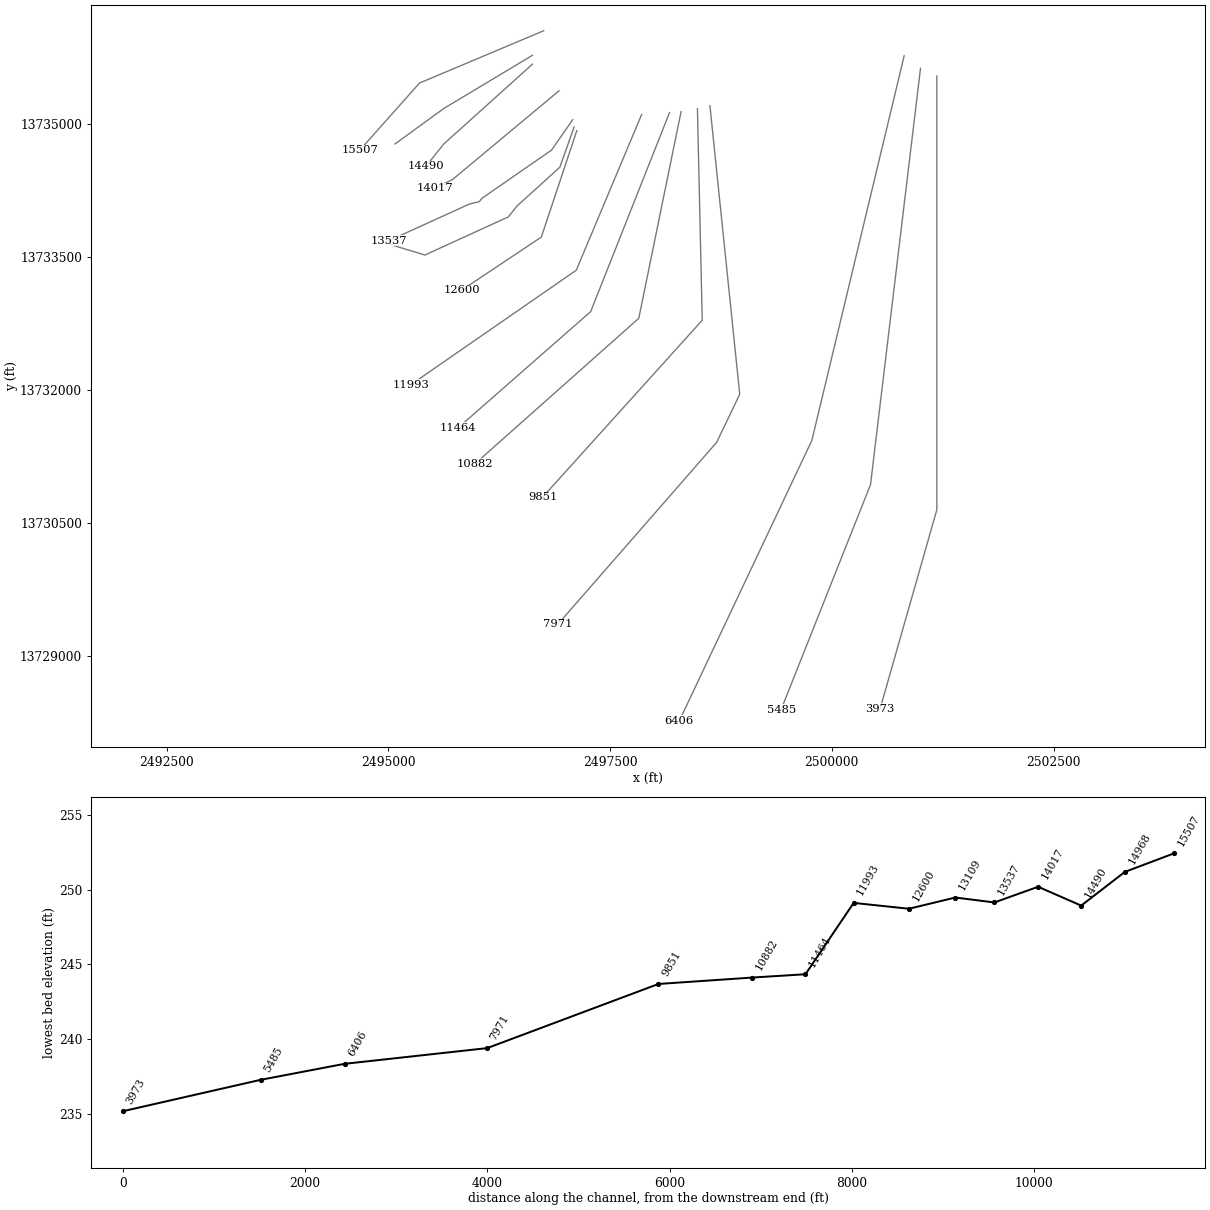
HEC-RAS study MITCHELL CREEK.prj: MITCHELL CREEK Base Level Engineering

--- MITCHELL CREEK.g01 (geometry) --- (continued)

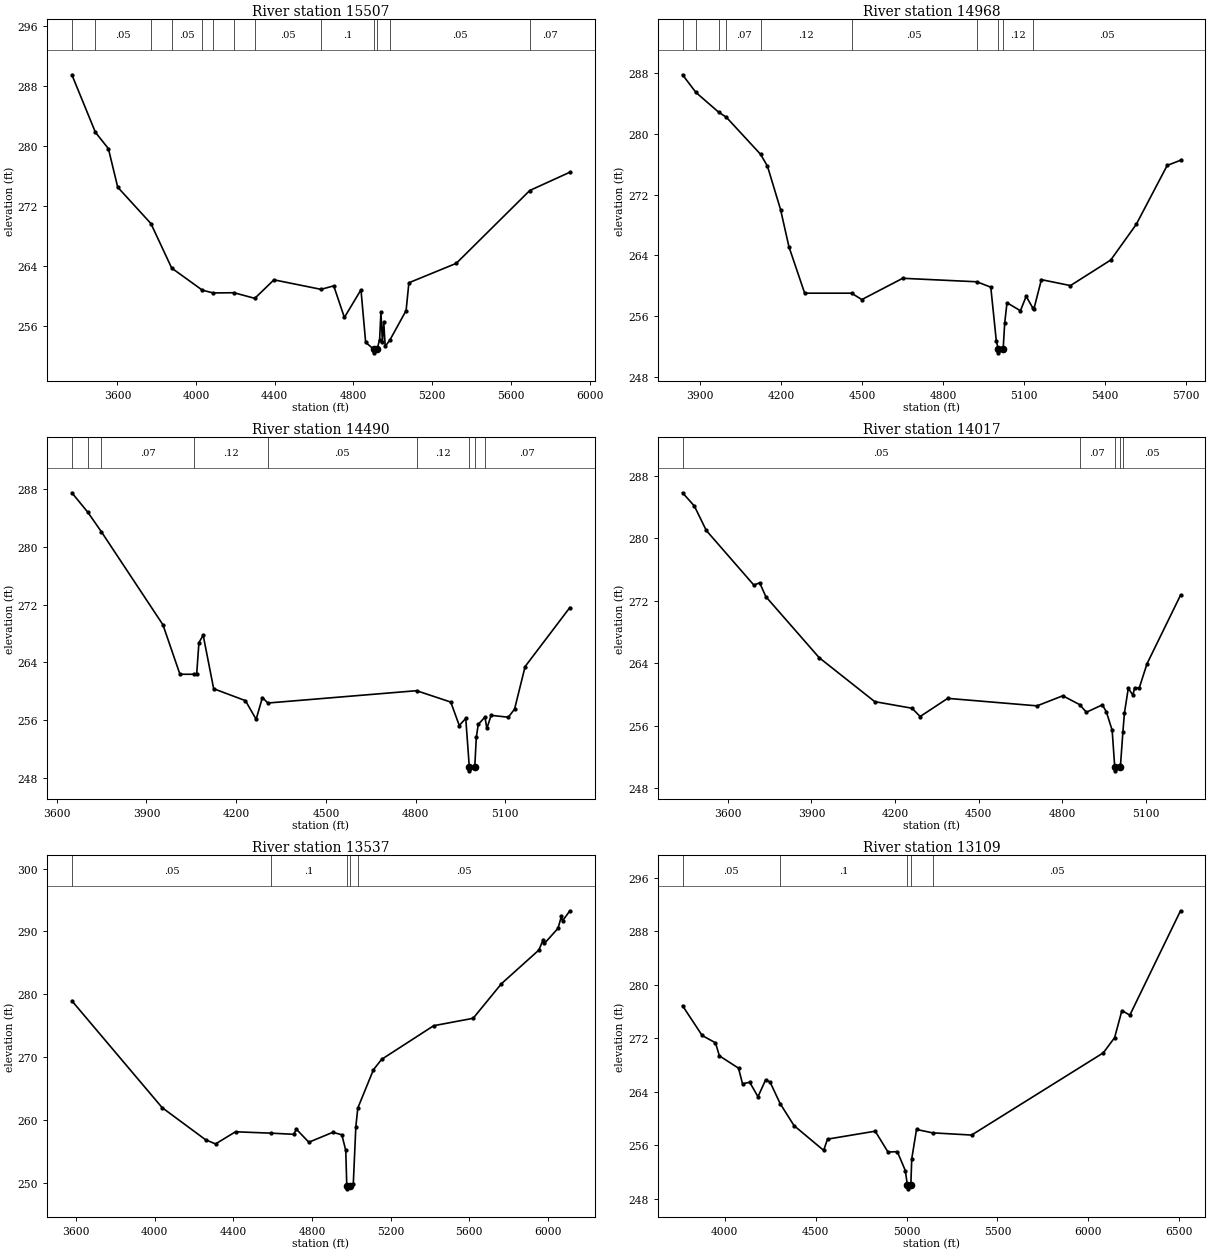
Type RM Length L Ch R = 1 ,15507   ,539,539,539
BEGIN DESCRIPTION:
MITCHELL CREEK 13.0
END DESCRIPTION:
XS GIS Cut Line= 3
      2496751.61     13736051.81      2495351.25     13735461.72
      2494678.72     13734705.67
#Sta/Elev= 30
  3368.7  289.52  3488.4  281.84  3554.3  279.67  3601.7  274.52  3770.5  269.67
  3876.1  263.73    4032  260.78  4087.2  260.41  4192.8  260.44  4298.4  259.69
  4395.9  262.16  4635.5  260.89  4699.8  261.36    4754  257.14  4838.3  260.83
  4862.1  253.82  4902.3  252.92  4902.8  252.42  4920.4  252.92  4933.1  254.18
  4939.7  257.82  4947.3  253.89    4954  256.55  4961.5  253.28  4985.2  254.12
  5067.7  258.06  5081.9  261.77  5322.7  264.36  5696.4  274.08  5900.2  276.52
#Mann= 13 ,-1 , 0
  3368.7    .035       0  3488.4     .05       0  3770.5     .12       0
  3876.1     .05       0    4032     .12       0  4087.2     .05       0
  4192.8     .12       0  4298.4     .05       0  4635.5      .1       0
  4902.3     .05       0  4920.4      .1       0  4985.2     .05       0
  5696.4     .07       0
Bank Sta=4902.3,4920.4
XS Rating Curve= 0 ,0
Exp/Cntr=0.3,0.1

Type RM Length L Ch R = 1 ,14968   ,478,478,478
BEGIN DESCRIPTION:
MITCHELL CREEK 12.0
END DESCRIPTION:
XS GIS Cut Line= 3
      2496624.96     13735774.98        2495625.       13735175.
      2495075.02     13734775.01
#Sta/Elev= 30
  3834.3  287.77  3883.9  285.45  3967.9  282.86  3996.8  282.18  4123.8   277.3
  4149.1  275.75  4197.7  270.04  4228.8  265.14  4287.1  259.03  4460.8  259.03
    4499  258.19  4650.6  260.99  4925.4  260.53  4977.1  259.82  4997.5  252.78
  5004.9  251.68  5005.4  251.18    5023  251.68  5028.7   255.1  5037.2  257.77
    5087  256.72  5108.3  258.62  5132.3  257.12  5136.5  256.89  5164.7  260.81
  5272.5  260.03    5422   263.4  5516.3  268.08  5631.1  275.84  5680.5  276.52
#Mann= 10 ,-1 , 0
  3834.3    .035       0  3883.9     .07       0  3967.9     .05       0
  3996.8     .07       0  4123.8     .12       0  4460.8     .05       0
  4925.4     .12       0  5004.9     .05       0    5023     .12       0
  5132.3     .05       0
Bank Sta=5004.9,5023
XS Rating Curve= 0 ,0
Exp/Cntr=0.3,0.1

Type RM Length L Ch R = 1 ,14490   ,473,473,473
BEGIN DESCRIPTION:
MITCHELL CREEK 11.0
END DESCRIPTION:
XS GIS Cut Line= 3
      2496624.99     13735674.99        2495625.       13734775.
      2495425.01     13734525.01
#Sta/Elev= 30
  3650.5  287.51  3703.6  284.82  3749.2   282.1  3955.1  269.19  4011.9  262.33
  4059.3  262.33  4067.9  262.33  4075.4  266.72  4089.6  267.75  4124.7  260.32
  4230.9  258.67  4266.7  256.08  4287.7   259.1    4306  258.34  4803.3  260.05
  4917.7  258.47  4946.1  255.22  4967.8  256.21  4979.7  249.43  4980.2  248.93
  4997.9  249.43  5003.1  253.56  5009.5  255.37  5032.1  256.39  5038.3  254.81
  5052.7  256.63  5110.3  256.37  5131.1   257.5  5166.3   263.4    5316  271.59
#Mann= 9 ,-1 , 0
  3650.5    .035       0  3703.6     .05       0  3749.2     .07       0
  4059.3     .12       0    4306     .05       0  4803.3     .12       0
  4979.7     .05       0  4997.9     .12       0  5032.1     .07       0
Bank Sta=4979.7,4997.9
XS Rating Curve= 0 ,0
Exp/Cntr=0.3,0.1

Type RM Length L Ch R = 1 ,14017   ,480,480,480
BEGIN DESCRIPTION:
MITCHELL CREEK 10.0
END DESCRIPTION:
XS GIS Cut Line= 3
      2496924.97     13735374.98        2495725.       13734375.
      2495525.02     13734275.01
#Sta/Elev= 30
  3437.7  285.83    3480  284.14  3522.9     281  3693.4     274  3714.3  274.29
  3736.4  272.52  3927.8  264.69  4126.9  259.06    4261  258.21  4289.6  257.15
  4388.6  259.48  4708.8  258.52  4801.2  259.81  4861.5  258.68  4885.8   257.7
  4943.1  258.65  4957.4  257.75  4978.2  255.39  4987.4  250.69  4987.9  250.19
  5005.6  250.69  5008.1   250.9  5016.6  255.13  5022.1  257.57    5036  260.76
  5052.8  259.89  5058.4  260.84  5075.2   260.8  5103.1  263.91  5223.3   272.7
#Mann= 5 ,-1 , 0
  3437.7     .05       0  4861.5     .07       0  4987.4     .05       0
  5005.6     .07       0  5016.6     .05       0
Bank Sta=4987.4,5005.6
XS Rating Curve= 0 ,0
Exp/Cntr=0.3,0.1

Type RM Length L Ch R = 1 ,13537   ,428,428,428
BEGIN DESCRIPTION:
MITCHELL CREEK 9.0
END DESCRIPTION:
XS GIS Cut Line= 6
       2497079.1     13735048.98      2496839.52     13734705.23
      2496057.17     13734163.61        2496025.       13734125.
      2495910.97     13734096.49      2495006.23     13733684.41
#Sta/Elev= 30
  3578.9  278.99    4038  262.03    4259  256.93  4309.6  256.27    4411   258.2
    4592  257.98  4706.3   257.8    4721   258.6    4784  256.54  4906.3  258.12
  4951.8  257.72  4971.7  255.24  4976.9  249.64  4977.4  249.14  4995.1  249.64
    5010  249.89  5022.9  258.99    5033  261.97  5112.6  268.06  5154.1   269.7
  5418.7  275.04  5619.6  276.22  5763.4  281.71  5953.3  287.04  5976.3  288.72
  5981.8   288.1    6051   290.5  6068.5  292.42    6074  291.68  6111.4  293.29
#Mann= 5 ,-1 , 0
  3578.9     .05       0    4592      .1       0  4976.9     .05       0
  4995.1      .1       0    5033     .05       0
Bank Sta=4976.9,4995.1
XS Rating Curve= 0 ,0
Exp/Cntr=0.3,0.1

Type RM Length L Ch R = 1 ,13109   ,509,509,509
BEGIN DESCRIPTION:
MITCHELL CREEK 8.0
END DESCRIPTION:
XS GIS Cut Line= 6
      2497094.72     13734965.62      2496933.27     13734512.52
      2496449.79     13734074.57      2496352.58     13733952.58
      2495412.43     13733522.93      2495018.34      13733642.2
#Sta/Elev= 30
  3769.2  276.85    3877   272.4  3950.3   271.3  3971.6  269.36  4076.8  267.51
  4098.9  265.18  4138.4   265.4  4183.9  263.24  4225.6  265.75  4250.2  265.44
  4305.5  262.22    4382  258.92  4544.7  255.22  4565.9   256.9    4828  258.09
  4898.4  254.97  4949.6  255.03  4993.3  252.21  5005.3  249.97  5005.8  249.47
  5023.8  249.97  5028.7  253.94  5055.1  258.35  5143.3  257.84  5357.7  257.51
  6081.4   269.8  6143.6  272.07  6183.8  276.13  6227.2  275.43  6505.8  291.04
#Mann= 5 ,-1 , 0
  3769.2     .05       0  4305.5      .1       0  5005.3     .05       0
  5023.8      .1       0  5143.3     .05       0
Bank Sta=5005.3,5023.8
XS Rating Curve= 0 ,0
Exp/Cntr=0.3,0.1

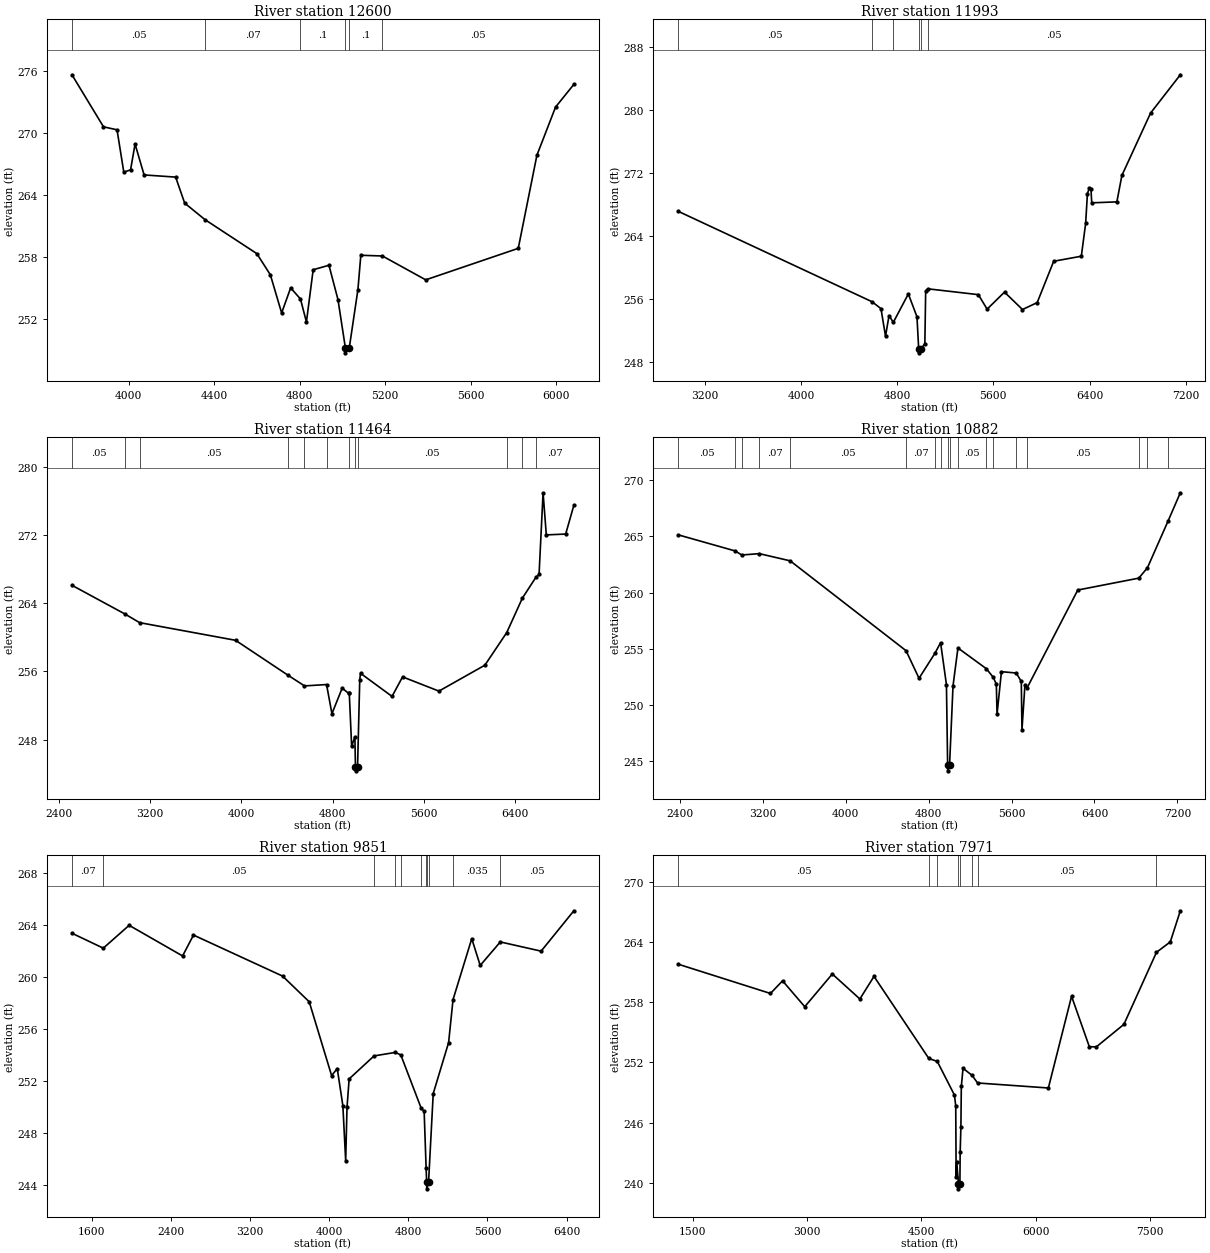
Type RM Length L Ch R = 1 ,12600   ,607,607,607
BEGIN DESCRIPTION:
MITCHELL CREEK 7.0
END DESCRIPTION:
XS GIS Cut Line= 3
      2497124.99     13734924.96        2496725.       13733725.
      2495825.03     13733125.02
#Sta/Elev= 30
  3735.1  275.65  3882.6  270.61  3945.9  270.32  3977.5  266.22  4009.1  266.44
  4030.2  268.94  4072.4  265.95  4219.9  265.74  4262.1  263.22  4357.1  261.62
  4599.4  258.33  4662.7  256.28  4715.4  252.58  4757.5  255.01  4803.4  253.94
  4831.3  251.71  4862.9  256.77  4936.7   257.2  4978.9  253.87  5013.3  249.22
  5013.8  248.72  5031.8  249.22  5072.1  254.85  5085.6  258.17  5186.6   258.1
  5389.1  255.79  5821.7  258.84  5908.9  267.86    5996  272.52  6081.6  274.72
#Mann= 6 ,-1 , 0
  3735.1     .05       0  4357.1     .07       0  4803.4      .1       0
  5013.3     .05       0  5031.8      .1       0  5186.6     .05       0
Bank Sta=5013.3,5031.8
XS Rating Curve= 0 ,0
Exp/Cntr=0.3,0.1

Type RM Length L Ch R = 1 ,11993   ,529,529,529
BEGIN DESCRIPTION:
B19603
END DESCRIPTION:
XS GIS Cut Line= 3
      2497856.25     13735107.73      2497119.01     13733351.36
      2495254.15     13732061.14
#Sta/Elev= 30
  2981.9  267.07  4591.5   255.6  4665.9  254.72  4703.6  251.22  4732.8  253.84
  4768.4  252.98  4893.4  256.59    4965  253.69  4979.4  249.61  4979.9  249.11
    4998  249.61  5030.6  250.26  5037.5  256.96    5055  257.24  5475.3   256.5
  5548.2  254.66  5692.8  256.82  5842.2  254.61  5964.5  255.49  6101.7  260.74
  6331.4  261.38  6367.3  265.54  6382.1  269.31    6397  270.01  6411.6   269.9
  6417.9  268.16  6626.8  268.28  6668.7  271.64  6907.2  279.56  7154.4  284.42
#Mann= 6 ,-1 , 0
  2981.9     .05       0  4591.5     .07       0  4768.4      .1       0
  4979.4     .05       0    4998      .1       0    5055     .05       0
Bank Sta=4979.4,4998
XS Rating Curve= 0 ,0
Exp/Cntr=0.3,0.1

Type RM Length L Ch R = 1 ,11464   ,582,582,582
BEGIN DESCRIPTION:
B19602
END DESCRIPTION:
XS GIS Cut Line= 3
      2498170.68     13735129.45      2497281.64     13732885.15
      2495785.41     13731573.24
#Sta/Elev= 30
  2512.6   266.1  2976.6  262.74  3106.2  261.72  3947.9  259.65  4404.3  255.59
    4553   254.3  4746.7  254.46  4793.8  251.04  4883.7  254.04    4940  253.43
  4945.8  253.51  4966.7  247.22  4995.2  248.34  5000.1  244.84  5000.6  244.34
  5018.7  244.84  5037.9  255.04  5044.5  255.78  5321.1  253.07  5413.7  255.36
  5732.5  253.69  6135.8  256.73  6327.8  260.56  6464.6  264.59  6583.5  267.04
  6611.2  267.37  6646.4  276.95  6674.9  272.01  6844.7  272.11  6916.5  275.48
#Mann= 12 ,-1 , 0
  2512.6     .05       0  2976.6     .07       0  3106.2     .05       0
  4404.3     .07       0    4553     .05       0  4746.7      .1       0
    4940     .05       0  5000.1     .05       0  5018.7     .05       0
  6327.8     .07       0  6464.6     .05       0  6583.5     .07       0
Bank Sta=5000.1,5018.7
XS Rating Curve= 0 ,0
Exp/Cntr=0.3,0.1

Type RM Length L Ch R = 1 ,10882   ,1031,1031,1031
BEGIN DESCRIPTION:
B19601
END DESCRIPTION:
XS GIS Cut Line= 3
      2498300.79      13735140.3      2497823.74     13732809.26
      2495980.59     13731172.11
#Sta/Elev= 30
    2384  265.13    2932   263.7  2995.1  263.34  3164.7  263.46  3462.8  262.82
  4581.1  254.82  4706.5  252.36  4861.4  254.61  4914.5  255.53    4971   251.8
  4982.6  244.62  4983.1  244.12  5001.2  244.62  5034.6  251.69  5082.1  255.06
  5355.4  253.22  5421.4  252.47  5452.7  251.84  5459.4  249.15    5502  252.95
  5644.8  252.83  5693.5  252.08  5700.2  247.79  5728.7  251.75  5750.5  251.52
  6238.8  260.22  6828.1  261.28  6911.6  262.21  7112.5  266.41  7228.6  268.88
#Mann= 18 ,-1 , 0
    2384     .05       0    2932     .07       0  2995.1     .05       0
  3164.7     .07       0  3462.8     .05       0  4581.1     .07       0
  4861.4     .05       0  4914.5      .1       0  4982.6     .05       0
  5001.2      .1       0  5082.1     .05       0  5355.4     .07       0
  5421.4     .05       0  5644.8     .07       0  5750.5     .05       0
  6828.1    .035       0  6911.6     .05       0  7112.5     .07       0
Bank Sta=4982.6,5001.2
XS Rating Curve= 0 ,0
Exp/Cntr=0.3,0.1

Type RM Length L Ch R = 1 ,9851    ,1880,1880,1880
BEGIN DESCRIPTION:
B19600
END DESCRIPTION:
XS GIS Cut Line= 3
       2498485.1     13735172.85      2498539.31     13732787.57
      2496739.74     13730792.86
#Sta/Elev= 30
  1401.2  263.38    1718  262.23  1979.2  263.99  2519.3  261.63  2629.4  263.24
  3529.6  260.08  3799.1   258.1  4025.6  252.41  4082.4  252.96  4139.2  250.09
  4167.6  245.86  4181.1  249.97  4202.7  252.16  4454.6  253.93  4669.8   254.2
    4725     254  4930.8   249.9  4960.5  249.67  4980.5   245.3  4986.1  244.19
  4986.6  243.69  5005.1  244.19  5052.4  251.03  5207.9  254.96  5252.6  258.27
  5441.8  262.96    5527   260.9  5730.5  262.71  6142.8     262  6473.6  265.11
#Mann= 11 ,-1 , 0
  1401.2     .07       0    1718     .05       0  4454.6      .1       0
  4669.8     .05       0    4725      .1       0  4930.8     .07       0
  4980.5     .05       0  4986.1     .05       0  5005.1     .05       0
  5252.6    .035       0  5730.5     .05       0
Bank Sta=4986.1,5005.1
XS Rating Curve= 0 ,0
Exp/Cntr=0.3,0.1

Type RM Length L Ch R = 1 ,7971    ,1565,1565,1565
BEGIN DESCRIPTION:
B19599
END DESCRIPTION:
XS GIS Cut Line= 4
      2498626.05     13735205.38      2498962.15     13731952.74
      2498701.94     13731410.64      2496913.03     13729361.52
#Sta/Elev= 30
  1309.7  261.78  2518.6  258.87  2677.3  260.13  2968.9  257.55  3330.8  260.81
  3692.7  258.32  3878.2  260.57  4598.4  252.39  4709.1   252.1  4934.5  248.75
  4951.6  247.67  4957.1  240.61  4965.4  242.06  4987.3   239.9  4987.8   239.4
  5006.4   239.9  5009.8  243.06  5019.5  245.55    5025  249.61  5047.7  251.41
  5165.9  250.71  5238.6  249.95  6168.2  249.45  6472.9  258.59  6706.4  253.56
  6798.5  253.55  7160.2  255.79    7588  262.97  7769.6  264.01  7901.1  267.11
#Mann= 8 ,-1 , 0
  1309.7     .05       0  4598.4    .035       0  4709.1     .05       0
  4987.3     .05       0  5006.4     .05       0  5165.9     .07       0
  5238.6     .05       0    7588     .07       0
Bank Sta=4987.3,5006.4
XS Rating Curve= 0 ,0
Exp/Cntr=0.3,0.1

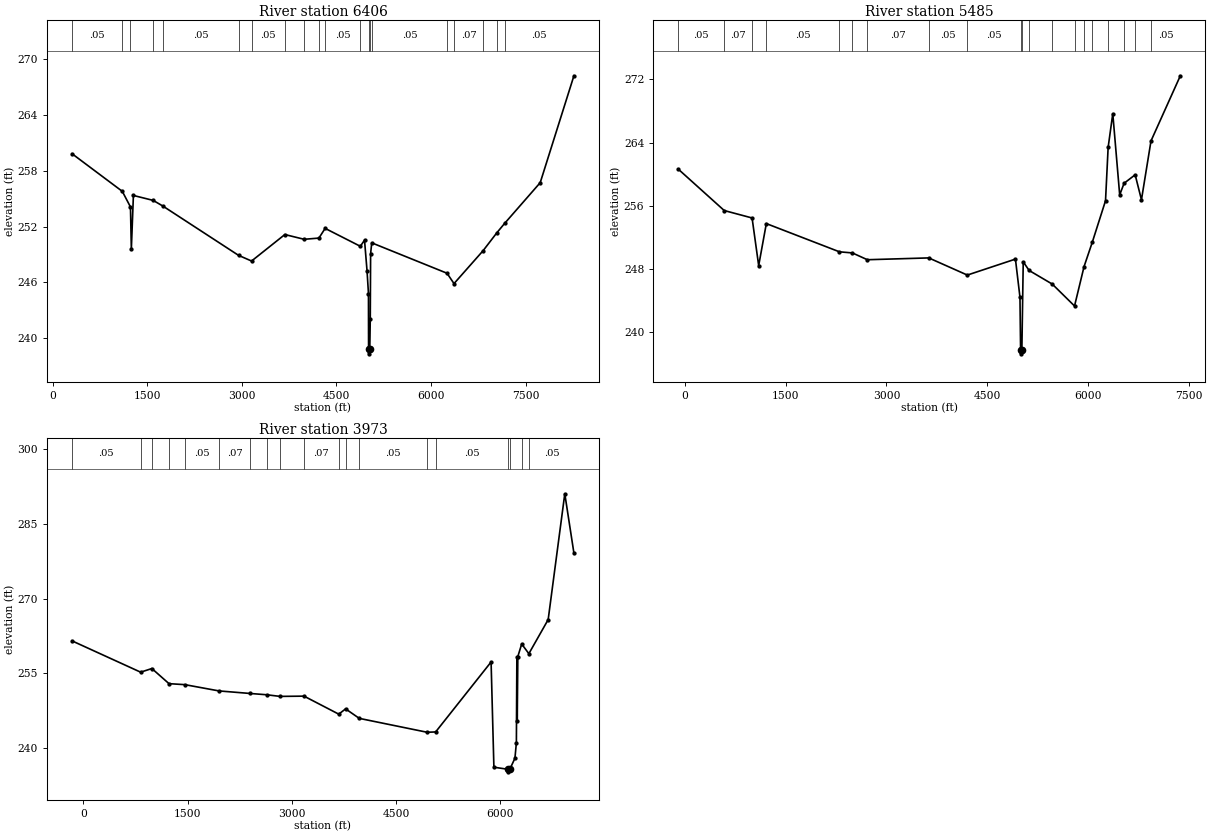
Type RM Length L Ch R = 1 ,6406    ,921,921,921
BEGIN DESCRIPTION:
B19598
END DESCRIPTION:
XS GIS Cut Line= 3
      2500816.14     13735769.16       2499775.3     13731432.32
      2498280.39     13728269.18
#Sta/Elev= 30
   308.7   259.8  1105.2  255.77  1234.7   254.1  1248.8  249.59  1281.3  255.33
    1595   254.8  1749.3  254.19  2948.4  248.91  3155.3   248.3  3683.1  251.14
  3989.1  250.63  4223.3  250.76  4321.8   251.8  4880.3  249.88  4946.6  250.54
  4986.6  247.24  5009.1  244.81  5010.8  238.85  5011.3  238.35  5029.9  238.85
  5037.6  242.07  5043.2   249.1  5061.2  250.25  6255.2  246.99  6365.5  245.88
  6827.1  249.41  7046.4  251.34  7169.1  252.34  7732.7   256.7  8267.3  268.16
#Mann= 20 ,-1 , 0
   308.7     .05       0  1105.2     .07       0  1234.7     .05       0
    1595     .07       0  1749.3     .05       0  2948.4     .07       0
  3155.3     .05       0  3683.1     .05       0  3989.1     .07       0
  4223.3    .035       0  4321.8     .05       0  4880.3      .1       0
  5010.8     .05       0  5029.9      .1       0  5061.2     .05       0
  6255.2     .05       0  6365.5     .07       0  6827.1     .05       0
  7046.4     .07       0  7169.1     .05       0
Bank Sta=5010.8,5029.9
XS Rating Curve= 0 ,0
Exp/Cntr=0.3,0.1

Type RM Length L Ch R = 1 ,5485    ,1512,1512,1512
BEGIN DESCRIPTION:
B19597
END DESCRIPTION:
XS GIS Cut Line= 3
      2501000.45     13735628.16      2500436.66     13730933.59
      2499429.04     13728398.29
#Sta/Elev= 30
   -90.4  260.61   589.6   255.4  1003.3  254.46  1101.3  248.44  1214.9  253.75
  2301.4  250.18  2493.4  250.04    2716  249.18  3628.1  249.41  4201.3  247.24
  4916.2  249.26  4983.5  244.44  4992.7  237.78  4993.2  237.28  5011.8  237.78
  5032.1  248.91  5120.1  247.82  5463.3   246.1  5794.2  243.33    5936  248.32
  6058.8  251.41  6254.7  256.64  6293.5  263.38  6362.6  267.65  6465.2  257.38
  6530.7  258.85  6695.1  259.92  6788.6  256.76  6930.3   264.2  7366.1  272.44
#Mann= 20 ,-1 , 0
   -90.4     .05       0   589.6     .07       0  1003.3     .05       0
  1214.9     .05       0  2301.4     .07       0  2493.4     .12       0
    2716     .07       0  3628.1     .05       0  4201.3     .05       0
  4992.7     .05       0  5011.8     .12       0  5120.1     .05       0
  5463.3     .07       0  5794.2     .07       0    5936     .05       0
  6058.8     .07       0  6293.5     .05       0  6530.7     .07       0
  6695.1     .05       0  6930.3     .05       0
Bank Sta=4992.7,5011.8
XS Rating Curve= 0 ,0
Exp/Cntr=0.3,0.1

Type RM Length L Ch R = 1 ,3973    ,0,0,0
BEGIN DESCRIPTION:
B19596
END DESCRIPTION:
XS GIS Cut Line= 3
      2501184.76     13735541.44      2501184.76      13730651.7
      2500545.45     13728408.67
#Sta/Elev= 30
  -161.5  261.51   825.2  255.22   986.8  255.95  1233.6  252.91  1462.1  252.71
    1953  251.45  2398.8  250.94  2637.2  250.68  2831.5  250.35  3176.7   250.4
  3676.4  246.78  3774.8  247.84  3971.8  245.93  4947.4  243.14  5070.5   243.2
  5868.6  257.27    5909  236.11  6117.8  235.68  6118.3  235.18  6137.6  235.68
  6211.8  237.92  6232.6  241.04  6239.6   258.3  6244.8  245.37  6253.4  258.37
    6309  260.88  6412.2  258.94  6690.1  265.79  6929.2  291.09  7060.6  279.16
#Mann= 19 ,-1 , 0
  -161.5     .05       0   825.2     .07       0   986.8     .12       0
  1233.6     .07       0  1462.1     .05       0    1953     .07       0
  2398.8     .05       0  2637.2     .07       0  2831.5     .05       0
  3176.7     .07       0  3676.4    .035       0  3774.8     .07       0
  3971.8     .05       0  4947.4     .12       0  5070.5     .05       0
  6117.8     .05       0  6137.6     .05       0    6309    .035       0
  6412.2     .05       0
Bank Sta=6117.8,6137.6
XS Rating Curve= 0 ,0
Exp/Cntr=0.3,0.1

Chan Stop Cuts=-1
Use User Specified Reach Order=0
Composite Channel Slope=5