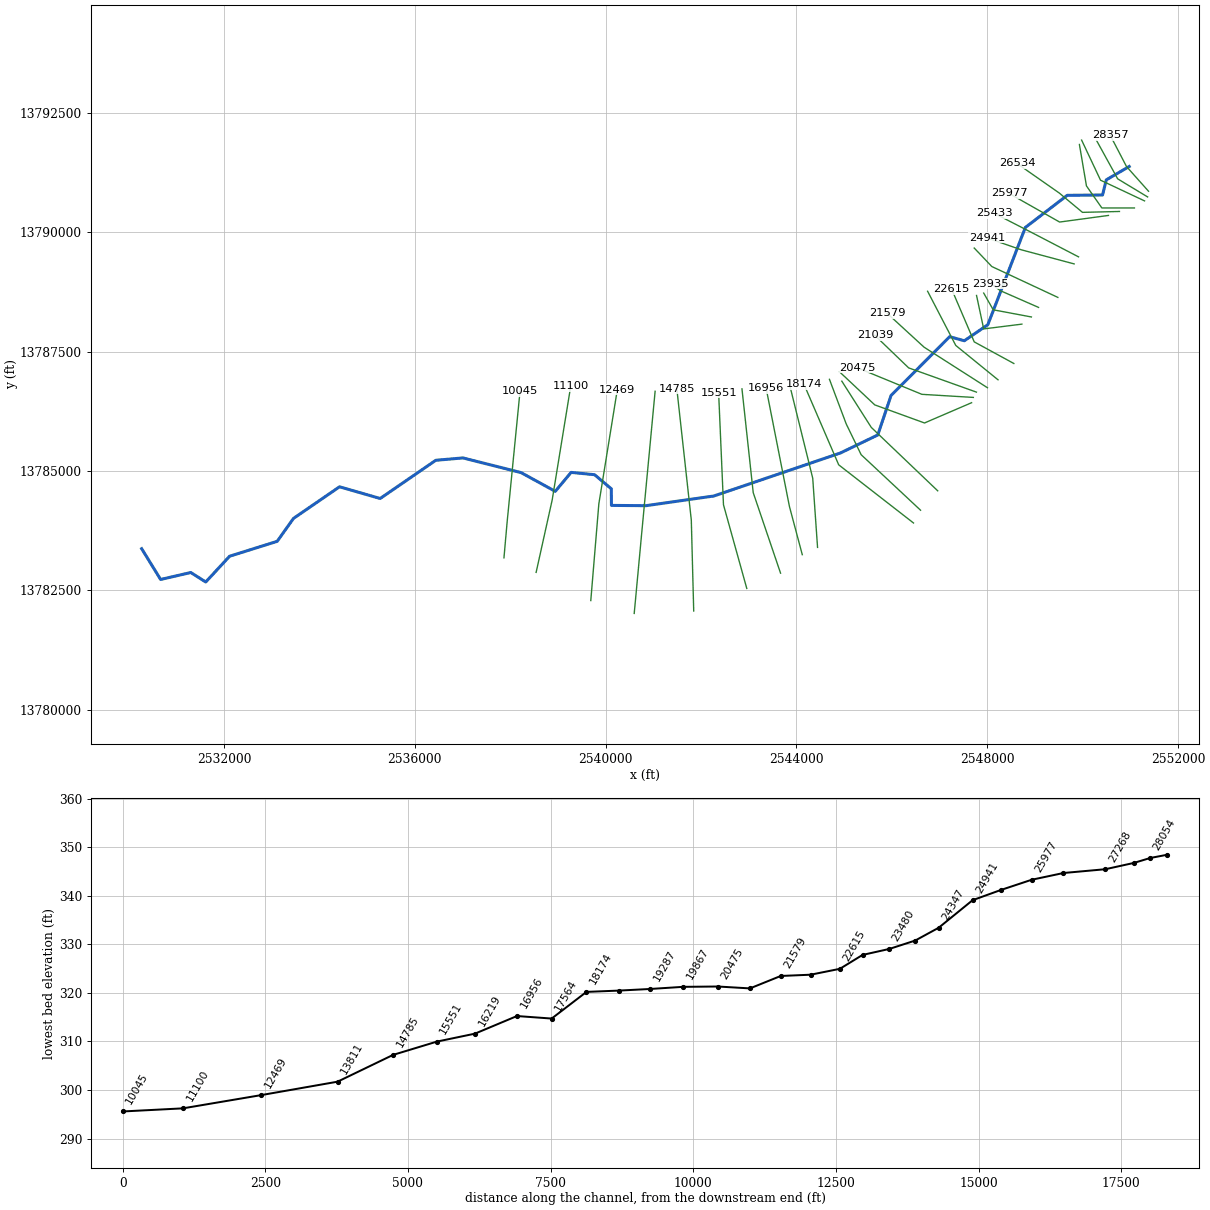
--- OBAR CREEK.prj (project) ---

Proj Title=OBAR CREEK Base Level Engineering
Current Plan=p01
Default Exp/Contr=0.3,0.1
English Units
Geom File=g01
Flow File=f01
Plan File=p01
Y Axis Title=Elevation
X Axis Title(PF)=Main Channel Distance
X Axis Title(XS)=Station
BEGIN DESCRIPTION:
OBAR CREEK
END DESCRIPTION:
DSS Export Rating Curves= 0
DSS Export Rating Curve Sorted= 0
DSS Export Volume Flow Curves= 0
DXF OffsetX= 0
DXF OffsetY= 0
DXF ScaleX= 1
DXF ScaleY= 10

--- OBAR CREEK.p01 (plan) ---

Plan Title=Multiple Run
Short Identifier=Multiple
Geom File=g01
Flow File=f01
Subcritical Flow
K Sum by GR= 0
Std Step Tol= 0.01
Critical Tol= 0.01
Num of Std Step Trials= 20
Max Error Tol= 0.3
Flow Tol Ratio= 0.001
Split Flow NTrial= 30
Split Flow Tol= 0.02
Split Flow Ratio= 0.02
Log Output Level= 0
Friction Slope Method= 1
Unsteady Friction Slope Method= 2
Unsteady Bridges Friction Slope Method= 1
Parabolic Critical Depth
Global Vel Dist=  1 , 1 , 1
Global Log Level= 0
CheckData=True
Encroach Param= -1, 0, 0, 0
BEGIN DESCRIPTION:
Multiple Run
END DESCRIPTION:

--- OBAR CREEK.f01 (steady flow) ---

Flow Title=Multiple
Number of Profiles=7
Profile Names=10-year,25-year,50-year,1pct_min,100-year,1pct_plu,500-year
River Rch & RM= OBAR CREEK,Reach-1,28357
     900    1464    1978    1294    2581    5150    4349
River Rch & RM= OBAR CREEK,Reach-1,25977
    1094    1797    2445    1608    3209    6403    5473
River Rch & RM= OBAR CREEK,Reach-1,25433
    1786    2994    4127    2746    5478   10931    9562
River Rch & RM= OBAR CREEK,Reach-1,18743
    2441    4123    5711    3814    7609   15182   13378
River Rch & RM= OBAR CREEK,Reach-1,17564
    2998    5112    7124    4782    9542   19038   16960
River Rch & RM= OBAR CREEK,Reach-1,3171
    3099    5282    7360    4939    9855   19663   17505
Boundary for River Rch & Prof#=OBAR CREEK,Reach-1,1
Up Type=0
Dn Type=3
Dn Slope=0.005
Boundary for River Rch & Prof#=OBAR CREEK,Reach-1,2
Up Type=0
Dn Type=3
Dn Slope=0.005
Boundary for River Rch & Prof#=OBAR CREEK,Reach-1,3
Up Type=0
Dn Type=3
Dn Slope=0.005
Boundary for River Rch & Prof#=OBAR CREEK,Reach-1,4
Up Type=0
Dn Type=3
Dn Slope=0.005
Boundary for River Rch & Prof#=OBAR CREEK,Reach-1,5
Up Type=0
Dn Type=3
Dn Slope=0.005
Boundary for River Rch & Prof#=OBAR CREEK,Reach-1,6
Up Type=0
Dn Type=3
Dn Slope=0.005
Boundary for River Rch & Prof#=OBAR CREEK,Reach-1,7
Up Type=0
Dn Type=3
Dn Slope=0.005

--- OBAR CREEK.g01 (geometry) ---

Geom Title=Existing Conditions
Program Version=4.10

River Reach=OBAR CREEK      ,Reach-1
Reach XY= 30
        2550975.       13791375.      2550494.58     13791095.15
      2550416.52     13790778.51       2549676.5     13790771.39
      2548798.18      13790098.7      2548011.38     13788061.73
      2547519.14     13787727.06      2547211.37     13787812.06
      2545982.86     13786581.17      2545705.39      13785754.8
      2544923.35     13785378.17      2542269.06     13784477.26
      2540845.15     13784274.64      2540122.22     13784280.36
      2540119.89      13784627.3      2539769.33     13784923.02
       2539276.5     13784971.54      2538945.06     13784574.79
      2538228.31     13784966.92      2537009.79     13785274.49
      2536440.21     13785224.49        2535275.       13784425.
      2534422.71      13784669.9      2533458.32     13784008.36
      2533116.52     13783528.51      2532117.94     13783215.99
      2531619.11     13782676.96      2531304.97     13782875.44
      2530672.69     13782730.06        2530275.       13783375.

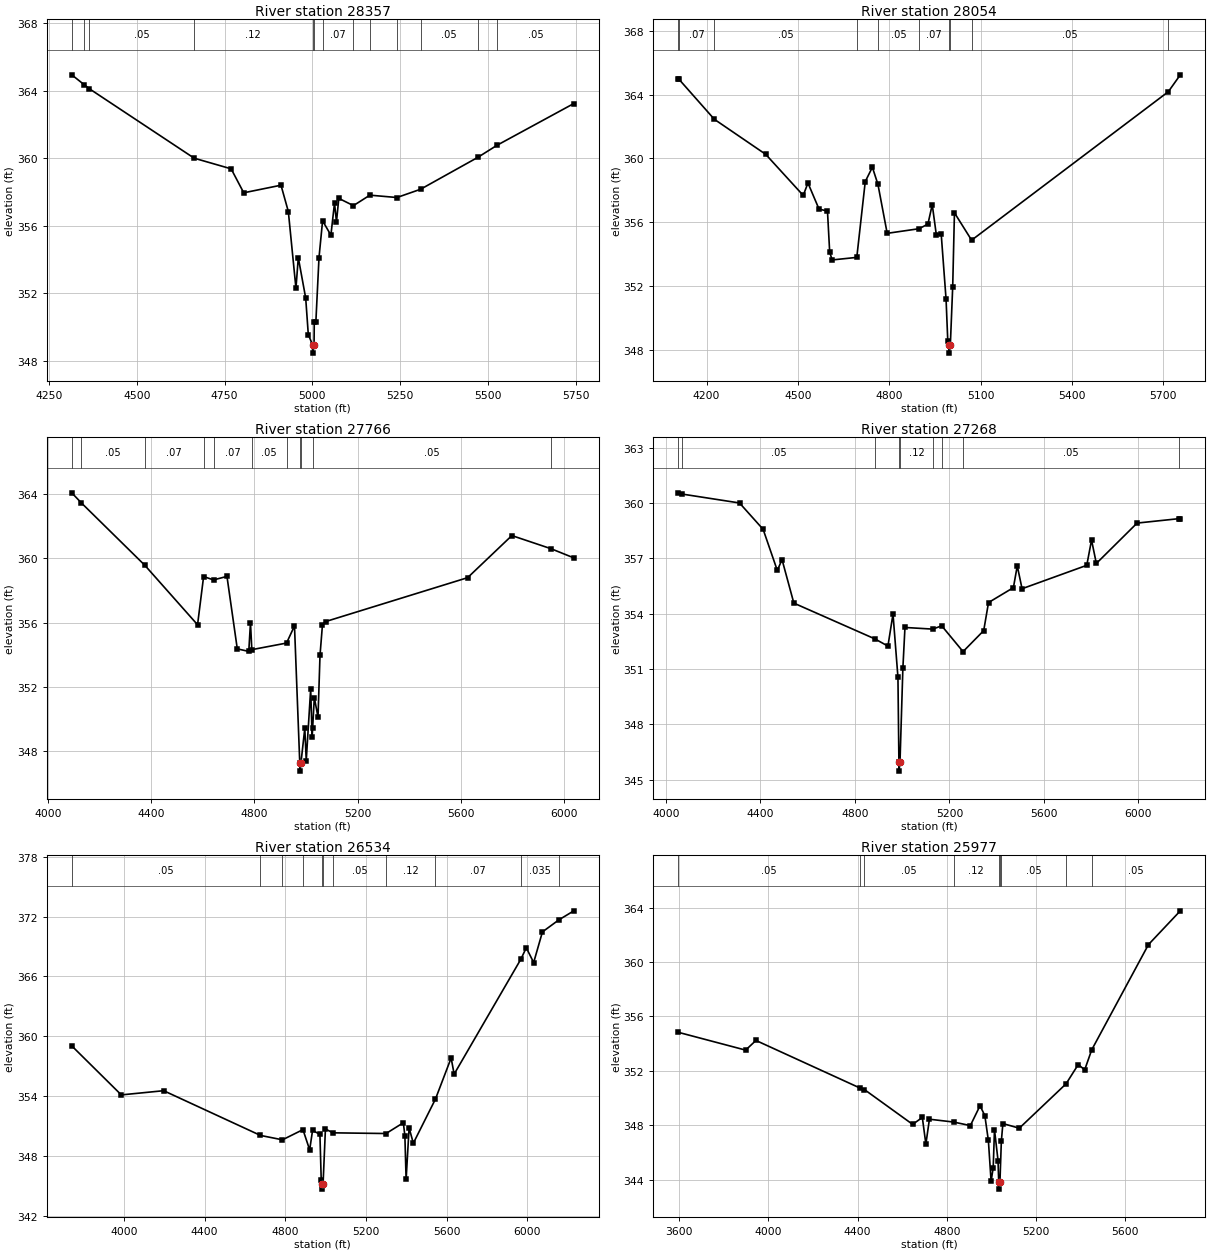
Type RM Length L Ch R = 1 ,28357   ,303,303,303
BEGIN DESCRIPTION:
OBAR CREEK 19.0
END DESCRIPTION:
XS GIS Cut Line= 3
      2551379.37     13790857.67      2550918.21     13791374.17
      2550576.92     13792029.06
#Sta/Elev= 30
  4314.2  364.95  4349.9  364.36    4364  364.13  4663.1  360.01  4768.4  359.38
  4804.3  357.96  4910.5  358.41  4931.4  356.85  4953.1   352.3  4959.8  354.12
  4980.9  351.72  4988.3  349.56  5000.3  348.96  5000.6  348.46  5004.7  348.96
  5005.3  350.33  5009.9  350.33  5018.8  354.12    5029   356.3  5052.7  355.45
    5063  357.35  5068.6  356.24  5075.2  357.63  5116.9   357.2  5163.8  357.82
  5240.9  357.68  5308.3  358.17  5471.4  360.06  5526.5  360.78  5745.1  363.25
#Mann= 13 ,-1 , 0
  4314.2     .05       0  4349.9     .07       0    4364     .05       0
  4663.1     .12       0  5000.3     .05       0  5004.7     .12       0
    5029     .07       0  5116.9     .12       0  5163.8     .05       0
  5240.9     .07       0  5308.3     .05       0  5471.4     .07       0
  5526.5     .05       0
Bank Sta=5000.3,5004.7
XS Rating Curve= 0 ,0
Exp/Cntr=0.3,0.1

Type RM Length L Ch R = 1 ,28054   ,288,288,288
BEGIN DESCRIPTION:
B19856
END DESCRIPTION:
XS GIS Cut Line= 3
      2551360.99     13790737.71      2550733.74      13791115.9
      2550291.02     13791918.33
#Sta/Elev= 30
  4107.1  364.99  4108.6  364.99  4225.6  362.46  4394.3  360.26  4517.6  357.68
  4533.1  358.46  4569.5  356.82  4597.2   356.7  4604.5  354.11  4612.7  353.63
  4693.5  353.79  4721.3  358.55  4744.7  359.45    4763  358.37  4793.3   355.3
    4898  355.59  4927.1  355.88  4941.3   357.1  4954.6  355.22  4970.7  355.26
  4986.7  351.16  4992.4  348.51  4996.2  348.28  4996.5  347.78  5000.7  348.28
  5008.5  351.96  5014.2  356.59  5070.6  354.87  5716.6  364.19    5756  365.25
#Mann= 10 ,-1 , 0
  4107.1     .05       0  4108.6     .07       0  4225.6     .05       0
  4693.5     .07       0    4763     .05       0    4898     .07       0
  4996.2     .05       0  5000.7     .07       0  5070.6     .05       0
  5716.6     .07       0
Bank Sta=4996.2,5000.7
XS Rating Curve= 0 ,0
Exp/Cntr=0.3,0.1

Type RM Length L Ch R = 1 ,27766   ,498,498,498
BEGIN DESCRIPTION:
B19855
END DESCRIPTION:
XS GIS Cut Line= 3
      2551296.41     13790654.71      2550374.01     13791088.23
      2549977.41     13791927.55
#Sta/Elev= 30
  4091.6  364.08  4128.4  363.46    4375  359.57  4579.5  355.87    4603  358.87
  4641.6  358.66  4693.6  358.88  4733.6  354.37  4778.2  354.21  4784.8     356
    4790  354.32  4924.7  354.73  4955.5   355.8    4976  347.26  4976.3  346.76
  4980.5  347.26  4995.5  349.43  5001.1  347.42  5018.3  351.87  5023.9  348.86
    5026  349.47  5032.4  351.34  5046.7  350.12  5054.5  353.97    5064  355.87
  5076.6  356.07  5627.1   358.8  5798.7  361.42  5950.9   360.6  6039.1  360.03
#Mann= 11 ,-1 , 0
  4091.6     .07       0  4128.4     .05       0    4375     .07       0
    4603     .05       0  4641.6     .07       0    4790     .05       0
  4924.7     .07       0    4976     .05       0  4980.5     .07       0
    5026     .05       0  5950.9     .07       0
Bank Sta=4976,4980.5
XS Rating Curve= 0 ,0
Exp/Cntr=0.3,0.1

Type RM Length L Ch R = 1 ,27268   ,734,734,734
BEGIN DESCRIPTION:
B19854
END DESCRIPTION:
XS GIS Cut Line= 4
      2551084.26     13790507.14      2550401.68     13790507.14
      2550078.85     13790968.32      2549931.28     13791835.33
#Sta/Elev= 30
    4052  360.56  4069.8  360.49  4311.3  360.01  4411.3  358.58  4471.3  356.35
  4491.3  356.94  4541.3  354.58  4884.3  352.64  4939.5  352.25    4961  353.99
  4981.9  350.56    4986  345.97  4986.4  345.47  4990.6  345.97  5002.8  351.06
  5011.6  353.26  5129.4  353.17  5167.1  353.35  5257.5  351.95  5344.9  353.09
  5365.2  354.61  5470.6  355.42  5486.9   356.6  5507.2  355.36  5781.1  356.63
  5801.3     358  5821.6  356.73  5994.1  358.92  6171.9  359.16    6177  359.16
#Mann= 9 ,-1 , 0
    4052     .07       0  4069.8     .05       0  4884.3     .12       0
    4986     .05       0  4990.6     .12       0  5129.4     .05       0
  5167.1     .12       0  5257.5     .05       0  6171.9     .12       0
Bank Sta=4986,4990.6
XS Rating Curve= 0 ,0
Exp/Cntr=0.3,0.1

Type RM Length L Ch R = 1 ,26534   ,557,557,557
BEGIN DESCRIPTION:
B19853
END DESCRIPTION:
XS GIS Cut Line= 4
      2550770.59     13790433.35      2549995.84      13790414.9
      2549506.99     13790820.74      2548621.54     13791438.71
#Sta/Elev= 30
  3741.2  359.04  3986.9  354.13  4196.9  354.55  4677.1  350.07  4786.1  349.63
  4887.8  350.65  4921.1  348.62  4935.4  350.57  4971.9  350.18  4978.4   345.6
  4982.9  345.19  4983.2  344.69  4987.5  345.19  4999.2  350.71  5036.9  350.33
  5299.9  350.26  5385.7  351.34  5393.3  350.03  5399.4  345.66  5414.2  350.83
  5435.2  349.29  5544.9  353.71  5622.7  357.83  5637.6  356.21  5968.7  367.73
  5995.4  368.87    6032  367.39  6075.5  370.46  6157.4  371.67  6231.3  372.57
#Mann= 11 ,-1 , 0
  3741.2     .05       0  4677.1     .07       0  4786.1     .12       0
  4887.8     .07       0  4982.9     .05       0  4987.5     .07       0
  5036.9     .05       0  5299.9     .12       0  5544.9     .07       0
  5968.7    .035       0  6157.4     .05       0
Bank Sta=4982.9,4987.5
XS Rating Curve= 0 ,0
Exp/Cntr=0.3,0.1

Type RM Length L Ch R = 1 ,25977   ,544,544,544
BEGIN DESCRIPTION:
B19852
END DESCRIPTION:
XS GIS Cut Line= 3
      2550540.07     13790350.34      2549516.21     13790211.98
      2548456.79     13790810.78
#Sta/Elev= 30
  3596.4  354.83  3898.4  353.52  3944.6  354.23  4411.3  350.73  4430.7  350.62
    4647  348.06  4690.3  348.57  4706.2  346.61  4722.1  348.44  4831.3  348.23
  4905.5  347.97  4948.8  349.43  4970.4  348.71  4986.3  346.88  4998.5  343.88
    5008  344.88  5013.7  347.67  5029.6   345.4  5032.7   343.8  5033.1   343.3
  5038.1   343.8  5044.4  346.81  5051.3  348.12  5124.9  347.78  5334.4  351.04
  5389.1  352.46    5418  352.07  5449.4  353.54  5703.8  361.28  5846.5  363.76
#Mann= 9 ,-1 , 0
  3596.4     .05       0  4411.3     .12       0  4430.7     .05       0
  4831.3     .12       0  5032.7     .05       0  5038.1     .12       0
  5044.4     .05       0  5334.4    .035       0  5449.4     .05       0
Bank Sta=5032.7,5038.1
XS Rating Curve= 0 ,0
Exp/Cntr=0.3,0.1

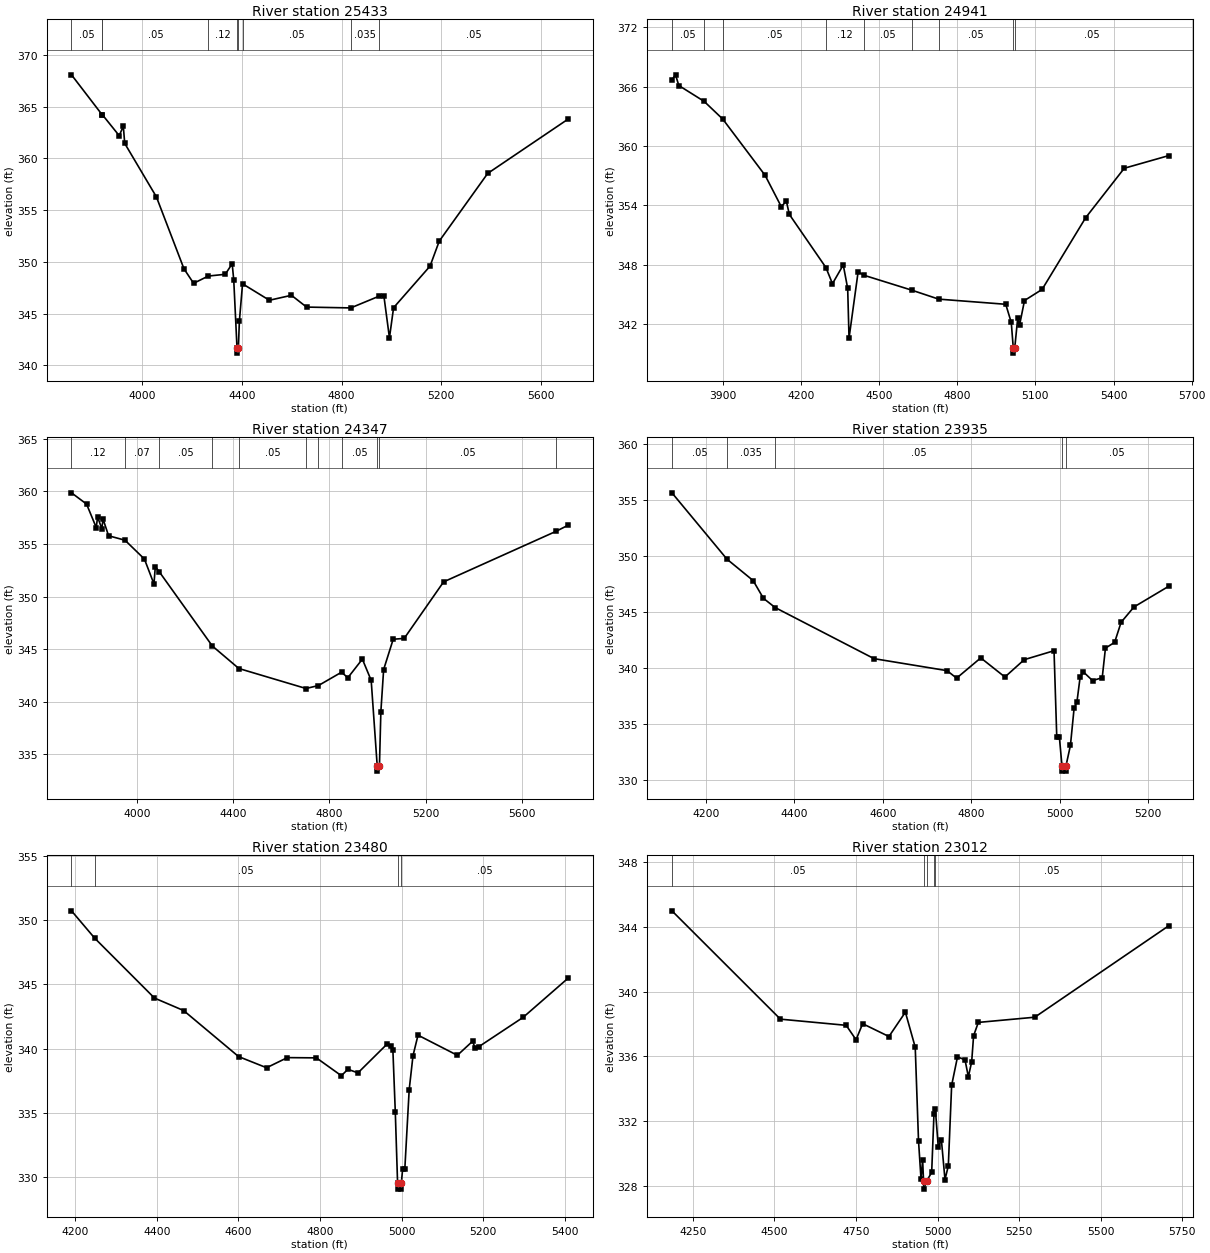
Type RM Length L Ch R = 1 ,25433   ,492,492,492
BEGIN DESCRIPTION:
OBAR CREEK 18.0
END DESCRIPTION:
XS GIS Cut Line= 3
      2549912.81     13789483.32      2548935.12     13789990.61
      2548141.88     13790396.46
#Sta/Elev= 30
  3716.6  368.08  3839.2  364.23  3840.3  364.23    3908   362.2  3924.5  363.11
  3930.2  361.45  4057.3  356.28  4167.9  349.33  4206.5  347.93  4265.6  348.63
  4333.6   348.8  4361.3  349.82  4367.6  348.25  4380.7  341.68  4381.2  341.18
  4386.2  341.68  4390.1  344.24  4402.9  347.88  4510.6  346.29  4599.1  346.77
  4659.8  345.63    4837  345.55  4949.3  346.67  4969.8  346.74  4992.3  342.66
  5008.9  345.57  5155.2  349.59  5192.2  352.01  5386.5  358.55  5709.1   363.8
#Mann= 9 ,-1 , 0
  3716.6     .05       0  3839.2     .07       0  3840.3     .05       0
  4265.6     .12       0  4380.7     .05       0  4386.2     .12       0
  4402.9     .05       0    4837    .035       0  4949.3     .05       0
Bank Sta=4380.7,4386.2
XS Rating Curve= 0 ,0
Exp/Cntr=0.3,0.1

Type RM Length L Ch R = 1 ,24941   ,594,594,594
BEGIN DESCRIPTION:
OBAR CREEK 17.0
END DESCRIPTION:
XS GIS Cut Line= 3
      2549820.57     13789335.74      2548713.75     13789630.89
      2547994.33     13789879.92
#Sta/Elev= 30
  3704.4  366.68  3718.1  367.18  3730.9   366.1  3828.1   364.5  3899.6  362.71
    4062  357.04  4124.1  353.88  4143.8  354.42  4155.2  353.09  4295.6  347.73
  4320.8   346.1  4362.2  347.99  4379.2  345.62  4384.4   340.6  4419.3   347.3
  4440.4  346.96  4625.9  345.44  4728.6  344.54  4986.1  344.02  5007.3  342.19
  5015.1  339.59  5015.6  339.09  5020.6  339.59  5032.2  342.66  5039.1  341.91
  5058.1   344.4  5125.7  345.52    5293  352.76  5441.2  357.75  5611.2  359.02
#Mann= 9 ,-1 , 0
  3704.4     .05       0  3828.1     .07       0  3899.6     .05       0
  4295.6     .12       0  4440.4     .05       0  4625.9    .035       0
  4728.6     .05       0  5015.1     .05       0  5020.6     .05       0
Bank Sta=5015.1,5020.6
XS Rating Curve= 0 ,0
Exp/Cntr=0.3,0.1

Type RM Length L Ch R = 1 ,24347   ,412,412,412
BEGIN DESCRIPTION:
B19851
END DESCRIPTION:
XS GIS Cut Line= 3
       2549479.3     13788634.74      2548095.76     13789280.39
      2547726.85     13789667.75
#Sta/Elev= 30
  3729.3  359.86  3791.9  358.79  3832.1  356.56  3837.6  357.58  3854.9  356.46
  3860.5  357.35  3883.3  355.78  3951.3  355.36    4032  353.57  4071.7   351.2
  4077.2  352.84  4093.7  352.36  4313.9  345.31  4424.1  343.17  4702.9  341.27
  4754.4  341.55  4850.6  342.82  4876.5  342.29  4936.9  344.06  4973.5  342.04
  4998.5  333.92    4999  333.42  5007.8  333.92  5013.7  339.08  5025.2  343.07
  5064.9  345.95  5110.6  346.03  5274.1   351.4  5739.7  356.19    5791  356.78
#Mann= 11 ,-1 , 0
  3729.3     .12       0  3951.3     .07       0  4093.7     .05       0
  4313.9    .035       0  4424.1     .05       0  4702.9    .035       0
  4754.4     .12       0  4850.6     .05       0  4998.5     .05       0
  5007.8     .05       0  5739.7    .035       0
Bank Sta=4998.5,5007.8
XS Rating Curve= 0 ,0
Exp/Cntr=0.3,0.1

Type RM Length L Ch R = 1 ,23935   ,455,455,455
BEGIN DESCRIPTION:
OBAR CREEK 16.0
END DESCRIPTION:
XS GIS Cut Line= 3
      2549074.96     13788425.02        2548275.       13788775.
      2548074.97     13788925.02
#Sta/Elev= 30
  4122.8  355.65  4247.3  349.72  4306.4  347.81  4329.8  346.22  4356.1   345.4
    4580  340.83  4744.9  339.76  4766.7  339.09  4821.3   340.9  4875.9  339.19
  4919.6  340.74    4987  341.54  4993.2  333.82  4999.1  333.82  5004.9  331.28
  5005.4  330.78  5013.7  330.78  5014.2  331.28  5024.1  333.08  5032.4   336.4
  5038.7  336.93    5046  339.17  5053.3  339.65  5074.1  338.87    5096  339.13
  5103.3  341.77  5124.1  342.29  5138.7  344.08  5167.8  345.45    5246  347.29
#Mann= 5 ,-1 , 0
  4122.8     .05       0  4247.3    .035       0  4356.1     .05       0
  5004.9     .05       0  5014.2     .05       0
Bank Sta=5004.9,5014.2
XS Rating Curve= 0 ,0
Exp/Cntr=0.3,0.1

Type RM Length L Ch R = 1 ,23480   ,468,468,468
BEGIN DESCRIPTION:
OBAR CREEK 15.0
END DESCRIPTION:
XS GIS Cut Line= 3
      2548924.96     13788225.01        2548125.       13788375.
      2547925.01     13788724.99
#Sta/Elev= 30
  4190.8  350.74  4247.6  348.61  4394.2  343.94  4465.5  342.97  4600.3  339.38
  4668.9  338.51  4719.8   339.3    4791  339.28  4852.1  337.89  4868.2  338.39
  4892.8  338.11    4964  340.35  4973.3  340.22  4978.4   339.9  4984.3  335.09
  4989.9  329.55  4990.4  329.05  4998.7  329.05  4999.2  329.55  5002.2  330.58
  5007.6  330.58  5018.4  336.81  5027.7  339.45    5040  341.05  5136.4  339.48
  5173.9  340.58  5179.6  340.05    5189  340.15  5297.7  342.44  5407.8  345.49
#Mann= 4 ,-1 , 0
  4190.8    .035       0  4247.6     .05       0  4989.9     .05       0
  4999.2     .05       0
Bank Sta=4989.9,4999.2
XS Rating Curve= 0 ,0
Exp/Cntr=0.3,0.1

Type RM Length L Ch R = 1 ,23012   ,397,397,397
BEGIN DESCRIPTION:
OBAR CREEK 14.0
END DESCRIPTION:
XS GIS Cut Line= 3
      2548724.96       13788075.        2547925.       13787975.
        2547775.     13788675.02
#Sta/Elev= 30
    4186  344.98  4518.5   338.3  4720.1  337.92  4750.3  337.03  4770.5  338.02
  4851.1  337.23  4901.5  338.73  4931.7  336.57  4941.8  330.79  4949.4  328.45
  4954.4  329.61  4957.2  328.32  4957.7  327.82  4966.7  328.32  4982.1  328.85
  4989.1  332.43  4993.4  332.74  5002.4   330.4  5011.8  330.87  5022.9  328.41
  5033.1  329.25  5043.3  334.22  5061.2  335.97  5084.2   335.8  5094.5  334.75
  5104.7  335.67  5110.6  337.28  5125.1   338.1  5298.1  338.42  5708.1  344.05
#Mann= 5 ,-1 , 0
    4186     .05       0  4957.2     .05       0  4966.7     .05       0
  4989.1     .07       0  4993.4     .05       0
Bank Sta=4957.2,4966.7
XS Rating Curve= 0 ,0
Exp/Cntr=0.3,0.1

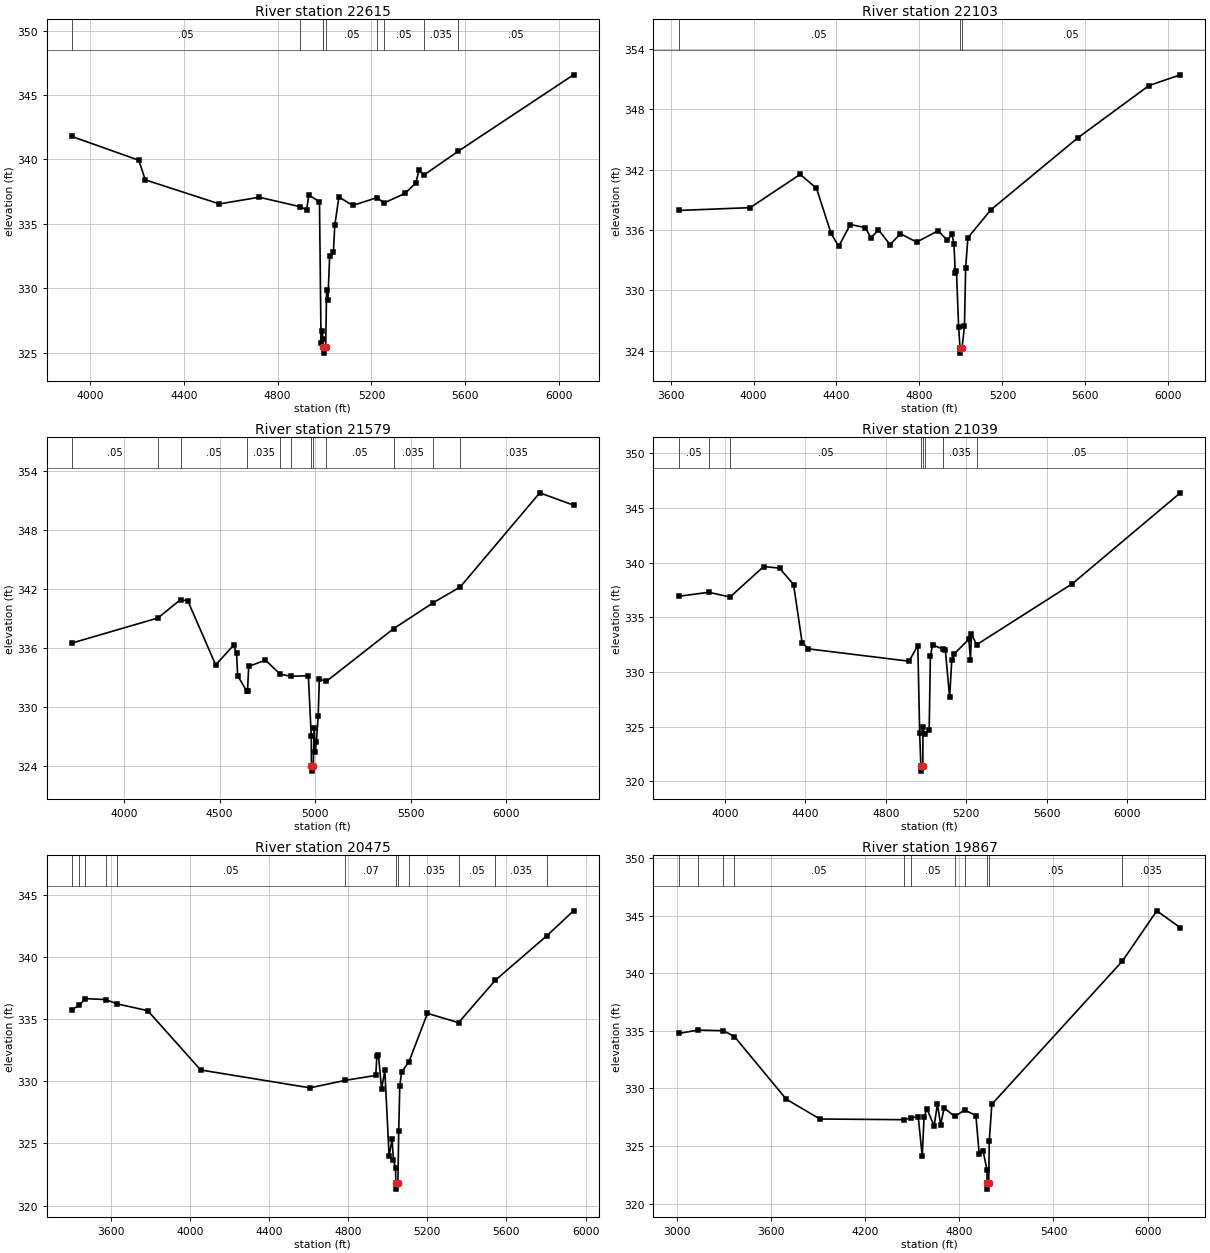
Type RM Length L Ch R = 1 ,22615   ,512,512,512
BEGIN DESCRIPTION:
B19850
END DESCRIPTION:
XS GIS Cut Line= 3
      2548556.98     13787251.16      2547726.82     13787703.14
      2547256.57     13788800.39
#Sta/Elev= 30
  3922.2  341.78    4208  339.93  4235.5  338.41  4551.8  336.54  4721.5  337.06
  4894.6  336.33  4923.9  336.09  4932.4  337.23  4978.3  336.71    4985  325.75
  4990.4  326.68    4993  326.03  4995.3  325.46  4995.8  324.96  5004.8  325.46
  5008.6  329.87    5014  329.07  5021.8  332.51  5037.6  332.81  5043.5  334.88
  5061.1  337.08  5119.7  336.42  5223.9  337.03  5252.9  336.61  5342.2  337.35
  5389.3  338.17  5402.6  339.17  5422.5  338.77  5570.6  340.64  6061.2  346.56
#Mann= 9 ,-1 , 0
  3922.2     .05       0  4894.6     .07       0    4993     .05       0
  4995.3     .05       0  5004.8     .05       0  5223.9     .07       0
  5252.9     .05       0  5422.5    .035       0  5570.6     .05       0
Bank Sta=4995.3,5004.8
XS Rating Curve= 0 ,0
Exp/Cntr=0.3,0.1

Type RM Length L Ch R = 1 ,22103   ,524,524,524
BEGIN DESCRIPTION:
B19849
END DESCRIPTION:
XS GIS Cut Line= 3
      2548224.93     13786909.88      2547339.42     13787629.35
      2546749.54     13788763.02
#Sta/Elev= 30
  3638.7  337.94  3983.9  338.22  4225.3  341.53  4303.6  340.14  4373.9  335.65
  4410.6  334.37  4466.6  336.54  4538.4  336.24  4566.3  335.21  4602.4  336.01
  4658.4  334.54    4708  335.63    4786  334.79  4889.9  335.92  4934.1  334.97
  4956.2  335.56  4966.4  334.63  4972.7  331.68  4978.3  331.91  4988.9  326.31
  4995.6  324.25  4996.1  323.75  5005.3  324.25  5016.9  326.44  5022.7  332.23
  5033.4  335.22  5143.9     338  5563.9  345.17  5906.3  350.36  6057.6  351.43
#Mann= 3 ,-1 , 0
  3638.7     .05       0  4995.6     .05       0  5005.3     .05       0
Bank Sta=4995.6,5005.3
XS Rating Curve= 0 ,0
Exp/Cntr=0.3,0.1

Type RM Length L Ch R = 1 ,21579   ,540,540,540
BEGIN DESCRIPTION:
B19848
END DESCRIPTION:
XS GIS Cut Line= 3
      2548003.55     13786743.86      2546675.32     13787592.46
      2545902.02     13788301.31
#Sta/Elev= 30
  3726.1   336.5  4176.8  339.05  4295.8  340.93  4333.7  340.78  4479.2  334.28
  4573.1  336.29  4588.3  335.48  4594.2  333.18  4641.6  331.62  4645.8  331.63
  4651.8  334.13  4739.7  334.77  4816.7  333.34    4872  333.13  4963.9  333.18
  4979.1  327.11  4980.2  323.99  4980.7  323.49  4989.9  323.99  4994.1  327.92
  5000.3  325.43  5006.2  326.49  5015.5  329.11  5021.4  332.84  5058.6  332.62
  5409.6  337.96  5617.1   340.6  5758.4   342.2  6174.7  351.77  6351.3  350.52
#Mann= 12 ,-1 , 0
  3726.1     .05       0  4176.8    .035       0  4295.8     .05       0
  4641.6    .035       0  4816.7     .05       0    4872     .12       0
  4980.2     .05       0  4989.9     .12       0  5058.6     .05       0
  5409.6    .035       0  5617.1     .05       0  5758.4    .035       0
Bank Sta=4980.2,4989.9
XS Rating Curve= 0 ,0
Exp/Cntr=0.3,0.1

Type RM Length L Ch R = 1 ,21039   ,564,564,564
BEGIN DESCRIPTION:
B19847
END DESCRIPTION:
XS GIS Cut Line= 3
      2547772.91     13786651.65      2546352.49     13787158.94
      2545643.01     13787840.78
#Sta/Elev= 30
  3770.8  336.93  3920.7   337.3  4026.3  336.86  4193.3  339.65  4272.2  339.51
    4342  338.01  4384.5   332.7  4415.5  332.12  4915.4  330.99  4959.2  332.41
  4968.5  324.38  4974.2  321.43  4974.7  320.93  4984.1  321.43  4984.7  324.94
  4993.1  324.31  5015.5  324.66  5021.6  331.44  5032.2  332.49  5082.7   332.1
  5095.9  332.02  5117.1  327.67  5127.8  331.07  5138.6  331.63  5212.7  333.01
  5220.4  331.13  5225.7  333.45  5251.3   332.5  5727.2  338.09  6263.1   346.4
#Mann= 8 ,-1 , 0
  3770.8     .05       0  3920.7    .035       0  4026.3     .05       0
  4974.2     .05       0  4984.1     .05       0  4993.1     .07       0
  5082.7    .035       0  5251.3     .05       0
Bank Sta=4974.2,4984.1
XS Rating Curve= 0 ,0
Exp/Cntr=0.3,0.1

Type RM Length L Ch R = 1 ,20475   ,608,608,608
BEGIN DESCRIPTION:
B19846
END DESCRIPTION:
XS GIS Cut Line= 3
      2547708.36     13786540.96       2546629.2     13786605.52
      2545282.57     13787158.93
#Sta/Elev= 30
  3402.3  335.78  3441.1  336.14  3471.1  336.67  3573.5  336.59  3632.4  336.24
  3786.3   335.7  4053.9  330.92  4606.9  329.48  4784.3  330.08  4939.5  330.48
  4944.9  332.01  4952.8  332.14  4968.9  329.39  4985.3  330.88  5006.9  323.98
  5022.2  325.35  5028.5  323.69  5039.3  323.02    5041  321.82  5041.5  321.32
  5051.4  321.82  5055.5  326.02  5060.9  329.61  5070.1  330.76  5107.3  331.58
  5200.8  335.48    5358  334.73  5544.1  338.15    5805  341.74  5939.3  343.74
#Mann= 12 ,-1 , 0
  3402.3     .05       0  3441.1     .07       0  3471.1    .035       0
  3573.5     .07       0  3632.4     .05       0  4784.3     .07       0
    5041     .05       0  5051.4     .07       0  5107.3    .035       0
    5358     .05       0  5544.1    .035       0    5805     .05       0
Bank Sta=5041,5051.4
XS Rating Curve= 0 ,0
Exp/Cntr=0.3,0.1

Type RM Length L Ch R = 1 ,19867   ,580,580,580
BEGIN DESCRIPTION:
B19845
END DESCRIPTION:
XS GIS Cut Line= 4
      2547671.48     13786430.27      2546684.54     13786005.98
      2545642.26     13786384.15      2544904.36     13787075.93
#Sta/Elev= 30
  3013.1  334.77  3136.8  335.06  3298.3  335.01  3368.7   334.5  3698.9  329.06
  3912.7  327.34  4447.7  327.28  4495.8  327.44    4539  327.55  4564.3   324.1
  4576.2  327.54  4594.9  328.21  4640.1  326.73  4661.4  328.65  4681.4  326.84
  4703.9   328.3  4771.2  327.56  4834.7  328.12    4906  327.64  4927.3  324.27
  4951.6  324.56  4976.9  322.92    4977  321.75  4977.5  321.25  4987.5  321.75
  4991.1  325.41  5007.6  328.62  5838.4  341.05  6057.8  345.42  6207.6  343.95
#Mann= 11 ,-1 , 0
  3013.1    .035       0  3136.8     .05       0  3298.3     .07       0
  3368.7     .05       0  4447.7     .07       0  4495.8     .05       0
  4771.2     .07       0  4834.7     .05       0    4977     .05       0
  4987.5     .05       0  5838.4    .035       0
Bank Sta=4977,4987.5
XS Rating Curve= 0 ,0
Exp/Cntr=0.3,0.1

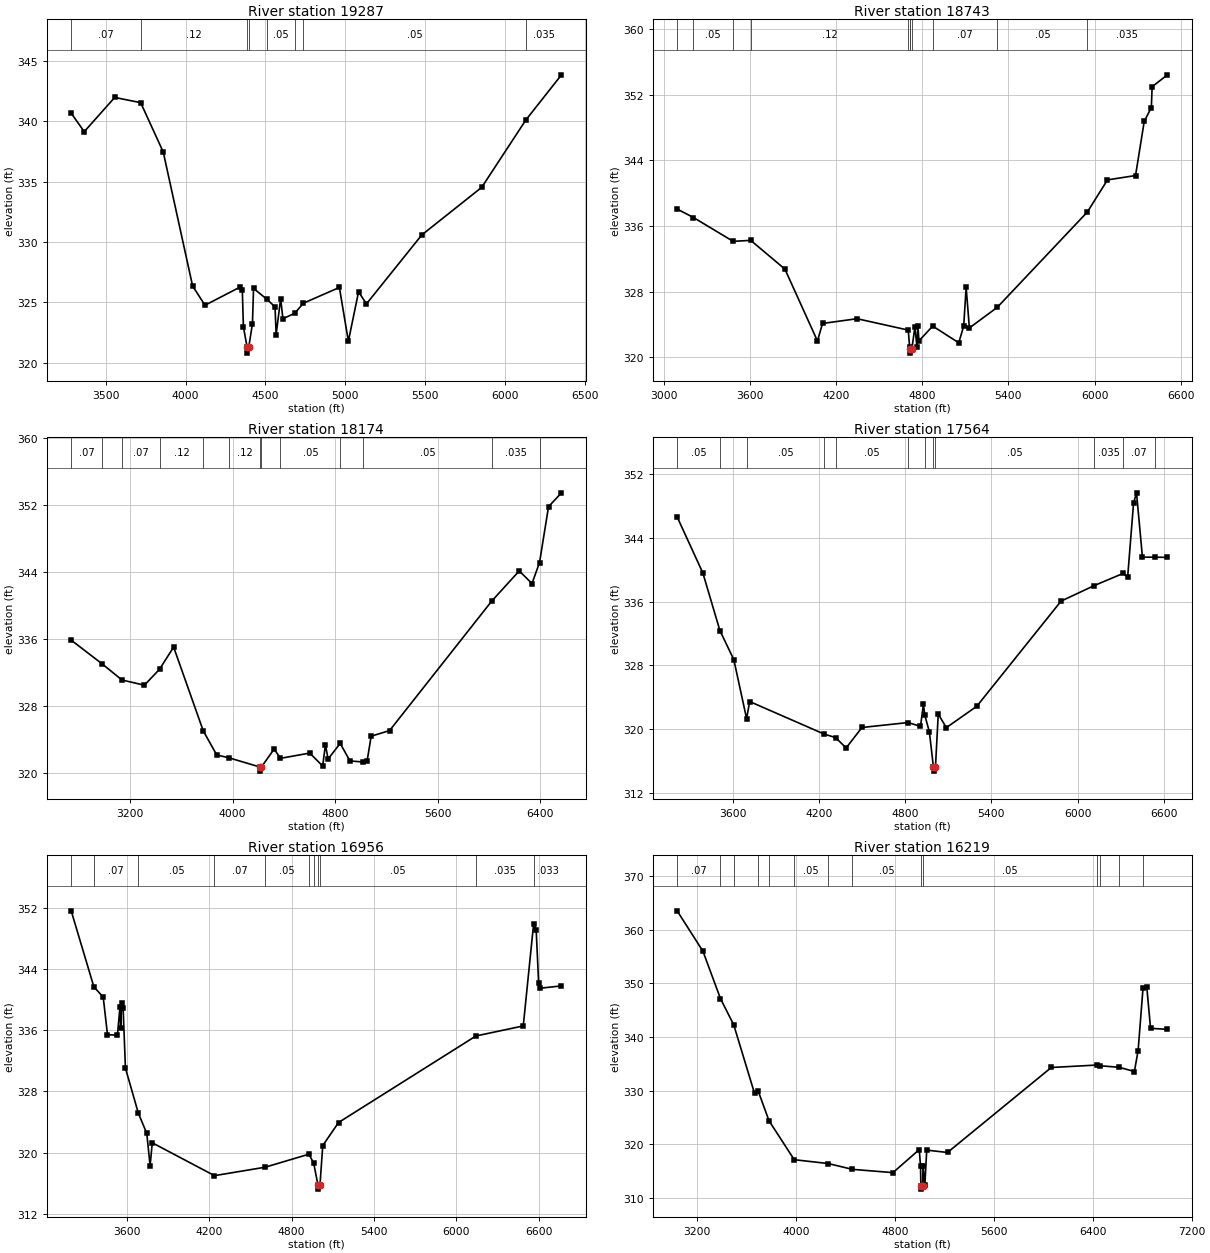
Type RM Length L Ch R = 1 ,19287   ,544,544,544
BEGIN DESCRIPTION:
B19844
END DESCRIPTION:
XS GIS Cut Line= 3
      2546961.23     13784585.55      2545568.47     13785913.75
      2544951.19     13786881.13
#Sta/Elev= 30
  3282.6  340.65  3364.4  339.12  3555.3  341.95  3717.9  341.52  3859.4  337.44
  4043.4  326.36  4121.1  324.77  4340.6  326.27  4354.8  326.04  4361.7  322.98
  4384.8  321.31  4385.3  320.81  4395.3  321.31  4418.3  323.24  4425.2  326.16
  4510.2  325.25  4559.9  324.63  4566.8  322.35  4595.1  325.32  4609.2  323.65
  4683.6  324.11  4737.8  324.94  4963.1  326.24  5019.4  321.79  5083.2  325.88
  5132.6  324.88  5479.3  330.58  5855.1  334.52  6131.1  340.08  6354.7  343.82
#Mann= 8 ,-1 , 0
  3282.6     .07       0  3717.9     .12       0  4384.8     .05       0
  4395.3     .12       0  4510.2     .05       0  4683.6     .12       0
  4737.8     .05       0  6131.1    .035       0
Bank Sta=4384.8,4395.3
XS Rating Curve= 0 ,0
Exp/Cntr=0.3,0.1

Type RM Length L Ch R = 1 ,18743   ,569,569,569
BEGIN DESCRIPTION:
B19843
END DESCRIPTION:
XS GIS Cut Line= 4
      2546601.56     13784179.67      2545356.33     13785341.88
      2545042.72     13785987.54      2544692.21     13786919.16
#Sta/Elev= 30
  3091.4  338.06  3205.2  337.03  3481.8  334.12  3604.3  334.24  3842.6  330.73
  4069.3  321.96  4104.5   324.1  4345.1  324.68  4701.9  323.29  4711.9  321.17
    4713  320.98  4713.5  320.48    4727  320.98  4748.3  323.68  4762.5  321.23
  4769.3  323.73  4776.7  321.98  4872.4  323.78  5053.9  321.74  5088.3  323.79
  5105.3  328.52  5127.9  323.55  5322.3  326.07  5949.9   337.7  6090.2  341.62
  6285.7  342.15  6346.2  348.75  6395.9  350.45  6401.3  352.99  6507.9  354.44
#Mann= 11 ,-1 , 0
  3091.4    .035       0  3205.2     .05       0  3481.8     .07       0
  3604.3     .12       0  4701.9     .07       0  4711.9     .12       0
    4713     .05       0    4727     .12       0  4872.4     .07       0
  5322.3     .05       0  5949.9    .035       0
Bank Sta=4713,4727
XS Rating Curve= 0 ,0
Exp/Cntr=0.3,0.1

Type RM Length L Ch R = 1 ,18174   ,610,610,610
BEGIN DESCRIPTION:
OBAR CREEK 13.0
END DESCRIPTION:
XS GIS Cut Line= 3
      2546453.96      13783912.2      2544885.92     13785129.73
      2544157.26     13786817.64
#Sta/Elev= 30
    2741  335.88  2982.3  333.04  3137.2  331.11  3311.9  330.49  3430.2   332.4
    3540  335.05  3770.9  325.03  3875.8  322.15  3974.3  321.79  4210.9  320.71
  4211.4  320.21  4224.9  320.71  4323.8  322.85  4372.9  321.74  4601.7  322.37
  4702.1  320.82  4723.7  323.35  4744.7  321.66    4839  323.53  4914.7  321.43
  5019.3   321.3  5048.6   321.4  5080.5  324.39  5224.1  325.06  6020.2  340.54
  6235.2  344.16  6334.6  342.65  6393.5  345.16  6463.8  351.85  6564.7   353.5
#Mann= 13 ,-1 , 0
    2741     .07       0  2982.3    .035       0  3137.2     .07       0
  3430.2     .12       0  3770.9     .07       0  3974.3     .12       0
  4210.9     .05       0  4224.9     .12       0  4372.9     .05       0
    4839     .07       0  5019.3     .05       0  6020.2    .035       0
  6393.5     .12       0
Bank Sta=4210.9,4224.9
XS Rating Curve= 0 ,0
Exp/Cntr=0.3,0.1

Type RM Length L Ch R = 1 ,17564   ,608,608,608
BEGIN DESCRIPTION:
OBAR CREEK 12.0
END DESCRIPTION:
XS GIS Cut Line= 3
      2544442.47     13783401.12      2544341.35     13784850.59
      2543869.72     13786753.93
#Sta/Elev= 30
  3211.5  346.65  3390.8   339.6  3509.4  332.37  3606.3  328.72  3695.3  321.31
  3716.6  323.46  4235.5  319.37  4315.3  318.93  4388.2  317.63  4498.5   320.2
  4819.5  320.82    4906  320.34  4926.6  323.11  4935.1  321.81  4967.8  319.65
  4996.2  315.22  4996.7  314.72  5010.3  315.22  5029.6  321.88  5086.1  320.18
  5298.2  322.87  5884.7  336.07  6116.8  338.03  6318.2  339.56  6348.3  339.06
  6389.5  348.36  6410.2  349.67  6451.4  341.59    6540  341.59  6625.4  341.56
#Mann= 12 ,-1 , 0
  3211.5     .05       0  3509.4     .07       0  3695.3     .05       0
  4235.5     .07       0  4315.3     .05       0  4819.5     .07       0
  4935.1     .05       0  4996.2     .05       0  5010.3     .05       0
  6116.8    .035       0  6318.2     .07       0    6540    .033       0
Bank Sta=4996.2,5010.3
XS Rating Curve= 0 ,0
Exp/Cntr=0.3,0.1

Type RM Length L Ch R = 1 ,16956   ,737,737,737
BEGIN DESCRIPTION:
OBAR CREEK 11.0
END DESCRIPTION:
XS GIS Cut Line= 3
      2544122.25     13783249.43      2543852.58     13784260.69
      2543363.81     13786738.24
#Sta/Elev= 30
  3193.8  351.58    3359  341.66  3427.2  340.31  3458.3   335.4  3530.7  335.35
    3549  338.98  3554.2  336.32  3561.8  339.58  3572.1   338.9  3589.1  331.04
    3683  325.16  3744.4  322.52  3768.8   318.3  3784.5  321.29  4237.7     317
  4606.5   318.1  4925.7   319.8  4960.4  318.64    4992  315.74  4992.5  315.24
  5006.1  315.74  5026.6  320.93  5141.7  323.94  6142.7  335.24  6487.2  336.55
  6562.7  349.88  6581.4  349.06  6599.3  342.15  6609.5  341.47  6765.7  341.78
#Mann= 11 ,-1 , 0
  3193.8     .05       0    3359     .07       0    3683     .05       0
  4237.7     .07       0  4606.5     .05       0  4925.7     .07       0
  4960.4     .05       0    4992     .05       0  5006.1     .05       0
  6142.7    .035       0  6562.7    .033       0
Bank Sta=4992,5006.1
XS Rating Curve= 0 ,0
Exp/Cntr=0.3,0.1

Type RM Length L Ch R = 1 ,16219   ,668,668,668
BEGIN DESCRIPTION:
OBAR CREEK 10.0
END DESCRIPTION:
XS GIS Cut Line= 3
      2543667.18      13782861.8      2543094.14     13784547.22
      2542858.26     13786720.69
#Sta/Elev= 30
    3037  363.55    3246     356  3387.5  347.18  3495.3  342.25  3663.5  329.46
  3693.7  329.87  3779.9  324.39  3984.4   317.1  4258.5  316.39  4455.1   315.3
  4783.1  314.69    4996  318.99  5006.1  315.84    5009  312.11  5009.5  311.61
  5023.2  312.11  5026.2     316  5041.1  312.41  5056.3  318.89  5224.3  318.45
  6063.8  334.31  6434.3  334.77    6455  334.64  6612.6  334.35  6736.2  333.56
  6766.3  337.48    6806  349.14  6836.7  349.26  6866.9  341.62  7003.4  341.43
#Mann= 14 ,-1 , 0
    3037     .07       0  3387.5     .12       0  3495.3     .07       0
  3693.7     .12       0  3779.9     .07       0  3984.4     .05       0
  4258.5     .07       0  4455.1     .05       0    5009     .05       0
  5023.2     .05       0  6434.3     .07       0    6455     .05       0
  6612.6    .035       0    6806    .033       0
Bank Sta=5009,5023.2
XS Rating Curve= 0 ,0
Exp/Cntr=0.3,0.1

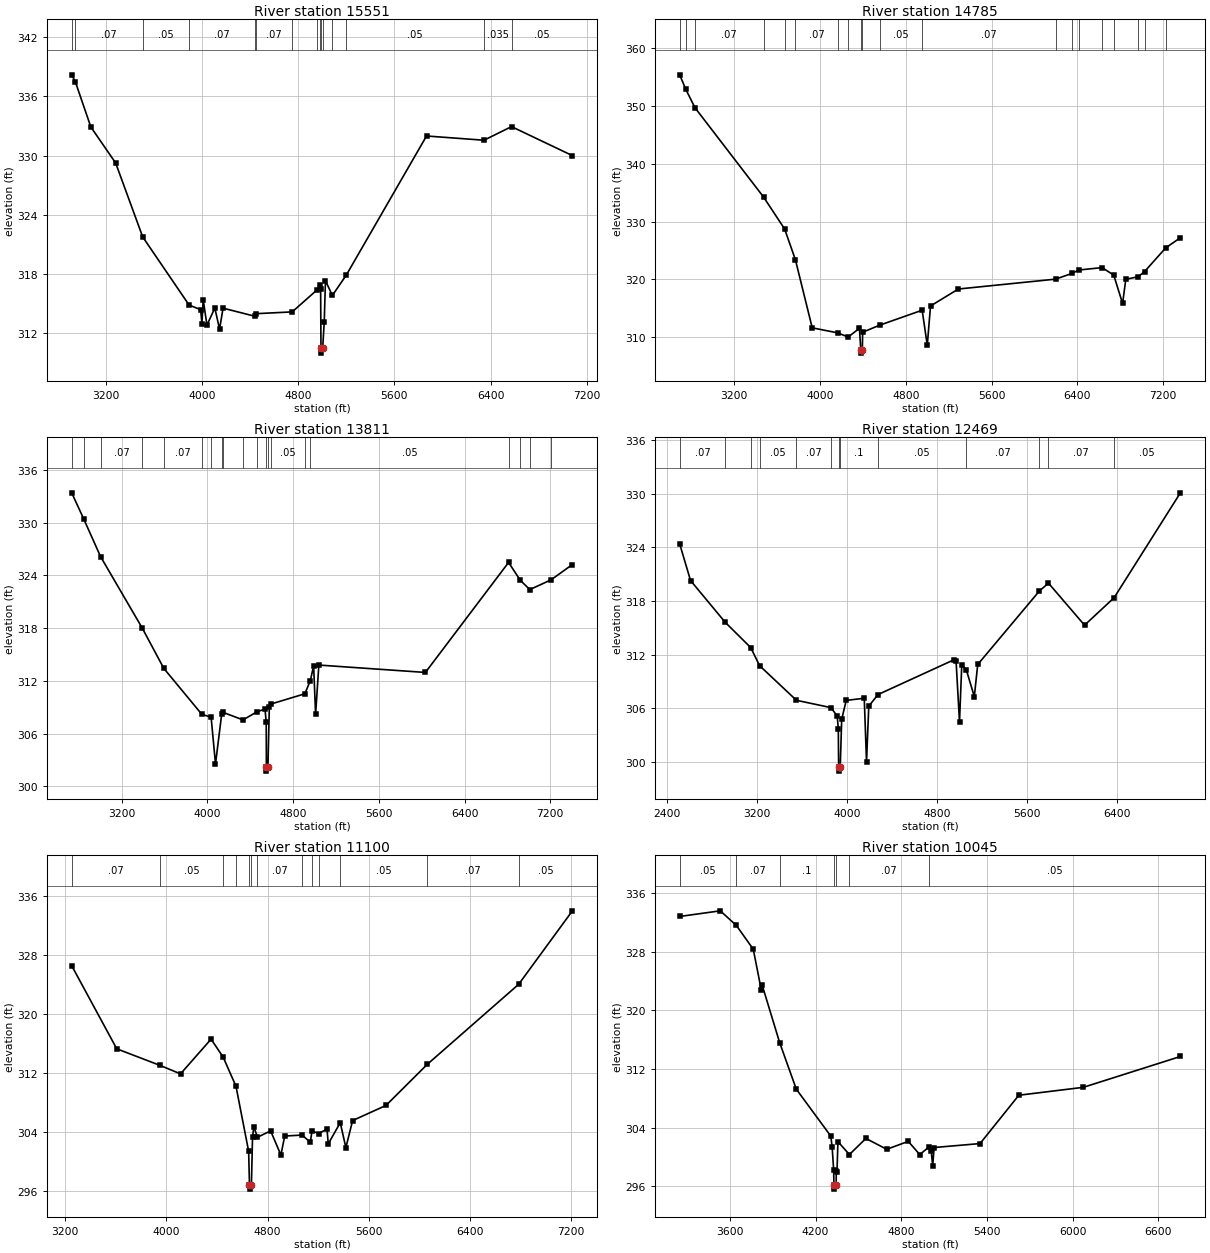
Type RM Length L Ch R = 1 ,15551   ,766,766,766
BEGIN DESCRIPTION:
OBAR CREEK 9.0
END DESCRIPTION:
XS GIS Cut Line= 3
       2542959.3     13782541.57      2542470.53      13784294.4
      2542369.41     13786637.12
#Sta/Elev= 30
    2916  338.18  2946.4  337.47  3075.3  332.89  3281.7  329.24  3506.5  321.75
  3892.7  314.84  3988.4  314.38  3999.2  312.96  4009.6   315.4  4040.8  312.81
  4106.5  314.54  4145.9   312.4  4174.9  314.53  4441.8   313.7  4451.9  313.97
    4750  314.15  4956.8  316.38  4983.5  316.91  4986.5  316.42  4989.4  310.47
  4989.9  309.97  5003.6  310.47  5016.6  313.16  5026.6  317.31  5084.2  315.82
    5200  317.88  5867.3  331.98  6344.9  331.55  6574.3  332.93  7080.6  329.99
#Mann= 15 ,-1 , 0
    2916    .035       0  2946.4     .07       0  3506.5     .05       0
  3892.7     .07       0  4441.8     .12       0  4451.9     .07       0
    4750     .05       0  4956.8     .07       0  4983.5     .05       0
  4989.4     .05       0  5003.6     .05       0  5084.2     .07       0
    5200     .05       0  6344.9    .035       0  6574.3     .05       0
Bank Sta=4989.4,5003.6
XS Rating Curve= 0 ,0
Exp/Cntr=0.3,0.1

Type RM Length L Ch R = 1 ,14785   ,974,974,974
BEGIN DESCRIPTION:
OBAR CREEK 8.0
END DESCRIPTION:
XS GIS Cut Line= 3
      2541846.93     13782069.65      2541796.37     13783974.17
      2541493.07     13786720.69
#Sta/Elev= 30
  2691.8  355.43  2747.8  352.96  2833.7  349.75  3473.8  334.27  3670.4  328.73
  3770.9   323.4  3927.6  311.62  4164.4  310.75  4262.8  310.03  4367.7  311.53
  4380.6  307.74  4381.1  307.24  4394.9  307.74  4397.7  310.86  4556.5  312.08
  4952.7  314.67  5000.3   308.6  5030.4   315.4  5289.9  318.34  6196.5  320.05
  6353.6  321.07  6412.6  321.63  6630.8  322.05  6738.9  320.74  6821.3  315.84
  6851.4  320.02    6967  320.47  7025.7  321.35  7223.1  325.46  7360.2  327.22
#Mann= 20 ,-1 , 0
  2691.8     .05       0  2747.8    .035       0  2833.7     .07       0
  3473.8     .07       0  3670.4     .12       0  3770.9     .07       0
  4164.4     .05       0  4262.8     .07       0  4380.6     .05       0
  4394.9     .12       0  4556.5     .05       0  4952.7     .07       0
  6196.5     .12       0  6353.6     .07       0  6412.6     .12       0
  6630.8     .07       0  6738.9     .12       0    6967     .07       0
  7025.7     .05       0  7223.1     .07       0
Bank Sta=4380.6,4394.9
XS Rating Curve= 0 ,0
Exp/Cntr=0.3,0.1

Type RM Length L Ch R = 1 ,13811   ,1342,1342,1342
BEGIN DESCRIPTION:
OBAR CREEK 7.0
END DESCRIPTION:
XS GIS Cut Line= 3
      2540599.72     13782019.09      2540768.26     13783822.49
      2541037.89      13786670.4
#Sta/Elev= 30
  2734.5  333.39  2846.2  330.43  3003.9  326.13  3393.6  317.98  3593.5  313.42
  3948.2  308.19  4035.5  307.85  4076.2  302.53  4134.6  308.27  4148.1   308.4
  4332.8  307.55  4461.8  308.46  4538.2  308.79  4549.5  307.28  4551.2  302.22
  4551.7  301.72  4565.5  302.22  4578.4  308.98  4597.6  309.37  4909.6  310.52
  4961.1  312.02  4991.9   313.7  5010.3  308.17  5040.5  313.79  6034.9  312.95
  6810.9  325.47  6920.6  323.43  7009.2  322.38  7207.4  323.49  7406.4  325.23
#Mann= 20 ,-1 , 0
  2734.5     .07       0  2846.2     .12       0  3003.9     .07       0
  3393.6     .05       0  3593.5     .07       0  3948.2     .05       0
  4035.5     .07       0  4134.6     .05       0  4148.1     .07       0
  4332.8     .05       0  4461.8      .1       0  4551.2     .05       0
  4565.5      .1       0  4597.6     .05       0  4909.6     .07       0
  4961.1     .05       0  6810.9     .07       0  6920.6     .05       0
  7009.2    .035       0  7207.4     .05       0
Bank Sta=4551.2,4565.5
XS Rating Curve= 0 ,0
Exp/Cntr=0.3,0.1

Type RM Length L Ch R = 1 ,12469   ,1369,1369,1369
BEGIN DESCRIPTION:
OBAR CREEK 6.0
END DESCRIPTION:
XS GIS Cut Line= 3
      2539689.59     13782288.75      2539858.13     13784311.26
      2540245.78     13786704.55
#Sta/Elev= 30
  2509.9  324.39  2606.5  320.29  2914.6  315.62    3142  312.78  3220.6  310.76
  3548.5  306.88  3855.9  306.06    3911  305.12    3921  303.72  3923.9  299.45
  3924.4  298.95  3938.2  299.45  3951.1  304.75  3991.3  306.87  4151.8  307.11
  4171.9  299.99    4192  306.22  4273.7  307.52  4948.4  311.41  4968.7  311.24
  4999.1  304.47  5019.3  310.87  5060.4  310.26  5130.8   307.3  5161.2  310.89
  5709.8  319.12  5790.4     320  6111.5  315.29  6374.7  318.37  6963.9  330.11
#Mann= 13 ,-1 , 0
  2509.9     .07       0  2914.6     .05       0    3142     .07       0
  3220.6     .05       0  3548.5     .07       0  3855.9      .1       0
  3923.9     .05       0  3938.2      .1       0  4273.7     .05       0
  5060.4     .07       0  5709.8    .035       0  5790.4     .07       0
  6374.7     .05       0
Bank Sta=3923.9,3938.2
XS Rating Curve= 0 ,0
Exp/Cntr=0.3,0.1

Type RM Length L Ch R = 1 ,11100   ,1055,1055,1055
BEGIN DESCRIPTION:
OBAR CREEK 5.0
END DESCRIPTION:
XS GIS Cut Line= 3
      2538543.51     13782878.66      2538880.59     13784395.53
      2539268.07     13786770.96
#Sta/Elev= 30
    3251  326.53  3607.3  315.26  3951.1     313  4111.8  311.86  4353.6  316.57
    4449  314.13  4550.4  310.19  4650.7  301.36  4657.3  296.73  4657.8  296.23
  4672.5  296.73  4681.4  303.27  4691.6  304.69  4720.7  303.27  4824.6  304.13
  4905.7  300.86  4936.1  303.43  5074.3  303.56  5138.7  302.57  5151.7  304.12
  5205.2  303.77  5270.4  304.38  5280.5  302.37  5375.3  305.24  5419.8  301.86
  5473.1  305.53  5737.2  307.58  6063.6  313.15  6786.8  324.01  7211.7  333.97
#Mann= 13 ,-1 , 0
    3251     .07       0  3951.1     .05       0    4449     .12       0
  4550.4      .1       0  4657.3     .05       0  4672.5      .1       0
  4720.7     .07       0  5074.3      .1       0  5151.7     .05       0
  5205.2      .1       0  5375.3     .05       0  6063.6     .07       0
  6786.8     .05       0
Bank Sta=4657.3,4672.5
XS Rating Curve= 0 ,0
Exp/Cntr=0.3,0.1

Type RM Length L Ch R = 1 ,10045   ,957,957,957
BEGIN DESCRIPTION:
OBAR CREEK 4.0
END DESCRIPTION:
XS GIS Cut Line= 3
      2537869.34     13783182.04      2537936.76     13783940.46
      2538206.38     13786670.37
#Sta/Elev= 30
  3249.3  332.82  3533.4  333.59  3646.2  331.59  3764.3  328.35  3820.5  322.78
  3825.5  323.52  3948.8  315.61  4065.5  309.24  4306.7  302.84  4316.7   301.3
  4326.8  298.25  4329.1  296.09  4329.6  295.59  4344.6  296.09  4345.4  298.06
  4350.4  297.92  4356.9  302.08  4437.2  300.31  4552.6  302.51  4698.6  301.03
  4849.3  302.11  4929.7  300.31    4993  301.33  5010.1   300.8  5020.1  298.77
  5030.2  301.27  5351.7  301.81  5623.1  308.41  6074.4  309.49  6753.9   313.7
#Mann= 7 ,-1 , 0
  3249.3     .05       0  3646.2     .07       0  3948.8      .1       0
  4329.1     .05       0  4344.6      .1       0  4437.2     .07       0
    4993     .05       0
Bank Sta=4329.1,4344.6
XS Rating Curve= 0 ,0
Exp/Cntr=0.3,0.1