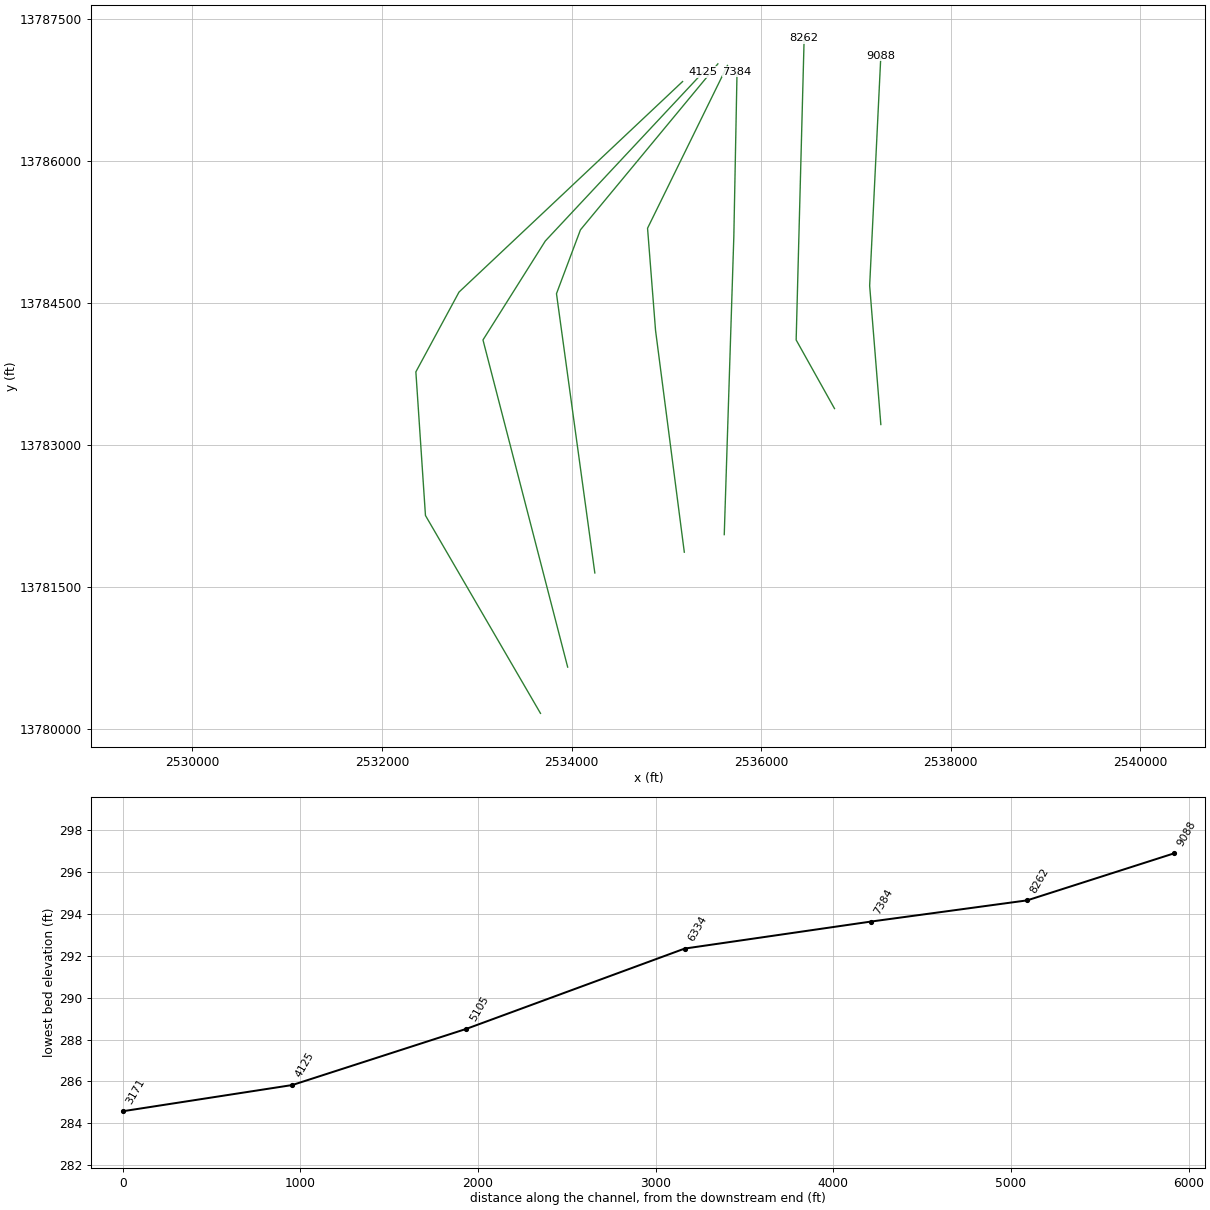
HEC-RAS study OBAR CREEK.prj: OBAR CREEK Base Level Engineering

--- OBAR CREEK.g01 (geometry) --- (continued)

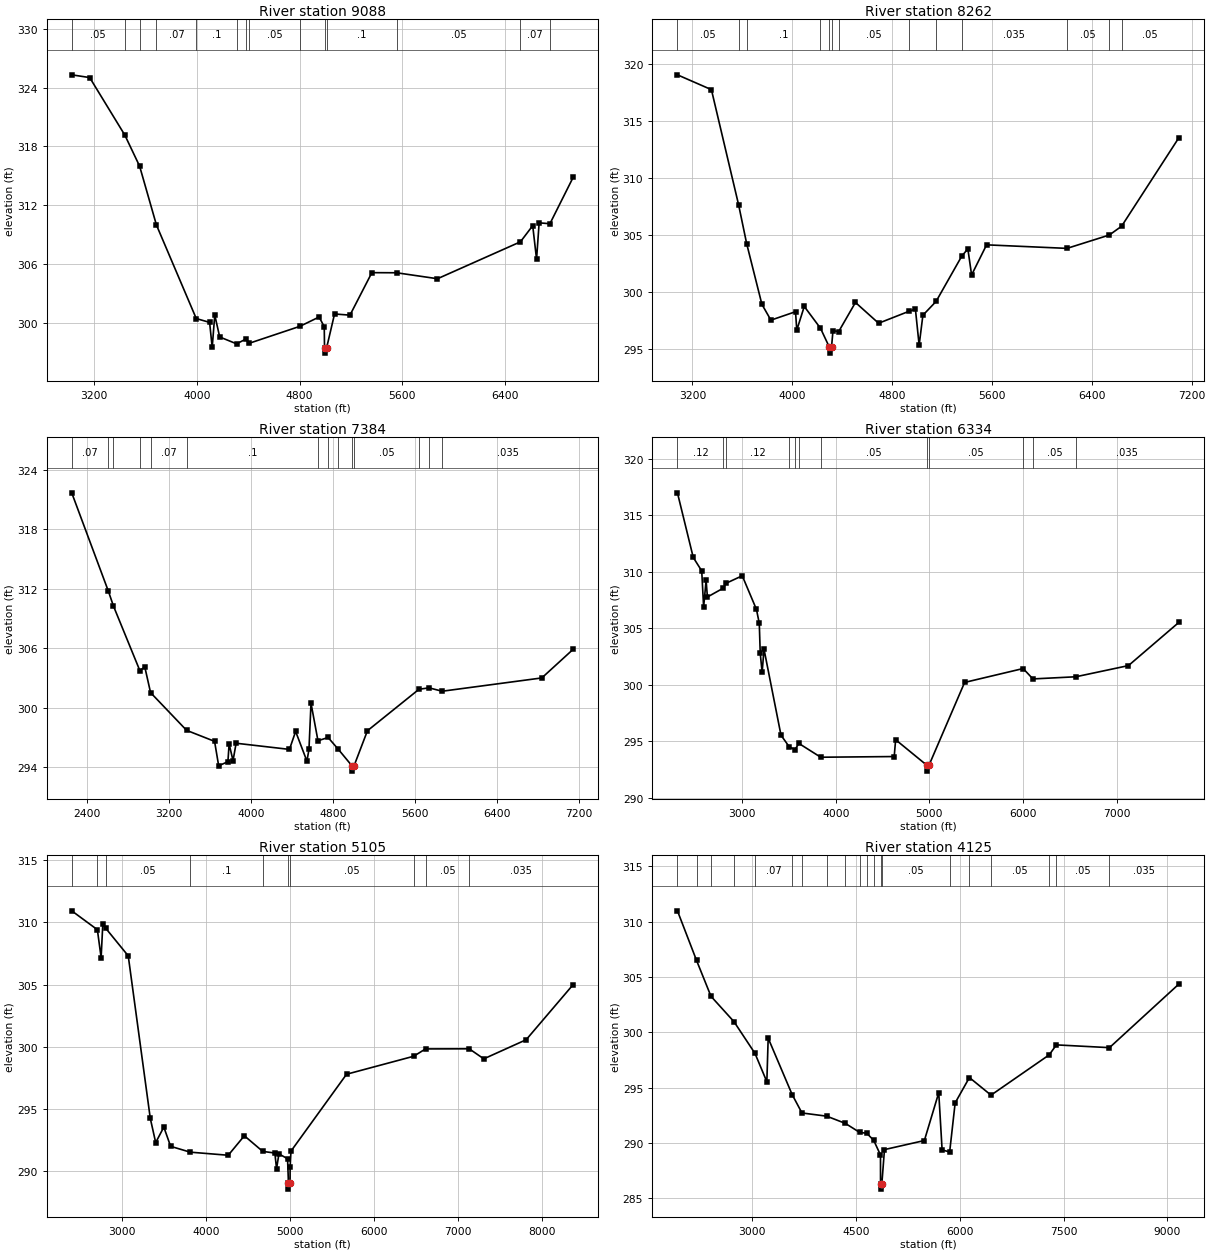
Type RM Length L Ch R = 1 ,9088    ,826,826,826
BEGIN DESCRIPTION:
OBAR CREEK 3.0
END DESCRIPTION:
XS GIS Cut Line= 3
      2537262.59     13783215.76      2537144.61     13784682.05
      2537262.59     13787109.06
#Sta/Elev= 30
  3027.3  325.31    3167  325.03  3440.5  319.15  3555.4  315.98  3686.3  309.97
  3996.2  300.41    4100  300.02  4120.1  297.46  4140.1  300.77  4178.5  298.53
  4309.8  297.83  4381.3  298.31    4409  297.89  4802.9  299.62  4951.8  300.57
  4991.9  299.58  4994.1  297.38  4994.6  296.88  5009.7  297.38    5072  300.88
  5192.1  300.76  5362.3   305.1  5554.5  305.09  5872.9  304.48  6518.2  308.25
  6613.8   309.9  6643.8  306.47  6663.8  310.19  6747.8   310.1  6928.2  314.83
#Mann= 14 ,-1 , 0
  3027.3     .05       0  3440.5     .07       0  3555.4     .12       0
  3686.3     .07       0  3996.2      .1       0  4309.8     .05       0
  4381.3     .07       0    4409     .05       0  4802.9      .1       0
  4994.1     .05       0  5009.7      .1       0  5554.5     .05       0
  6518.2     .07       0  6747.8     .05       0
Bank Sta=4994.1,5009.7
XS Rating Curve= 0 ,0
Exp/Cntr=0.3,0.1

Type RM Length L Ch R = 1 ,8262    ,878,878,878
BEGIN DESCRIPTION:
OBAR CREEK 2.0
END DESCRIPTION:
XS GIS Cut Line= 3
       2536773.8     13783384.31      2536369.32     13784109.01
      2536453.59     13787294.45
#Sta/Elev= 30
  3080.3  319.03  3352.5  317.73  3570.3  307.64    3635  304.23  3756.8  298.92
    3829  297.53  4026.3  298.27  4036.3  296.65  4096.3  298.73  4226.3  296.82
  4298.3  295.14  4298.8  294.64  4314.5  295.14  4326.4  296.61  4372.1  296.53
  4506.4  299.08  4691.9  297.26  4931.5  298.29  4986.6   298.5  5016.6  295.34
  5046.6  297.96  5152.2  299.17  5357.4  303.13  5406.8  303.78  5436.8  301.49
  5556.8  304.13    6201  303.82  6539.8  304.99  6638.3  305.76  7096.8  313.51
#Mann= 13 ,-1 , 0
  3080.3     .05       0  3570.3     .07       0    3635      .1       0
  4226.3     .07       0  4298.3     .05       0  4314.5     .07       0
  4372.1     .05       0  4931.5     .07       0  5152.2     .05       0
  5357.4    .035       0    6201     .05       0  6539.8    .035       0
  6638.3     .05       0
Bank Sta=4298.3,4314.5
XS Rating Curve= 0 ,0
Exp/Cntr=0.3,0.1

Type RM Length L Ch R = 1 ,7384    ,1050,1050,1050
BEGIN DESCRIPTION:
OBAR CREEK 1.0
END DESCRIPTION:
XS GIS Cut Line= 3
      2535610.88     13782052.81      2535712.01     13785204.53
      2535745.71     13786940.26
#Sta/Elev= 30
  2252.3  321.67  2610.6  311.73  2658.5  310.28  2916.4  303.76  2964.9  304.12
    3021  301.54  3372.3  297.74  3645.2  296.63  3685.2  294.17  3775.3  294.58
  3787.1  296.36  3825.3  294.69  3855.3  296.44  4375.6  295.82  4435.6  297.63
  4545.7  294.64  4565.7  295.81  4585.7  300.47  4653.6  296.69  4752.2  297.02
  4850.2  295.85  4987.8  294.13  4988.3  293.63  5004.1  294.13    5136   297.7
    5639  301.88  5737.5  302.02  5864.5  301.68  6836.4  303.02  7141.7   305.9
#Mann= 14 ,-1 , 0
  2252.3     .07       0  2610.6     .12       0  2658.5     .07       0
  2916.4     .12       0    3021     .07       0  3372.3      .1       0
  4653.6     .05       0  4752.2    .035       0  4850.2     .05       0
  4987.8     .05       0  5004.1     .05       0    5639    .035       0
  5737.5     .05       0  5864.5    .035       0
Bank Sta=4987.8,5004.1
XS Rating Curve= 0 ,0
Exp/Cntr=0.3,0.1

Type RM Length L Ch R = 1 ,6334    ,1229,1229,1229
BEGIN DESCRIPTION:
B19842
END DESCRIPTION:
XS GIS Cut Line= 4
      2535189.53      13781867.4      2534886.15     13784210.13
      2534801.88      13785288.8      2535644.59     13787007.92
#Sta/Elev= 30
  2306.7  316.97  2475.7  311.25  2566.4  310.06  2586.6  306.85  2613.1  309.23
  2626.9  307.75    2798  308.54  2825.3  308.96  2999.4  309.63  3151.3  306.65
  3181.5  305.42  3191.6  302.79  3211.8  301.07    3232  303.13  3413.5  295.52
  3502.9  294.48  3563.3  294.25  3604.8  294.79  3838.1  293.57  4623.5  293.63
  4638.8  295.12  4975.3  292.84  4975.8  292.34  4994.4  292.84    5376  300.19
  6001.5  301.42    6106   300.5  6564.4  300.69  7127.3  301.68  7665.5   305.5
#Mann= 12 ,-1 , 0
  2306.7     .12       0    2798     .07       0  2825.3     .12       0
  3502.9      .1       0  3563.3     .12       0  3604.8    .035       0
  3838.1     .05       0  4975.3     .05       0  4994.4     .05       0
  6001.5    .035       0    6106     .05       0  6564.4    .035       0
Bank Sta=4975.3,4994.4
XS Rating Curve= 0 ,0
Exp/Cntr=0.3,0.1

Type RM Length L Ch R = 1 ,5105    ,980,980,980
BEGIN DESCRIPTION:
B19841
END DESCRIPTION:
XS GIS Cut Line= 4
       2534245.7     13781648.26      2533841.19     13784597.78
        2534094.     13785271.95      2535543.44     13787024.75
#Sta/Elev= 30
  2399.5  310.94  2704.8  309.42  2749.5  307.17  2769.7  309.89  2803.7  309.54
  3072.5  307.31  3334.9  294.22  3399.4  292.26  3496.4  293.51  3577.2  291.96
  3810.1  291.49  4263.5  291.24  4455.3  292.81  4674.6  291.55  4818.7  291.42
  4838.9  290.15  4867.2  291.35  4970.1  290.96  4980.7  289.01  4981.2  288.51
  4999.9  289.01  5000.4  290.27  5010.5  291.57  5672.7  297.77  6472.7  299.22
  6613.2  299.81  7133.7  299.82  7307.4  299.01  7811.7  300.55  8371.1  304.99
#Mann= 10 ,-1 , 0
  2399.5     .07       0  2704.8    .035       0  2803.7     .05       0
  3810.1      .1       0  4674.6     .05       0  4980.7     .05       0
  4999.9     .05       0  6472.7    .035       0  6613.2     .05       0
  7133.7    .035       0
Bank Sta=4980.7,4999.9
XS Rating Curve= 0 ,0
Exp/Cntr=0.3,0.1

Type RM Length L Ch R = 1 ,4125    ,954,954,954
BEGIN DESCRIPTION:
B19840
END DESCRIPTION:
XS GIS Cut Line= 4
      2533959.16     13780653.93       2533065.9     13784109.01
      2533723.21     13785153.97      2535390.66     13786939.31
#Sta/Elev= 30
    1918  310.97  2194.2  306.49  2402.8  303.25  2736.1  300.95  3038.9  298.09
  3210.2  295.53  3229.4  299.47    3576  294.37  3717.5  292.71  4075.6  292.42
  4344.4  291.77  4552.8  290.95  4653.7  290.88  4754.6  290.24  4852.5  288.91
  4853.2  286.33  4853.7  285.83  4872.4  286.33  4910.1   289.4  5486.7  290.22
  5694.6  294.54  5743.1  289.37  5852.4  289.19  5931.6  293.62  6137.5  295.91
  6450.1  294.32  7291.2  297.96  7394.5  298.86  8161.9  298.61  9164.1  304.35
#Mann= 20 ,-1 , 0
    1918     .07       0  2194.2    .035       0  2402.8     .07       0
  2736.1    .035       0  3038.9     .07       0    3576    .035       0
  3717.5     .07       0  4075.6     .12       0  4344.4     .07       0
  4552.8     .05       0  4653.7      .1       0  4754.6     .07       0
  4853.2     .05       0  4872.4     .05       0  5852.4    .035       0
  6137.5     .05       0  6450.1     .05       0  7291.2    .035       0
  7394.5     .05       0  8161.9    .035       0
Bank Sta=4853.2,4872.4
XS Rating Curve= 0 ,0
Exp/Cntr=0.3,0.1

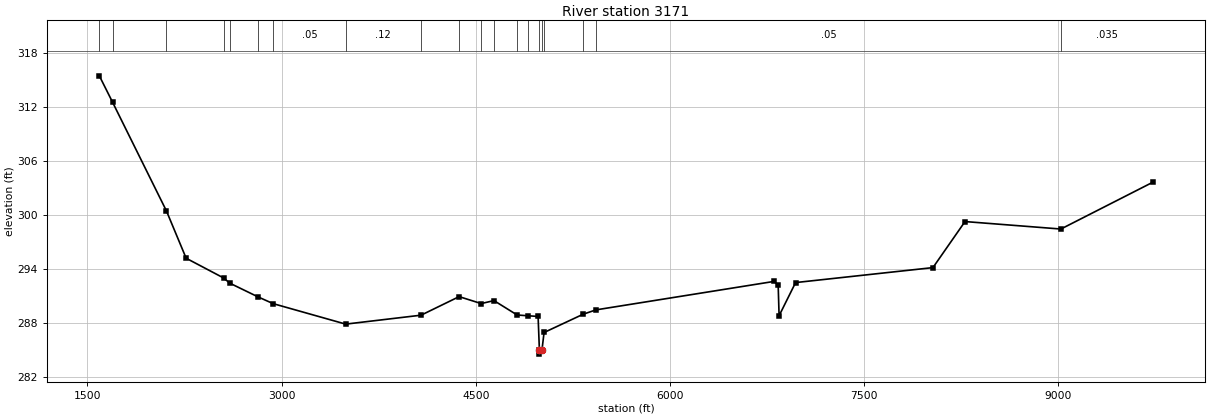
Type RM Length L Ch R = 1 ,3171    ,0,0,0
BEGIN DESCRIPTION:
B19839
END DESCRIPTION:
XS GIS Cut Line= 5
      2533672.63     13780165.17      2532459.15     13782255.05
      2532358.02     13783771.92      2532813.09     13784614.63
      2535171.35     13786838.13
#Sta/Elev= 30
  1592.8  315.46  1694.7  312.54    2111  300.47  2263.3  295.22    2554  293.02
  2599.5  292.46  2817.1  290.94  2935.5  290.18  3495.4  287.91  4077.4   288.9
  4371.6  290.96  4542.1  290.19  4640.6  290.52  4819.9  288.92  4900.9  288.84
  4981.5  288.76  4991.4  285.08  4991.9  284.58  5011.7  285.08  5027.6  286.98
  5329.8  289.01  5428.2  289.49  6800.3  292.64  6835.5   292.3  6842.8  288.84
  6970.2  292.52    8031  294.18  8278.6  299.29  9019.1  298.46  9728.6  303.65
#Mann= 20 ,-1 , 0
  1592.8     .07       0  1694.7     .05       0    2111     .07       0
    2554     .05       0  2599.5     .12       0  2817.1     .05       0
  2935.5     .05       0  3495.4     .12       0  4077.4    .035       0
  4371.6     .12       0  4542.1     .07       0  4640.6    .035       0
  4819.9     .05       0  4900.9     .07       0  4991.4     .05       0
  5011.7     .07       0  5027.6     .05       0  5329.8    .035       0
  5428.2     .05       0  9019.1    .035       0
Bank Sta=4991.4,5011.7
XS Rating Curve= 0 ,0
Exp/Cntr=0.3,0.1

Chan Stop Cuts=-1
Use User Specified Reach Order=0
Composite Channel Slope=5