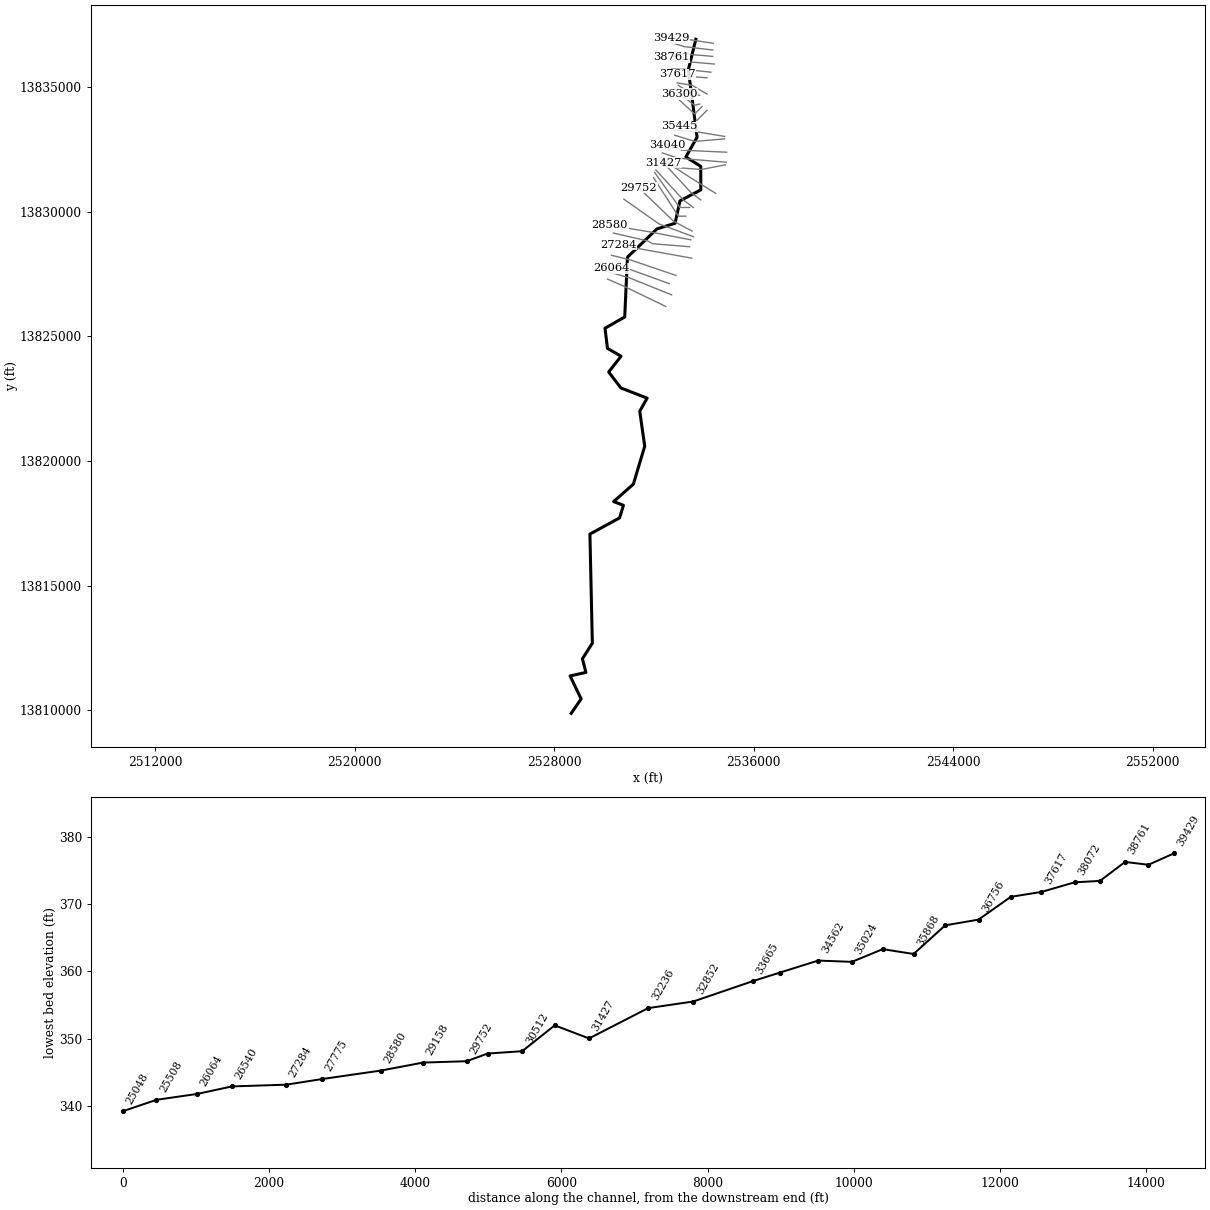
--- Pin Oak Creek 2.prj (project) ---

Proj Title=Pin Oak Creek 2 Base Level Engineering
Current Plan=p01
Default Exp/Contr=0.3,0.1
English Units
Geom File=g01
Flow File=f01
Plan File=p01
Y Axis Title=Elevation
X Axis Title(PF)=Main Channel Distance
X Axis Title(XS)=Station
BEGIN DESCRIPTION:
Pin Oak Creek 2
END DESCRIPTION:
DSS Export Rating Curves= 0
DSS Export Rating Curve Sorted= 0
DSS Export Volume Flow Curves= 0
DXF OffsetX= 0
DXF OffsetY= 0
DXF ScaleX= 1
DXF ScaleY= 10

--- Pin Oak Creek 2.p01 (plan) ---

Plan Title=Multiple Run
Short Identifier=Multiple
Geom File=g01
Flow File=f01
Subcritical Flow
K Sum by GR= 0
Std Step Tol= 0.01
Critical Tol= 0.01
Num of Std Step Trials= 20
Max Error Tol= 0.3
Flow Tol Ratio= 0.001
Split Flow NTrial= 30
Split Flow Tol= 0.02
Split Flow Ratio= 0.02
Log Output Level= 0
Friction Slope Method= 1
Unsteady Friction Slope Method= 2
Unsteady Bridges Friction Slope Method= 1
Parabolic Critical Depth
Global Vel Dist=  1 , 1 , 1
Global Log Level= 0
CheckData=True
Encroach Param= -1, 0, 0, 0
BEGIN DESCRIPTION:
Multiple Run
END DESCRIPTION:

--- Pin Oak Creek 2.f01 (steady flow) ---

Flow Title=Multiple
Number of Profiles=7
Profile Names=10-year,25-year,50-year,1pct_min,100-year,1pct_plu,500-year
River Rch & RM= Pin Oak Creek 2,Reach-1,39429
     596     952    1272     824    1644    3280    2715
River Rch & RM= Pin Oak Creek 2,Reach-1,35024
     964    1555    2087    1354    2702    5390    4481
River Rch & RM= Pin Oak Creek 2,Reach-1,26540
    1243    2036    2762    1809    3610    7203    6108
River Rch & RM= Pin Oak Creek 2,Reach-1,25508
    1614    2645    3588    2347    4682    9343    7898
River Rch & RM= Pin Oak Creek 2,Reach-1,17303
    1860    3063    4168    2732    5451   10877    9238
River Rch & RM= Pin Oak Creek 2,Reach-1,10502
    1966    3236    4401    2883    5752   11476    9732
River Rch & RM= Pin Oak Creek 2,Reach-1,5964
    2000    3285    4462    2918    5822   11615    9817
Boundary for River Rch & Prof#=Pin Oak Creek 2,Reach-1,1
Up Type=0
Dn Type=3
Dn Slope=0.0013
Boundary for River Rch & Prof#=Pin Oak Creek 2,Reach-1,2
Up Type=0
Dn Type=3
Dn Slope=0.0013
Boundary for River Rch & Prof#=Pin Oak Creek 2,Reach-1,3
Up Type=0
Dn Type=3
Dn Slope=0.0013
Boundary for River Rch & Prof#=Pin Oak Creek 2,Reach-1,4
Up Type=0
Dn Type=3
Dn Slope=0.0013
Boundary for River Rch & Prof#=Pin Oak Creek 2,Reach-1,5
Up Type=0
Dn Type=3
Dn Slope=0.0013
Boundary for River Rch & Prof#=Pin Oak Creek 2,Reach-1,6
Up Type=0
Dn Type=3
Dn Slope=0.0013
Boundary for River Rch & Prof#=Pin Oak Creek 2,Reach-1,7
Up Type=0
Dn Type=3
Dn Slope=0.0013

--- Pin Oak Creek 2.g01 (geometry) ---

Geom Title=Existing Conditions
Program Version=4.10

River Reach=Pin Oak Creek 2 ,Reach-1
Reach XY= 30
        2533675.       13836925.      2533374.55      13835699.9
      2533725.11     13832995.09      2533274.79     13832199.91
      2533871.57     13831823.78      2533873.51     13830880.84
      2533038.36      13830438.8       2532841.8     13829541.41
      2532114.94      13829313.9      2530932.69     13828181.47
      2530822.86     13825780.97      2530032.58     13825328.35
      2530130.41     13824522.29      2530675.09     13824205.13
      2530180.05     13823572.74      2530668.48     13822932.67
      2531722.35     13822523.34      2531424.68     13822000.11
      2531624.96     13820595.03      2531169.52     13819072.56
      2530378.47      13818373.5      2530771.87     13818223.39
      2530616.87      13817718.3      2529427.14     13817069.03
      2529524.67     13812690.03      2529125.72     13812064.29
      2529267.31     13811518.52       2528632.6     13811378.35
      2529075.55     13810454.87        2528675.       13809875.

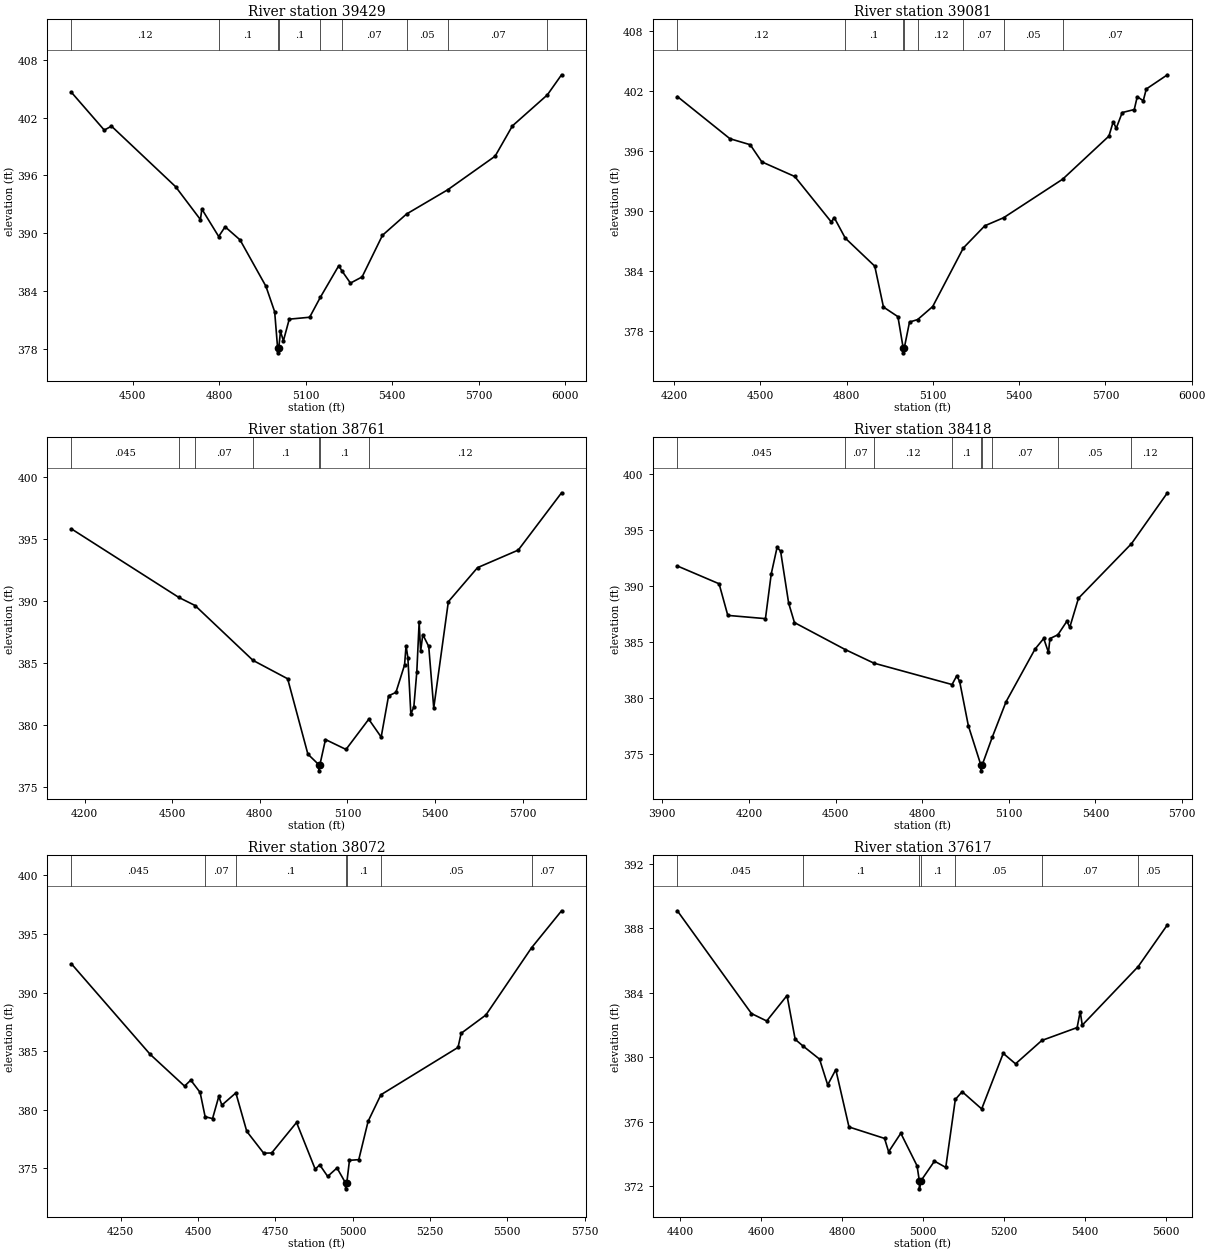
Type RM Length L Ch R = 1 ,39429   ,348,348,348
BEGIN DESCRIPTION:
B20063
END DESCRIPTION:
XS GIS Cut Line= 3
      2534372.21     13836762.88      2533273.22     13836929.55
      2532684.71      13836960.8
#Sta/Elev= 30
  4287.1  404.63  4400.9  400.71  4425.9  401.12  4648.4  394.83  4734.6  391.41
  4739.6   392.5    4798  389.65  4820.3  390.66  4872.1   389.3  4961.9  384.48
  4992.3  381.83  5002.5  378.06  5002.7  377.56  5006.5  378.06  5012.5  379.79
  5022.6  378.81  5042.9  381.06  5113.7  381.26  5150.6  383.32  5214.8  386.62
  5225.2   386.1  5255.3  384.81  5295.7  385.45  5366.5  389.78  5450.1  391.99
    5593  394.51  5757.4     398  5817.5  401.15  5938.7  404.37    5988  406.46
#Mann= 9 ,-1 , 0
  4287.1     .12       0    4798      .1       0  5002.5     .05       0
  5006.5      .1       0  5150.6     .12       0  5225.2     .07       0
  5450.1     .05       0    5593     .07       0  5938.7     .05       0
Bank Sta=5002.5,5006.5
XS Rating Curve= 0 ,0
Exp/Cntr=0.3,0.1

Type RM Length L Ch R = 1 ,39081   ,320,320,320
BEGIN DESCRIPTION:
B20062
END DESCRIPTION:
XS GIS Cut Line= 3
      2534356.57     13836492.05      2533215.93     13836627.47
      2532684.68     13836788.92
#Sta/Elev= 30
  4211.8  401.45  4394.6  397.24  4465.1  396.64  4505.4  394.93  4619.9  393.47
  4747.1  388.93  4757.2  389.37  4795.6  387.32  4898.2  384.52  4928.4  380.44
  4978.7  379.48  4996.9  376.37  4997.1  375.87  5000.9  376.37    5019  378.94
  5047.3  379.19  5099.6  380.49  5206.3  386.34  5280.8  388.55  5345.9  389.35
  5551.5   393.2  5712.3   397.5  5727.2  398.93  5737.7  398.28  5758.6  399.85
  5800.4  400.15  5810.8  401.43  5831.7  401.03  5842.2   402.2  5915.7  403.62
#Mann= 8 ,-1 , 0
  4211.8     .12       0  4795.6      .1       0  4996.9     .05       0
  5000.9      .1       0  5047.3     .12       0  5206.3     .07       0
  5345.9     .05       0  5551.5     .07       0
Bank Sta=4996.9,5000.9
XS Rating Curve= 0 ,0
Exp/Cntr=0.3,0.1

Type RM Length L Ch R = 1 ,38761   ,343,343,343
BEGIN DESCRIPTION:
B20061
END DESCRIPTION:
XS GIS Cut Line= 3
       2534351.4     13836236.84      2533262.81     13836330.59
      2532689.92      13836210.8
#Sta/Elev= 30
    4155  395.84  4522.8   390.3  4578.1  389.65  4776.3  385.22  4895.1  383.73
  4964.4  377.64  5001.6  376.79  5001.8  376.29  5005.6  376.79  5024.6  378.82
  5094.9  378.02  5172.8  380.46  5215.3  379.02  5240.6  382.35  5265.8  382.63
  5295.4  384.85  5300.5   386.4  5306.7  385.44  5316.9  380.88  5327.1  381.45
  5337.3  384.28  5345.3  388.29  5350.4  385.95  5357.8   387.3  5378.2  386.34
  5395.3  381.37  5445.3  389.96  5545.2  392.71  5684.7  394.13  5832.9  398.76
#Mann= 7 ,-1 , 0
    4155    .045       0  4522.8     .12       0  4578.1     .07       0
  4776.3      .1       0  5001.6     .05       0  5005.6      .1       0
  5172.8     .12       0
Bank Sta=5001.6,5005.6
XS Rating Curve= 0 ,0
Exp/Cntr=0.3,0.1

Type RM Length L Ch R = 1 ,38418   ,346,346,346
BEGIN DESCRIPTION:
B20060
END DESCRIPTION:
XS GIS Cut Line= 2
      2534419.02     13835929.55      2532728.18     13836075.22
#Sta/Elev= 30
  3952.1  391.75  4096.7  390.16  4126.8  387.34  4257.2  387.05  4277.3  391.05
  4297.4   393.4  4309.6  393.08  4337.5  388.44  4357.6   386.7  4533.6  384.29
  4632.7  383.08  4903.4  381.17  4919.7  381.95  4929.7  381.45  4959.8   377.5
  5003.4  373.97  5003.7  373.47  5007.4  373.97  5042.9  376.49  5090.3  379.63
  5190.7  384.33  5220.8  385.28  5237.3  384.04  5242.4  385.27  5269.9  385.61
  5301.1  386.82  5311.1  386.28  5341.2  388.87  5524.8  393.74  5649.2  398.28
#Mann= 9 ,-1 , 0
  3952.1    .045       0  4533.6     .07       0  4632.7     .12       0
  4903.4      .1       0  5003.4     .05       0  5007.4      .1       0
  5042.9     .07       0  5269.9     .05       0  5524.8     .12       0
Bank Sta=5003.4,5007.4
XS Rating Curve= 0 ,0
Exp/Cntr=0.3,0.1

Type RM Length L Ch R = 1 ,38072   ,455,455,455
BEGIN DESCRIPTION:
B20059
END DESCRIPTION:
XS GIS Cut Line= 3
      2534278.46     13835601.42      2533200.31     13835721.22
       2532700.3     13835731.63
#Sta/Elev= 30
  4090.6  392.44    4345  384.73  4456.3  382.02  4476.4  382.53  4506.6  381.48
  4522.8  379.41  4546.8  379.25    4567  381.14    4577   380.4  4622.2  381.44
  4657.5  378.16  4712.2   376.3    4738  376.32  4818.5  378.92  4878.9  374.93
  4893.3  375.31  4919.1  374.32  4949.3  375.04  4976.9  373.76  4977.1  373.26
  4980.9  373.76  4989.6  375.69  5019.7  375.75  5049.9  379.02  5091.2  381.28
  5340.7  385.32  5350.7  386.52  5430.7  388.08  5578.3  393.81  5675.5  396.97
#Mann= 7 ,-1 , 0
  4090.6    .045       0  4522.8     .07       0  4622.2      .1       0
  4976.9     .05       0  4980.9      .1       0  5091.2     .05       0
  5578.3     .07       0
Bank Sta=4976.9,4980.9
XS Rating Curve= 0 ,0
Exp/Cntr=0.3,0.1

Type RM Length L Ch R = 1 ,37617   ,420,420,420
BEGIN DESCRIPTION:
Pin Oak Creek 2 61.0
END DESCRIPTION:
XS GIS Cut Line= 3
      2534124.98       13835375.        2533525.       13835425.
      2532925.04     13835524.99
#Sta/Elev= 30
  4392.7  389.09  4575.8  382.71  4613.4  382.25  4663.6  383.83  4683.7  381.11
  4701.9  380.72  4743.9  379.88    4764  378.28    4784  379.23  4816.6  375.67
  4904.4  374.96  4914.5  374.13  4944.6  375.28  4984.7  373.26  4990.3  372.33
  4990.5  371.83  4994.3  372.33  5027.7  373.55  5055.6  373.16  5079.2  377.38
  5096.1  377.86  5144.3  376.79  5197.5  380.24  5227.9  379.59  5292.8  381.04
    5380  381.84  5387.6  382.83  5392.7  381.99  5530.9  385.63    5603  388.22
#Mann= 7 ,-1 , 0
  4392.7    .045       0  4701.9      .1       0  4990.3     .05       0
  4994.3      .1       0  5079.2     .05       0  5292.8     .07       0
  5530.9     .05       0
Bank Sta=4990.3,4994.3
XS Rating Curve= 0 ,0
Exp/Cntr=0.3,0.1

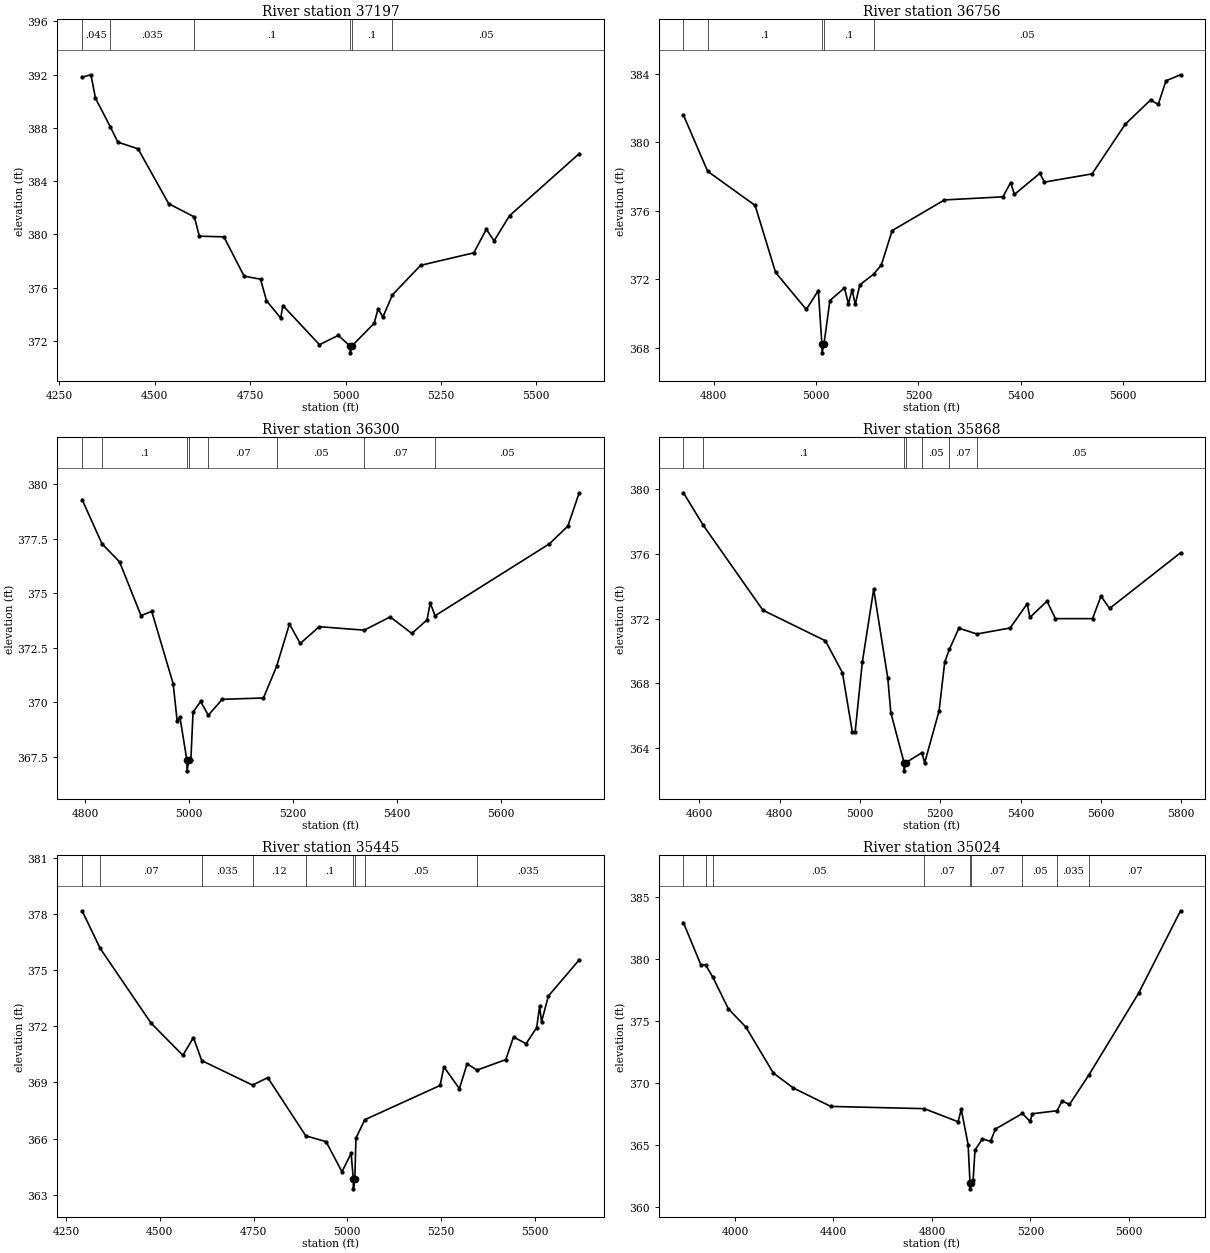
Type RM Length L Ch R = 1 ,37197   ,441,441,441
BEGIN DESCRIPTION:
Pin Oak Creek 2 60.0
END DESCRIPTION:
XS GIS Cut Line= 3
      2534124.97     13834725.02        2533525.       13835075.
      2532924.96     13835175.01
#Sta/Elev= 30
  4309.6   391.8  4332.7  391.98  4344.7  390.22  4383.3  388.09  4403.4  386.92
  4456.3  386.42  4536.6   382.3    4604   381.3  4616.8  379.86  4681.3  379.81
  4734.2  376.86  4777.2  376.63  4792.9  375.02  4830.1  373.71  4835.9  374.65
  4931.8  371.71    4981  372.41  5012.3   371.6  5012.6   371.1  5016.3   371.6
  5075.1  373.32  5085.3   374.4    5098  373.79  5122.9  375.45  5196.8  377.67
  5336.2  378.61  5369.1  380.38  5389.4  379.51    5430   381.4  5612.5  386.06
#Mann= 6 ,-1 , 0
  4309.6    .045       0  4383.3    .035       0    4604      .1       0
  5012.3     .05       0  5016.3      .1       0  5122.9     .05       0
Bank Sta=5012.3,5016.3
XS Rating Curve= 0 ,0
Exp/Cntr=0.3,0.1

Type RM Length L Ch R = 1 ,36756   ,456,456,456
BEGIN DESCRIPTION:
Pin Oak Creek 2 59.0
END DESCRIPTION:
XS GIS Cut Line= 3
      2533825.01       13834675.        2533575.       13834675.
      2532975.01     13835074.99
#Sta/Elev= 30
    4741  381.58  4788.3   378.3    4881  376.31    4921   372.4    4981  370.24
  5004.5  371.34  5011.5  368.21  5011.8  367.71  5015.5  368.21  5027.1  370.76
  5055.6   371.5  5063.1  370.58  5070.6  371.38  5076.6  370.54  5085.7  371.68
    5113  372.31  5127.7  372.84  5148.7  374.84  5250.9  376.63  5365.1  376.81
  5380.1  377.64  5387.6  376.95  5437.2  378.18  5446.2  377.67  5539.3  378.15
  5603.9  381.04  5653.5  382.46  5668.5   382.2  5683.6  383.58  5712.1  383.93
#Mann= 5 ,-1 , 0
    4741     .12       0  4788.3      .1       0  5011.5     .05       0
  5015.5      .1       0    5113     .05       0
Bank Sta=5011.5,5015.5
XS Rating Curve= 0 ,0
Exp/Cntr=0.3,0.1

Type RM Length L Ch R = 1 ,36300   ,432,432,432
BEGIN DESCRIPTION:
Pin Oak Creek 2 58.0
END DESCRIPTION:
XS GIS Cut Line= 3
      2533824.95     13834324.99        2533625.       13834275.
      2533025.01       13834725.
#Sta/Elev= 30
    4794   379.3  4832.3  377.27  4866.1  376.44  4907.3  373.98    4928  374.17
  4969.2  370.85  4976.9  369.13  4982.1  369.33  4995.5  367.36  4995.8  366.86
  4999.5  367.36  5003.2  367.36  5007.4  369.55    5022  370.04  5036.7  369.41
  5063.6  370.14  5142.8   370.2  5168.1  371.65  5192.8  373.59  5213.6   372.7
  5250.1  373.47  5336.7  373.31  5386.6  373.92  5428.2  373.16  5457.4  373.78
  5463.6  374.56  5472.8  373.97  5692.8  377.27  5728.2  378.08  5750.1  379.61
#Mann= 8 ,-1 , 0
    4794     .12       0  4832.3      .1       0  4995.5     .05       0
  4999.5      .1       0  5036.7     .07       0  5168.1     .05       0
  5336.7     .07       0  5472.8     .05       0
Bank Sta=4995.5,4999.5
XS Rating Curve= 0 ,0
Exp/Cntr=0.3,0.1

Type RM Length L Ch R = 1 ,35868   ,423,423,423
BEGIN DESCRIPTION:
Pin Oak Creek 2 57.0
END DESCRIPTION:
XS GIS Cut Line= 3
        2533925.       13834225.        2533625.       13833925.
      2533025.01     13834474.99
#Sta/Elev= 30
  4560.2  379.79  4609.9  377.77  4758.2  372.53  4913.8  370.64  4956.2  368.67
  4980.9     365  4987.9     365  5005.7  369.31  5034.1  373.83  5069.3  368.31
  5076.7   366.2  5109.8   363.1    5110   362.6  5113.8   363.1    5154  363.72
  5161.1   363.1  5196.9   366.3  5211.1  369.34  5222.7  370.11  5246.2  371.42
  5291.1  371.06  5373.9  371.43  5416.4  372.93  5423.2  372.08  5465.7  373.09
  5486.7  372.01  5579.2  372.01  5600.2   373.4  5621.7  372.64  5798.4  376.08
#Mann= 7 ,-1 , 0
  4560.2    .035       0  4609.9      .1       0  5109.8     .05       0
  5113.8      .1       0    5154     .05       0  5222.7     .07       0
  5291.1     .05       0
Bank Sta=5109.8,5113.8
XS Rating Curve= 0 ,0
Exp/Cntr=0.3,0.1

Type RM Length L Ch R = 1 ,35445   ,421,421,421
BEGIN DESCRIPTION:
Pin Oak Creek 2 56.0
END DESCRIPTION:
XS GIS Cut Line= 3
      2534125.03     13834075.03        2533625.       13833575.
      2533025.02       13833425.
#Sta/Elev= 30
  4292.7  378.17  4340.7  376.17  4476.6  372.17  4561.4  370.45  4589.7   371.4
  4611.7  370.17  4747.2  368.86  4787.7  369.26  4889.2  366.15  4943.3  365.84
  4985.7  364.23  5010.2  365.22  5015.9  363.82  5016.1  363.32  5019.9  363.82
    5023  366.03  5046.4  367.01  5247.2  368.84  5257.5  369.83  5298.8  368.67
  5319.4     370  5345.6  369.66  5422.5  370.22  5443.1  371.43  5476.6  371.07
  5504.9  371.93  5512.7  373.07  5517.8  372.24  5535.9  373.61  5618.3  375.55
#Mann= 9 ,-1 , 0
  4292.7      .1       0  4340.7     .07       0  4611.7    .035       0
  4747.2     .12       0  4889.2      .1       0  5015.9     .05       0
  5019.9      .1       0  5046.4     .05       0  5345.6    .035       0
Bank Sta=5015.9,5019.9
XS Rating Curve= 0 ,0
Exp/Cntr=0.3,0.1

Type RM Length L Ch R = 1 ,35024   ,462,462,462
BEGIN DESCRIPTION:
Pin Oak Creek 2 55.0
END DESCRIPTION:
XS GIS Cut Line= 3
      2534824.97     13833025.01        2533625.       13833225.
      2532824.98       13833275.
#Sta/Elev= 30
  3791.1  382.94    3862  379.53  3880.8  379.54  3910.4  378.54  3973.6  375.97
  4044.5  374.51    4156  370.79  4237.1  369.58  4389.2  368.09  4768.6  367.91
  4906.2  366.85  4918.9  367.86  4946.8     365  4954.4  361.93  4954.8  361.43
  4959.5  361.93  4967.1  362.11  4974.7  364.56  5005.1  365.47  5037.7  365.27
  5057.7  366.26  5167.2  367.52    5198  366.88    5208   367.5  5307.8  367.74
  5328.2  368.52  5358.3  368.25  5436.4  370.61  5638.9  377.24  5809.2   383.9
#Mann= 9 ,-1 , 0
  3791.1     .05       0  3880.8     .07       0  3910.4     .05       0
  4768.6     .07       0  4954.4     .05       0  4959.5     .07       0
  5167.2     .05       0  5307.8    .035       0  5436.4     .07       0
Bank Sta=4954.4,4959.5
XS Rating Curve= 0 ,0
Exp/Cntr=0.3,0.1

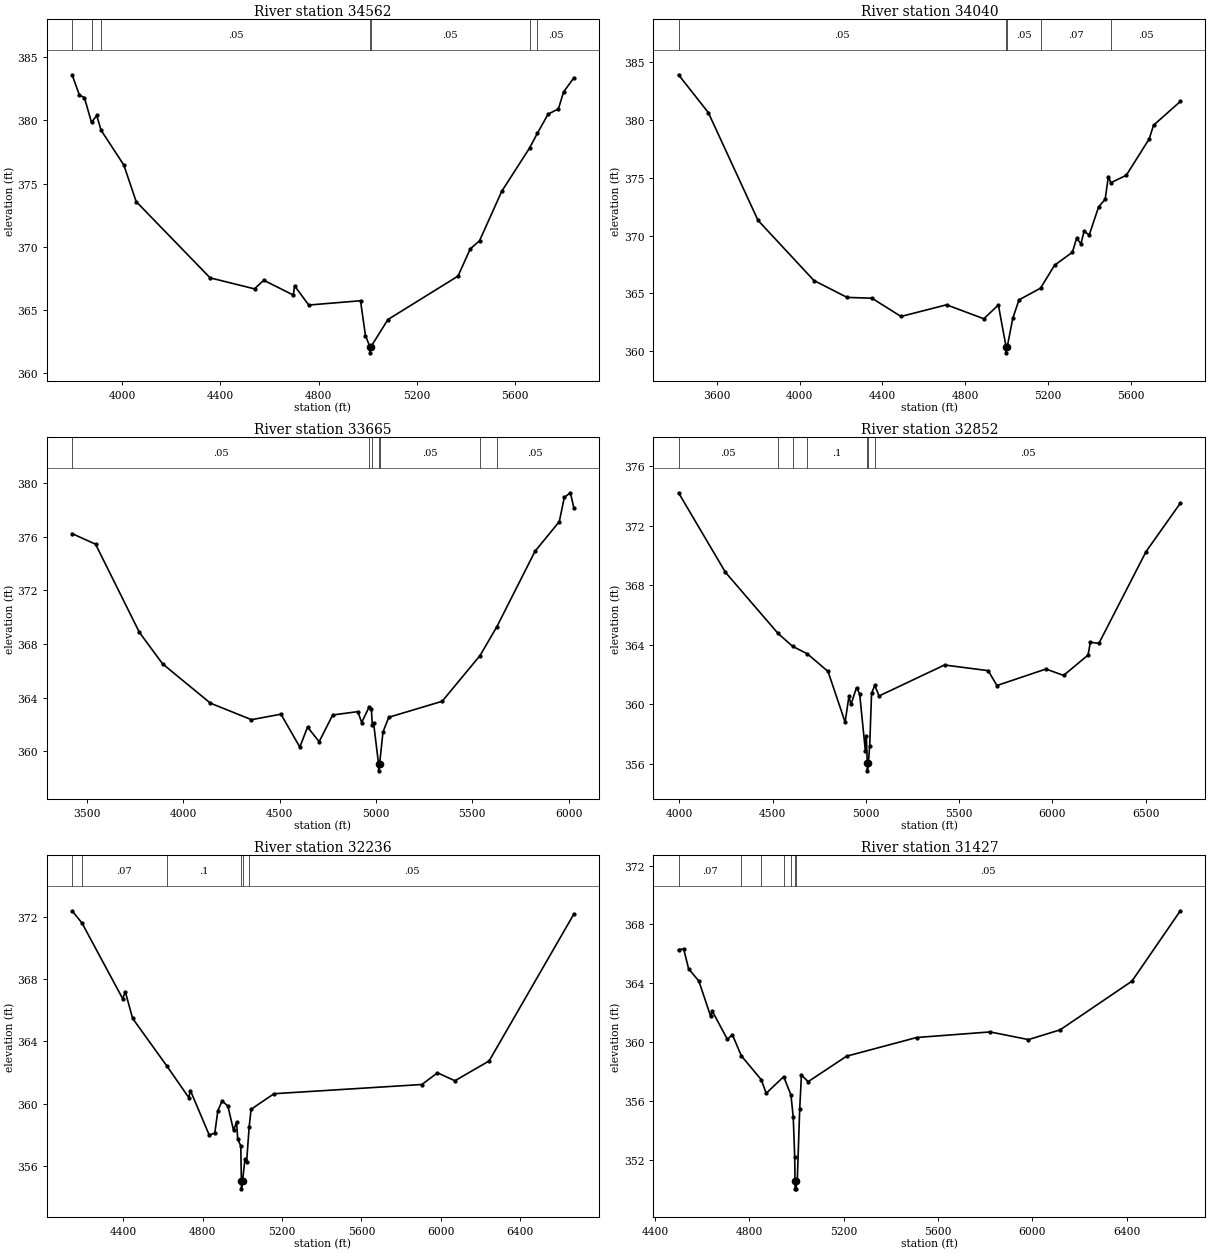
Type RM Length L Ch R = 1 ,34562   ,522,522,522
BEGIN DESCRIPTION:
Pin Oak Creek 2 54.0
END DESCRIPTION:
XS GIS Cut Line= 3
      2534824.95       13832925.        2533625.       13832825.
      2532824.97     13833075.01
#Sta/Elev= 30
  3796.6  383.61  3826.7     382  3846.7  381.81  3875.7  379.84  3896.9  380.39
  3914.9  379.22  4007.3  376.47  4057.5  373.58  4358.5  367.55  4539.1  366.68
  4576.7  367.36  4697.2  366.19  4702.2  366.92  4759.9   365.4  4970.6  365.74
  4990.7  362.98  5008.6  362.12    5009  361.62  5013.7  362.12  5081.9  364.25
  5367.4  367.69  5417.2  369.84  5454.9  370.48  5545.5   374.4  5658.4  377.81
  5690.6  378.99  5734.1   380.5    5776  380.91    5797  382.25  5838.9  383.37
#Mann= 7 ,-1 , 0
  3796.6     .05       0  3875.7     .07       0  3914.9     .05       0
  5008.6     .05       0  5013.7     .05       0  5658.4     .07       0
  5690.6     .05       0
Bank Sta=5008.6,5013.7
XS Rating Curve= 0 ,0
Exp/Cntr=0.3,0.1

Type RM Length L Ch R = 1 ,34040   ,375,375,375
BEGIN DESCRIPTION:
B20058
END DESCRIPTION:
XS GIS Cut Line= 3
      2534908.67     13832391.01      2533116.97     13832474.34
      2532523.24     13832687.88
#Sta/Elev= 30
    3415  383.92  3558.8  380.65  3799.1  371.31  4069.4   366.1  4229.6  364.64
  4349.7  364.57  4489.8  362.99  4710.1     364  4890.3  362.79  4960.3  363.99
  4997.8  360.34  4998.2  359.84    5003  360.34  5030.4  362.86  5060.4  364.43
    5164  365.44    5232  367.43  5318.2  368.55  5338.2  369.75  5359.5  369.29
  5374.3  370.35  5399.7  370.06  5444.5  372.47  5476.4  373.14  5491.8   375.1
    5504  374.57  5578.7  375.22    5689  378.36  5710.2  379.55  5839.6  381.61
#Mann= 5 ,-1 , 0
    3415     .05       0  4997.8     .05       0    5003     .05       0
    5164     .07       0    5504     .05       0
Bank Sta=4997.8,5003
XS Rating Curve= 0 ,0
Exp/Cntr=0.3,0.1

Type RM Length L Ch R = 1 ,33665   ,813,813,813
BEGIN DESCRIPTION:
B20057
END DESCRIPTION:
XS GIS Cut Line= 3
      2534892.97     13831989.97      2532960.72     13832151.42
       2532330.5     13832364.97
#Sta/Elev= 30
    3423  376.22  3544.9  375.43  3772.2  368.87  3892.6  366.52  4141.2  363.59
  4354.2  362.36    4507  362.77  4605.1  360.32  4645.2  361.81  4705.4  360.72
  4775.7  362.71  4906.1  362.96  4926.2  362.15  4965.2  363.32  4976.4  363.19
  4981.1  361.97    4988   362.1  5013.9  359.05  5014.3  358.55  5019.1  359.05
  5036.6  361.44  5066.7  362.54  5343.8  363.73  5540.6  367.14  5627.6  369.28
  5826.1  374.91  5951.8  377.11  5977.9  378.92  6009.4  379.26  6027.4  378.14
#Mann= 7 ,-1 , 0
    3423     .05       0  4965.2     .12       0  4981.1     .05       0
  5013.9     .05       0  5019.1     .05       0  5540.6     .07       0
  5627.6     .05       0
Bank Sta=5013.9,5019.1
XS Rating Curve= 0 ,0
Exp/Cntr=0.3,0.1

Type RM Length L Ch R = 1 ,32852   ,616,616,616
BEGIN DESCRIPTION:
B20056
END DESCRIPTION:
XS GIS Cut Line= 4
      2534861.77      13831885.8      2533898.22      13831698.3
       2532945.1     13831771.22      2532304.45     13832167.06
#Sta/Elev= 30
  3995.1  374.21  4246.5  368.87  4528.7  364.76  4606.2   363.9  4685.6  363.39
  4796.6  362.21  4888.3   358.8  4908.7  360.53  4919.7  359.99  4949.4  361.12
  4966.3   360.7    4997  356.85    5002  357.88  5007.2  356.03  5007.6  355.53
  5012.9  356.03  5020.1  357.19  5030.1  360.75  5047.6  361.27  5070.2  360.56
  5421.2  362.64  5655.7  362.26  5702.1  361.26  5965.2  362.37  6059.8  361.94
  6191.1  363.31  6203.1  364.17    6249  364.09    6502  370.26  6685.7  373.51
#Mann= 7 ,-1 , 0
  3995.1     .05       0  4528.7     .07       0  4606.2     .05       0
  4685.6      .1       0  5007.2     .05       0  5012.9      .1       0
  5047.6     .05       0
Bank Sta=5007.2,5012.9
XS Rating Curve= 0 ,0
Exp/Cntr=0.3,0.1

Type RM Length L Ch R = 1 ,32236   ,809,809,809
BEGIN DESCRIPTION:
B20055
END DESCRIPTION:
XS GIS Cut Line= 3
      2534471.15     13830739.96      2533502.39     13831344.13
      2532335.69     13832094.15
#Sta/Elev= 30
  4141.8  372.38    4192  371.59  4396.5  366.75  4410.3  367.18  4446.9  365.48
  4619.3  362.43  4730.1   360.4  4738.3  360.85  4832.6  358.01    4861  358.12
  4876.4  359.56  4897.6  360.19  4926.9  359.86  4955.4  358.31  4970.7  358.82
  4976.6  357.74    4992   357.3    4995  355.05  4995.5  354.55  5000.8  355.05
  5013.2  356.46  5021.2  356.25  5034.4  358.54  5043.9  359.65  5159.5  360.65
  5904.6  361.24  5983.2  361.99    6071  361.48  6243.4  362.75  6670.5  372.17
#Mann= 6 ,-1 , 0
  4141.8     .05       0    4192     .07       0  4619.3      .1       0
    4995     .05       0  5000.8      .1       0  5034.4     .05       0
Bank Sta=4995,5000.8
XS Rating Curve= 0 ,0
Exp/Cntr=0.3,0.1

Type RM Length L Ch R = 1 ,31427   ,470,470,470
BEGIN DESCRIPTION:
Pin Oak Creek 2 50.0
END DESCRIPTION:
XS GIS Cut Line= 3
      2533874.97     13830475.02        2533475.       13830775.
      2532374.97     13831975.04
#Sta/Elev= 30
    4500  366.29  4521.8  366.34  4542.7  364.99  4586.4  364.15  4636.4  361.75
  4642.7  362.13  4707.3  360.19  4728.1  360.52  4766.2  359.08  4850.9  357.45
  4871.8  356.53  4945.8  357.66  4976.7  356.42  4986.4  354.91  4992.7  352.19
  4993.9  350.54  4994.4  350.04  4999.3  350.04  4999.7  350.54  5003.4  350.54
  5013.8  355.45  5021.2  357.77  5049.6  357.32  5212.4  359.05  5509.6  360.32
    5821   360.7  5983.8  360.18  6118.2  360.84  6422.8  364.15  6627.9  368.93
#Mann= 7 ,-1 , 0
    4500     .07       0  4766.2     .12       0  4850.9      .1       0
  4945.8     .12       0  4976.7     .05       0  4993.9     .05       0
  4999.7     .05       0
Bank Sta=4993.9,4999.7
XS Rating Curve= 0 ,0
Exp/Cntr=0.3,0.1

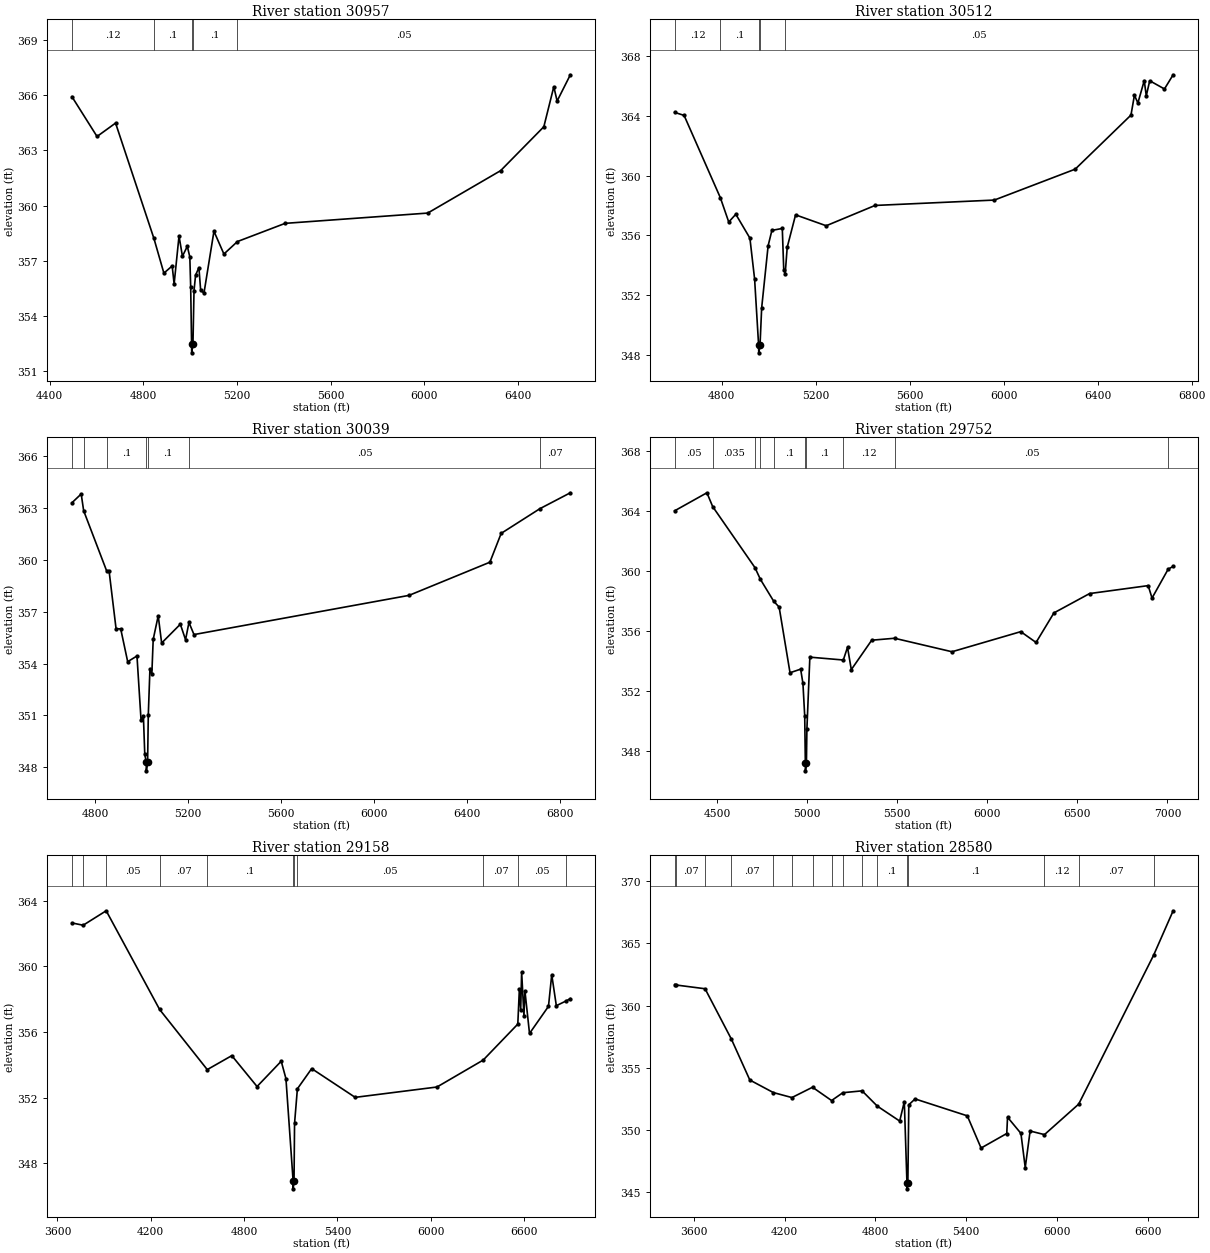
Type RM Length L Ch R = 1 ,30957   ,445,445,445
BEGIN DESCRIPTION:
Pin Oak Creek 2 49.0
END DESCRIPTION:
XS GIS Cut Line= 3
      2533574.99     13830175.01        2533175.       13830475.
      2532074.98     13831675.03
#Sta/Elev= 30
  4495.5  365.93  4602.8  363.76  4681.9  364.49  4845.6  358.21  4888.2  356.32
  4923.6  356.71  4931.9  355.73  4952.8  358.34  4967.4  357.24  4988.2  357.78
  4998.9   357.2  5002.6  355.56  5006.4  352.48  5006.9  351.98  5012.3  352.48
  5016.8  355.36  5023.5  356.21  5037.7  356.62  5045.1   355.4  5059.3  355.23
  5101.9   358.6  5144.4  357.36  5202.2  358.04  5405.8  359.03  6014.5  359.59
  6325.8   361.9  6510.2  364.29  6552.8  366.47  6566.9  365.69  6623.4  367.12
#Mann= 5 ,-1 , 0
  4495.5     .12       0  4845.6      .1       0  5006.4     .05       0
  5012.3      .1       0  5202.2     .05       0
Bank Sta=5006.4,5012.3
XS Rating Curve= 0 ,0
Exp/Cntr=0.3,0.1

Type RM Length L Ch R = 1 ,30512   ,473,473,473
BEGIN DESCRIPTION:
Pin Oak Creek 2 48.0
END DESCRIPTION:
XS GIS Cut Line= 3
      2533425.02       13830175.        2533025.       13830175.
      2532024.99     13831575.02
#Sta/Elev= 30
  4600.7  364.24  4640.7  364.04  4794.9  358.53  4830.7   356.9  4860.7  357.42
  4920.7  355.82  4940.7  353.08  4957.8  348.64  4958.3  348.14  4963.7  348.64
  4970.7  351.15  4998.2  355.31  5014.2  356.34  5058.5  356.47  5064.6  353.71
  5070.8  353.44  5079.4  355.21    5115  357.38  5245.3  356.65    5453  358.01
  5960.5  358.37  6304.6  360.44  6541.8  364.06  6556.5  365.39  6571.3  364.87
  6598.3  366.37  6606.9  365.35  6621.6  366.36  6684.3  365.81  6721.2  366.76
#Mann= 5 ,-1 , 0
  4600.7     .12       0  4794.9      .1       0  4957.8     .05       0
  4963.7      .1       0  5070.8     .05       0
Bank Sta=4957.8,4963.7
XS Rating Curve= 0 ,0
Exp/Cntr=0.3,0.1

Type RM Length L Ch R = 1 ,30039   ,287,287,287
BEGIN DESCRIPTION:
Pin Oak Creek 2 47.0
END DESCRIPTION:
XS GIS Cut Line= 3
      2533274.98       13829825.        2532975.       13829825.
      2531974.98     13831375.03
#Sta/Elev= 30
  4700.5  363.31  4740.5  363.82  4751.1  362.85  4849.6  359.38  4860.5  359.36
  4890.5  356.02  4910.5  356.01  4940.5  354.11  4980.5  354.44    4998  350.73
  5008.1  350.97    5014  348.76  5020.3  348.29  5020.8  347.79  5026.2  348.29
  5029.2  351.03  5036.2  353.67  5044.4  353.39  5050.3   355.4  5071.9  356.77
  5086.6  355.19  5167.1  356.28  5189.5  355.38  5204.1  356.38  5225.8  355.68
  6151.1  357.95  6498.9  359.87  6547.5  361.54  6714.2  362.97  6845.1  363.89
#Mann= 7 ,-1 , 0
  4700.5     .07       0  4751.1    .035       0  4849.6      .1       0
  5020.3     .05       0  5026.2      .1       0  5204.1     .05       0
  6714.2     .07       0
Bank Sta=5020.3,5026.2
XS Rating Curve= 0 ,0
Exp/Cntr=0.3,0.1

Type RM Length L Ch R = 1 ,29752   ,594,594,594
BEGIN DESCRIPTION:
B20054
END DESCRIPTION:
XS GIS Cut Line= 3
      2533523.18     13829229.57      2532783.64     13829620.17
      2531393.03      13830958.7
#Sta/Elev= 30
  4265.2  363.99  4444.1  365.19    4476  364.27  4710.7   360.2  4740.8  359.42
  4815.2  357.95  4844.9  357.57  4905.3  353.19  4964.3  353.43    4977  352.48
  4986.9   350.3  4990.4  347.15  4990.9  346.65  4996.3  347.15    4999  349.43
  5015.4  354.23  5201.1  354.04  5224.4  354.89  5245.5   353.4  5358.7  355.36
  5485.5  355.49  5804.2  354.59    6186  355.93  6270.9  355.21    6370  357.18
  6568.1  358.47  6893.2     359  6914.6  358.17  7004.3   360.1  7031.7  360.28
#Mann= 10 ,-1 , 0
  4265.2     .05       0    4476    .035       0  4710.7     .07       0
  4740.8    .035       0  4815.2      .1       0  4990.4     .05       0
  4996.3      .1       0  5201.1     .12       0  5485.5     .05       0
  7004.3    .035       0
Bank Sta=4990.4,4996.3
XS Rating Curve= 0 ,0
Exp/Cntr=0.3,0.1

Type RM Length L Ch R = 1 ,29158   ,578,578,578
BEGIN DESCRIPTION:
B20053
END DESCRIPTION:
XS GIS Cut Line= 3
      2533580.54     13829000.37       2532195.1     13829516.01
       2530784.2      13830510.4
#Sta/Elev= 30
  3692.9  362.64  3765.2   362.5  3913.4  363.38  4256.8  357.37  4563.1  353.71
  4720.9  354.56  4883.2  352.68  5038.6  354.22  5068.9  353.16  5114.9  346.95
  5115.4  346.45  5120.9  346.95  5124.3  350.44  5142.5  352.54  5234.4  353.77
    5514  352.02  6039.9  352.65    6337  354.29  6559.5  356.48  6569.5  358.59
  6578.1  357.35  6584.2  359.65    6599  356.98  6605.2  358.51  6634.8  355.91
  6756.7  357.56  6777.6  359.49  6807.2   357.6  6872.2   357.9  6897.3  358.03
#Mann= 11 ,-1 , 0
  3692.9     .05       0  3765.2     .07       0  3913.4     .05       0
  4256.8     .07       0  4563.1      .1       0  5114.9     .05       0
  5120.9      .1       0  5142.5     .05       0    6337     .07       0
  6559.5     .05       0  6872.2     .07       0
Bank Sta=5114.9,5120.9
XS Rating Curve= 0 ,0
Exp/Cntr=0.3,0.1

Type RM Length L Ch R = 1 ,28580   ,805,805,805
BEGIN DESCRIPTION:
B20052
END DESCRIPTION:
XS GIS Cut Line= 3
      2533476.35     13828875.38      2531778.43     13829203.51
      2530231.58     13829458.71
#Sta/Elev= 30
    3472  361.69  3481.8  361.65  3672.9  361.35    3847   357.3    3969  354.01
  4124.8     353  4247.5   352.6  4383.7  353.43  4509.8  352.36  4584.3  352.99
  4711.6  353.14  4812.4  351.91  4960.4  350.71  4990.9  352.27  5008.3  345.76
  5008.8  345.26  5014.3  345.76  5020.6  352.02  5062.2  352.49  5407.5  351.13
  5498.7  348.54  5668.6  349.71  5673.7  351.02  5762.2  349.72  5790.8  346.97
  5823.1  349.91    5918  349.62  6144.2  352.07  6639.7  364.04  6769.1  367.62
#Mann= 16 ,-1 , 0
    3472     .05       0  3481.8     .07       0  3672.9     .05       0
    3847     .07       0  4124.8    .035       0  4247.5     .07       0
  4383.7    .035       0  4509.8     .12       0  4584.3      .1       0
  4711.6     .12       0  4812.4      .1       0  5008.3     .05       0
  5014.3      .1       0    5918     .12       0  6144.2     .07       0
  6639.7     .05       0
Bank Sta=5008.3,5014.3
XS Rating Curve= 0 ,0
Exp/Cntr=0.3,0.1

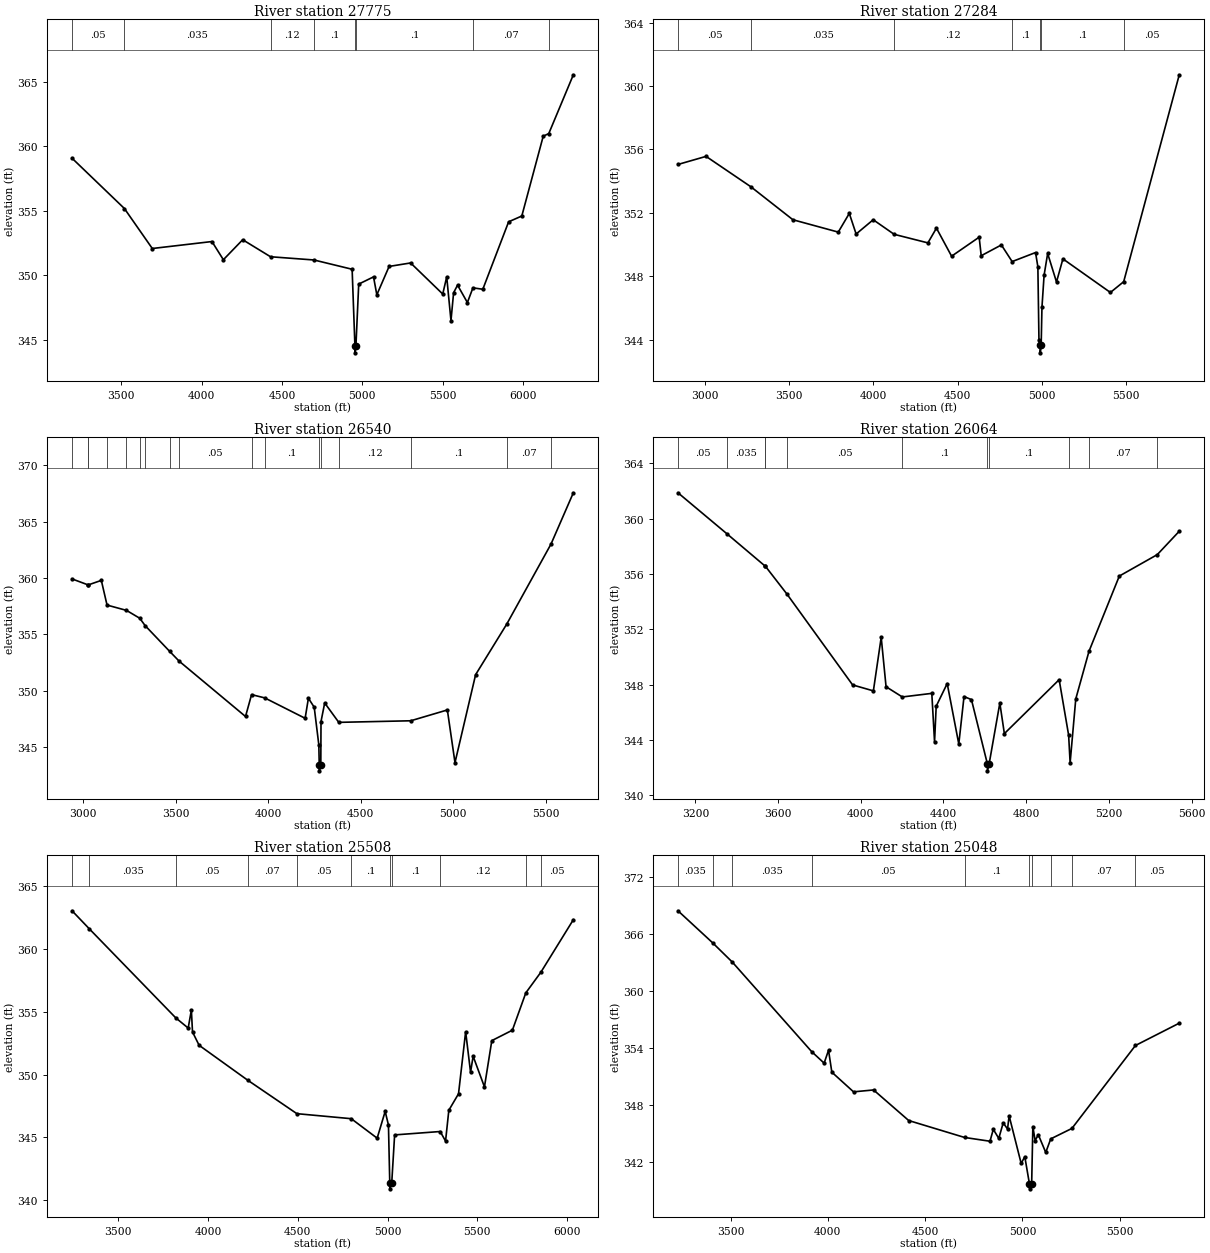
Type RM Length L Ch R = 1 ,27775   ,491,491,491
BEGIN DESCRIPTION:
Pin Oak Creek 2 44.0
END DESCRIPTION:
XS GIS Cut Line= 4
      2533424.22     13828599.34       2531945.1     13828719.13
      2531736.76     13828833.72      2530372.21     13829146.21
#Sta/Elev= 30
  3193.1  359.09  3519.1  355.19  3692.8  352.09  4064.3  352.63  4135.4  351.22
  4255.8  352.77  4429.1  351.45  4699.6   351.2  4937.2  350.48  4954.7   344.5
  4955.2     344  4960.7   344.5  4978.2  349.33  5070.5  349.89    5091   348.5
  5167.5   350.7  5301.4  350.97  5501.4  348.56  5526.2  349.89  5552.7   346.5
  5569.1  348.66  5593.7  349.25  5654.9   347.9  5689.5  349.04    5751  348.93
  5911.7  354.16  5993.8  354.61  6127.2   360.8  6161.7     361  6314.7  365.56
#Mann= 8 ,-1 , 0
  3193.1     .05       0  3519.1    .035       0  4429.1     .12       0
  4699.6      .1       0  4954.7     .05       0  4960.7      .1       0
  5689.5     .07       0  6161.7     .12       0
Bank Sta=4954.7,4960.7
XS Rating Curve= 0 ,0
Exp/Cntr=0.3,0.1

Type RM Length L Ch R = 1 ,27284   ,744,744,744
BEGIN DESCRIPTION:
Pin Oak Creek 2 43.0
END DESCRIPTION:
XS GIS Cut Line= 3
      2533507.65       13828141.        2531375.       13828525.
      2530574.98       13828675.
#Sta/Elev= 30
  2837.8  355.05  3004.8  355.56  3271.5  353.64  3521.3  351.56    3791  350.78
  3856.6  351.96  3897.2  350.66  3998.8  351.56  4123.3  350.64    4324   350.1
  4374.8  351.03  4464.9  349.26  4628.8  350.46    4641  349.29  4760.9  349.97
  4824.9  348.92  4964.1  349.49  4977.9  348.59  4984.4  343.94  4991.6  343.66
  4992.1  343.16  4997.6  343.66  5002.2  346.04  5014.9  348.06  5036.1  349.43
  5088.7  347.63  5126.8  349.09  5409.2  346.97  5488.2  347.65  5818.7  360.71
#Mann= 7 ,-1 , 0
  2837.8     .05       0  3271.5    .035       0  4123.3     .12       0
  4824.9      .1       0  4991.6     .05       0  4997.6      .1       0
  5488.2     .05       0
Bank Sta=4991.6,4997.6
XS Rating Curve= 0 ,0
Exp/Cntr=0.3,0.1

Type RM Length L Ch R = 1 ,26540   ,476,476,476
BEGIN DESCRIPTION:
Pin Oak Creek 2 42.0
END DESCRIPTION:
XS GIS Cut Line= 3
      2532877.41     13827448.29      2531054.47     13828068.09
      2530294.07     13828255.59
#Sta/Elev= 30
  2940.8  359.92  3024.4  359.41  3024.9  359.37    3099  359.79  3129.9   357.6
    3235  357.13  3306.8  356.43  3335.6  355.78  3468.6  353.49  3519.3  352.63
  3878.1  347.72  3910.8  349.66  3981.8  349.37  4200.2  347.56  4217.9  349.34
  4249.3  348.54  4274.2   345.2  4276.5   343.4    4277   342.9  4284.9   343.4
    4286  347.27  4305.9  348.92    4382   347.2  4770.9  347.34  4968.7   348.3
  5009.9  343.63  5121.4  351.43  5289.1   355.9  5528.7  363.01  5649.4  367.56
#Mann= 17 ,-1 , 0
  2940.8     .07       0  3024.4    .035       0  3024.9     .05       0
  3129.9    .035       0    3235     .05       0  3306.8     .12       0
  3335.6     .05       0  3468.6    .035       0  3519.3     .05       0
  3910.8     .12       0  3981.8      .1       0  4276.5     .05       0
  4284.9      .1       0    4382     .12       0  4770.9      .1       0
  5289.1     .07       0  5528.7     .05       0
Bank Sta=4276.5,4284.9
XS Rating Curve= 0 ,0
Exp/Cntr=0.3,0.1

Type RM Length L Ch R = 1 ,26064   ,556,556,556
BEGIN DESCRIPTION:
Pin Oak Creek 2 41.0
END DESCRIPTION:
XS GIS Cut Line= 3
      2532609.09     13827118.36      2531056.29      13827680.8
      2530286.03     13827741.93
#Sta/Elev= 30
    3116  361.88    3354   358.9  3537.5  356.58  3537.7  356.59  3643.4  354.55
  3960.6  347.99    4061  347.56  4098.8  351.43  4122.3  347.86  4200.9  347.12
  4343.5  347.38  4356.8  343.87  4364.7  346.45    4418  348.09    4474  343.72
  4499.3  347.15  4535.2  346.93  4612.3  342.28  4612.8  341.78  4620.7  342.28
  4672.5  346.68  4694.4  344.47  4959.4  348.37  5005.2  344.36  5012.4  342.36
  5039.7  346.98  5103.6  350.42  5250.3  355.86  5433.9  357.41  5540.2   359.1
#Mann= 11 ,-1 , 0
    3116     .05       0    3354    .035       0  3537.5     .05       0
  3537.7    .035       0  3643.4     .05       0  4200.9      .1       0
  4612.3     .05       0  4620.7      .1       0  5005.2     .12       0
  5103.6     .07       0  5433.9     .05       0
Bank Sta=4612.3,4620.7
XS Rating Curve= 0 ,0
Exp/Cntr=0.3,0.1

Type RM Length L Ch R = 1 ,25508   ,460,460,460
BEGIN DESCRIPTION:
Pin Oak Creek 2 40.0
END DESCRIPTION:
XS GIS Cut Line= 4
      2532701.51     13826668.37        2531075.       13827325.
      2531042.43     13827339.25       2530078.8     13827619.64
#Sta/Elev= 30
  3242.1  363.03  3339.3  361.58  3820.1  354.51  3889.2   353.7    3907  355.13
  3913.3  353.39  3950.1  352.33  4220.2  349.56  4494.8  346.89  4797.9  346.49
  4942.2  344.94  4986.8  347.07  5005.1  345.99  5012.4  341.41  5012.9  340.91
  5023.5  341.41  5039.5   345.2  5293.3  345.47  5323.3  344.71  5341.5  347.16
  5395.5  348.47  5435.2  353.41  5462.6  350.18  5476.9  351.46    5540  349.02
    5581   352.7  5695.6  353.53  5770.5   356.5  5854.8  358.15  6035.3  362.32
#Mann= 11 ,-1 , 0
  3242.1     .05       0  3339.3    .035       0  3820.1     .05       0
  4220.2     .07       0  4494.8     .05       0  4797.9      .1       0
  5012.4     .05       0  5023.5      .1       0  5293.3     .12       0
  5770.5     .07       0  5854.8     .05       0
Bank Sta=5012.4,5023.5
XS Rating Curve= 0 ,0
Exp/Cntr=0.3,0.1

Type RM Length L Ch R = 1 ,25048   ,433,433,433
BEGIN DESCRIPTION:
Pin Oak Creek 2 39.0
END DESCRIPTION:
XS GIS Cut Line= 5
      2532467.48     13826203.33      2530879.19     13826971.51
        2530875.       13826975.      2530869.32     13826979.13
      2530136.12     13827299.71
#Sta/Elev= 30
  3229.5  368.48  3407.1  365.12  3509.3  363.07    3917  353.65  3980.9  352.44
  4003.5   353.8  4020.5  351.49    4132  349.42    4235  349.62  4415.7   346.4
  4702.5  344.62  4833.5  344.22  4850.5  345.47  4878.7  344.52  4901.3  346.15
  4923.8  345.51  4931.8   346.9  4993.8  341.88  5012.4   342.6  5036.5  339.71
    5037  339.21  5047.7  339.71  5053.8  345.76  5065.6  344.29  5081.9  344.91
  5120.1  343.04  5145.8  344.47  5254.7  345.57  5581.2   354.3  5806.5  356.65
#Mann= 10 ,-1 , 0
  3229.5    .035       0  3407.1     .05       0  3509.3    .035       0
    3917     .05       0  4702.5      .1       0  5036.5     .05       0
  5047.7      .1       0  5145.8     .05       0  5254.7     .07       0
  5581.2     .05       0
Bank Sta=5036.5,5047.7
XS Rating Curve= 0 ,0
Exp/Cntr=0.3,0.1