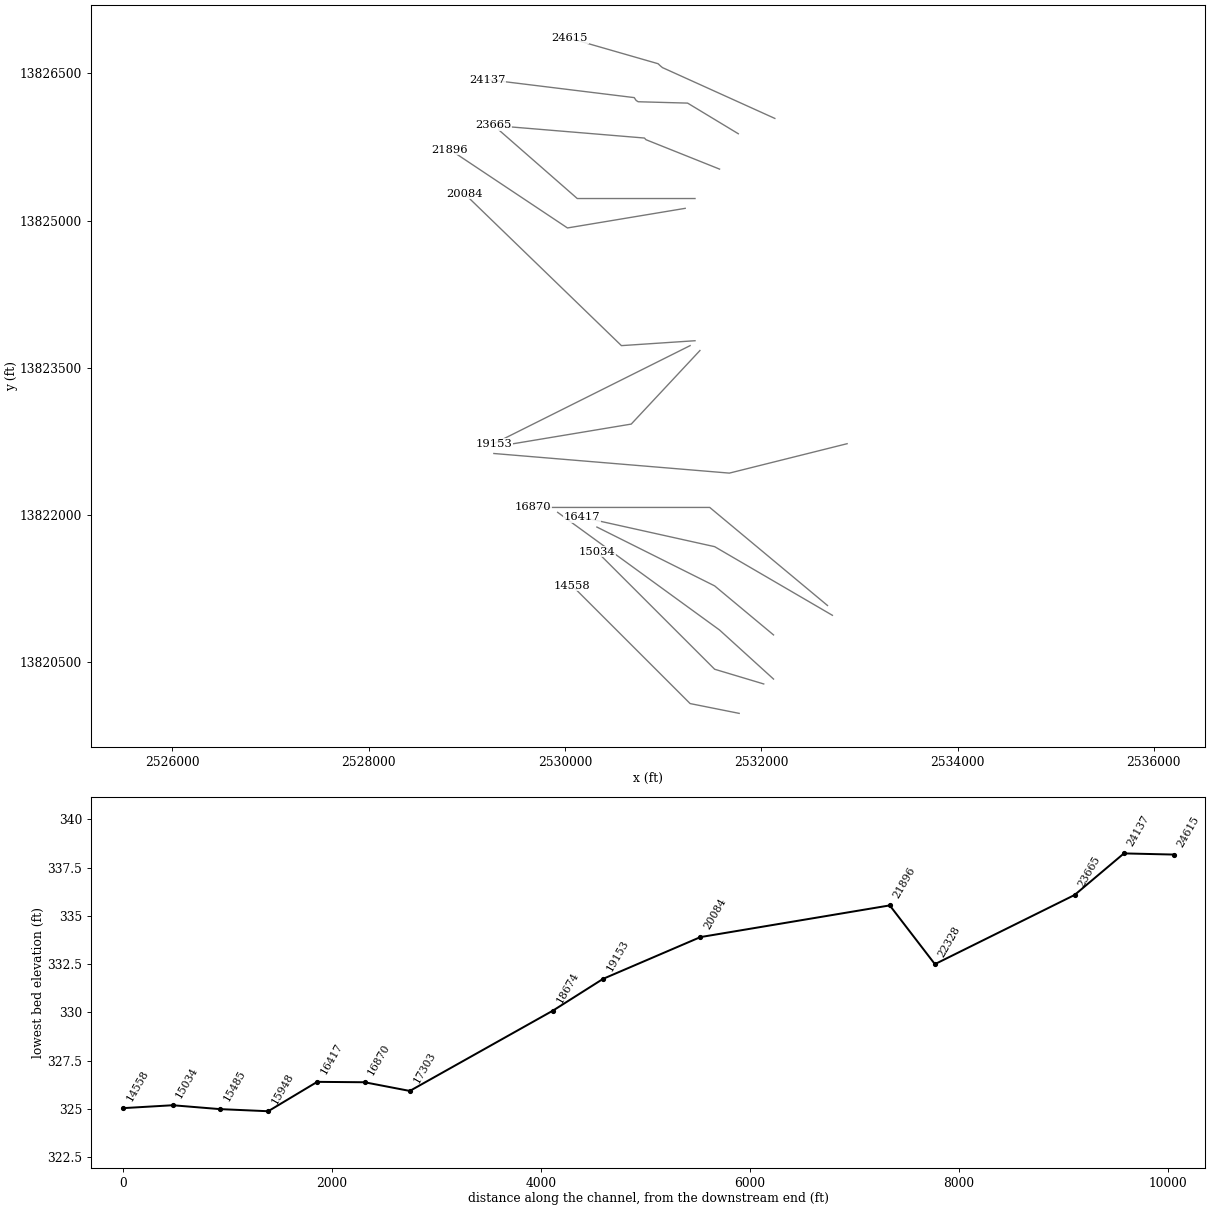
HEC-RAS study Pin Oak Creek 2.prj: Pin Oak Creek 2 Base Level Engineering

--- Pin Oak Creek 2.g01 (geometry) --- (continued)

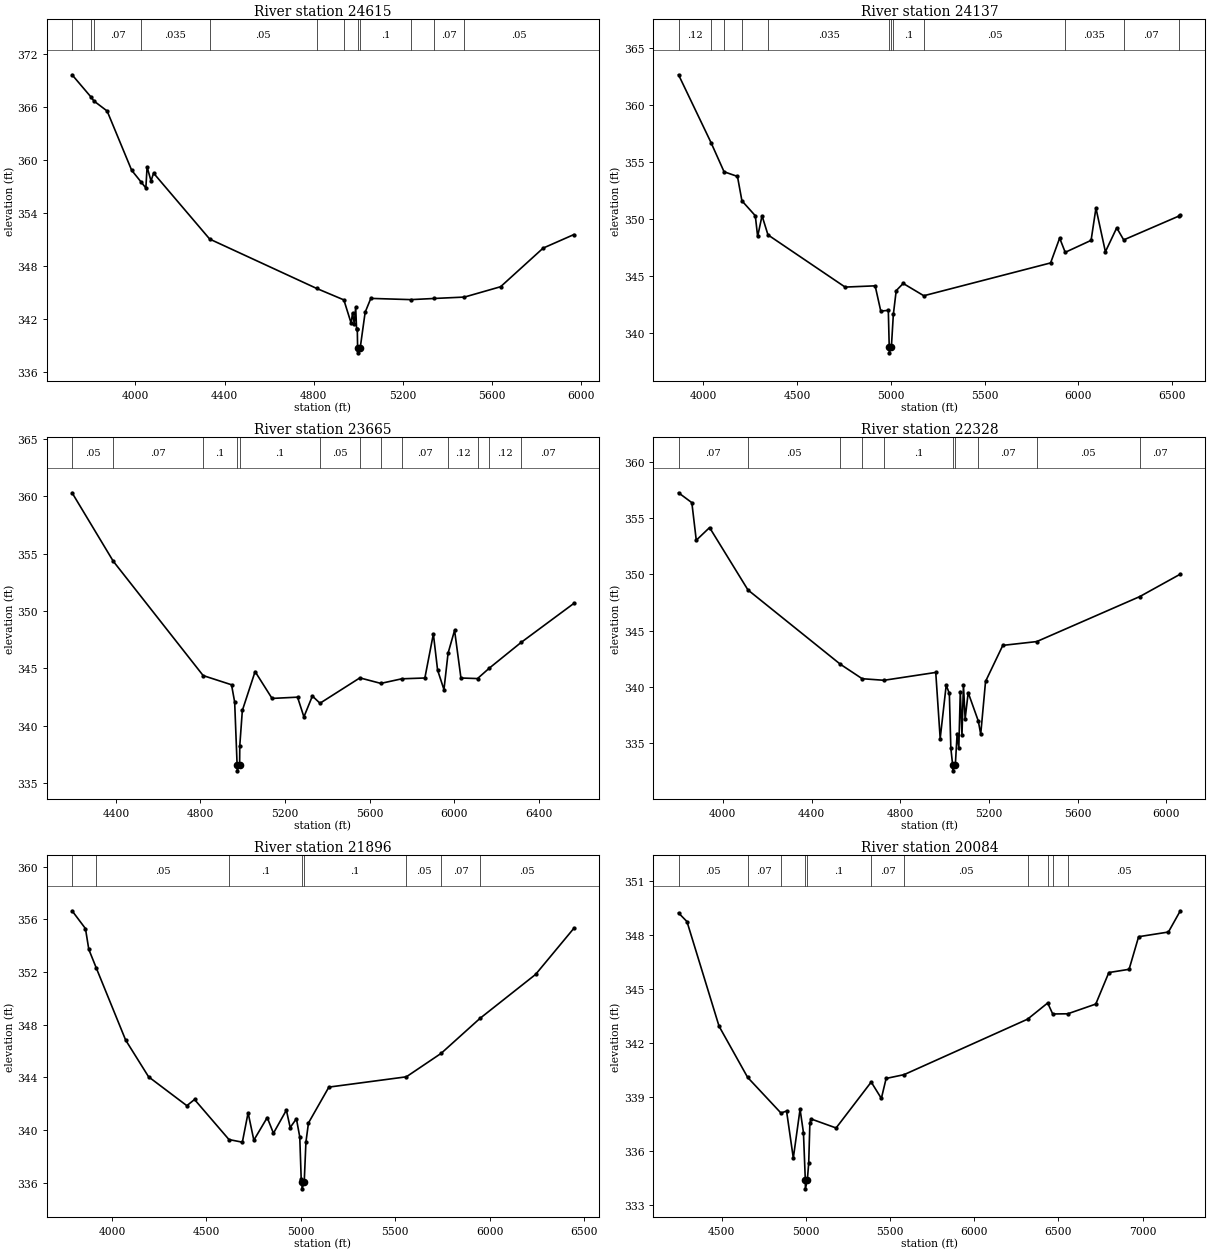
Type RM Length L Ch R = 1 ,24615   ,478,478,478
BEGIN DESCRIPTION:
Pin Oak Creek 2 38.0
END DESCRIPTION:
XS GIS Cut Line= 5
      2532138.42     13826041.87      2530993.43     13826560.03
        2530975.       13826575.      2530948.31     13826599.79
      2530048.94     13826858.55
#Sta/Elev= 30
  3715.3  369.63  3800.4  367.11  3813.6  366.66  3872.7  365.53  3982.8  358.83
  4025.1   357.5  4046.6  356.82  4052.1  359.21  4069.7  357.62  4081.3   358.5
  4333.2  351.04  4813.1  345.46  4935.5  344.16  4968.4  341.51  4974.3  342.68
  4982.2  341.48  4988.6  343.31  4992.6  340.88  4995.8  340.88  4997.3  338.67
  4997.8  338.17  5008.6  338.67  5031.1  342.76  5056.5  344.33  5236.4  344.19
  5339.7  344.32    5477  344.48  5639.2  345.65  5830.2  350.02  5968.1  351.55
#Mann= 12 ,-1 , 0
  3715.3     .07       0  3800.4     .05       0  3813.6     .07       0
  4025.1    .035       0  4333.2     .05       0  4813.1     .12       0
  4935.5      .1       0  4997.3     .05       0  5008.6      .1       0
  5236.4     .05       0  5339.7     .07       0    5477     .05       0
Bank Sta=4997.3,5008.6
XS Rating Curve= 0 ,0
Exp/Cntr=0.3,0.1

Type RM Length L Ch R = 1 ,24137   ,472,472,472
BEGIN DESCRIPTION:
Pin Oak Creek 2 37.0
END DESCRIPTION:
XS GIS Cut Line= 6
      2531765.99     13825885.67      2531249.36     13826198.05
      2530745.92     13826211.93        2530725.       13826225.
      2530705.63     13826254.06      2529208.45     13826438.15
#Sta/Elev= 30
  3867.7  362.63  4040.9  356.68  4110.4  354.12  4181.9  353.71  4205.7  351.57
    4277  350.26  4289.5  348.44  4312.9  350.26  4344.6  348.58  4755.9     344
    4916  344.11    4946  341.89  4986.2  341.96  4991.1  338.73  4991.6  338.23
  5002.5  338.73    5013   341.6  5028.3  343.69  5065.5  344.32  5175.4  343.24
  5851.4  346.12  5899.7   348.3  5929.4  347.05  6067.3   348.1  6093.2  350.93
  6143.6   347.1    6204   349.2  6241.2  348.14  6535.1  350.23  6543.1  350.33
#Mann= 12 ,-1 , 0
  3867.7     .12       0  4040.9     .07       0  4110.4     .12       0
  4205.7     .07       0  4344.6    .035       0  4991.1    .035       0
  5002.5    .035       0    5013      .1       0  5175.4     .05       0
  5929.4    .035       0  6241.2     .07       0  6535.1     .05       0
Bank Sta=4991.1,5002.5
XS Rating Curve= 0 ,0
Exp/Cntr=0.3,0.1

Type RM Length L Ch R = 1 ,23665   ,1337,1337,1337
BEGIN DESCRIPTION:
Pin Oak Creek 2 36.0
END DESCRIPTION:
XS GIS Cut Line= 4
      2531575.04     13825524.99        2530825.       13825825.
      2530809.51      13825841.9      2529272.96     13825969.77
#Sta/Elev= 30
  4193.1  360.31  4387.7  354.35    4813  344.38  4947.1  343.58  4961.9  342.07
  4973.5  336.58    4974  336.08  4985.3  336.58  4986.1  338.28  4998.2  341.34
  5058.5  344.73  5138.7  342.39  5259.2   342.5  5289.3  340.78  5329.4   342.6
  5365.3  341.97  5553.9  344.18    5653   343.7  5752.1   344.1  5861.2  344.17
  5901.4  348.01  5921.4  344.86  5951.5  343.16    5971  346.34  6001.7  348.32
  6031.8  344.17  6110.1  344.12  6166.6  345.04  6316.4  347.27  6565.7  350.67
#Mann= 13 ,-1 , 0
  4193.1     .05       0  4387.7     .07       0    4813      .1       0
  4973.5     .05       0  4985.3      .1       0  5365.3     .05       0
  5553.9     .07       0    5653     .05       0  5752.1     .07       0
    5971     .12       0  6110.1     .07       0  6166.6     .12       0
  6316.4     .07       0
Bank Sta=4973.5,4985.3
XS Rating Curve= 0 ,0
Exp/Cntr=0.3,0.1

Type RM Length L Ch R = 1 ,22328   ,432,432,432
BEGIN DESCRIPTION:
Pin Oak Creek 2 35.0
END DESCRIPTION:
XS GIS Cut Line= 3
      2531324.98       13825225.        2530125.       13825225.
        2529325.       13825925.
#Sta/Elev= 30
  3800.3  357.28  3860.3   356.4  3880.3  353.05  3940.3  354.18  4113.4  348.62
    4530     342  4628.5  340.71    4727  340.57  4960.3  341.27  4980.3  335.38
  5007.4  340.13  5021.6   339.4  5028.3  334.54  5036.6     333  5037.1   332.5
  5048.5     333  5056.8  335.82  5064.3  334.52    5071  339.57  5078.6  335.69
  5085.2  340.16  5092.8  337.13  5106.6  339.47  5152.2  336.94  5163.1  335.76
  5184.9  340.47  5262.7  343.68  5415.8  344.02  5880.5  348.03  6063.3  350.03
#Mann= 10 ,-1 , 0
  3800.3     .07       0  4113.4     .05       0    4530     .07       0
  4628.5     .05       0    4727      .1       0  5036.6     .05       0
  5048.5      .1       0  5152.2     .07       0  5415.8     .05       0
  5880.5     .07       0
Bank Sta=5036.6,5048.5
XS Rating Curve= 0 ,0
Exp/Cntr=0.3,0.1

Type RM Length L Ch R = 1 ,21896   ,1812,1812,1812
BEGIN DESCRIPTION:
Pin Oak Creek 2 34.0
END DESCRIPTION:
XS GIS Cut Line= 3
      2531224.97       13825125.        2530025.       13824925.
      2528825.04     13825724.97
#Sta/Elev= 30
  3788.1  356.64    3859  355.29  3876.8  353.71  3916.6  352.29  4071.9  346.83
  4193.6  344.04  4396.3  341.85  4436.9  342.32  4619.4  339.28  4690.3  339.08
  4720.8  341.31  4751.2  339.23  4822.1  340.95  4855.1  339.76  4923.5  341.51
  4943.8  340.19  4976.7  340.86  4994.5  339.48  5002.1   336.3  5006.1  336.04
  5006.6  335.54  5018.1  336.04  5027.2  339.09  5040.7  340.54  5148.8  343.26
  5559.1  344.04  5743.6  345.82  5949.8  348.48    6244  351.81  6446.8  355.31
#Mann= 8 ,-1 , 0
  3788.1     .07       0  3916.6     .05       0  4619.4      .1       0
  5006.1     .05       0  5018.1      .1       0  5559.1     .05       0
  5743.6     .07       0  5949.8     .05       0
Bank Sta=5006.1,5018.1
XS Rating Curve= 0 ,0
Exp/Cntr=0.3,0.1

Type RM Length L Ch R = 1 ,20084   ,931,931,931
BEGIN DESCRIPTION:
Pin Oak Creek 2 33.0
END DESCRIPTION:
XS GIS Cut Line= 3
      2531325.02       13823775.        2530575.       13823725.
      2528974.97     13825275.03
#Sta/Elev= 30
  4244.2  349.22  4294.3  348.74  4484.8  342.93  4654.4  340.09  4852.3  338.11
  4885.6  338.22  4925.7  335.61  4965.8  338.32  4985.9  337.02  4996.9   334.4
  4997.4   333.9    5009   334.4  5017.1  335.33  5024.1  337.56  5031.3  337.78
  5179.7  337.28  5388.2  339.83  5448.5  338.92  5476.8  340.03  5583.2  340.24
  6316.4  343.32    6436  344.22    6466  343.61  6555.2  343.62  6721.5  344.16
  6799.2  345.91  6919.4  346.09    6976   347.9  7152.9  348.16  7223.6  349.34
#Mann= 11 ,-1 , 0
  4244.2     .05       0  4654.4     .07       0  4852.3      .1       0
  4996.9     .05       0    5009      .1       0  5388.2     .07       0
  5583.2     .05       0  6316.4     .07       0    6436     .05       0
    6466     .07       0  6555.2     .05       0
Bank Sta=4996.9,5009
XS Rating Curve= 0 ,0
Exp/Cntr=0.3,0.1

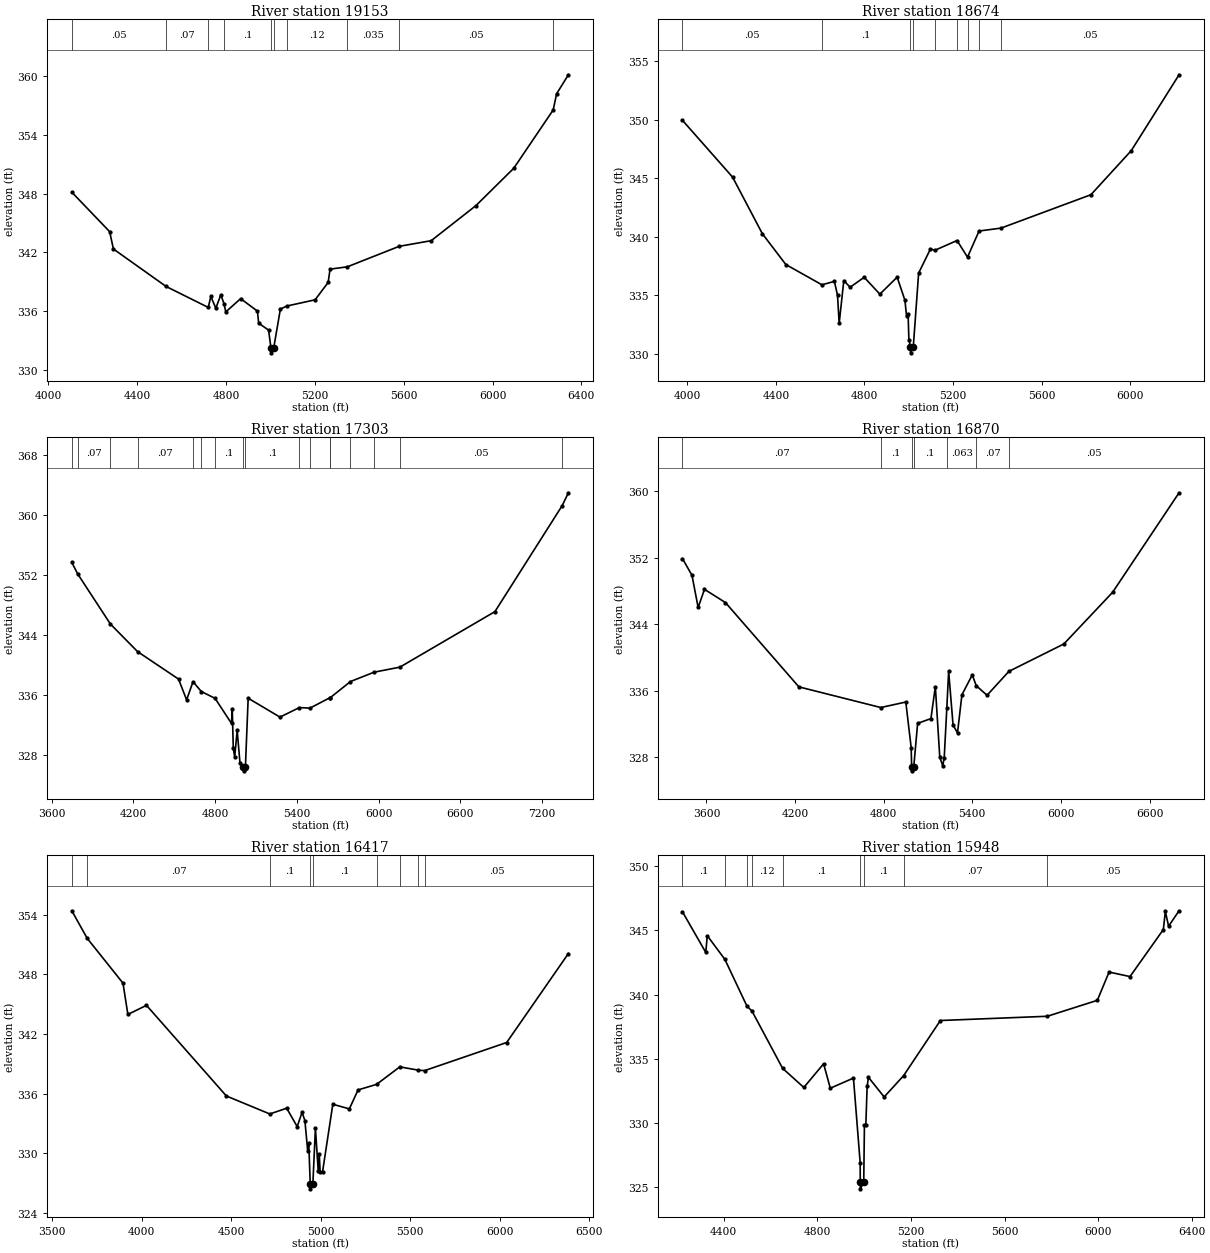
Type RM Length L Ch R = 1 ,19153   ,479,479,479
BEGIN DESCRIPTION:
Pin Oak Creek 2 32.0
END DESCRIPTION:
XS GIS Cut Line= 3
      2531275.03     13823725.02        2530475.       13823325.
        2529275.       13822725.
#Sta/Elev= 30
  4105.3  348.15  4275.8  344.12  4292.6  342.35    4530  338.52  4719.7  336.38
  4731.4   337.5  4753.8   336.3  4776.2  337.66    4791  336.74  4798.5  335.92
  4865.6  337.28  4941.1     336  4946.7  334.77  4991.4  334.06  5001.9  332.24
  5002.4  331.74  5014.4  332.24  5044.5  336.21  5073.1  336.52    5201  337.16
  5259.7  338.94  5268.1  340.29    5346  340.53  5579.1  342.62  5723.7   343.2
  5924.9  346.78  6095.4   350.6    6273  356.56  6288.3  358.21  6341.4  360.15
#Mann= 10 ,-1 , 0
  4105.3     .05       0    4530     .07       0  4719.7     .05       0
    4791      .1       0  5001.9     .05       0  5014.4      .1       0
  5073.1     .12       0    5346    .035       0  5579.1     .05       0
    6273     .07       0
Bank Sta=5001.9,5014.4
XS Rating Curve= 0 ,0
Exp/Cntr=0.3,0.1

Type RM Length L Ch R = 1 ,18674   ,1371,1371,1371
BEGIN DESCRIPTION:
Pin Oak Creek 2 31.0
END DESCRIPTION:
XS GIS Cut Line= 3
        2531375.       13823675.        2530675.       13822925.
      2529474.96     13822724.99
#Sta/Elev= 30
  3978.1  349.95  4204.5   345.1  4338.9  340.27  4444.9  337.64  4607.8  335.91
  4664.2   336.2  4678.4     335  4685.7  332.61  4706.7  336.27  4735.1   335.7
  4798.8  336.55  4869.4  335.11  4947.6  336.56  4982.8  334.58  4990.1  333.22
  4996.9  333.44  5000.6  331.23  5007.8   330.6  5008.3   330.1  5020.4   330.6
  5044.6  336.91  5097.8  338.96  5118.6  338.86    5218  339.69  5265.3  338.27
  5317.4   340.5  5416.8  340.75  5822.6   343.6  6005.1  347.37  6220.6  353.84
#Mann= 9 ,-1 , 0
  3978.1     .05       0  4607.8      .1       0  5007.8     .05       0
  5020.4      .1       0  5118.6     .07       0    5218     .12       0
  5265.3     .05       0  5317.4    .035       0  5416.8     .05       0
Bank Sta=5007.8,5020.4
XS Rating Curve= 0 ,0
Exp/Cntr=0.3,0.1

Type RM Length L Ch R = 1 ,17303   ,433,433,433
BEGIN DESCRIPTION:
Pin Oak Creek 2 30.0
END DESCRIPTION:
XS GIS Cut Line= 3
      2532875.01       13822725.        2531675.       13822425.
      2529274.97       13822625.
#Sta/Elev= 30
  3748.6  353.72  3791.9  352.18  4032.1   345.5  4231.4  341.83    4532  338.17
  4591.3   335.4  4638.4  337.82  4699.4  336.51  4800.2   335.6  4921.1  332.25
  4926.3  334.24    4934  328.93  4944.3  327.79  4962.4  331.32    4983  327.01
  5008.5  326.44    5009  325.94  5022.9  326.44  5043.2  335.62  5276.6   333.1
  5418.9  334.37    5497   334.3  5644.8   335.7  5646.5   335.7  5794.2  337.84
  5967.7  339.09  6156.8  339.76  6854.5  347.16  7348.3  361.29  7393.9     363
#Mann= 17 ,-1 , 0
  3748.6     .05       0  3791.9     .07       0  4032.1     .05       0
  4231.4     .07       0  4638.4     .05       0  4699.4     .07       0
  4800.2      .1       0  5008.5     .05       0  5022.9      .1       0
  5418.9     .07       0    5497     .05       0  5644.8     .07       0
  5646.5     .05       0  5794.2     .07       0  5967.7    .035       0
  6156.8     .05       0  7348.3     .07       0
Bank Sta=5008.5,5022.9
XS Rating Curve= 0 ,0
Exp/Cntr=0.3,0.1

Type RM Length L Ch R = 1 ,16870   ,453,453,453
BEGIN DESCRIPTION:
Pin Oak Creek 2 29.0
END DESCRIPTION:
XS GIS Cut Line= 3
      2532675.02     13821074.98        2531475.       13822075.
      2529674.97       13822075.
#Sta/Elev= 30
  3437.9  351.87  3502.4  349.86    3544     346    3587  348.18  3728.9  346.59
  4226.1  336.47  4780.5  333.99  4949.9  334.65  4986.3  329.19  4989.5  326.89
    4990  326.39  5003.9  326.89    5030  332.09    5120  332.66    5150  336.49
    5180  328.03    5200     327    5210  327.95  5227.8  333.96    5240  338.35
    5270  331.88    5300  330.95    5330  335.52    5400  337.91  5426.8  336.61
    5500  335.46  5647.9  338.33    6020  341.62    6350  347.82    6800  359.77
#Mann= 7 ,-1 , 0
  3437.9     .07       0  4780.5      .1       0  4989.5     .05       0
  5003.9      .1       0  5227.8    .063       0  5426.8     .07       0
  5647.9     .05       0
Bank Sta=4989.5,5003.9
XS Rating Curve= 0 ,0
Exp/Cntr=0.3,0.1

Type RM Length L Ch R = 1 ,16417   ,469,469,469
BEGIN DESCRIPTION:
Pin Oak Creek 2 28.0
END DESCRIPTION:
XS GIS Cut Line= 3
      2532725.01     13820974.99        2531525.       13821675.
      2530174.99       13821975.
#Sta/Elev= 30
  3610.7  354.38    3697   351.6  3896.4   347.1  3923.7  343.95  4027.5  344.87
  4473.6  335.75    4716  333.94  4810.2  334.52  4868.9  332.67  4896.2  334.11
  4911.9  333.27  4927.6  330.21  4933.4  330.99  4941.8  326.91  4942.3  326.41
  4956.4  326.91  4970.6  332.52  4986.3  328.22  4992.1  329.89  4997.1  328.08
  5010.2  328.09  5067.8  334.92    5160  334.45  5208.7  336.36  5312.3  336.92
  5441.6  338.68  5544.3  338.35  5579.8   338.3  6038.4  341.13  6382.9  350.08
#Mann= 9 ,-1 , 0
  3610.7     .12       0    3697     .07       0    4716      .1       0
  4941.8     .05       0  4956.4      .1       0  5312.3     .07       0
  5441.6     .05       0  5544.3     .07       0  5579.8     .05       0
Bank Sta=4941.8,4956.4
XS Rating Curve= 0 ,0
Exp/Cntr=0.3,0.1

Type RM Length L Ch R = 1 ,15948   ,463,463,463
BEGIN DESCRIPTION:
Pin Oak Creek 2 27.0
END DESCRIPTION:
XS GIS Cut Line= 3
      2532125.01       13820775.        2531525.       13821275.
      2530324.98     13821875.01
#Sta/Elev= 30
  4223.3  346.45  4322.9  343.29  4329.4  344.59  4404.5  342.75  4499.2   339.1
    4520  338.74  4651.3  334.27    4742  332.78  4826.6  334.62  4855.3  332.72
  4954.2  333.51  4982.9  326.92  4983.3  325.39  4983.8  324.89  4998.1  325.39
  5001.1  329.84  5007.1  329.84  5012.7  332.88  5018.3  333.57  5085.4  332.04
  5168.2  333.69  5325.8  337.99  5782.8  338.32  5996.6  339.56  6046.9  341.76
  6136.3  341.41  6278.9  345.07  6287.3  346.48  6301.3  345.33    6346  346.53
#Mann= 9 ,-1 , 0
  4223.3      .1       0  4404.5     .12       0  4499.2      .1       0
    4520     .12       0  4651.3      .1       0  4983.3     .05       0
  4998.1      .1       0  5168.2     .07       0  5782.8     .05       0
Bank Sta=4983.3,4998.1
XS Rating Curve= 0 ,0
Exp/Cntr=0.3,0.1

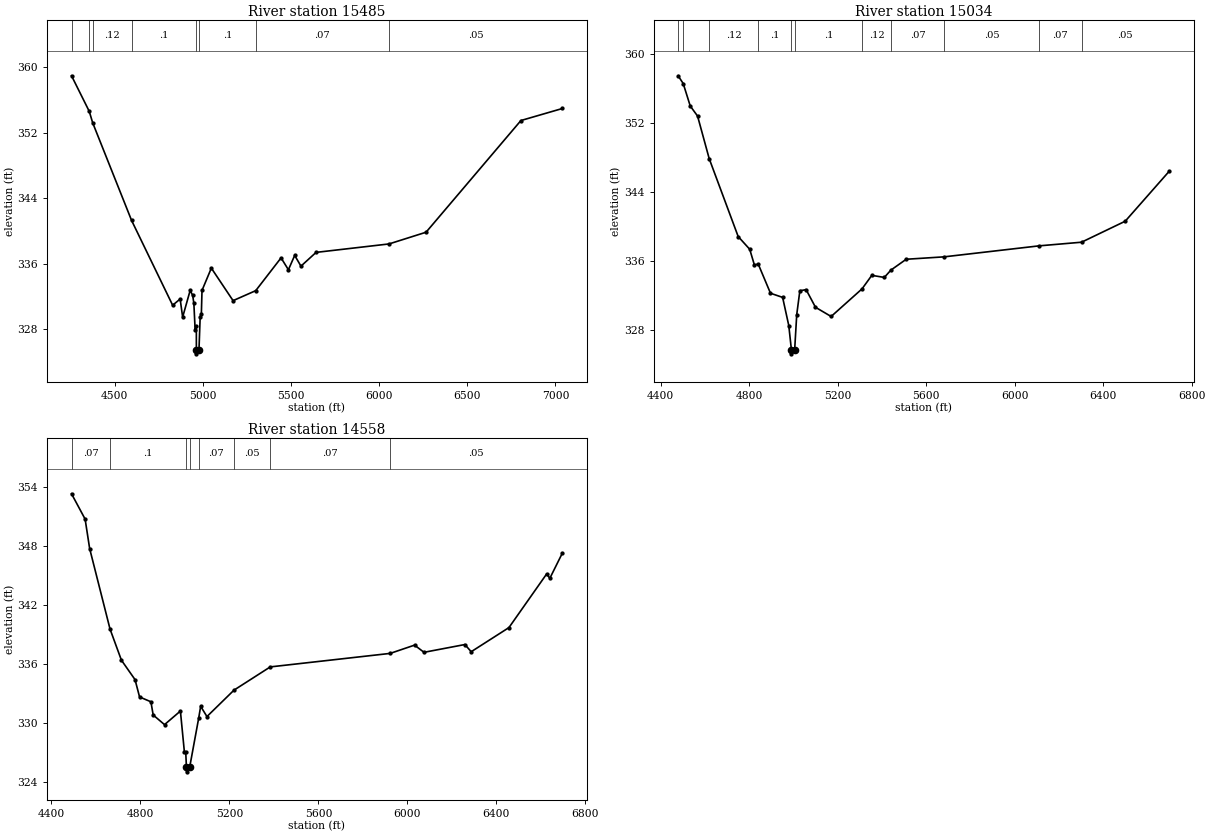
Type RM Length L Ch R = 1 ,15485   ,451,451,451
BEGIN DESCRIPTION:
Pin Oak Creek 2 26.0
END DESCRIPTION:
XS GIS Cut Line= 3
      2532125.01     13820324.99        2531575.       13820825.
      2529925.03     13822024.98
#Sta/Elev= 30
  4256.3  358.93  4356.8  354.59  4376.3  353.19  4596.8  341.28  4829.7  330.93
  4872.2  331.69  4886.4  329.48    4929  332.74  4943.2  332.14    4950  331.16
  4957.4  327.85  4964.1  328.42  4964.2   325.5  4964.7     325    4979   325.5
  4985.8  329.51  4992.5  329.86  4996.2  332.74  5049.1  335.46  5172.3  331.49
  5300.8  332.71  5444.4  336.71  5486.1  335.26  5521.7  337.01  5557.2   335.7
    5643  337.38  6056.6  338.41  6266.6  339.84  6804.5  353.47  7039.8  354.94
#Mann= 8 ,-1 , 0
  4256.3     .12       0  4356.8     .07       0  4376.3     .12       0
  4596.8      .1       0  4964.2     .05       0    4979      .1       0
  5300.8     .07       0  6056.6     .05       0
Bank Sta=4964.2,4979
XS Rating Curve= 0 ,0
Exp/Cntr=0.3,0.1

Type RM Length L Ch R = 1 ,15034   ,476,476,476
BEGIN DESCRIPTION:
Pin Oak Creek 2 25.0
END DESCRIPTION:
XS GIS Cut Line= 3
      2532025.01       13820275.        2531525.       13820425.
      2530324.99     13821625.01
#Sta/Elev= 30
  4478.5  357.51  4501.5  356.61  4533.3     354  4566.4  352.83    4619  347.88
    4750  338.83  4802.2  337.35    4823  335.55  4840.8  335.62  4896.1  332.24
  4950.9  331.76  4978.8  328.48  4990.5   325.7    4991   325.2  5005.4   325.7
  5014.7  329.76  5028.8  332.53  5057.1  332.66  5099.5  330.61  5170.2  329.54
  5309.9  332.75  5354.1  334.32  5410.6  334.08  5440.4  334.93  5509.6  336.19
  5680.8  336.47  6111.1  337.75    6302  338.17  6499.6  340.61  6697.6  346.39
#Mann= 11 ,-1 , 0
  4478.5     .12       0  4501.5     .07       0    4619     .12       0
  4840.8      .1       0  4990.5     .05       0  5005.4      .1       0
  5309.9     .12       0  5440.4     .07       0  5680.8     .05       0
  6111.1     .07       0    6302     .05       0
Bank Sta=4990.5,5005.4
XS Rating Curve= 0 ,0
Exp/Cntr=0.3,0.1

Type RM Length L Ch R = 1 ,14558   ,469,469,469
BEGIN DESCRIPTION:
Pin Oak Creek 2 24.0
END DESCRIPTION:
XS GIS Cut Line= 3
      2531774.95     13819975.01        2531275.       13820075.
      2530075.01     13821274.99
#Sta/Elev= 30
  4490.1  353.27  4551.2   350.7  4571.6  347.71  4663.2  339.54  4714.4  336.38
  4775.6  334.41    4796  332.65    4847  332.16  4857.2  330.82  4908.2  329.84
  4979.6  331.22  4997.4  327.09  5003.5  327.09  5006.6  325.55  5007.1  325.05
  5021.5  325.55  5061.7  330.49  5070.7   331.7  5098.9  330.66  5220.4  333.34
  5383.6   335.7  5922.6  337.07  6032.3  337.91  6074.8  337.18  6258.6  337.97
  6286.9  337.24  6456.6  339.69  6626.3  345.14  6640.4  344.69    6697  347.26
#Mann= 8 ,-1 , 0
  4490.1     .07       0  4663.2      .1       0  5006.6     .05       0
  5021.5      .1       0  5061.7     .07       0  5220.4     .05       0
  5383.6     .07       0  5922.6     .05       0
Bank Sta=5006.6,5021.5
XS Rating Curve= 0 ,0
Exp/Cntr=0.3,0.1