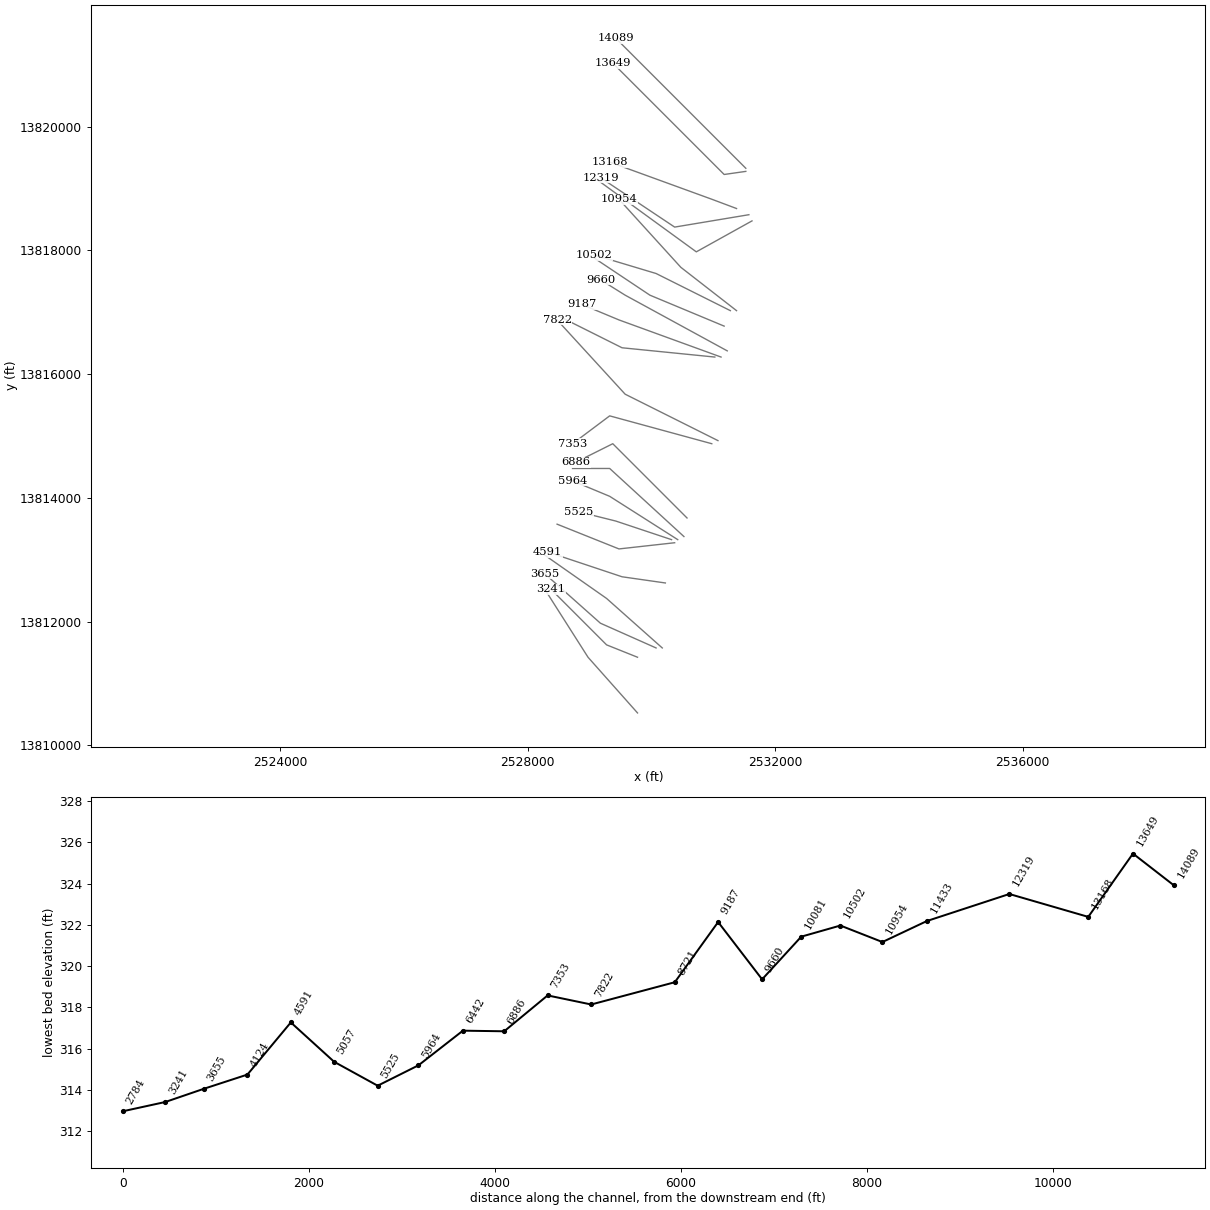
HEC-RAS study Pin Oak Creek 2.prj: Pin Oak Creek 2 Base Level Engineering

--- Pin Oak Creek 2.g01 (geometry) --- (continued)

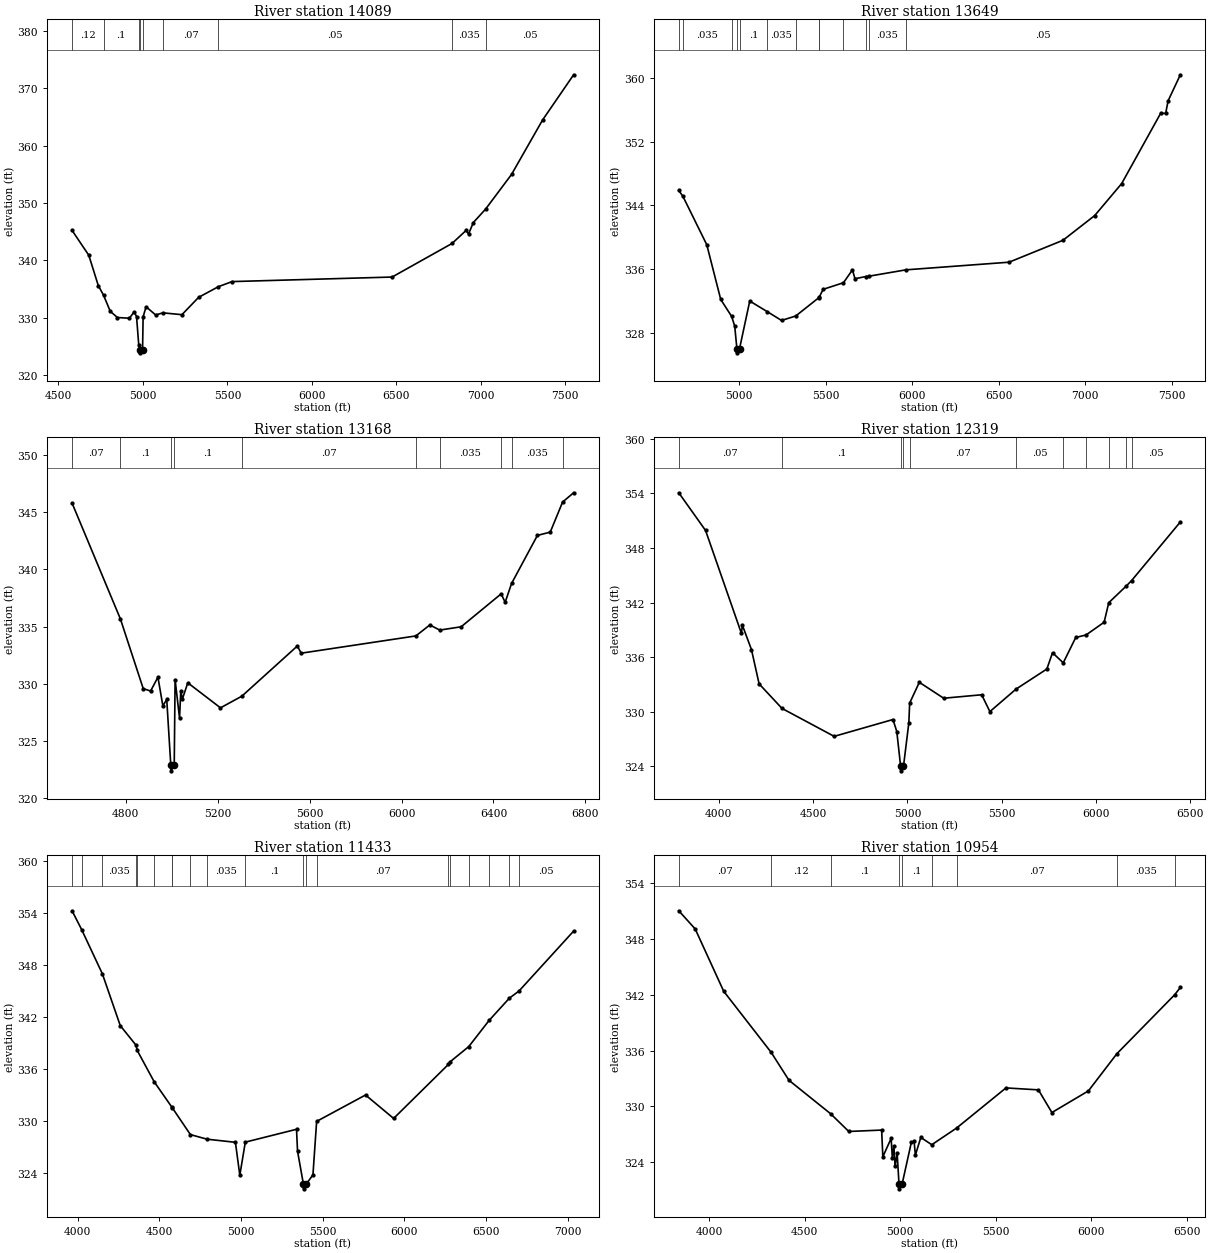
Type RM Length L Ch R = 1 ,14089   ,440,440,440
BEGIN DESCRIPTION:
Pin Oak Creek 2 23.0
END DESCRIPTION:
XS GIS Cut Line= 3
      2531524.98     13819325.02        2531225.       13819625.
      2529425.02     13821424.98
#Sta/Elev= 30
  4580.3  345.23  4679.3  340.91  4735.8  335.61  4766.8  333.95  4806.6  331.14
    4849  330.07  4919.7  329.94    4948  331.05  4962.1  330.24  4975.2  325.28
  4982.9  324.42  4983.4  323.92  4997.8  324.42    5001  330.18  5018.7  331.94
  5075.3  330.51  5118.5  330.88  5230.8  330.56  5329.8  333.58  5446.5  335.43
  5527.8  336.32  6475.3  337.11  6830.6  342.96  6913.7  345.23  6927.9  344.59
  6956.2  346.59  7028.5  348.92  7182.4  354.96  7366.3  364.44  7550.1  372.31
#Mann= 9 ,-1 , 0
  4580.3     .12       0  4766.8      .1       0  4975.2     .12       0
  4982.9     .05       0  4997.8     .12       0  5118.5     .07       0
  5446.5     .05       0  6830.6    .035       0  7028.5     .05       0
Bank Sta=4982.9,4997.8
XS Rating Curve= 0 ,0
Exp/Cntr=0.3,0.1

Type RM Length L Ch R = 1 ,13649   ,481,481,481
BEGIN DESCRIPTION:
Pin Oak Creek 2 22.0
END DESCRIPTION:
XS GIS Cut Line= 3
      2531525.05     13819275.01        2531175.       13819225.
      2529374.99     13821025.01
#Sta/Elev= 30
  4651.6  345.86  4675.6  345.12  4813.3  339.05  4894.1  332.17  4957.1  330.04
  4974.9  328.82  4987.6  325.96  4988.1  325.46  5002.6  325.96  5061.8  331.97
  5162.7  330.64  5245.6  329.53  5327.5  330.09  5460.1  332.37  5462.8  332.43
    5486  333.44  5603.4  334.27  5655.7  335.89  5669.9  334.77  5733.5  335.05
  5750.6  335.09  5964.8  335.89  6560.8  336.85    6872   339.6  7055.8  342.71
  7211.4  346.72  7437.6  355.58  7465.9  355.54  7480.1  357.13  7550.8   360.4
#Mann= 13 ,-1 , 0
  4651.6     .12       0  4675.6    .035       0  4957.1      .1       0
  4987.6     .05       0  5002.6      .1       0  5162.7    .035       0
  5327.5     .07       0  5460.1     .05       0  5462.8     .07       0
  5603.4    .035       0  5733.5     .05       0  5750.6    .035       0
  5964.8     .05       0
Bank Sta=4987.6,5002.6
XS Rating Curve= 0 ,0
Exp/Cntr=0.3,0.1

Type RM Length L Ch R = 1 ,13168   ,849,849,849
BEGIN DESCRIPTION:
Pin Oak Creek 2 21.0
END DESCRIPTION:
XS GIS Cut Line= 3
      2531375.04     13818674.99        2530975.       13818825.
      2529325.04     13819424.99
#Sta/Elev= 30
  4565.8  345.81  4776.3  335.67  4875.6  329.58  4907.6  329.37  4939.6  330.58
    4961  328.07  4977.9  328.63  4995.5  322.89    4996  322.39  5010.5  322.89
  5014.3  330.37  5033.6  326.99  5038.9  329.36  5046.2  328.68  5069.5  330.09
  5211.8   327.9  5304.8  328.92  5546.4  333.31    5563  332.68  6062.1  334.19
  6122.9  335.15  6166.1   334.7  6259.3  334.99  6433.4  337.87  6450.8  337.13
  6478.7  338.78  6591.1  342.98    6647  343.27  6700.8   345.9  6748.7  346.71
#Mann= 10 ,-1 , 0
  4565.8     .07       0  4776.3      .1       0  4995.5     .05       0
  5010.5      .1       0  5304.8     .07       0  6062.1     .05       0
  6166.1    .035       0  6433.4     .05       0  6478.7    .035       0
  6700.8     .07       0
Bank Sta=4995.5,5010.5
XS Rating Curve= 0 ,0
Exp/Cntr=0.3,0.1

Type RM Length L Ch R = 1 ,12319   ,886,886,886
BEGIN DESCRIPTION:
Pin Oak Creek 2 20.0
END DESCRIPTION:
XS GIS Cut Line= 3
        2531575.       13818575.        2530375.       13818375.
      2529174.98     13819175.01
#Sta/Elev= 30
  3788.1  354.06    3930  349.92  4120.1  338.61  4125.2  339.51  4173.3  336.83
  4213.9  333.06  4335.3  330.36  4611.8  327.29  4923.6  329.14  4943.8  327.82
  4964.1     324  4964.6   323.5  4979.3     324  5007.7  328.79  5012.1  330.95
  5063.2  333.23  5192.4  331.48  5393.8  331.86  5437.3  330.01  5575.7  332.48
  5739.3  334.69  5769.3  336.48  5826.2  335.37  5892.5  338.16  5946.8  338.43
  6042.8  339.83  6067.5  341.98  6160.6  343.82  6188.1   344.4  6446.9  350.85
#Mann= 11 ,-1 , 0
  3788.1     .07       0  4335.3      .1       0  4964.1     .05       0
  4979.3      .1       0  5012.1     .07       0  5575.7     .05       0
  5826.2     .07       0  5946.8    .035       0  6067.5     .05       0
  6160.6     .07       0  6188.1     .05       0
Bank Sta=4964.1,4979.3
XS Rating Curve= 0 ,0
Exp/Cntr=0.3,0.1

Type RM Length L Ch R = 1 ,11433   ,479,479,479
BEGIN DESCRIPTION:
Pin Oak Creek 2 19.0
END DESCRIPTION:
XS GIS Cut Line= 3
      2531624.97     13818474.98        2530725.       13817975.
      2529075.04     13819174.97
#Sta/Elev= 30
  3966.2  354.22  4024.7  352.06  4151.7  346.96  4261.3  340.99  4357.6  338.74
  4365.1  338.13  4468.6  334.53  4578.5  331.56  4579.5  331.53  4690.5  328.44
  4791.9  327.91    4966  327.55  4992.9  323.76  5026.6  327.57    5340  329.05
  5346.2  326.53  5382.6  322.69  5383.1  322.19  5397.8  322.69  5440.5   323.8
  5463.1  329.96  5762.4     333  5934.3   330.3    6270  336.53  6277.2  336.78
  6394.4  338.58  6518.7  341.59  6643.1  344.16  6701.8  344.98  7035.9  351.88
#Mann= 20 ,-1 , 0
  3966.2    .035       0  4024.7     .07       0  4151.7    .035       0
  4357.6     .07       0  4365.1    .035       0  4468.6     .07       0
  4578.5    .035       0  4579.5     .07       0  4690.5      .1       0
  4791.9    .035       0  5026.6      .1       0  5382.6    .035       0
  5397.8      .1       0  5463.1     .07       0    6270    .035       0
  6277.2     .07       0  6394.4    .035       0  6518.7     .05       0
  6643.1     .07       0  6701.8     .05       0
Bank Sta=5382.6,5397.8
XS Rating Curve= 0 ,0
Exp/Cntr=0.3,0.1

Type RM Length L Ch R = 1 ,10954   ,452,452,452
BEGIN DESCRIPTION:
Pin Oak Creek 2 18.0
END DESCRIPTION:
XS GIS Cut Line= 3
      2531375.03     13817024.98        2530475.       13817725.
      2529475.01     13818824.99
#Sta/Elev= 30
  3840.6  350.98  3926.6  349.03  4075.9  342.35  4324.1  335.81    4418   332.8
  4635.2  329.23  4731.1  327.32    4903  327.47  4909.3  324.61  4952.8  326.58
  4959.1  324.48  4967.2  325.72  4973.6  323.59  4984.2     325    4994  321.67
  4994.5  321.17  5010.1  321.67  5058.9  326.18    5073  326.25  5079.8  324.79
  5108.2  326.68  5165.5   325.9  5295.2  327.68  5554.2  331.99  5724.1  331.78
  5794.7  329.35    5986  331.67  6135.2  335.66  6437.4  341.97  6467.4  342.76
#Mann= 9 ,-1 , 0
  3840.6     .07       0  4324.1     .12       0  4635.2      .1       0
    4994     .05       0  5010.1      .1       0  5165.5    .035       0
  5295.2     .07       0  6135.2    .035       0  6437.4     .05       0
Bank Sta=4994,5010.1
XS Rating Curve= 0 ,0
Exp/Cntr=0.3,0.1

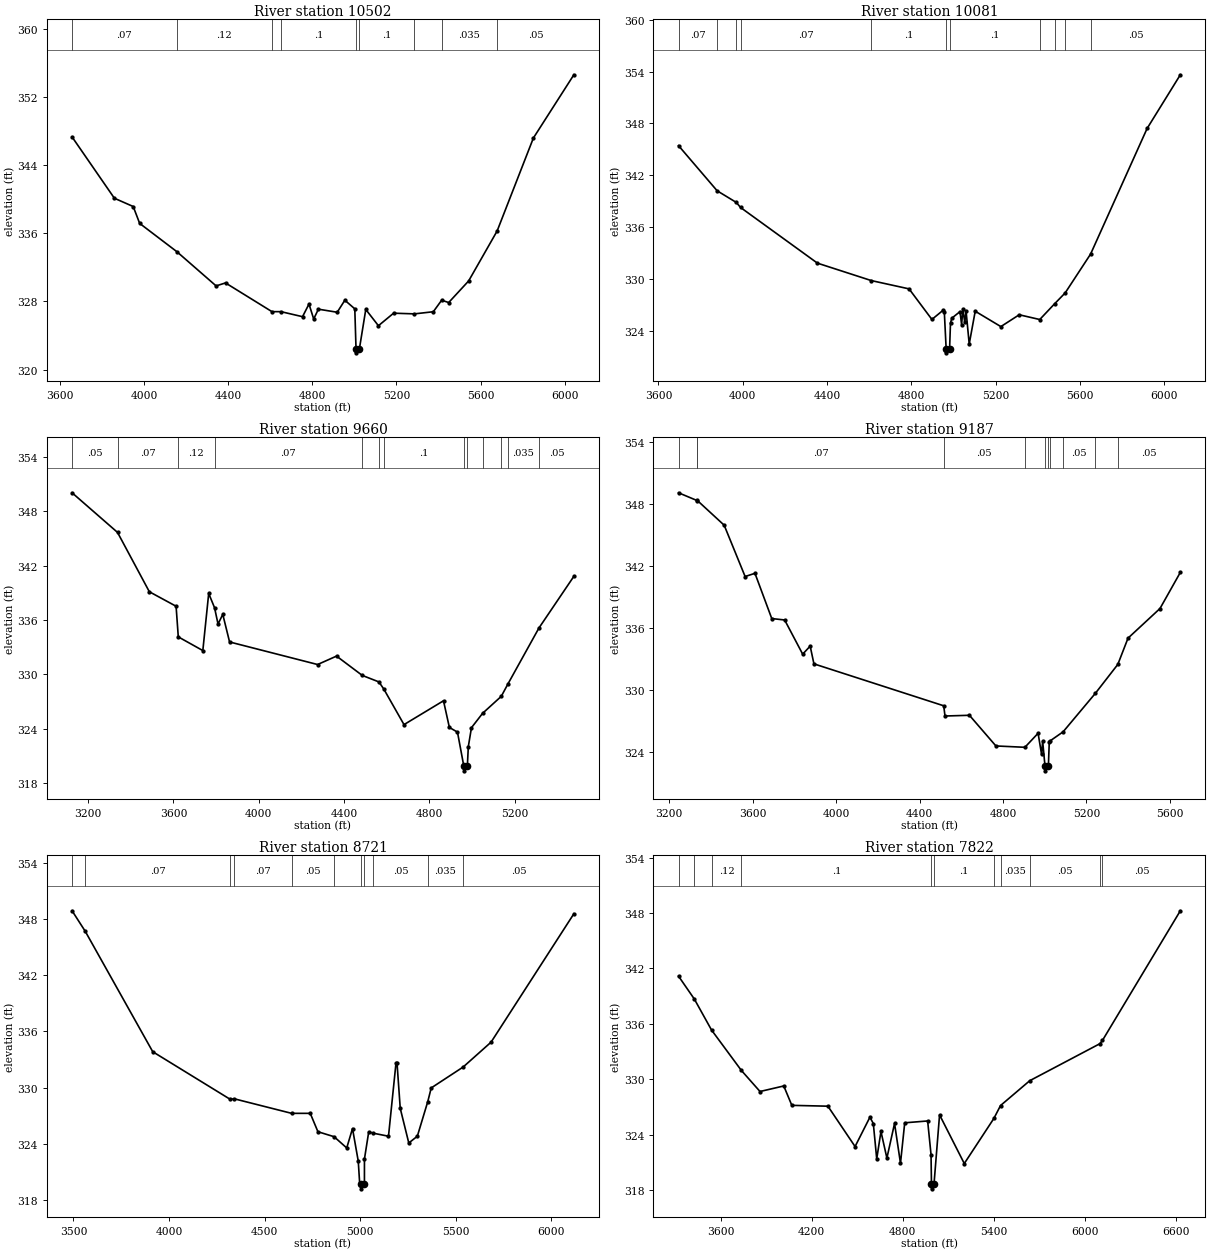
Type RM Length L Ch R = 1 ,10502   ,421,421,421
BEGIN DESCRIPTION:
Pin Oak Creek 2 17.0
END DESCRIPTION:
XS GIS Cut Line= 3
      2531274.98     13817025.01        2530075.       13817625.
      2529074.95     13817925.01
#Sta/Elev= 30
  3657.8  347.29    3859   340.1  3948.5  339.13  3979.2  337.15  4155.7  333.84
  4342.6  329.82  4387.3  330.17  4608.2   326.8  4650.8   326.8  4753.5  326.21
  4784.2  327.69  4806.6  325.94  4828.9  327.09  4918.4  326.73  4954.7  328.14
    5002  327.13  5007.8  322.47  5008.3  321.97  5024.1  322.47  5054.2  327.06
  5114.3  325.15  5186.5  326.62  5285.6  326.54  5375.3  326.79  5414.9  328.14
  5448.4  327.87  5543.2   330.4  5678.7  336.26  5851.2  347.17  6043.5  354.58
#Mann= 9 ,-1 , 0
  3657.8     .07       0  4155.7     .12       0  4608.2     .07       0
  4650.8      .1       0  5007.8     .05       0  5024.1      .1       0
  5285.6     .07       0  5414.9    .035       0  5678.7     .05       0
Bank Sta=5007.8,5024.1
XS Rating Curve= 0 ,0
Exp/Cntr=0.3,0.1

Type RM Length L Ch R = 1 ,10081   ,421,421,421
BEGIN DESCRIPTION:
Pin Oak Creek 2 16.0
END DESCRIPTION:
XS GIS Cut Line= 3
      2531174.97     13816775.01        2529975.       13817275.
      2529075.03     13817874.98
#Sta/Elev= 30
  3695.4  345.43  3878.7   340.2  3969.8  338.85  3989.7  338.27  4354.6  331.82
  4610.4   329.8  4789.5  328.84  4897.9   325.3  4951.5  326.37  4956.9  326.15
  4965.5  321.93    4966  321.43  4981.9  321.93  4986.2   324.9  4992.7  325.45
  5031.4  326.21  5038.9  324.69  5044.9  326.47    5054  324.95    5060   326.3
    5075  322.45  5103.5  326.25  5225.2  324.47  5312.4  325.84  5409.8  325.29
  5481.4  327.14  5530.4  328.37  5651.1  332.87  5919.3  347.42    6077  353.64
#Mann= 11 ,-1 , 0
  3695.4     .07       0  3878.7     .05       0  3969.8     .12       0
  3989.7     .07       0  4610.4      .1       0  4965.5     .05       0
  4981.9      .1       0  5409.8     .07       0  5481.4     .05       0
  5530.4    .035       0  5651.1     .05       0
Bank Sta=4965.5,4981.9
XS Rating Curve= 0 ,0
Exp/Cntr=0.3,0.1

Type RM Length L Ch R = 1 ,9660    ,473,473,473
BEGIN DESCRIPTION:
Pin Oak Creek 2 15.0
END DESCRIPTION:
XS GIS Cut Line= 3
      2531224.98     13816375.01        2529575.       13817275.
      2529174.97     13817525.02
#Sta/Elev= 30
  3125.3  350.04  3338.2  345.67  3487.4  339.12  3612.7  337.52    3623  334.14
    3738  332.63  3765.5  338.93    3793  337.35  3809.2  335.56  3831.5  336.62
  3863.3  333.58  4275.8  331.09  4364.5  332.02  4484.9  329.89  4563.2  329.17
  4586.3  328.37  4680.6  324.46  4865.7  327.09  4893.2  324.15  4931.2  323.63
    4961  319.86  4961.5  319.36  4977.4  319.86    4982  322.04  4996.7  324.12
    5049  325.71  5136.4  327.58  5167.2  328.93  5312.9  335.12  5476.5  340.82
#Mann= 13 ,-1 , 0
  3125.3     .05       0  3338.2     .07       0    3623     .12       0
    3793     .07       0  4484.9     .05       0  4563.2     .07       0
  4586.3      .1       0    4961     .05       0  4977.4      .1       0
    5049     .07       0  5136.4     .05       0  5167.2    .035       0
  5312.9     .05       0
Bank Sta=4961,4977.4
XS Rating Curve= 0 ,0
Exp/Cntr=0.3,0.1

Type RM Length L Ch R = 1 ,9187    ,466,466,466
BEGIN DESCRIPTION:
Pin Oak Creek 2 14.0
END DESCRIPTION:
XS GIS Cut Line= 3
      2531125.01       13816275.        2529475.       13816875.
      2528875.01     13817124.99
#Sta/Elev= 30
  3244.7  349.07    3332  348.33    3335  348.32  3463.5  345.93  3563.9  340.96
  3611.1  341.27  3691.6  336.89  3753.5  336.75  3839.9  333.44  3875.8  334.22
  3893.8   332.5  4516.1  328.44  4522.2  327.45  4639.3  327.52  4766.3  324.55
  4905.3  324.42  4968.5  325.78  4985.1  323.75  4990.4  325.01  5001.4  322.64
  5001.9  322.14  5017.9  322.64  5022.1  324.94  5026.8  325.05  5088.5  325.92
  5242.8  329.64  5350.8  332.45  5399.6  334.99  5552.9  337.86  5650.4  341.36
#Mann= 11 ,-1 , 0
  3244.7     .07       0    3332     .05       0    3335     .07       0
  4516.1     .05       0  4905.3     .12       0  5001.4     .05       0
  5017.9     .12       0  5026.8      .1       0  5088.5     .05       0
  5242.8    .035       0  5350.8     .05       0
Bank Sta=5001.4,5017.9
XS Rating Curve= 0 ,0
Exp/Cntr=0.3,0.1

Type RM Length L Ch R = 1 ,8721    ,899,899,899
BEGIN DESCRIPTION:
Pin Oak Creek 2 13.0
END DESCRIPTION:
XS GIS Cut Line= 3
      2531024.99       13816275.        2529525.       13816425.
      2528525.01       13816925.
#Sta/Elev= 30
  3492.6  348.87  3561.6  346.68  3914.7  333.84  4319.6  328.77  4341.3  328.82
  4641.4  327.27  4738.8  327.27    4779  325.31  4863.5  324.78  4929.7  323.58
  4959.9  325.65    4990  322.18  4997.6  319.73  5005.8  319.72  5006.3  319.22
  5022.3  319.72  5022.4   322.4  5044.8   325.3  5069.2  325.15  5148.2  324.83
  5187.3   332.6  5192.9  332.62  5209.7   327.8  5254.4  324.11  5299.1  324.83
  5353.7  328.52  5371.8  329.98  5538.9  332.21  5684.9  334.86  6118.1  348.55
#Mann= 11 ,-1 , 0
  3492.6     .05       0  3561.6     .07       0  4319.6     .05       0
  4341.3     .07       0  4641.4     .05       0  4863.5      .1       0
  5005.8     .05       0  5022.3      .1       0  5069.2     .05       0
  5353.7    .035       0  5538.9     .05       0
Bank Sta=5005.8,5022.3
XS Rating Curve= 0 ,0
Exp/Cntr=0.3,0.1

Type RM Length L Ch R = 1 ,7822    ,469,469,469
BEGIN DESCRIPTION:
Pin Oak Creek 2 12.0
END DESCRIPTION:
XS GIS Cut Line= 3
      2531074.96     13814925.02        2529575.       13815675.
      2528474.99     13816875.01
#Sta/Elev= 30
    3323  341.17  3427.1  338.69  3540.3  335.34  3736.9  330.96  3859.6  328.68
  4016.1  329.28  4069.2  327.18  4306.8  327.09  4485.7  322.72  4583.5   325.9
  4605.9  325.21  4628.3  321.38  4656.2  324.35  4695.3  321.47  4745.7  325.22
  4784.8  320.91  4812.7  325.29  4963.7  325.49    4986  321.85  4988.9  318.64
  4989.4  318.14  5005.5  318.64  5042.2  326.15    5205  320.88  5399.8  325.76
  5443.7  327.16  5636.2  329.85  6098.5  333.86  6115.3  334.22  6627.9  348.25
#Mann= 11 ,-1 , 0
    3323      .1       0  3427.1     .07       0  3540.3     .12       0
  3736.9      .1       0  4988.9     .05       0  5005.5      .1       0
  5399.8     .05       0  5443.7    .035       0  5636.2     .05       0
  6098.5    .035       0  6115.3     .05       0
Bank Sta=4988.9,5005.5
XS Rating Curve= 0 ,0
Exp/Cntr=0.3,0.1

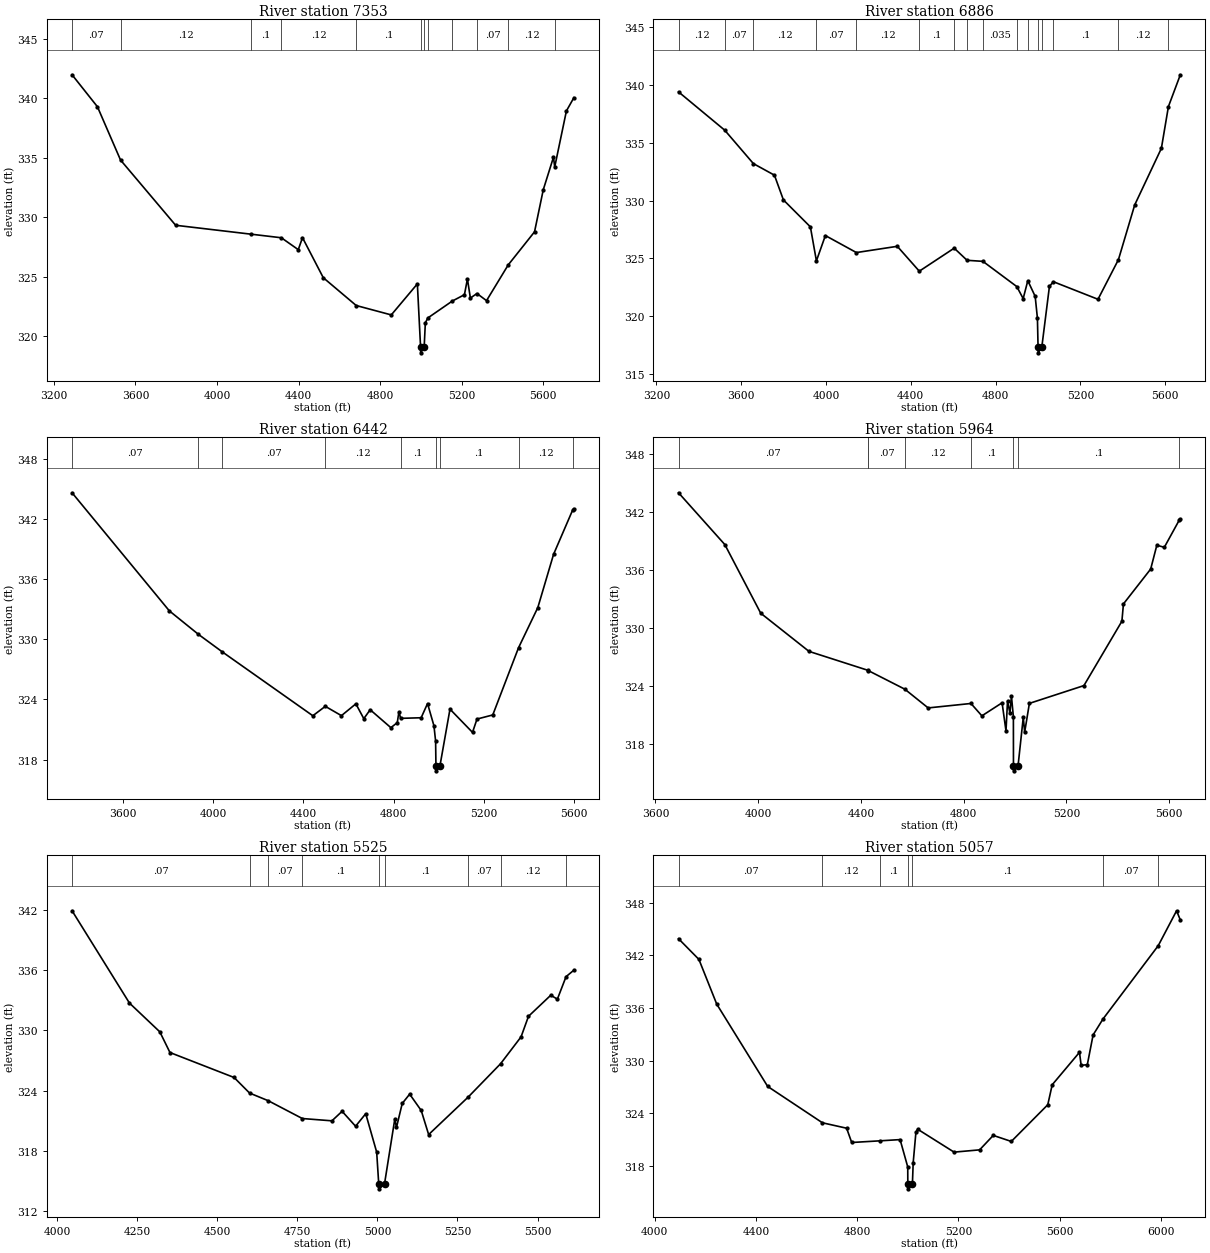
Type RM Length L Ch R = 1 ,7353    ,467,467,467
BEGIN DESCRIPTION:
Pin Oak Creek 2 11.0
END DESCRIPTION:
XS GIS Cut Line= 3
      2530974.99       13814875.        2529325.       13815325.
      2528724.96     13814874.97
#Sta/Elev= 30
  3289.2  341.97  3413.6  339.28  3526.8   334.8  3797.1  329.31  4167.4  328.56
  4315.3  328.26  4398.3  327.26    4419  328.27  4520.9   324.9  4682.4  322.56
  4854.3  321.77  4982.2  324.38  4997.9  319.08  4998.4  318.58  5015.6  319.08
  5021.3   321.1  5033.2  321.51  5153.8  322.94    5213  323.47  5227.6  324.79
  5242.2  323.19  5274.4  323.57  5321.3  322.97  5427.8  325.98  5556.7  328.76
  5599.5   332.3  5649.5  335.03  5655.7  334.22    5713  338.93  5749.5  340.04
#Mann= 12 ,-1 , 0
  3289.2     .07       0  3526.8     .12       0  4167.4      .1       0
  4315.3     .12       0  4682.4      .1       0  4997.9     .05       0
  5015.6      .1       0  5033.2    .035       0  5153.8     .12       0
  5274.4     .07       0  5427.8     .12       0  5655.7     .07       0
Bank Sta=4997.9,5015.6
XS Rating Curve= 0 ,0
Exp/Cntr=0.3,0.1

Type RM Length L Ch R = 1 ,6886    ,444,444,444
BEGIN DESCRIPTION:
Pin Oak Creek 2 10.0
END DESCRIPTION:
XS GIS Cut Line= 3
      2530574.97     13813675.03        2529375.       13814875.
      2528775.03     13814575.01
#Sta/Elev= 30
  3304.1   339.4    3522  336.09  3657.3   333.2  3756.6   332.2    3799  330.06
  3926.3  327.73  3954.7  324.79    3997  326.98  4143.4  325.51  4336.4  326.05
  4440.2   323.9  4604.9  325.89  4665.6  324.84  4740.3  324.75  4900.2  322.57
  4930.4  321.53  4952.2  323.08    4987  321.72  4997.6  319.83  5000.6  317.34
  5001.1  316.84  5018.3  317.34  5054.2  322.58  5072.7  322.99  5283.4  321.47
  5379.9   324.9  5456.7  329.63  5582.5  334.52  5615.7  338.13  5671.9  340.88
#Mann= 16 ,-1 , 0
  3304.1     .12       0    3522     .07       0  3657.3     .12       0
  3954.7     .07       0  4143.4     .12       0  4440.2      .1       0
  4604.9     .07       0  4665.6      .1       0  4740.3    .035       0
  4900.2      .1       0  4952.2    .035       0  5000.6    .035       0
  5018.3    .035       0  5072.7      .1       0  5379.9     .12       0
  5615.7     .07       0
Bank Sta=5000.6,5018.3
XS Rating Curve= 0 ,0
Exp/Cntr=0.3,0.1

Type RM Length L Ch R = 1 ,6442    ,478,478,478
BEGIN DESCRIPTION:
Pin Oak Creek 2 9.0
END DESCRIPTION:
XS GIS Cut Line= 3
      2530524.97     13813375.03        2529325.       13814475.
      2528725.04       13814475.
#Sta/Elev= 30
  3372.6  344.63  3804.5  332.84  3933.9  330.49  4038.7  328.76  4441.5  322.37
  4496.9  323.31  4568.5  322.38  4632.6  323.56  4667.8  322.08  4696.1  322.97
    4788  321.18  4816.4  321.68  4823.8  322.76  4831.4  322.11  4922.4  322.17
  4950.8  323.59  4979.2  321.37  4986.6  319.85  4988.1  317.37  4988.6  316.87
  5005.9  317.37  5050.4  323.03  5150.4  320.71  5170.4  322.04  5240.4  322.45
  5354.8  329.16  5440.4  333.17  5510.4  338.49  5595.1  342.91  5600.4  343.03
#Mann= 9 ,-1 , 0
  3372.6     .07       0  3933.9     .12       0  4038.7     .07       0
  4496.9     .12       0  4831.4      .1       0  4988.1     .05       0
  5005.9      .1       0  5354.8     .12       0  5595.1     .07       0
Bank Sta=4988.1,5005.9
XS Rating Curve= 0 ,0
Exp/Cntr=0.3,0.1

Type RM Length L Ch R = 1 ,5964    ,439,439,439
BEGIN DESCRIPTION:
Pin Oak Creek 2 8.0
END DESCRIPTION:
XS GIS Cut Line= 3
      2530424.98     13813325.01        2529325.       13814025.
      2528725.02     13814274.99
#Sta/Elev= 30
  3689.9  343.96  3870.2   338.6  4009.9   331.5  4197.9  327.55  4428.7  325.58
  4428.9  325.56  4570.9  323.64  4661.8   321.7  4828.5  322.16    4871  320.88
  4949.7  322.23  4964.9  319.32  4970.9  322.42  4980.2  321.15  4986.1  322.93
  4993.7  320.78    4994  315.69  4994.5  315.19  5011.8  315.69  5032.2  320.73
  5037.6  319.19    5056  322.17  5268.3  324.01  5416.2  330.67  5422.2  332.46
  5528.3  336.07  5552.2  338.53  5581.4  338.32  5640.1  341.16  5643.7   341.2
#Mann= 8 ,-1 , 0
  3689.9     .07       0  4428.7     .12       0  4428.9     .07       0
  4570.9     .12       0  4828.5      .1       0    4994     .05       0
  5011.8      .1       0  5640.1     .07       0
Bank Sta=4994,5011.8
XS Rating Curve= 0 ,0
Exp/Cntr=0.3,0.1

Type RM Length L Ch R = 1 ,5525    ,468,468,468
BEGIN DESCRIPTION:
Pin Oak Creek 2 7.0
END DESCRIPTION:
XS GIS Cut Line= 3
        2530325.       13813325.        2529425.       13813625.
      2528825.04     13813774.99
#Sta/Elev= 30
  4046.3  341.92  4225.5  332.72  4320.4  329.85    4352  327.79  4552.3   325.3
  4600.6  323.75  4659.3  322.98  4765.4  321.21  4857.9  320.98  4889.6  321.93
  4931.7  320.44  4963.4  321.69  4997.6  317.86    5004   314.7  5004.5   314.2
  5022.1   314.7  5054.2  321.16  5059.4  320.32  5077.4  322.71  5100.6  323.64
  5136.7  322.01  5159.9  319.61  5283.1  323.34  5384.5  326.67  5448.5  329.35
  5471.7   331.4  5541.3   333.5  5561.9  333.11    5589  335.35  5613.4     336
#Mann= 9 ,-1 , 0
  4046.3     .07       0  4600.6     .12       0  4659.3     .07       0
  4765.4      .1       0    5004     .05       0  5022.1      .1       0
  5283.1     .07       0  5384.5     .12       0    5589     .07       0
Bank Sta=5004,5022.1
XS Rating Curve= 0 ,0
Exp/Cntr=0.3,0.1

Type RM Length L Ch R = 1 ,5057    ,466,466,466
BEGIN DESCRIPTION:
Pin Oak Creek 2 6.0
END DESCRIPTION:
XS GIS Cut Line= 3
      2530375.04       13813275.        2529475.       13813175.
      2528475.01       13813575.
#Sta/Elev= 30
  4094.5  343.91    4175  341.55  4245.5  336.44  4446.7  327.05    4663   322.9
  4758.6  322.28  4778.7  320.65    4890  320.84  4969.9  320.98  5000.1  317.86
  5000.4  315.86  5000.9  315.36  5018.5  315.86  5021.6  318.33  5032.4  321.82
  5039.1  322.17  5183.2  319.55  5284.1  319.81    5338  321.46  5409.3  320.77
  5553.4  324.96  5570.9  327.24  5678.6  330.94  5685.3  329.46  5709.6  329.53
  5732.5  332.93  5771.4  334.74  5989.7  343.11  6062.3   347.1  6077.1  346.05
#Mann= 7 ,-1 , 0
  4094.5     .07       0    4663     .12       0    4890      .1       0
  5000.4     .05       0  5018.5      .1       0  5771.4     .07       0
  5989.7     .05       0
Bank Sta=5000.4,5018.5
XS Rating Curve= 0 ,0
Exp/Cntr=0.3,0.1

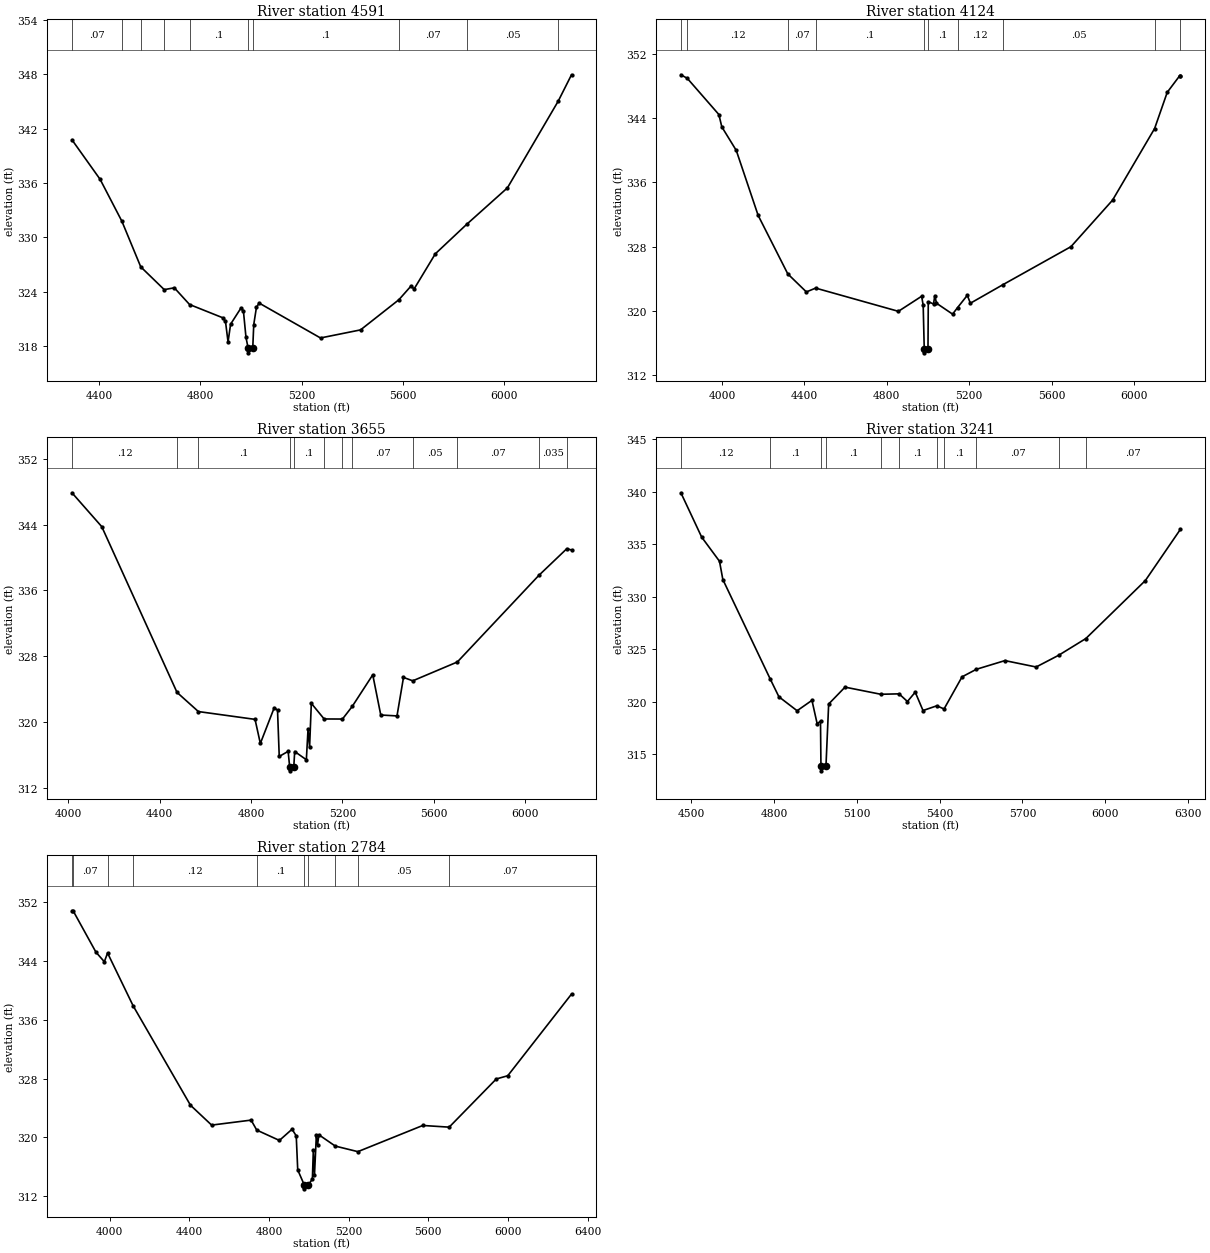
Type RM Length L Ch R = 1 ,4591    ,467,467,467
BEGIN DESCRIPTION:
Pin Oak Creek 2 5.0
END DESCRIPTION:
XS GIS Cut Line= 3
      2530225.05     13812624.99        2529525.       13812725.
      2528324.97     13813125.01
#Sta/Elev= 30
  4293.3  340.76  4404.5   336.4  4490.4  331.78  4564.9  326.75  4657.6  324.24
  4697.4  324.44  4757.5   322.6  4889.3  321.13  4899.4  320.73  4909.5  318.47
  4919.6  320.43    4960  322.19  4970.1  321.91  4980.3  318.98  4988.9  317.77
  4989.4  317.27    5007  317.77    5011  320.39  5021.5  322.27  5032.1  322.76
  5274.5  318.91  5432.6   319.8  5584.1  323.13  5632.9  324.67  5643.5  324.29
  5727.8  328.19  5851.2  331.43  6012.4  335.46  6212.9  345.02  6265.4  347.93
#Mann= 10 ,-1 , 0
  4293.3     .07       0  4490.4     .12       0  4564.9     .07       0
  4657.6     .12       0  4757.5      .1       0  4988.9     .05       0
    5007      .1       0  5584.1     .07       0  5851.2     .05       0
  6212.9    .035       0
Bank Sta=4988.9,5007
XS Rating Curve= 0 ,0
Exp/Cntr=0.3,0.1

Type RM Length L Ch R = 1 ,4124    ,469,469,469
BEGIN DESCRIPTION:
Pin Oak Creek 2 4.0
END DESCRIPTION:
XS GIS Cut Line= 3
      2530174.97     13811575.03        2529275.       13812375.
      2528274.98     13813075.02
#Sta/Elev= 30
  3800.8  349.44  3831.7     349  3985.1  344.48  3999.4  342.94  4069.6     340
  4175.8  331.89  4319.7  324.59  4409.9  322.34  4454.9  322.82  4856.5  319.92
  4969.4   321.8  4976.9  320.67    4982  315.24  4982.5  314.74  5000.2  315.24
  5001.6  321.12  5027.1  320.84  5033.3  321.88  5041.5  320.93  5119.6  319.57
  5143.6  320.38  5191.1  321.92  5205.9  320.93  5364.3  323.25  5694.2  327.99
    5896  333.79  6100.2  342.73  6161.5  347.25  6222.9  349.35  6225.6  349.35
#Mann= 10 ,-1 , 0
  3800.8     .07       0  3831.7     .12       0  4319.7     .07       0
  4454.9      .1       0    4982     .05       0  5000.2      .1       0
  5143.6     .12       0  5364.3     .05       0  6100.2    .035       0
  6222.9     .05       0
Bank Sta=4982,5000.2
XS Rating Curve= 0 ,0
Exp/Cntr=0.3,0.1

Type RM Length L Ch R = 1 ,3655    ,414,414,414
BEGIN DESCRIPTION:
Pin Oak Creek 2 3.0
END DESCRIPTION:
XS GIS Cut Line= 3
        2530075.       13811575.        2529175.       13811975.
      2528275.04     13812774.97
#Sta/Elev= 30
  4015.3  347.87  4145.9  343.75  4475.7  323.59  4569.3  321.26  4817.6  320.31
  4840.8  317.38  4901.7  321.73  4916.1  321.42  4923.6   315.8  4962.6  316.42
  4969.2  314.55  4969.7  314.05  4987.4  314.55  4991.3   316.4  5042.4   315.4
  5049.9  319.16  5056.6  316.92  5064.2  322.26  5120.3  320.36  5200.7  320.35
  5243.6  321.89  5333.4  325.73  5368.5  320.84  5439.6  320.73  5468.1  325.41
  5508.7     325  5704.1  327.29  6060.7  337.81  6183.8  341.07  6204.3  340.91
#Mann= 12 ,-1 , 0
  4015.3     .12       0  4475.7     .07       0  4569.3      .1       0
  4969.2     .05       0  4987.4      .1       0  5120.3     .07       0
  5200.7      .1       0  5243.6     .07       0  5508.7     .05       0
  5704.1     .07       0  6060.7    .035       0  6183.8     .07       0
Bank Sta=4969.2,4987.4
XS Rating Curve= 0 ,0
Exp/Cntr=0.3,0.1

Type RM Length L Ch R = 1 ,3241    ,457,457,457
BEGIN DESCRIPTION:
Pin Oak Creek 2 2.0
END DESCRIPTION:
XS GIS Cut Line= 3
      2529775.01       13811425.        2529275.       13811625.
      2528375.01     13812524.99
#Sta/Elev= 30
  4461.6  339.92    4537  335.69  4601.6  333.39  4613.7  331.65  4785.6  322.16
    4817  320.47    4883  319.14  4936.8  320.13  4955.7   317.9  4967.8  318.15
  4969.4  313.91  4969.9  313.41  4987.7  313.91  4997.4  319.78  5056.7  321.39
  5186.4  320.71  5252.7  320.75    5283  320.02  5311.3  320.91  5339.5  319.16
  5389.5  319.61  5415.8  319.31    5481  322.37  5532.8  323.09  5636.5  323.92
  5749.7  323.31  5831.5  324.43  5929.8  326.02  6145.6  331.55  6272.9  336.44
#Mann= 11 ,-1 , 0
  4461.6     .12       0  4785.6      .1       0  4969.4     .05       0
  4987.7      .1       0  5186.4     .07       0  5252.7      .1       0
  5389.5     .07       0  5415.8      .1       0  5532.8     .07       0
  5831.5     .05       0  5929.8     .07       0
Bank Sta=4969.4,4987.7
XS Rating Curve= 0 ,0
Exp/Cntr=0.3,0.1

Type RM Length L Ch R = 1 ,2784    ,0,0,0
BEGIN DESCRIPTION:
Pin Oak Creek 2 1.0
END DESCRIPTION:
XS GIS Cut Line= 3
        2529775.       13810525.        2528975.       13811425.
        2528275.       13812525.
#Sta/Elev= 30
  3810.6  350.87  3817.2  350.83    3931  345.23  3973.2  343.92  3989.4  345.11
  4117.8  337.91  4405.6  324.36  4511.8  321.65    4710  322.33  4738.4  320.97
  4852.1  319.56  4915.7  321.09  4936.6  320.18  4944.1  315.54  4977.5  313.46
    4978  312.96  4995.9  313.46  5017.7  314.29  5022.4  318.21  5028.3   314.9
  5037.6  320.24  5043.5  318.94  5050.3  320.33  5132.5  318.79    5246  318.03
  5571.9   321.6  5704.4  321.37    5941  327.94  5998.6  328.38  6318.6  339.51
#Mann= 10 ,-1 , 0
  3810.6     .05       0  3817.2     .07       0  3989.4    .035       0
  4117.8     .12       0  4738.4      .1       0  4977.5     .05       0
  4995.9      .1       0  5132.5     .07       0    5246     .05       0
  5704.4     .07       0
Bank Sta=4977.5,4995.9
XS Rating Curve= 0 ,0
Exp/Cntr=0.3,0.1

Chan Stop Cuts=-1
Use User Specified Reach Order=0
Composite Channel Slope=5