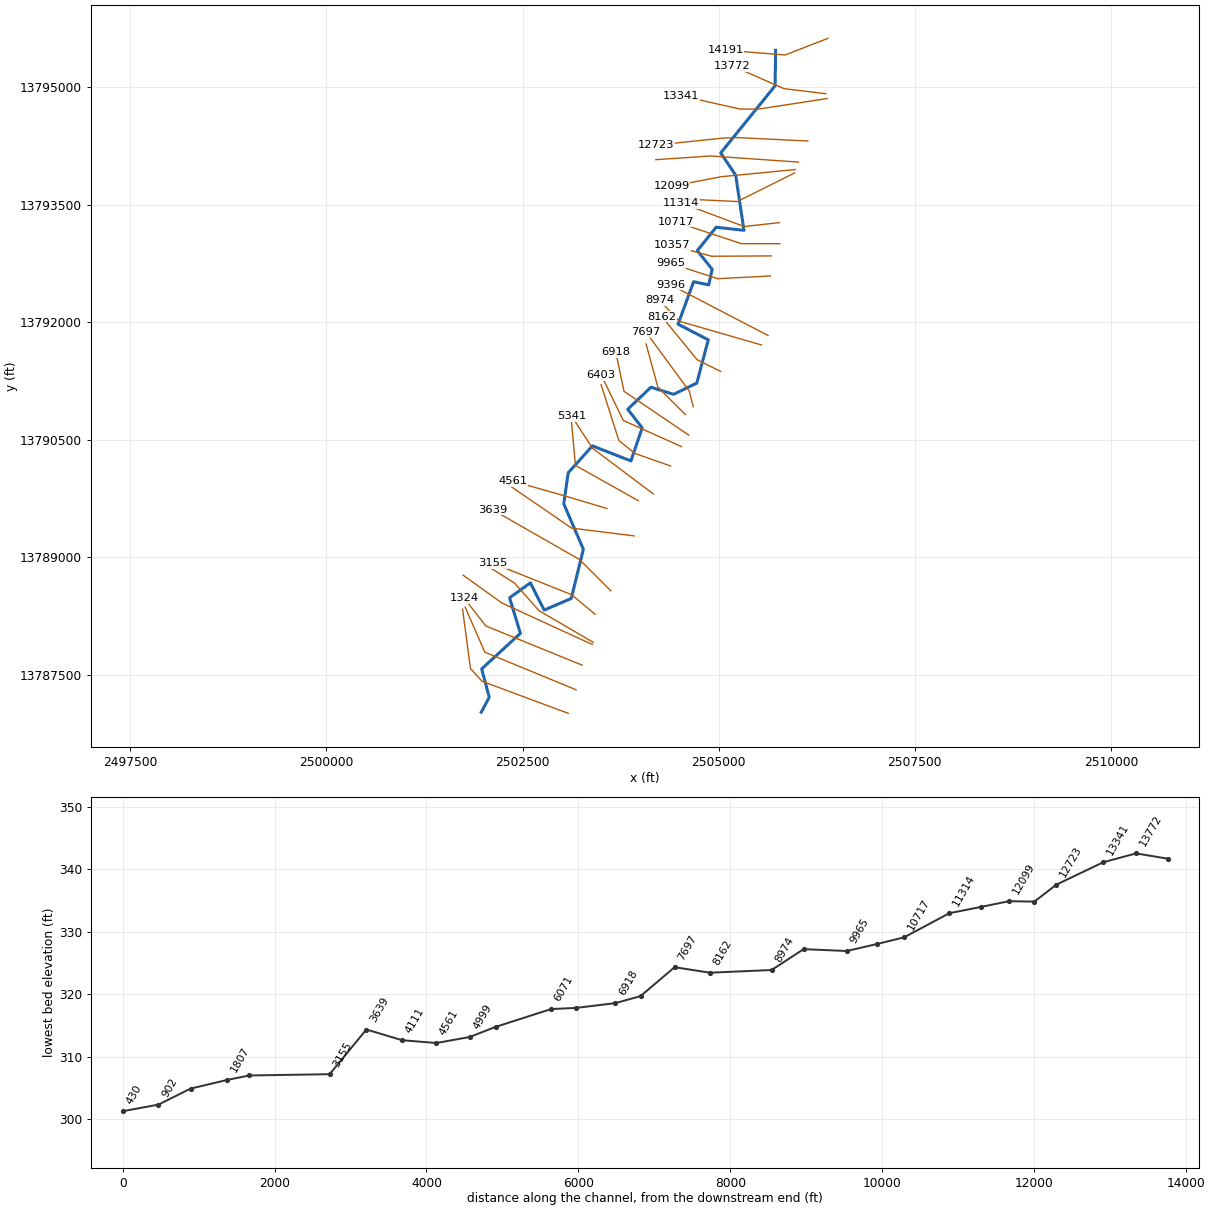
--- REED BRANCH.prj (project) ---

Proj Title=REED BRANCH Base Level Engineering
Current Plan=p01
Default Exp/Contr=0.3,0.1
English Units
Geom File=g01
Flow File=f01
Plan File=p01
BEGIN DESCRIPTION:
REED BRANCH
END DESCRIPTION:

--- REED BRANCH.p01 (plan) ---

Plan Title=Multiple Run
Short Identifier=Multiple
Geom File=g01
Flow File=f01
Subcritical Flow
K Sum by GR= 0
Std Step Tol= 0.01
Critical Tol= 0.01
Num of Std Step Trials= 20
Max Error Tol= 0.3
Flow Tol Ratio= 0.001
Split Flow NTrial= 30
Split Flow Tol= 0.02
Split Flow Ratio= 0.02
Log Output Level= 0
Friction Slope Method= 1
Unsteady Friction Slope Method= 2
Unsteady Bridges Friction Slope Method= 1
Parabolic Critical Depth
Global Vel Dist=  1 , 1 , 1
Global Log Level= 0
CheckData=True
Encroach Param= -1, 0, 0, 0
BEGIN DESCRIPTION:
Multiple Run
END DESCRIPTION:

--- REED BRANCH.f01 (steady flow) ---

Flow Title=Multiple
Number of Profiles=7
Profile Names=10-year,25-year,50-year,1pct_min,100-year,1pct_plu,500-year
River Rch & RM= REED BRANCH,Reach-1,14191
     723    1163    1559    1013    2020    4031    3357
River Rch & RM= REED BRANCH,Reach-1,13772
    1033    1685    2281    1492    2978    5941    5026
River Rch & RM= REED BRANCH,Reach-1,5341
    1161    1898    2572    1683    3359    6702    5674
Boundary for River Rch & Prof#=REED BRANCH,Reach-1,1
Up Type=0
Dn Type=3
Dn Slope=0.005
Boundary for River Rch & Prof#=REED BRANCH,Reach-1,2
Up Type=0
Dn Type=3
Dn Slope=0.005
Boundary for River Rch & Prof#=REED BRANCH,Reach-1,3
Up Type=0
Dn Type=3
Dn Slope=0.005
Boundary for River Rch & Prof#=REED BRANCH,Reach-1,4
Up Type=0
Dn Type=3
Dn Slope=0.005
Boundary for River Rch & Prof#=REED BRANCH,Reach-1,5
Up Type=0
Dn Type=3
Dn Slope=0.005
Boundary for River Rch & Prof#=REED BRANCH,Reach-1,6
Up Type=0
Dn Type=3
Dn Slope=0.005
Boundary for River Rch & Prof#=REED BRANCH,Reach-1,7
Up Type=0
Dn Type=3
Dn Slope=0.005

--- REED BRANCH.g01 (geometry) ---

Geom Title=Existing Conditions

River Reach=REED BRANCH,Reach-1
Reach XY= 30
      2505725.00     13795475.00      2505719.60     13795022.57
      2505026.08     13794164.46      2505217.28     13793878.66
      2505321.99     13793176.37      2504968.00     13793216.17
      2504727.46     13792916.83      2504917.21     13792678.42
      2504872.99     13792480.62      2504680.65     13792520.27
      2504482.52     13791978.12      2504867.24     13791778.42
      2504721.46     13791226.46      2504424.90     13791082.33
      2504136.83     13791173.38      2503841.04     13790892.04
      2504025.22     13790654.94      2503881.67     13790232.46
      2503390.88     13790424.48      2503082.81     13790081.19
      2503025.77     13789685.69      2503275.41     13789104.87
      2503121.55     13788476.25      2502776.03     13788328.46
      2502600.09     13788675.63      2502335.47     13788484.82
      2502473.18     13788031.12      2501979.97     13787577.58
      2502075.78     13787214.95      2501975.00     13787025.00

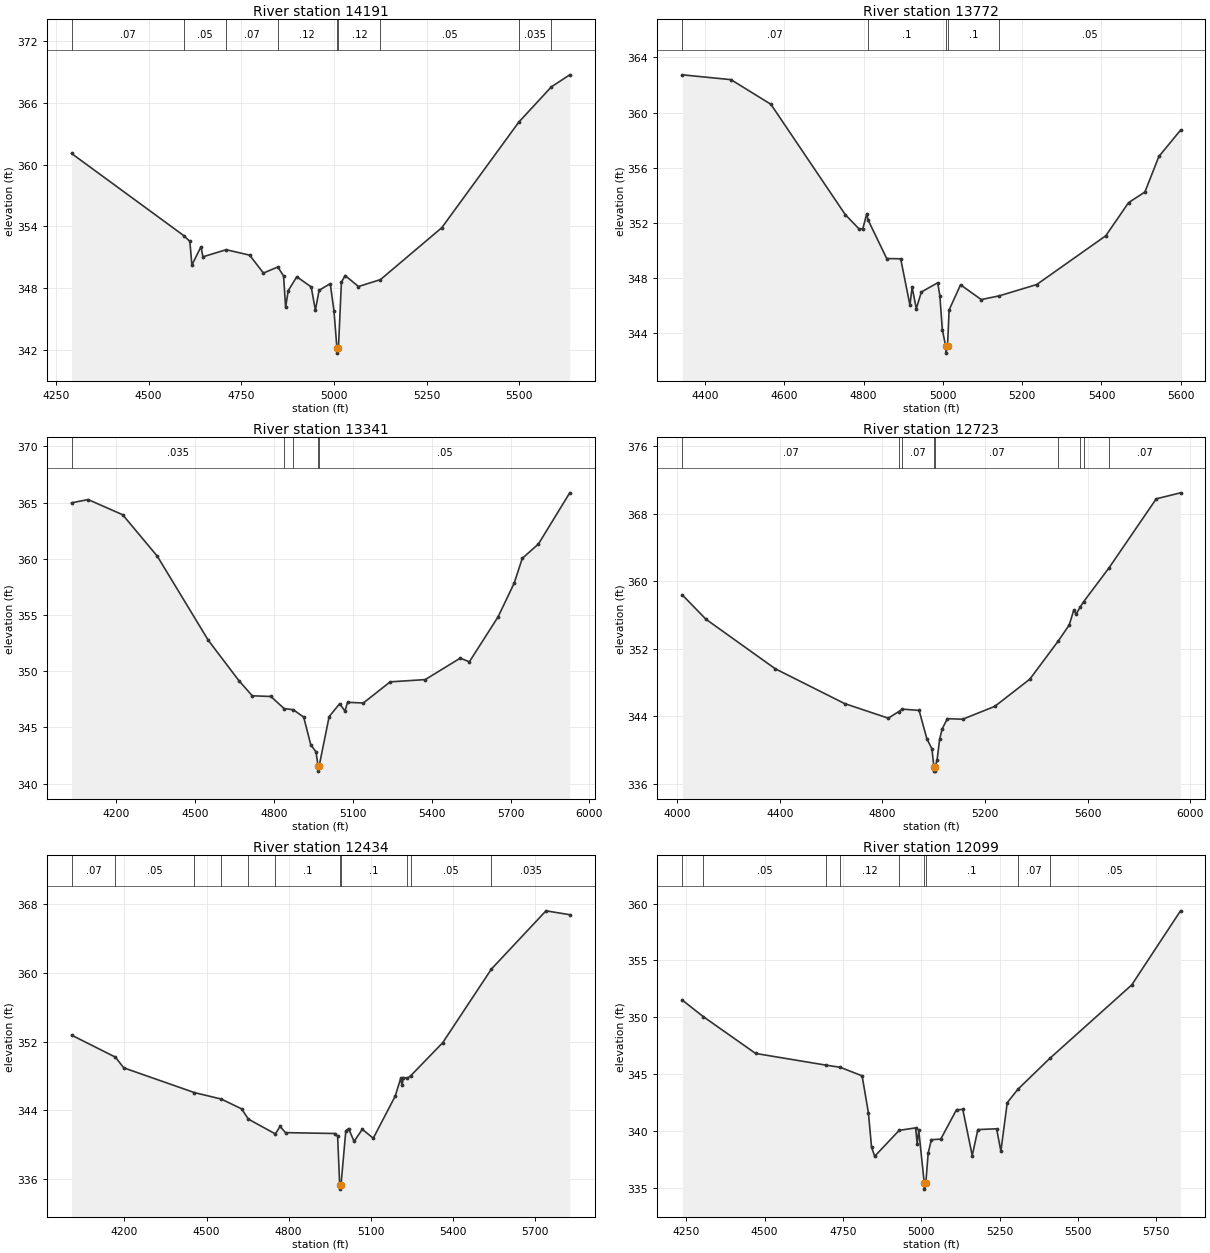
Type RM Length L Ch R = 1,14191,419,419,419
BEGIN DESCRIPTION:
REED BRANCH 22.0
END DESCRIPTION:
XS GIS Cut Line= 3
      2506392.83     13795627.57      2505845.93     13795414.89
      2505090.77     13795475.65
#Sta/Elev= 30
  4291.9  361.10  4595.5  353.09  4611.2  352.54  4616.6  350.24  4641.1  352.03
  4646.4  351.05  4709.3  351.74  4772.4  351.21  4809.7  349.47  4848.5  350.06
  4864.1  349.18  4869.5  346.13  4876.5  347.75  4899.7  349.11  4938.6  348.12
  4949.9  345.85  4959.9  347.79  4990.0  348.44  5000.0  345.80  5008.0  342.18
  5008.3  341.68  5012.1  342.18  5020.1  348.57  5030.1  349.23  5066.2  348.16
  5125.4  348.83  5291.0  353.88  5498.8  364.15  5587.0  367.59  5636.3  368.75
#Mann=9,-1,0
  4291.9    0.07       0  4595.5    0.05       0  4709.3    0.07       0
  4848.5    0.12       0  5008.0    0.05       0  5012.1    0.12       0
  5125.4    0.05       0  5498.8   0.035       0  5587.0    0.05       0
Bank Sta=5008,5012.1
Exp/Cntr=0.3,0.1

Type RM Length L Ch R = 1,13772,431,431,431
BEGIN DESCRIPTION:
REED BRANCH 21.0
END DESCRIPTION:
XS GIS Cut Line= 3
      2506366.79     13794920.09      2505832.91     13794985.20
      2505175.04     13795274.98
#Sta/Elev= 30
  4342.7  362.74  4465.4  362.39  4566.1  360.60  4753.7  352.59  4787.8  351.57
  4797.8  351.54  4807.9  352.65  4811.4  352.19  4858.3  349.40  4893.5  349.38
  4916.9  346.01  4922.3  347.33  4932.9  345.76  4945.7  346.97  4986.9  347.64
  4992.3  346.71  4998.5  344.24  5007.1  343.03  5007.5  342.53  5011.6  343.03
  5015.7  345.67  5044.5  347.49  5096.8  346.42  5142.2  346.69  5236.6  347.51
  5410.8  351.05  5468.4  353.46  5509.6  354.23  5544.8  356.81  5599.4  358.72
#Mann=5,-1,0
  4342.7    0.07       0  4811.4     0.1       0  5007.1    0.05       0
  5011.6     0.1       0  5142.2    0.05       0
Bank Sta=5007.1,5011.6
Exp/Cntr=0.3,0.1

Type RM Length L Ch R = 1,13341,618,618,618
BEGIN DESCRIPTION:
B20176
END DESCRIPTION:
XS GIS Cut Line= 4
      2506384.08     13794859.33      2505511.73     13794724.78
      2505273.01     13794724.78      2504518.90     13794893.81
#Sta/Elev= 30
  4030.7  364.98  4093.7  365.27  4225.1  363.92  4356.5  360.24  4551.0  352.74
  4667.2  349.16  4717.8  347.82  4788.6  347.76  4839.0  346.68  4874.0  346.58
  4913.4  345.92  4940.1  343.47  4960.1  342.83  4967.7  341.62  4968.1  341.12
  4972.4  341.62  5010.1  345.97  5050.1  347.12  5070.1  346.46  5080.1  347.24
  5140.1  347.18  5242.3  349.06  5375.5  349.26  5508.7  351.17  5543.1  350.84
  5652.2  354.83  5713.7  357.84  5744.4  360.04  5805.9  361.32  5924.9  365.87
#Mann=5,-1,0
  4030.7   0.035       0  4839.0     0.1       0  4874.0    0.05       0
  4967.7    0.05       0  4972.4    0.05       0
Bank Sta=4967.7,4972.4
Exp/Cntr=0.3,0.1

Type RM Length L Ch R = 1,12723,289,289,289
BEGIN DESCRIPTION:
B20175
END DESCRIPTION:
XS GIS Cut Line= 4
      2506136.71     13794316.80      2505238.29     13794360.20
      2505073.36     13794355.86      2504200.96     13794264.71
#Sta/Elev= 30
  4020.1  358.39  4111.9  355.52  4382.2  349.65  4652.5  345.53  4822.7  343.80
  4863.7  344.58  4878.1  344.87  4942.9  344.72  4972.9  341.39  4992.9  340.16
  5000.5  338.03  5000.9  337.53  5004.9  337.53  5005.2  338.03  5012.9  338.84
  5022.9  341.30  5032.9  342.54  5052.9  343.74  5113.1  343.68  5238.0  345.20
  5374.5  348.42  5485.2  352.94  5528.1  354.84  5545.4  356.57  5555.5  356.14
  5570.0  356.93  5583.9  357.58  5682.7  361.58  5867.1  369.77  5961.7  370.48
#Mann=9,-1,0
  4020.1    0.07       0  4863.7     0.1       0  4878.1    0.07       0
  5000.5    0.05       0  5005.2    0.07       0  5485.2   0.035       0
  5570.0    0.07       0  5583.9   0.035       0  5682.7    0.07       0
Bank Sta=5000.5,5005.2
Exp/Cntr=0.3,0.1

Type RM Length L Ch R = 1,12434,335,335,335
BEGIN DESCRIPTION:
B20174
END DESCRIPTION:
XS GIS Cut Line= 3
      2506015.21     13794047.70      2504895.41     13794125.83
      2504198.35     13794078.20
#Sta/Elev= 30
  4006.6  352.76  4166.7  350.20  4197.3  348.95  4455.3  346.07  4553.9  345.31
  4628.3  344.17  4652.8  342.98  4751.7  341.25  4768.7  342.13  4788.7  341.40
  4969.1  341.30  4979.2  341.00  4986.8  335.32  4987.1  334.82  4991.6  335.32
  5009.2  341.62  5019.3  341.88  5039.3  340.38  5069.4  341.79  5109.5  340.75
  5189.7  345.65  5209.7  347.71  5214.7  346.91  5219.7  347.82  5234.6  347.76
  5245.9  348.01  5363.2  351.87  5541.5  360.46  5741.0  367.24  5827.8  366.79
#Mann=11,-1,0
  4006.6    0.07       0  4166.7    0.05       0  4455.3    0.07       0
  4553.9    0.12       0  4652.8    0.07       0  4751.7     0.1       0
  4986.8    0.05       0  4991.6     0.1       0  5234.6    0.07       0
  5245.9    0.05       0  5541.5   0.035       0
Bank Sta=4986.8,4991.6
Exp/Cntr=0.3,0.1

Type RM Length L Ch R = 1,12099,363,363,363
BEGIN DESCRIPTION:
B20173
END DESCRIPTION:
XS GIS Cut Line= 3
      2505976.09     13793952.21      2505034.30     13793861.07
      2504401.82     13793739.77
#Sta/Elev= 30
  4237.6  351.51  4304.9  350.05  4471.5  346.82  4696.2  345.79  4741.7  345.60
  4811.4  344.85  4831.5  341.61  4841.5  338.59  4851.5  337.77  4929.7  340.05
  4982.2  340.27  4987.2  338.89  4992.2  340.06  5009.9  335.38  5010.2  334.88
  5014.7  335.38  5022.3  338.04  5032.4  339.23  5062.5  339.28  5112.8  341.87
  5132.9  341.89  5163.0  337.83  5180.9  340.12  5240.8  340.19  5254.4  338.22
  5274.7  342.49  5309.1  343.68  5410.3  346.38  5672.1  352.85  5827.8  359.37
#Mann=9,-1,0
  4237.6    0.07       0  4304.9    0.05       0  4696.2    0.07       0
  4741.7    0.12       0  4929.7     0.1       0  5009.9    0.05       0
  5014.7     0.1       0  5309.1    0.07       0  5410.3    0.05       0
Bank Sta=5009.9,5014.7
Exp/Cntr=0.3,0.1

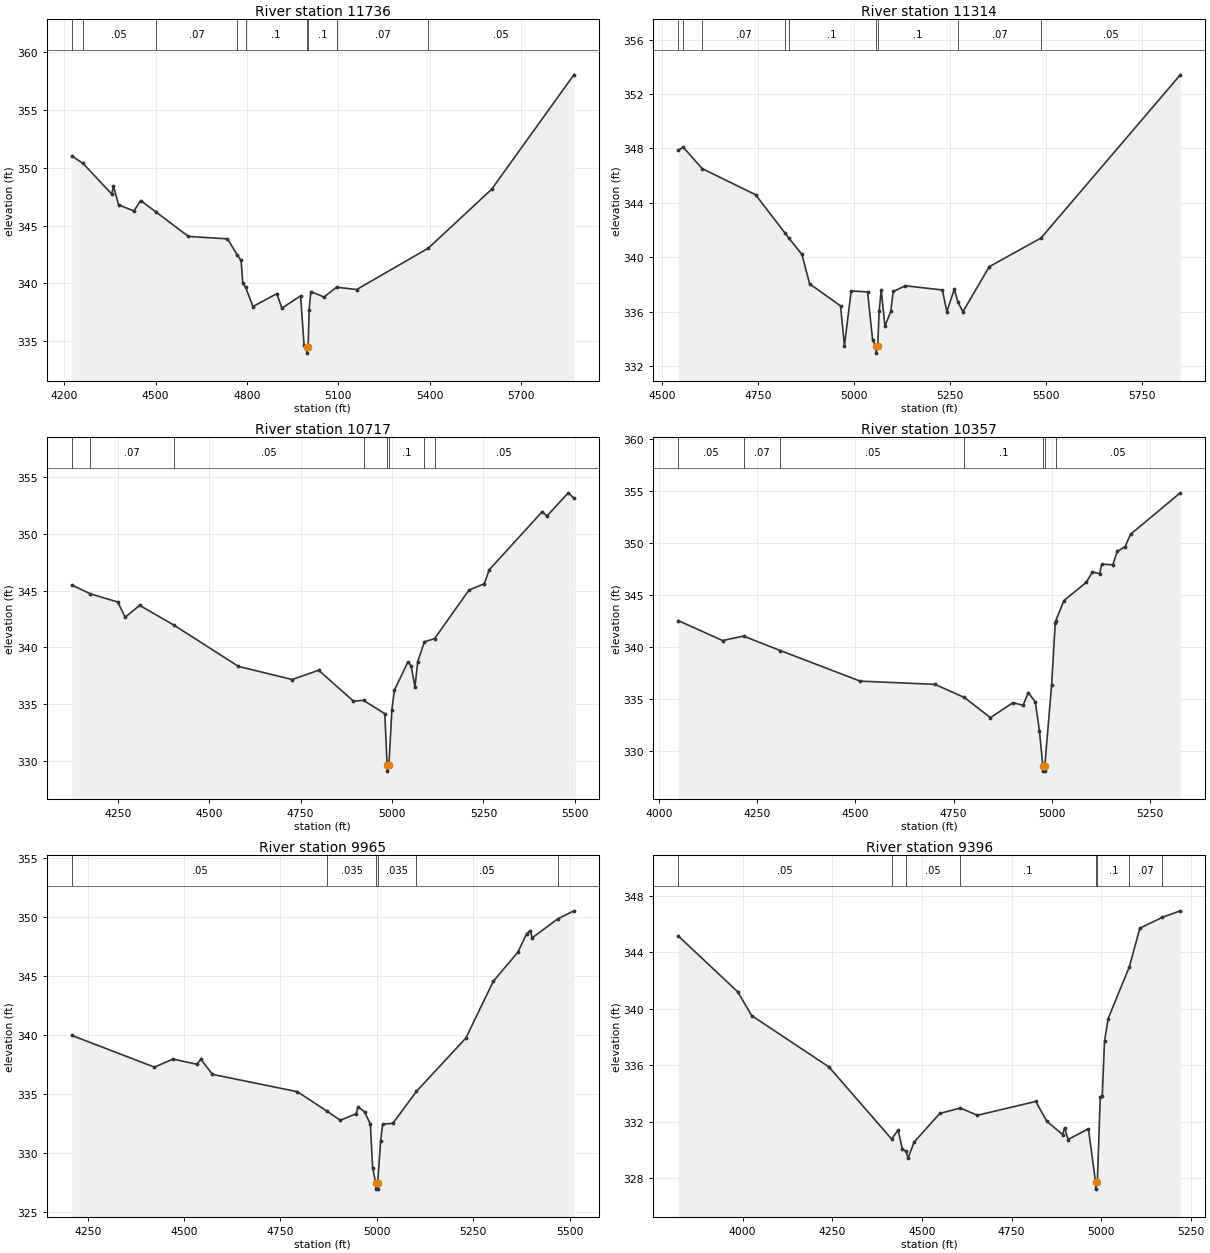
Type RM Length L Ch R = 1,11736,422,422,422
BEGIN DESCRIPTION:
B20172
END DESCRIPTION:
XS GIS Cut Line= 3
      2505967.42     13793908.79      2505238.29     13793544.23
      2504404.99     13793583.29
#Sta/Elev= 30
  4224.4  351.02  4261.2  350.39  4355.8  347.73  4361.4  348.44  4378.1  346.80
  4428.4  346.27  4450.8  347.17  4499.8  346.21  4607.3  344.07  4735.9  343.86
  4768.1  342.47  4780.6  341.99  4786.2  340.02  4795.4  339.66  4819.7  338.01
  4898.0  339.12  4914.8  337.87  4976.2  338.93  4987.5  334.68  4996.1  334.48
  4996.5  333.98  5000.9  334.48  5004.2  337.74  5009.8  339.30  5052.9  338.83
  5094.1  339.68  5160.4  339.48  5395.4  343.05  5603.5  348.14  5873.8  358.04
#Mann=9,-1,0
  4224.4    0.07       0  4261.2    0.05       0  4499.8    0.07       0
  4768.1    0.12       0  4795.4     0.1       0  4996.1    0.05       0
  5000.9     0.1       0  5094.1    0.07       0  5395.4    0.05       0
Bank Sta=4996.1,5000.9
Exp/Cntr=0.3,0.1

Type RM Length L Ch R = 1,11314,597,597,597
BEGIN DESCRIPTION:
REED BRANCH 17.0
END DESCRIPTION:
XS GIS Cut Line= 3
      2505775.03     13793275.00      2505325.00     13793225.00
      2504525.00     13793525.00
#Sta/Elev= 30
  4542.0  347.87  4555.0  348.09  4604.3  346.52  4743.3  344.60  4819.9  341.79
  4829.2  341.44  4864.0  340.21  4884.1  338.05  4964.6  336.43  4974.7  333.51
  4992.3  337.53  5034.9  337.46  5048.2  333.91  5056.4  333.46  5056.8  332.96
  5061.3  333.46  5065.1  336.05  5070.5  337.60  5080.2  334.94  5095.4  336.03
  5101.6  337.49  5133.6  337.91  5229.8  337.60  5241.3  336.01  5260.9  337.66
  5269.7  336.75  5283.2  336.00  5351.7  339.31  5486.6  341.42  5849.2  353.41
#Mann=9,-1,0
  4542.0    0.07       0  4555.0    0.05       0  4604.3    0.07       0
  4819.9    0.05       0  4829.2     0.1       0  5056.4    0.05       0
  5061.3     0.1       0  5269.7    0.07       0  5486.6    0.05       0
Bank Sta=5056.4,5061.3
Exp/Cntr=0.3,0.1

Type RM Length L Ch R = 1,10717,360,360,360
BEGIN DESCRIPTION:
B20171
END DESCRIPTION:
XS GIS Cut Line= 3
      2505780.84     13793006.03      2505290.37     13793006.03
      2504452.69     13793283.81
#Sta/Elev= 30
  4124.2  345.51  4175.1  344.73  4250.0  344.01  4270.0  342.67  4310.0  343.71
  4403.1  341.98  4580.0  338.33  4726.8  337.17  4799.4  337.99  4894.2  335.27
  4922.0  335.33  4980.3  334.16  4986.6  329.59  4987.0  329.09  4991.5  329.59
  4999.6  334.52  5006.7  336.25  5043.6  338.73  5052.3  338.36  5062.8  336.53
  5070.1  338.73  5088.6  340.50  5116.5  340.78  5210.3  345.06  5252.5  345.62
  5265.5  346.84  5410.5  351.97  5423.9  351.60  5482.0  353.64  5497.2  353.17
#Mann=8,-1,0
  4124.2    0.05       0  4175.1    0.07       0  4403.1    0.05       0
  4922.0     0.1       0  4986.6    0.05       0  4991.5     0.1       0
  5088.6    0.07       0  5116.5    0.05       0
Bank Sta=4986.6,4991.5
Exp/Cntr=0.3,0.1

Type RM Length L Ch R = 1,10357,392,392,392
BEGIN DESCRIPTION:
B20170
END DESCRIPTION:
XS GIS Cut Line= 3
      2505667.93     13792849.78      2504908.43     13792845.44
      2504409.70     13792984.22
#Sta/Elev= 30
  4049.4  342.52  4162.3  340.60  4215.5  341.03  4309.4  339.63  4512.3  336.69
  4702.3  336.38  4777.0  335.12  4843.6  333.17  4900.6  334.61  4926.7  334.37
  4940.0  335.59  4957.8  334.67  4968.2  331.92  4976.9  328.52  4977.3  328.02
  4981.5  328.02  4981.9  328.52  4999.3  336.36  5008.5  342.32  5009.9  342.51
  5030.5  344.45  5087.3  346.20  5103.1  347.20  5121.5  347.04  5126.7  347.96
  5155.0  347.90  5166.1  349.18  5186.2  349.65  5200.3  350.85  5326.6  354.83
#Mann=7,-1,0
  4049.4    0.05       0  4215.5    0.07       0  4309.4    0.05       0
  4777.0     0.1       0  4976.9    0.05       0  4981.9     0.1       0
  5009.9    0.05       0
Bank Sta=4976.9,4981.9
Exp/Cntr=0.3,0.1

Type RM Length L Ch R = 1,9965,569,569,569
BEGIN DESCRIPTION:
B20169
END DESCRIPTION:
XS GIS Cut Line= 3
      2505659.32     13792593.71      2504986.55     13792558.99
      2504388.79     13792753.91
#Sta/Elev= 30
  4208.8  339.94  4423.4  337.25  4471.6  337.94  4533.5  337.49  4543.6  337.92
  4573.6  336.64  4793.9  335.17  4871.8  333.50  4905.1  332.75  4946.1  333.29
  4951.4  333.89  4968.2  333.47  4983.3  332.42  4989.3  328.72  4997.3  327.41
  4997.7  326.91  5001.9  326.91  5002.3  327.41  5009.9  330.95  5015.2  332.42
  5041.8  332.49  5103.0  335.20  5231.2  339.72  5302.3  344.53  5366.1  347.00
  5389.0  348.57  5398.0  348.82  5403.3  348.21  5469.0  349.81  5511.2  350.50
#Mann=6,-1,0
  4208.8    0.05       0  4871.8   0.035       0  4997.3   0.035       0
  5002.3   0.035       0  5103.0    0.05       0  5469.0   0.035       0
Bank Sta=4997.3,5002.3
Exp/Cntr=0.3,0.1

Type RM Length L Ch R = 1,9396,422,422,422
BEGIN DESCRIPTION:
B20168
END DESCRIPTION:
XS GIS Cut Line= 2
      2505628.95     13791834.14      2504387.61     13792480.85
#Sta/Elev= 30
  3820.7  345.17  3986.8  341.20  4025.3  339.52  4240.7  335.88  4415.4  330.77
  4433.9  331.40  4445.3  330.06  4455.7  329.88  4461.6  329.42  4478.1  330.54
  4550.0  332.58  4607.0  332.96  4654.9  332.45  4817.4  333.43  4848.1  332.03
  4892.3  331.08  4897.9  331.57  4907.6  330.73  4964.2  331.49  4984.1  327.71
  4984.5  327.21  4989.1  327.71  4997.2  333.74  5002.8  333.79  5009.1  337.70
  5019.3  339.31  5078.3  342.98  5107.6  345.72  5170.4  346.49  5220.4  346.95
#Mann=8,-1,0
  3820.7    0.05       0  4415.4   0.035       0  4455.7    0.05       0
  4607.0     0.1       0  4984.1    0.05       0  4989.1     0.1       0
  5078.3    0.07       0  5170.4    0.05       0
Bank Sta=4984.1,4989.1
Exp/Cntr=0.3,0.1

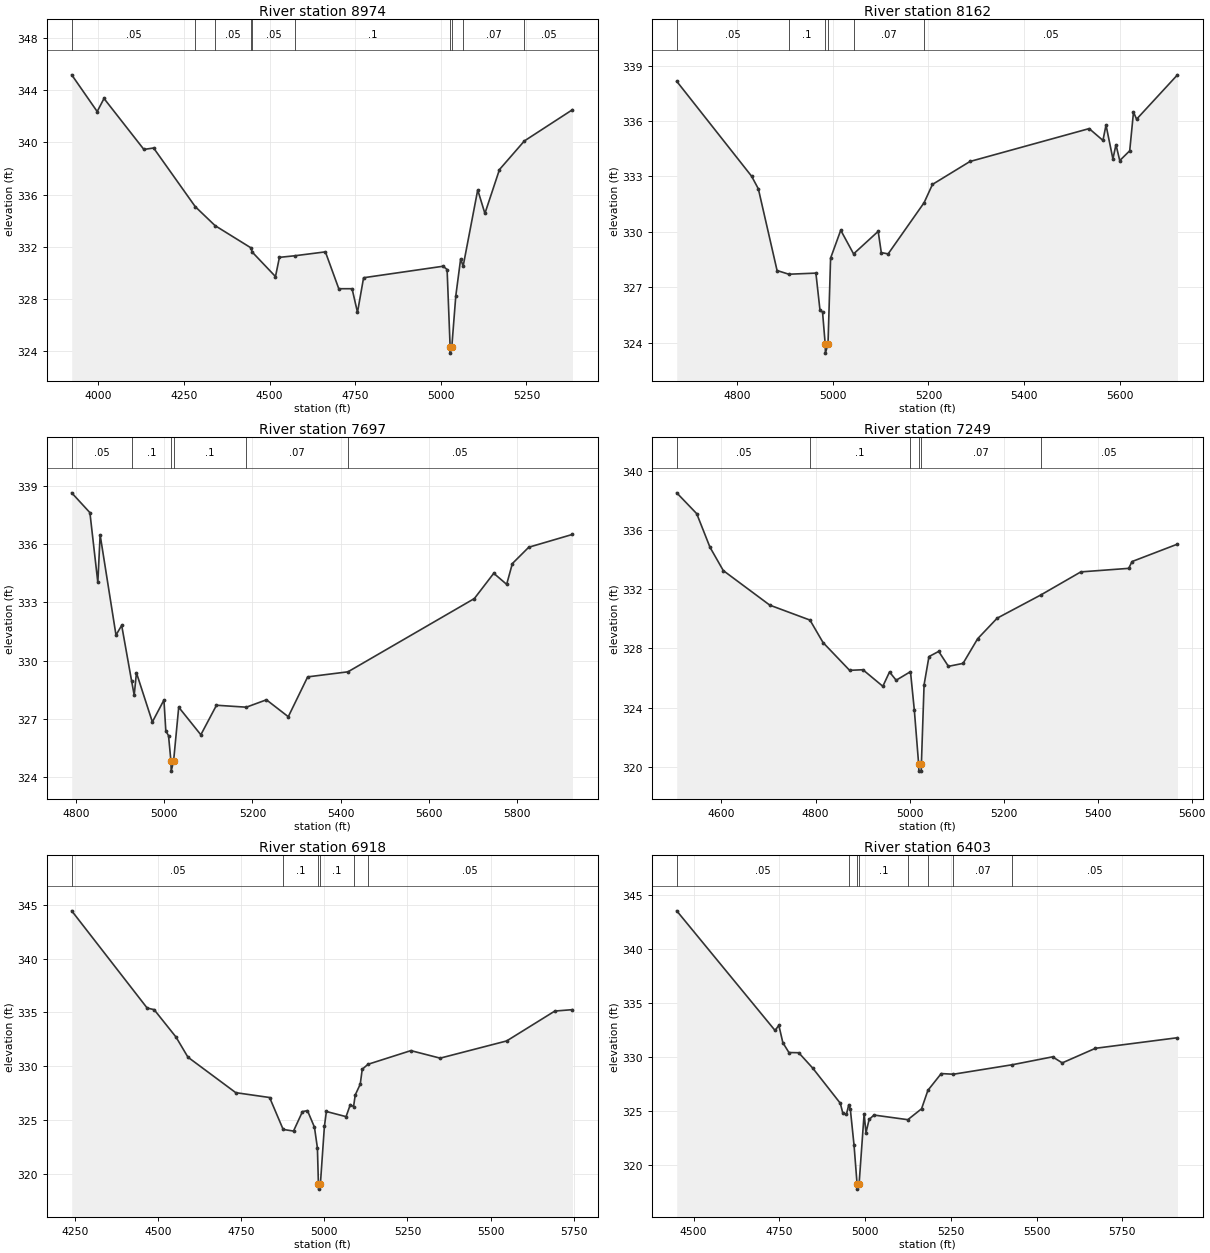
Type RM Length L Ch R = 1,8974,812,812,812
BEGIN DESCRIPTION:
B20167
END DESCRIPTION:
XS GIS Cut Line= 3
      2505546.46     13791712.63      2504496.10     13792016.45
      2504244.37     13792285.54
#Sta/Elev= 30
  3922.5  345.17  3996.9  342.36  4016.8  343.36  4133.2  339.46  4161.6  339.57
  4283.2  335.08  4341.0  333.63  4445.0  331.94  4450.0  331.59  4517.4  329.73
  4528.9  331.20  4573.2  331.32  4663.1  331.62  4702.2  328.80  4741.0  328.80
  4756.8  326.99  4774.6  329.64  5006.7  330.52  5018.4  330.27  5027.2  324.37
  5027.5  323.87  5032.2  324.37  5043.8  328.25  5058.0  331.09  5065.2  330.52
  5107.8  336.36  5128.8  334.56  5171.3  337.92  5244.0  340.11  5384.4  342.50
#Mann=10,-1,0
  3922.5    0.05       0  4283.2   0.035       0  4341.0    0.05       0
  4445.0   0.035       0  4450.0    0.05       0  4573.2     0.1       0
  5027.2    0.05       0  5032.2     0.1       0  5065.2    0.07       0
  5244.0    0.05       0
Bank Sta=5027.2,5032.2
Exp/Cntr=0.3,0.1

Type RM Length L Ch R = 1,8162,465,465,465
BEGIN DESCRIPTION:
REED BRANCH 13.0
END DESCRIPTION:
XS GIS Cut Line= 3
      2505024.98     13791375.01      2504725.00     13791525.00
      2504275.02     13792074.98
#Sta/Elev= 30
  4674.1  338.15  4830.6  333.01  4844.6  332.33  4883.7  327.91  4908.3  327.71
  4964.8  327.77  4973.2  325.80  4978.7  325.66  4984.2  323.94  4984.7  323.44
  4990.1  323.94  4995.5  328.58  5016.7  330.09  5043.5  328.81  5094.9  330.03
  5101.4  328.88  5115.7  328.81  5190.8  331.58  5208.3  332.57  5286.6  333.81
  5535.6  335.59  5564.4  334.95  5570.8  335.78  5585.2  333.95  5591.6  334.72
  5599.5  333.86  5620.3  334.39  5628.2  336.48  5634.7  336.10  5720.1  338.50
#Mann=6,-1,0
  4674.1    0.05       0  4908.3     0.1       0  4984.2    0.05       0
  4990.1     0.1       0  5043.5    0.07       0  5190.8    0.05       0
Bank Sta=4984.2,4990.1
Exp/Cntr=0.3,0.1

Type RM Length L Ch R = 1,7697,448,448,448
BEGIN DESCRIPTION:
REED BRANCH 12.0
END DESCRIPTION:
XS GIS Cut Line= 3
      2504675.01     13790924.96      2504625.00     13791125.00
      2504075.03     13791874.96
#Sta/Elev= 30
  4789.8  338.64  4831.1  337.62  4849.1  334.03  4854.3  336.48  4890.3  331.32
  4903.2  331.82  4925.7  328.96  4931.6  328.23  4936.7  329.38  4972.8  326.85
  4999.1  327.98  5003.3  326.40  5009.5  326.14  5015.0  324.82  5015.5  324.32
  5020.9  324.82  5032.6  327.61  5082.8  326.19  5118.3  327.71  5186.0  327.61
  5231.6  327.99  5281.2  327.12  5325.2  329.17  5416.6  329.43  5703.4  333.20
  5747.4  334.50  5776.7  333.93  5789.6  335.00  5826.8  335.84  5926.0  336.50
#Mann=6,-1,0
  4789.8    0.05       0  4925.7     0.1       0  5015.0    0.05       0
  5020.9     0.1       0  5186.0    0.07       0  5416.6    0.05       0
Bank Sta=5015,5020.9
Exp/Cntr=0.3,0.1

Type RM Length L Ch R = 1,7249,331,331,331
BEGIN DESCRIPTION:
REED BRANCH 11.0
END DESCRIPTION:
XS GIS Cut Line= 3
      2504575.02     13790824.98      2504225.00     13791175.00
      2504075.00     13791725.01
#Sta/Elev= 30
  4504.8  338.53  4547.3  337.12  4575.5  334.85  4603.8  333.27  4702.8  330.93
  4788.2  329.92  4816.0  328.40  4872.5  326.52  4900.8  326.56  4943.2  325.44
  4957.4  326.41  4971.5  325.85  5002.0  326.43  5010.2  323.82  5019.3  320.20
  5019.8  319.70  5024.8  319.70  5025.2  320.20  5030.9  325.54  5041.3  327.45
  5062.0  327.80  5082.7  326.79  5113.8  326.99  5144.9  328.66  5186.4  330.05
  5279.8  331.63  5364.3  333.18  5466.2  333.42  5473.2  333.88  5569.9  335.06
#Mann=6,-1,0
  4504.8    0.05       0  4788.2     0.1       0  5002.0    0.07       0
  5019.3    0.05       0  5025.2    0.07       0  5279.8    0.05       0
Bank Sta=5019.3,5025.2
Exp/Cntr=0.3,0.1

Type RM Length L Ch R = 1,6918,515,515,515
BEGIN DESCRIPTION:
B20166
END DESCRIPTION:
XS GIS Cut Line= 3
      2504617.61     13790562.47      2503792.98     13791122.35
      2503688.96     13791620.78
#Sta/Elev= 30
  4240.5  344.45  4467.4  335.41  4488.4  335.26  4554.2  332.71  4590.1  330.84
  4733.9  327.54  4835.6  327.09  4876.4  324.12  4907.5  323.97  4934.5  325.78
  4949.5  325.87  4970.5  324.33  4979.4  322.40  4982.4  319.07  4982.9  318.57
  4988.4  319.07  5000.4  324.40  5006.4  325.79  5065.6  325.31  5078.3  326.43
  5088.1  326.24  5093.2  327.33  5108.2  328.33  5114.2  329.72  5131.6  330.18
  5260.4  331.45  5348.5  330.75  5548.5  332.35  5693.4  335.13  5746.4  335.26
#Mann=6,-1,0
  4240.5    0.05       0  4876.4     0.1       0  4982.4    0.05       0
  4988.4     0.1       0  5088.1    0.07       0  5131.6    0.05       0
Bank Sta=4982.4,4988.4
Exp/Cntr=0.3,0.1

Type RM Length L Ch R = 1,6403,332,332,332
BEGIN DESCRIPTION:
B20165
END DESCRIPTION:
XS GIS Cut Line= 3
      2504526.44     13790414.91      2503784.30     13790749.09
      2503502.36     13791330.31
#Sta/Elev= 30
  4450.9  343.58  4737.6  332.50  4748.6  332.98  4760.3  331.37  4778.0  330.46
  4806.6  330.44  4847.3  329.02  4927.8  325.76  4935.0  324.86  4945.5  324.73
  4952.6  325.63  4957.0  325.22  4967.9  321.86  4976.6  318.31  4977.1  317.81
  4982.6  318.31  4997.2  324.78  5002.7  323.04  5011.8  324.26  5025.9  324.67
  5124.6  324.24  5164.7  325.25  5183.2  326.96  5222.0  328.51  5257.7  328.45
  5429.6  329.33  5546.6  330.06  5574.8  329.50  5671.5  330.85  5910.8  331.83
#Mann=8,-1,0
  4450.9    0.05       0  4952.6     0.1       0  4976.6    0.05       0
  4982.6     0.1       0  5124.6    0.07       0  5183.2     0.1       0
  5257.7    0.07       0  5429.6    0.05       0
Bank Sta=4976.6,4982.6
Exp/Cntr=0.3,0.1

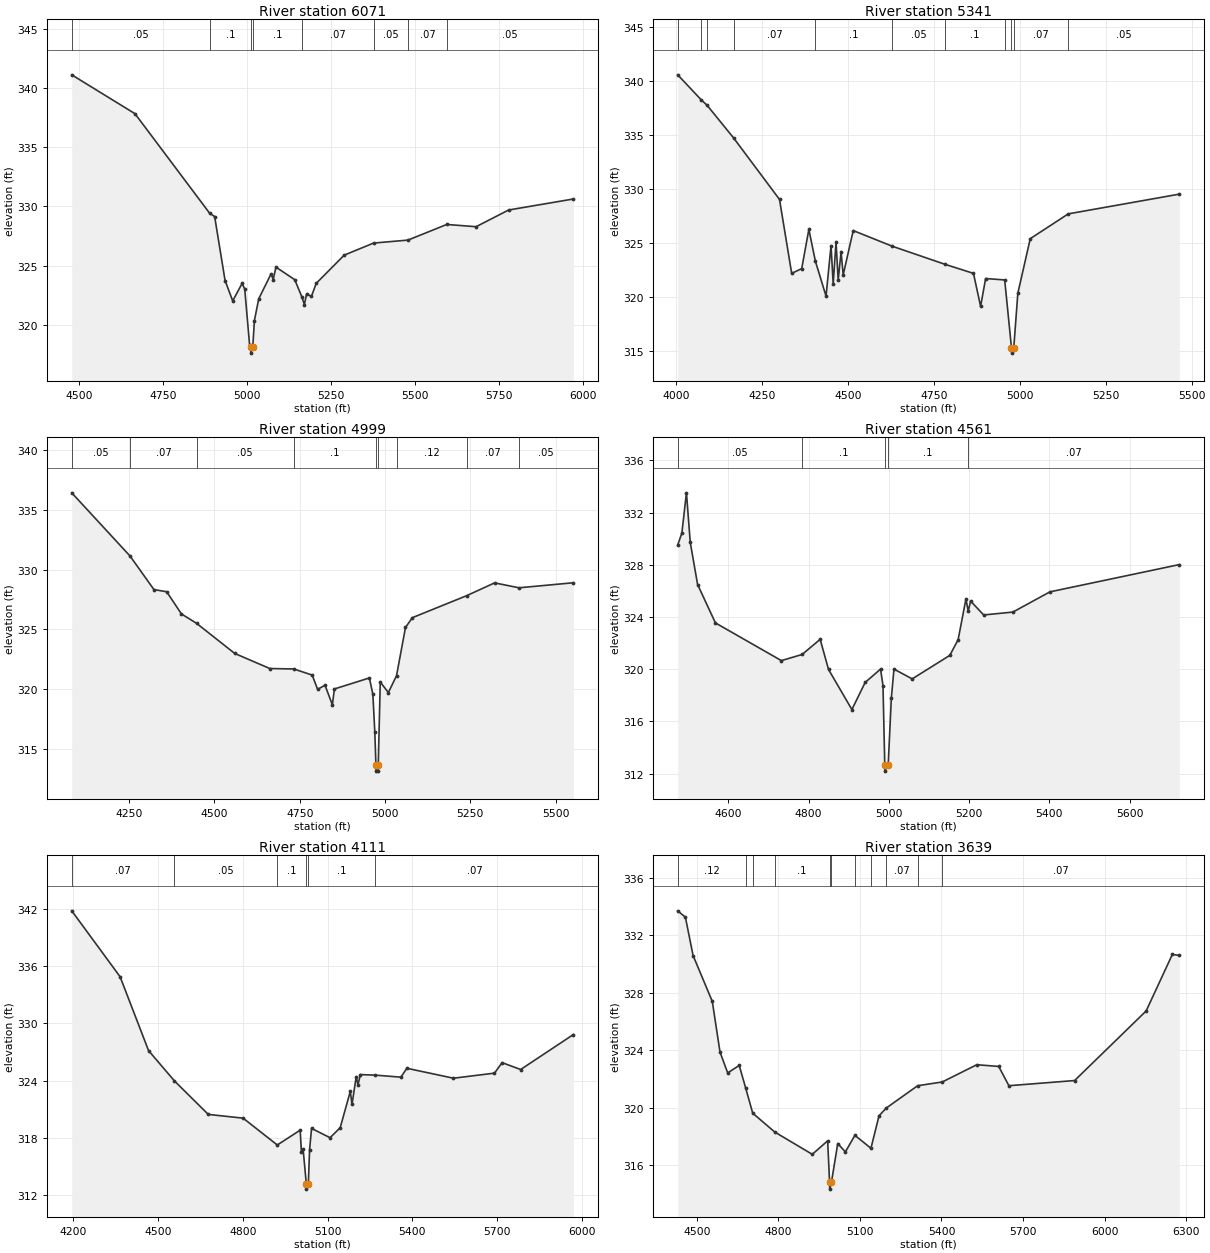
Type RM Length L Ch R = 1,6071,730,730,730
BEGIN DESCRIPTION:
B20164
END DESCRIPTION:
XS GIS Cut Line= 4
      2504387.56     13790167.51      2503931.87     13790328.08
      2503727.87     13790493.01      2503502.18     13791204.81
#Sta/Elev= 30
  4478.4  341.11  4666.5  337.83  4889.1  329.41  4903.5  329.15  4934.5  323.75
  4957.2  322.03  4985.1  323.50  4993.0  323.04  5007.4  318.33  5010.9  318.12
  5011.4  317.62  5016.9  318.12  5021.8  320.37  5034.7  322.21  5071.4  324.31
  5077.8  323.83  5085.8  324.88  5141.8  323.82  5162.6  322.39  5170.5  321.72
  5177.0  322.61  5191.4  322.41  5205.7  323.51  5288.9  325.89  5376.3  326.91
  5478.6  327.16  5594.0  328.48  5681.2  328.29  5778.0  329.70  5970.6  330.63
#Mann=8,-1,0
  4478.4    0.05       0  4889.1     0.1       0  5010.9    0.05       0
  5016.9     0.1       0  5162.6    0.07       0  5376.3    0.05       0
  5478.6    0.07       0  5594.0    0.05       0
Bank Sta=5010.9,5016.9
Exp/Cntr=0.3,0.1

Type RM Length L Ch R = 1,5341,342,342,342
BEGIN DESCRIPTION:
B20163
END DESCRIPTION:
XS GIS Cut Line= 3
      2504166.27     13789811.57      2503393.67     13790393.19
      2503124.59     13790805.49
#Sta/Elev= 30
  4004.8  340.59  4073.3  338.27  4089.9  337.78  4167.8  334.72  4301.0  329.03
  4336.4  322.17  4365.6  322.61  4386.4  326.25  4405.3  323.31  4436.4  320.06
  4450.9  324.74  4457.2  321.21  4465.5  325.07  4471.8  321.55  4480.1  324.18
  4486.3  322.03  4515.5  326.14  4629.7  324.68  4783.5  323.00  4865.3  322.17
  4886.1  319.11  4900.7  321.69  4956.2  321.56  4975.9  315.27  4976.4  314.77
  4982.6  315.27  4994.4  320.32  5030.6  325.39  5141.1  327.69  5464.2  329.52
#Mann=11,-1,0
  4004.8    0.12       0  4073.3    0.07       0  4089.9    0.12       0
  4167.8    0.07       0  4405.3     0.1       0  4629.7    0.05       0
  4783.5     0.1       0  4956.2    0.07       0  4975.9    0.05       0
  4982.6    0.07       0  5141.1    0.05       0
Bank Sta=4975.9,4982.6
Exp/Cntr=0.3,0.1

Type RM Length L Ch R = 1,4999,438,438,438
BEGIN DESCRIPTION:
REED BRANCH 8.0
END DESCRIPTION:
XS GIS Cut Line= 3
      2503975.00     13789725.00      2503175.00     13790175.00
      2503125.00     13790724.96
#Sta/Elev= 30
  4081.8  336.42  4252.8  331.13  4322.7  328.33  4360.0  328.15  4403.4  326.29
  4447.6  325.51  4559.5  322.99  4662.2  321.73  4732.7  321.69  4786.5  321.18
  4802.4  319.99  4824.1  320.33  4845.7  318.69  4851.5  320.02  4954.1  320.94
  4964.3  319.58  4970.0  316.43  4973.3  313.65  4973.8  313.15  4979.6  313.15
  4980.1  313.65  4986.0  320.60  5009.7  319.72  5033.7  321.13  5059.9  325.16
  5080.0  325.98  5239.2  327.82  5321.0  328.89  5392.7  328.48  5551.9  328.90
#Mann=9,-1,0
  4081.8    0.05       0  4252.8    0.07       0  4447.6    0.05       0
  4732.7     0.1       0  4973.3    0.05       0  4980.1     0.1       0
  5033.7    0.12       0  5239.2    0.07       0  5392.7    0.05       0
Bank Sta=4973.3,4980.1
Exp/Cntr=0.3,0.1

Type RM Length L Ch R = 1,4561,450,450,450
BEGIN DESCRIPTION:
REED BRANCH 7.0
END DESCRIPTION:
XS GIS Cut Line= 3
      2503575.01     13789625.00      2503075.00     13789775.00
      2502375.03     13789974.99
#Sta/Elev= 30
  4473.8  329.51  4484.2  330.44  4495.6  333.52  4505.1  329.72  4523.4  326.49
  4567.8  323.55  4732.2  320.66  4783.8  321.13  4828.8  322.29  4849.7  319.98
  4907.9  316.91  4941.0  318.99  4979.3  320.01  4985.4  318.74  4989.8  312.69
  4990.3  312.19  4996.7  312.69  4998.4  312.69  5006.2  317.78  5012.7  320.01
  5058.2  319.26  5151.8  321.06  5172.6  322.26  5192.1  325.38  5197.8  324.46
  5203.8  325.22  5236.3  324.16  5309.1  324.38  5401.4  325.93  5723.8  328.02
#Mann=5,-1,0
  4473.8    0.05       0  4783.8     0.1       0  4989.8    0.05       0
  4996.7     0.1       0  5197.8    0.07       0
Bank Sta=4989.8,4996.7
Exp/Cntr=0.3,0.1

Type RM Length L Ch R = 1,4111,472,472,472
BEGIN DESCRIPTION:
REED BRANCH 6.0
END DESCRIPTION:
XS GIS Cut Line= 3
      2503924.96     13789275.01      2503125.00     13789375.00
      2502325.00     13789925.00
#Sta/Elev= 30
  4193.8  341.76  4365.1  334.86  4465.9  327.13  4557.5  323.96  4677.5  320.45
  4800.9  320.06  4922.0  317.25  5003.0  318.80  5007.4  316.56  5013.5  316.81
  5024.9  313.13  5025.4  312.63  5031.9  313.13  5036.4  316.76  5043.3  318.99
  5108.9  318.01  5144.8  319.06  5180.6  322.86  5186.7  321.51  5201.6  324.40
  5207.7  323.54  5216.5  324.62  5269.8  324.56  5359.9  324.35  5380.9  325.28
  5546.1  324.24  5691.4  324.77  5718.4  325.87  5784.1  325.15  5970.8  328.81
#Mann=6,-1,0
  4193.8    0.07       0  4557.5    0.05       0  4922.0     0.1       0
  5024.9    0.05       0  5031.9     0.1       0  5269.8    0.07       0
Bank Sta=5024.9,5031.9
Exp/Cntr=0.3,0.1

Type RM Length L Ch R = 1,3639,484,484,484
BEGIN DESCRIPTION:
REED BRANCH 5.0
END DESCRIPTION:
XS GIS Cut Line= 3
      2503625.00     13788575.00      2503225.00     13788975.00
      2502114.97     13789610.97
#Sta/Elev= 30
  4429.7  333.70  4458.0  333.26  4486.3  330.59  4557.0  327.40  4585.3  323.88
  4613.6  322.43  4656.0  322.95  4679.7  321.38  4705.7  319.63  4786.7  318.32
  4924.7  316.77  4981.3  317.71  4988.3  314.85  4988.8  314.35  4995.4  314.85
  5018.4  317.52  5046.5  316.94  5081.5  318.09  5140.5  317.19  5170.2  319.45
  5196.9  319.99  5312.3  321.54  5402.8  321.80  5529.9  323.00  5610.5  322.88
  5647.9  321.54  5889.6  321.90  6152.8  326.74  6249.2  330.67  6274.7  330.60
#Mann=11,-1,0
  4429.7    0.12       0  4679.7     0.1       0  4705.7    0.05       0
  4786.7     0.1       0  4988.3    0.05       0  4995.4     0.1       0
  5081.5    0.07       0  5140.5    0.05       0  5196.9    0.07       0
  5312.3    0.05       0  5402.8    0.07       0
Bank Sta=4988.3,4995.4
Exp/Cntr=0.3,0.1

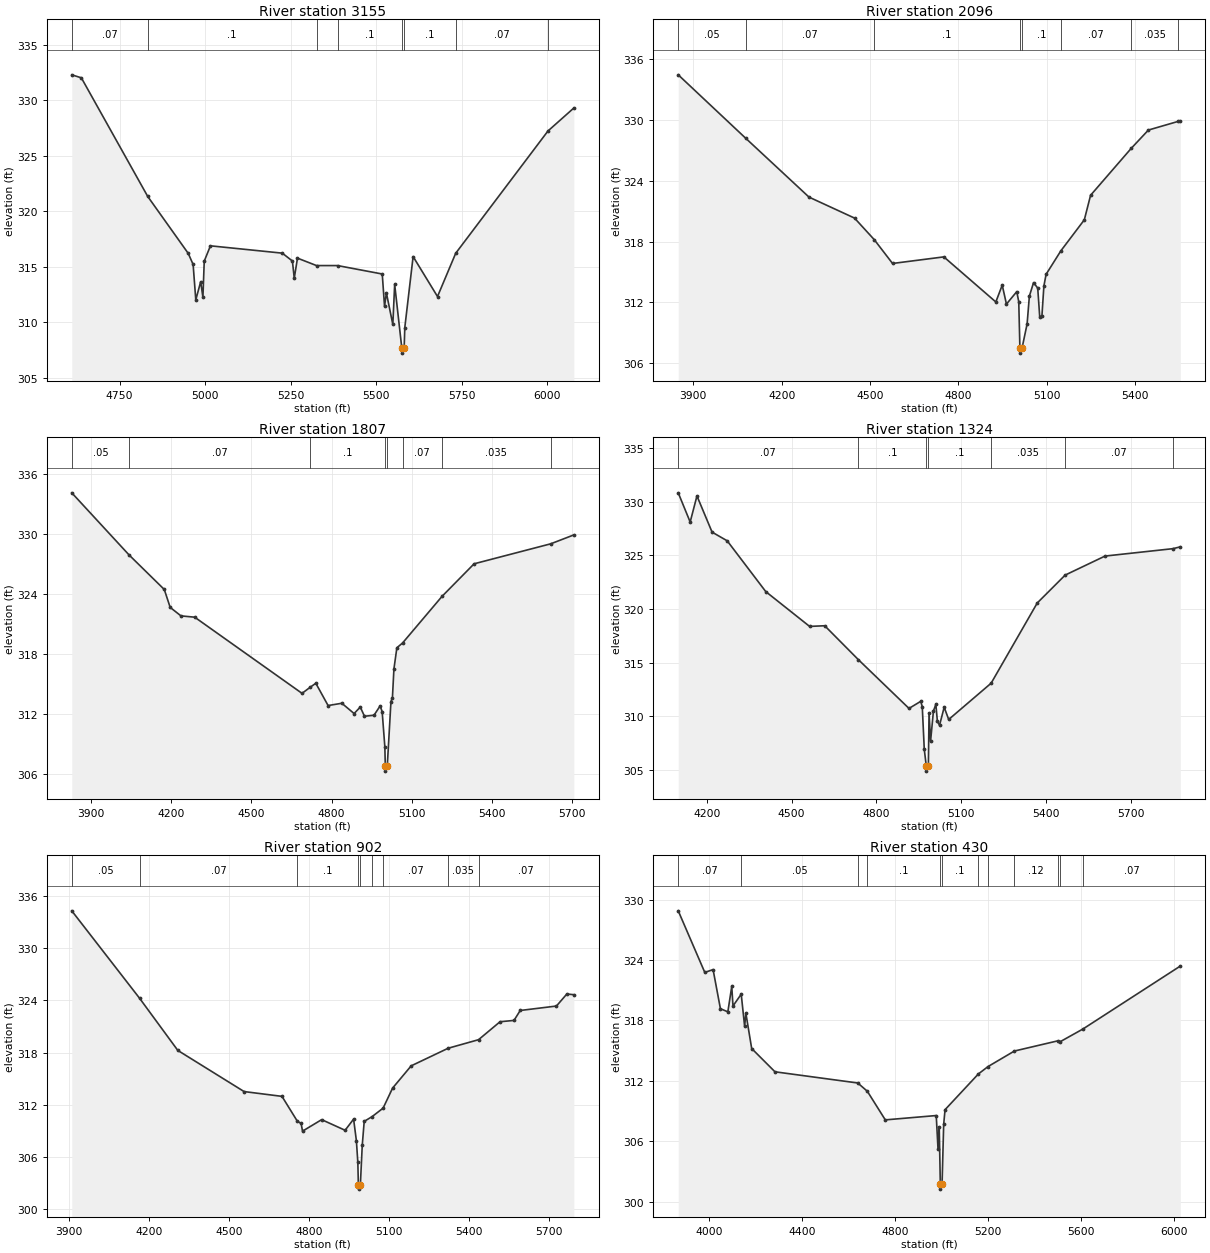
Type RM Length L Ch R = 1,3155,1059,1059,1059
BEGIN DESCRIPTION:
REED BRANCH 4.0
END DESCRIPTION:
XS GIS Cut Line= 3
      2503424.98     13788275.02      2503125.00     13788525.00
      2502125.01     13788924.99
#Sta/Elev= 30
  4610.1  332.28  4638.1  332.01  4832.1  321.32  4950.5  316.19  4964.8  315.19
  4972.6  312.00  4986.9  313.64  4993.4  312.23  4997.3  315.49  5015.4  316.87
  5225.4  316.21  5255.0  315.50  5260.4  313.95  5269.8  315.76  5325.5  315.09
  5387.0  315.09  5517.6  314.33  5524.3  311.41  5529.7  312.63  5548.5  309.78
  5553.9  313.39  5574.6  307.70  5575.1  307.20  5581.7  307.70  5583.5  309.50
  5607.8  315.90  5679.1  312.30  5732.3  316.20  6002.0  327.22  6077.6  329.29
#Mann=8,-1,0
  4610.1    0.07       0  4832.1     0.1       0  5325.5    0.05       0
  5387.0     0.1       0  5574.6    0.05       0  5581.7     0.1       0
  5732.3    0.07       0  6002.0   0.035       0
Bank Sta=5574.6,5581.7
Exp/Cntr=0.3,0.1

Type RM Length L Ch R = 1,2096,289,289,289
BEGIN DESCRIPTION:
B20162
END DESCRIPTION:
XS GIS Cut Line= 4
      2503402.85     13787915.58      2502709.63     13788321.37
      2502398.54     13788673.03      2502033.36     13788902.96
#Sta/Elev= 30
  3848.8  334.46  4078.2  328.19  4292.7  322.39  4447.2  320.32  4514.2  318.19
  4576.3  315.84  4750.4  316.49  4926.9  312.04  4948.6  313.70  4962.9  311.83
  4998.0  313.06  5004.7  312.06  5008.6  307.49  5009.1  306.99  5015.9  307.49
  5033.1  309.88  5040.7  312.61  5054.9  313.95  5069.1  313.41  5075.8  310.60
  5083.3  310.64  5090.0  313.61  5097.5  314.77  5147.7  317.09  5227.3  320.15
  5248.5  322.57  5386.4  327.20  5444.8  329.01  5545.4  329.86  5553.1  329.89
#Mann=8,-1,0
  3848.8    0.05       0  4078.2    0.07       0  4514.2     0.1       0
  5008.6    0.05       0  5015.9     0.1       0  5147.7    0.07       0
  5386.4   0.035       0  5545.4    0.07       0
Bank Sta=5008.6,5015.9
Exp/Cntr=0.3,0.1

Type RM Length L Ch R = 1,1807,483,483,483
BEGIN DESCRIPTION:
B20161
END DESCRIPTION:
XS GIS Cut Line= 3
      2503389.32     13787888.54      2502236.24     13788419.43
      2501742.57     13788774.46
#Sta/Elev= 30
  3828.1  334.12  4042.2  327.91  4174.1  324.45  4196.1  322.66  4236.4  321.81
  4287.8  321.68  4689.2  314.06  4718.6  314.65  4740.7  315.07  4786.6  312.84
  4838.0  313.07  4883.9  312.04  4906.9  312.69  4922.7  311.77  4958.3  311.87
  4981.3  312.81  4988.8  312.23  4998.8  308.73  5000.6  306.78  5001.1  306.28
  5007.9  306.78  5021.7  313.24  5027.2  313.63  5032.8  316.50  5043.8  318.62
  5065.2  319.10  5212.6  323.76  5332.6  327.02  5619.2  329.02  5705.6  329.91
#Mann=8,-1,0
  3828.1    0.05       0  4042.2    0.07       0  4718.6     0.1       0
  5000.6    0.05       0  5007.9     0.1       0  5065.2    0.07       0
  5212.6   0.035       0  5619.2    0.07       0
Bank Sta=5000.6,5007.9
Exp/Cntr=0.3,0.1

Type RM Length L Ch R = 1,1324,422,422,422
BEGIN DESCRIPTION:
B20160
END DESCRIPTION:
XS GIS Cut Line= 3
      2503260.80     13787624.81      2502033.36     13788125.25
      2501756.22     13788480.12
#Sta/Elev= 30
  4099.0  330.81  4141.2  328.09  4165.2  330.52  4218.7  327.15  4272.2  326.34
  4408.6  321.61  4563.6  318.37  4617.1  318.43  4735.8  315.28  4915.2  310.73
  4956.7  311.39  4962.1  310.90  4969.2  306.93  4976.2  305.39  4976.7  304.89
  4983.7  305.39  4986.1  310.33  4991.5  307.67  5001.6  310.49  5010.2  311.11
  5015.6  309.53  5023.2  309.16  5039.6  310.84  5055.6  309.70  5205.7  313.08
  5368.8  320.55  5467.6  323.15  5608.5  324.92  5848.9  325.61  5874.8  325.78
#Mann=7,-1,0
  4099.0    0.07       0  4735.8     0.1       0  4976.2    0.05       0
  4983.7     0.1       0  5205.7   0.035       0  5467.6    0.07       0
  5848.9   0.035       0
Bank Sta=4976.2,4983.7
Exp/Cntr=0.3,0.1

Type RM Length L Ch R = 1,902,472,472,472
BEGIN DESCRIPTION:
B20159
END DESCRIPTION:
XS GIS Cut Line= 3
      2503182.98     13787310.36      2502019.83     13787790.50
      2501769.80     13788364.89
#Sta/Elev= 30
  3909.5  334.25  4164.1  324.22  4307.6  318.24  4556.4  313.52  4698.6  312.97
  4756.5  310.11  4770.4  309.87  4775.8  308.98  4847.6  310.30  4935.6  309.08
  4967.5  310.36  4978.0  307.88  4983.4  305.39  4985.4  302.83  4985.9  302.33
  4992.9  302.83  5000.0  307.37  5007.3  310.10  5037.1  310.65  5078.3  311.62
  5113.9  313.92  5183.7  316.47  5322.5  318.49  5436.6  319.47  5517.3  321.53
  5569.6  321.68  5593.0  322.82  5729.0  323.33  5768.0  324.71  5794.3  324.63
#Mann=9,-1,0
  3909.5    0.05       0  4164.1    0.07       0  4756.5     0.1       0
  4985.4    0.05       0  4992.9     0.1       0  5037.1    0.12       0
  5078.3    0.07       0  5322.5   0.035       0  5436.6    0.07       0
Bank Sta=4985.4,4992.9
Exp/Cntr=0.3,0.1

Type RM Length L Ch R = 1,430,0,0,0
BEGIN DESCRIPTION:
B20158
END DESCRIPTION:
XS GIS Cut Line= 4
      2503084.98     13787009.39      2501986.02     13787418.54
      2501837.24     13787580.85      2501735.91     13788340.79
#Sta/Elev= 30
  3869.0  328.88  3983.2  322.77  4018.9  323.05  4050.4  319.17  4082.4  318.86
  4099.2  321.38  4104.5  319.44  4139.9  320.61  4154.6  317.42  4159.9  318.72
  4184.9  315.22  4285.1  312.91  4641.2  311.80  4682.3  310.98  4759.6  308.14
  4978.7  308.57  4986.3  305.29  4991.6  307.46  4996.3  301.77  4996.8  301.27
  5003.8  301.77  5010.7  307.69  5016.6  309.15  5160.1  312.70  5201.5  313.43
  5314.9  314.97  5503.2  315.99  5512.9  315.91  5609.3  317.15  6028.5  323.40
#Mann=12,-1,0
  3869.0    0.07       0  4139.9    0.05       0  4641.2    0.07       0
  4682.3     0.1       0  4996.3    0.05       0  5003.8     0.1       0
  5160.1    0.12       0  5201.5    0.07       0  5314.9    0.12       0
  5503.2    0.07       0  5512.9    0.12       0  5609.3    0.07       0
Bank Sta=4996.3,5003.8
Exp/Cntr=0.3,0.1

Chan Stop Cuts=-1