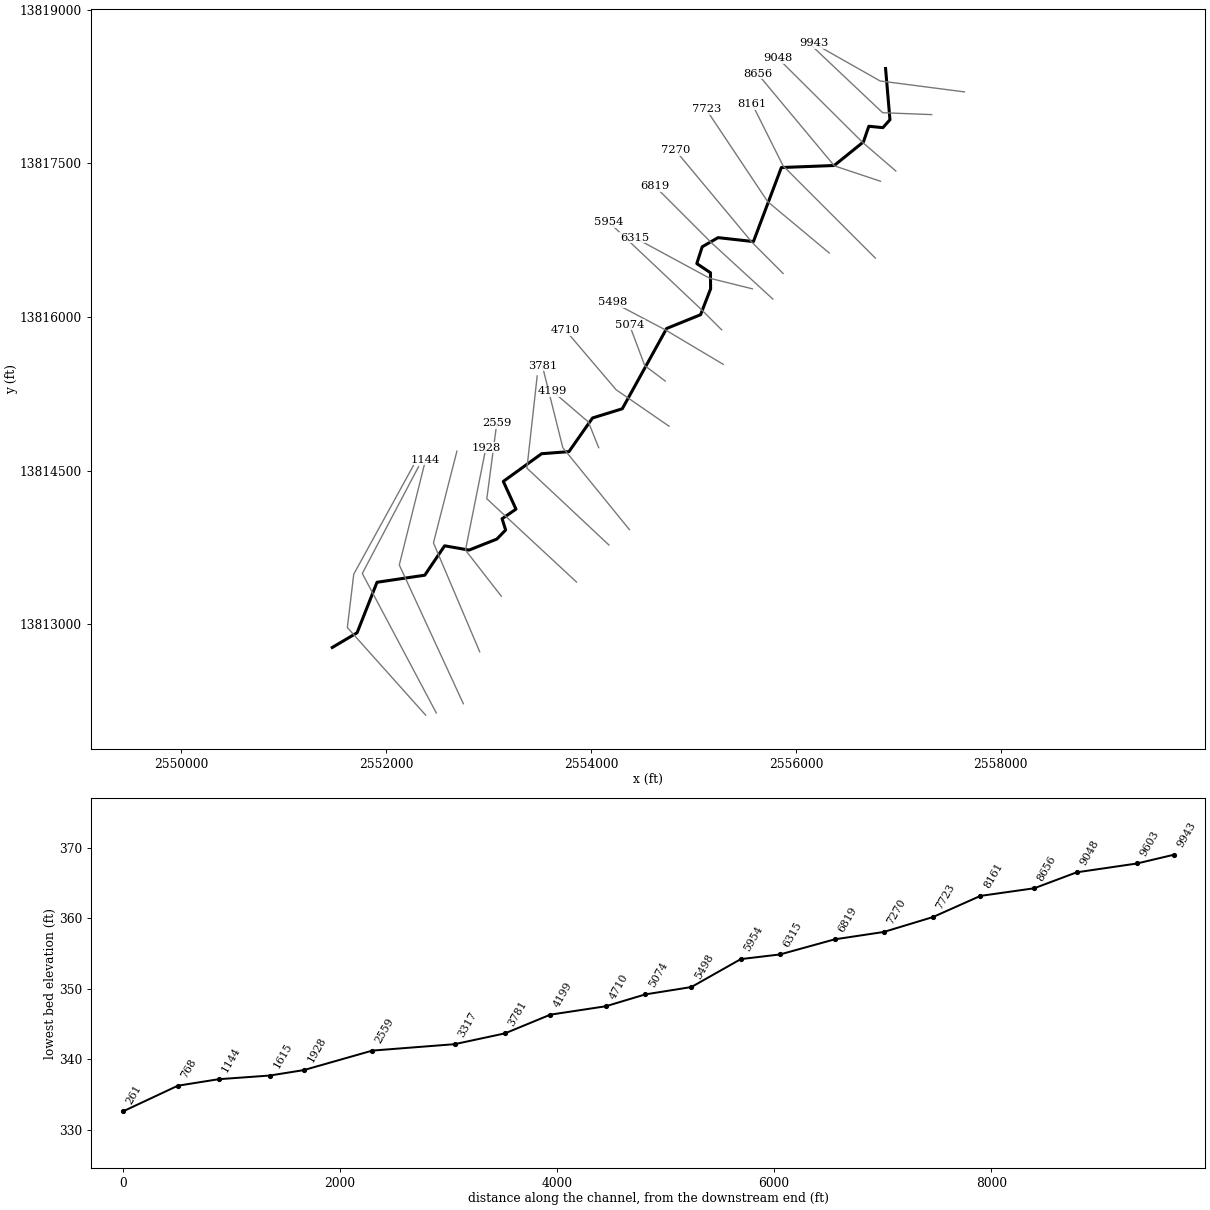
--- Rocky Creek 4.prj (project) ---

Proj Title=Rocky Creek 4 Base Level Engineering
Current Plan=p01
Default Exp/Contr=0.3,0.1
English Units
Geom File=g01
Flow File=f01
Plan File=p01
BEGIN DESCRIPTION:
Rocky Creek 4
END DESCRIPTION:

--- Rocky Creek 4.p01 (plan) ---

Plan Title=Multiple Run
Short Identifier=Multiple
Geom File=g01
Flow File=f01
Subcritical Flow
K Sum by GR= 0
Std Step Tol= 0.01
Critical Tol= 0.01
Num of Std Step Trials= 20
Max Error Tol= 0.3
Flow Tol Ratio= 0.001
Split Flow NTrial= 30
Split Flow Tol= 0.02
Split Flow Ratio= 0.02
Log Output Level= 0
Friction Slope Method= 1
Unsteady Friction Slope Method= 2
Unsteady Bridges Friction Slope Method= 1
Parabolic Critical Depth
Global Vel Dist=  1 , 1 , 1
Global Log Level= 0
CheckData=True
Encroach Param= -1, 0, 0, 0
BEGIN DESCRIPTION:
Multiple Run
END DESCRIPTION:

--- Rocky Creek 4.f01 (steady flow) ---

Flow Title=Multiple
Number of Profiles=7
Profile Names=10-year,25-year,50-year,1pct_min,100-year,1pct_plu,500-year
River Rch & RM= Rocky Creek 4,Reach-1,9943
     491     764    1003     638    1273    2540    2026
River Rch & RM= Rocky Creek 4,Reach-1,7270
     705    1119    1486     955    1905    3800    3097
Boundary for River Rch & Prof#=Rocky Creek 4,Reach-1,1
Up Type=0
Dn Type=3
Dn Slope=0.005
Boundary for River Rch & Prof#=Rocky Creek 4,Reach-1,2
Up Type=0
Dn Type=3
Dn Slope=0.005
Boundary for River Rch & Prof#=Rocky Creek 4,Reach-1,3
Up Type=0
Dn Type=3
Dn Slope=0.005
Boundary for River Rch & Prof#=Rocky Creek 4,Reach-1,4
Up Type=0
Dn Type=3
Dn Slope=0.005
Boundary for River Rch & Prof#=Rocky Creek 4,Reach-1,5
Up Type=0
Dn Type=3
Dn Slope=0.005
Boundary for River Rch & Prof#=Rocky Creek 4,Reach-1,6
Up Type=0
Dn Type=3
Dn Slope=0.005
Boundary for River Rch & Prof#=Rocky Creek 4,Reach-1,7
Up Type=0
Dn Type=3
Dn Slope=0.005

--- Rocky Creek 4.g01 (geometry) ---

Geom Title=Existing Conditions

River Reach=Rocky Creek 4,Reach-1
Reach XY= 30
      2556875.00     13818425.00      2556917.69     13817924.89
      2556848.57     13817847.71      2556711.57     13817861.46
      2556658.62     13817708.30      2556373.75     13817478.45
      2555857.86     13817458.73      2555585.32     13816736.10
      2555240.22     13816774.51      2555085.38     13816685.11
      2555032.69     13816521.33      2555165.97     13816432.01
      2555167.44     13816275.00      2555069.60     13816022.29
      2554738.61     13815888.24      2554305.53     13815104.46
      2554014.88     13815014.65      2553785.00     13814686.24
      2553518.27     13814665.85      2553144.27     13814395.47
      2553268.07     13814124.99      2553132.39     13814031.33
      2553167.19     13813921.58      2553081.21     13813832.86
      2552809.79     13813725.51      2552571.58     13813767.21
      2552377.74     13813480.34      2551911.76     13813411.39
      2551717.27     13812918.50      2551475.00     13812775.00

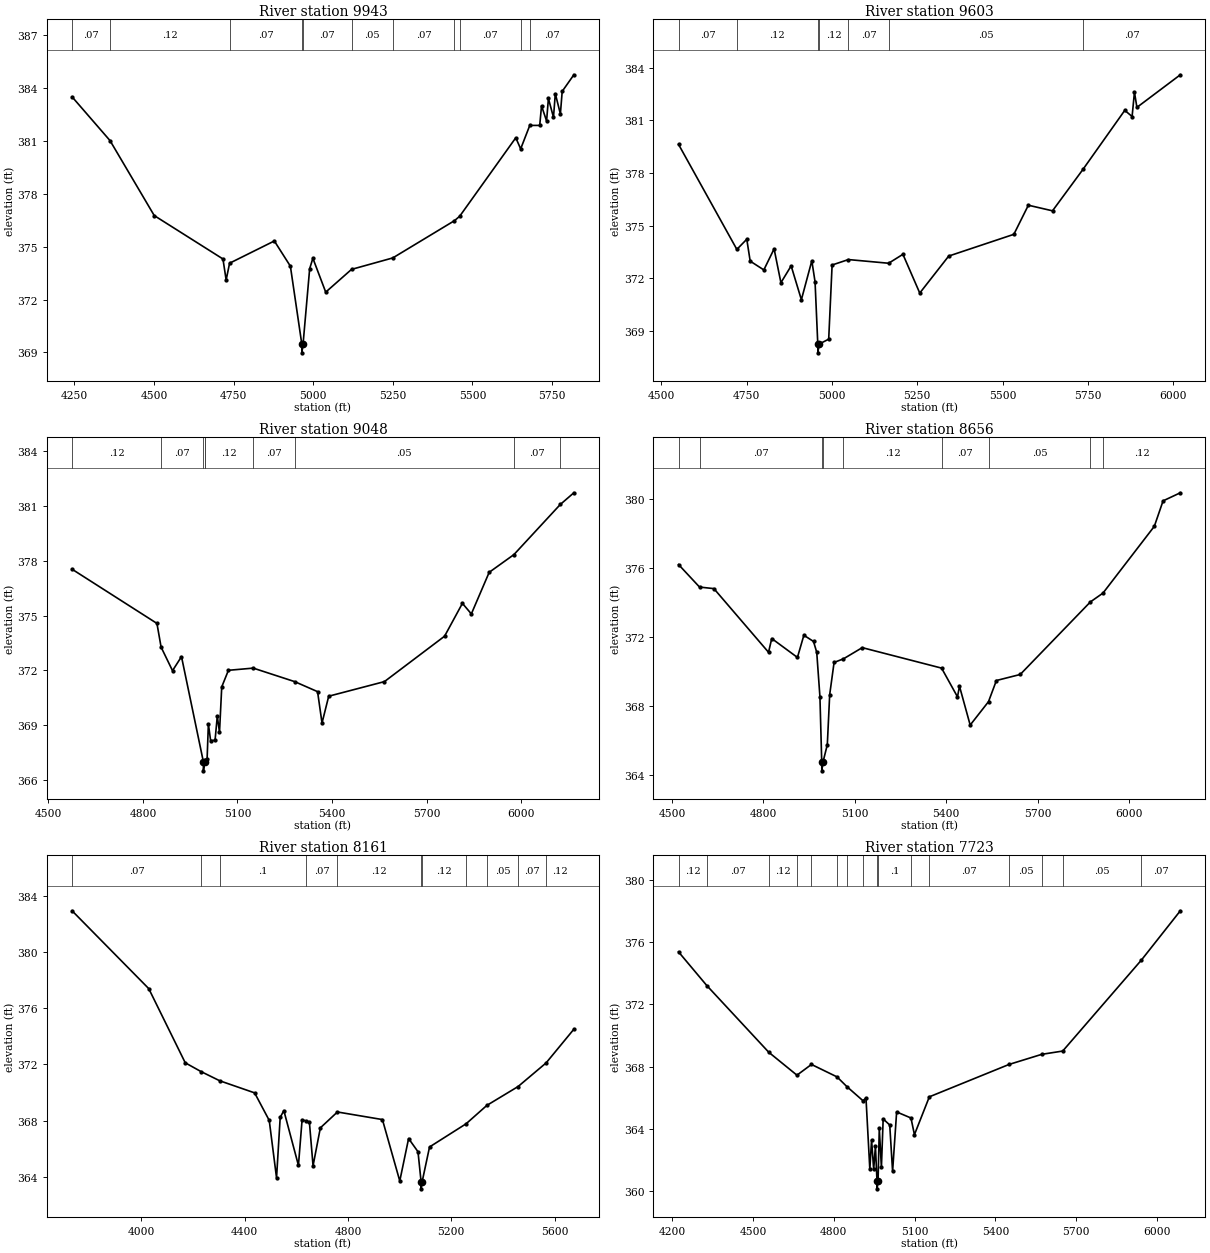
Type RM Length L Ch R = 1,9943,340,340,340
BEGIN DESCRIPTION:
Rocky Creek 4 17.0
END DESCRIPTION:
XS GIS Cut Line= 3
      2557644.72     13818196.67      2556822.19     13818303.36
      2556173.11     13818670.82
#Sta/Elev= 30
  4243.1  383.49  4362.2  381.01  4501.1  376.76  4716.8  374.30  4726.8  373.11
  4737.6  374.06  4878.1  375.32  4928.5  373.89  4964.3  369.48  4964.5  368.98
  4968.3  369.48  4989.0  373.75  4999.1  374.34  5039.4  372.42  5120.4  373.71
  5250.0  374.36  5443.5  376.47  5459.9  376.72  5636.1  381.17  5651.4  380.54
  5680.0  381.87  5711.2  381.87  5716.9  382.98  5732.8  382.12  5738.5  383.40
  5754.4  382.33  5760.2  383.67  5776.1  382.52  5781.8  383.80  5818.4  384.74
#Mann=11,-1,0
  4243.1    0.07       0  4362.2    0.12       0  4737.6    0.07       0
  4964.3    0.05       0  4968.3    0.07       0  5120.4    0.05       0
  5250.0    0.07       0  5443.5    0.05       0  5459.9    0.07       0
  5651.4    0.05       0  5680.0    0.07       0
Bank Sta=4964.3,4968.3
Exp/Cntr=0.3,0.1

Type RM Length L Ch R = 1,9603,555,555,555
BEGIN DESCRIPTION:
Rocky Creek 4 16.0
END DESCRIPTION:
XS GIS Cut Line= 3
      2557324.95     13817975.00      2556846.28     13817993.60
      2556124.98     13818675.02
#Sta/Elev= 30
  4550.0  379.63  4721.0  373.64  4750.1  374.22  4760.1  372.97  4800.1  372.47
  4830.2  373.67  4850.2  371.74  4880.2  372.70  4910.2  370.77  4940.8  372.99
  4950.3  371.79  4958.3  368.24  4958.5  367.74  4962.3  368.24  4990.3  368.52
  5000.3  372.75  5048.1  373.06  5166.0  372.85  5207.9  373.36  5257.3  371.15
  5342.2  373.26  5533.2  374.50  5575.7  376.16  5646.5  375.84  5735.7  378.20
  5858.4  381.57  5879.9  381.22  5886.8  382.61  5894.0  381.74  6021.3  383.60
#Mann=7,-1,0
  4550.0    0.07       0  4721.0    0.12       0  4958.3    0.05       0
  4962.3    0.12       0  5048.1    0.07       0  5166.0    0.05       0
  5735.7    0.07       0
Bank Sta=4958.3,4962.3
Exp/Cntr=0.3,0.1

Type RM Length L Ch R = 1,9048,392,392,392
BEGIN DESCRIPTION:
Rocky Creek 4 15.0
END DESCRIPTION:
XS GIS Cut Line= 3
      2556974.97     13817425.03      2556650.10     13817704.50
      2555824.97     13818525.03
#Sta/Elev= 30
  4575.2  377.54  4844.5  374.57  4857.7  373.27  4893.9  371.98  4922.4  372.75
  4991.8  366.99  4992.0  366.49  4995.8  366.99  4997.8  367.09  5003.7  367.14
  5007.7  369.06  5014.8  368.15  5028.9  368.16  5036.0  369.49  5043.0  368.60
  5050.1  371.09  5071.3  372.00  5150.1  372.12  5281.5  371.38  5354.2  370.83
  5368.3  369.11  5389.5  370.58  5566.3  371.38  5757.2  373.87  5813.8  375.67
  5842.1  375.09  5898.7  377.37  5977.1  378.34  6124.4  381.09  6167.4  381.73
#Mann=9,-1,0
  4575.2    0.12       0  4857.7    0.07       0  4991.8    0.05       0
  4995.8    0.07       0  4997.8    0.12       0  5150.1    0.07       0
  5281.5    0.05       0  5977.1    0.07       0  6124.4    0.12       0
Bank Sta=4991.8,4995.8
Exp/Cntr=0.3,0.1

Type RM Length L Ch R = 1,8656,495,495,495
BEGIN DESCRIPTION:
Rocky Creek 4 14.0
END DESCRIPTION:
XS GIS Cut Line= 3
      2556825.02     13817324.99      2556375.00     13817475.00
      2555625.00     13818375.00
#Sta/Elev= 30
  4521.7  376.22  4590.6  374.91  4637.7  374.82  4816.9  371.12  4827.4  371.92
  4911.7  370.82  4932.8  372.11  4964.4  371.75  4975.0  371.12  4985.5  368.53
  4991.4  364.73  4991.7  364.23  4995.4  364.73  5009.7  365.75  5017.5  368.66
  5031.9  370.53  5062.7  370.74  5124.3  371.39  5384.5  370.20  5436.7  368.53
  5443.2  369.15  5478.3  366.89  5538.4  368.25  5564.3  369.48  5642.4  369.83
  5872.8  374.05  5913.9  374.56  6082.3  378.44  6111.0  379.92  6167.6  380.39
#Mann=9,-1,0
  4521.7    0.12       0  4590.6    0.07       0  4991.4    0.05       0
  4995.4    0.07       0  5062.7    0.12       0  5384.5    0.07       0
  5538.4    0.05       0  5872.8    0.07       0  5913.9    0.12       0
Bank Sta=4991.4,4995.4
Exp/Cntr=0.3,0.1

Type RM Length L Ch R = 1,8161,438,438,438
BEGIN DESCRIPTION:
Rocky Creek 4 13.0
END DESCRIPTION:
XS GIS Cut Line= 3
      2556775.01     13816574.99      2555875.00     13817475.00
      2555575.01     13818074.98
#Sta/Elev= 30
  3731.3  382.94  4028.3  377.40  4169.7  372.12  4230.4  371.50  4303.4  370.84
  4438.4  369.98  4495.0  368.02  4523.3  363.93  4537.4  368.23  4551.6  368.72
  4608.1  364.82  4622.3  368.07  4636.0  367.99  4650.5  367.91  4664.7  364.79
  4693.0  367.49  4759.1  368.62  4933.4  368.08  5000.6  363.71  5034.8  366.73
  5071.2  365.79  5083.2  363.65  5083.4  363.15  5087.2  363.65  5115.9  366.13
  5257.5  367.78  5338.0  369.09  5458.8  370.43  5567.3  372.11  5674.9  374.51
#Mann=11,-1,0
  3731.3    0.07       0  4230.4    0.12       0  4303.4     0.1       0
  4636.0    0.07       0  4759.1    0.12       0  5083.2    0.05       0
  5087.2    0.12       0  5257.5    0.07       0  5338.0    0.05       0
  5458.8    0.07       0  5567.3    0.12       0
Bank Sta=5083.2,5087.2
Exp/Cntr=0.3,0.1

Type RM Length L Ch R = 1,7723,453,453,453
BEGIN DESCRIPTION:
Rocky Creek 4 12.0
END DESCRIPTION:
XS GIS Cut Line= 3
      2556325.01     13816624.99      2555725.00     13817125.00
      2555125.00     13818025.00
#Sta/Elev= 30
  4224.0  375.37  4328.8  373.21  4559.1  368.92  4663.6  367.45  4717.4  368.14
  4812.4  367.34  4848.7  366.72  4908.7  365.81  4919.8  365.99  4934.1  361.41
  4940.6  363.29  4948.4  361.40  4954.9  362.89  4960.7  360.65  4961.0  360.15
  4964.7  360.65  4969.2  364.03  4977.1  361.53  4983.6  364.64  5008.0  364.25
  5018.6  361.27  5033.6  365.09  5086.8  364.70  5099.7  363.63  5155.0  366.06
  5450.9  368.14  5572.5  368.79  5650.1  369.00  5942.5  374.85  6086.7  378.01
#Mann=16,-1,0
  4224.0    0.12       0  4328.8    0.07       0  4559.1    0.12       0
  4663.6    0.07       0  4717.4    0.12       0  4812.4     0.1       0
  4848.7    0.12       0  4908.7     0.1       0  4960.7    0.05       0
  4964.7     0.1       0  5086.8    0.12       0  5155.0    0.07       0
  5450.9    0.05       0  5572.5    0.07       0  5650.1    0.05       0
  5942.5    0.07       0
Bank Sta=4960.7,4964.7
Exp/Cntr=0.3,0.1

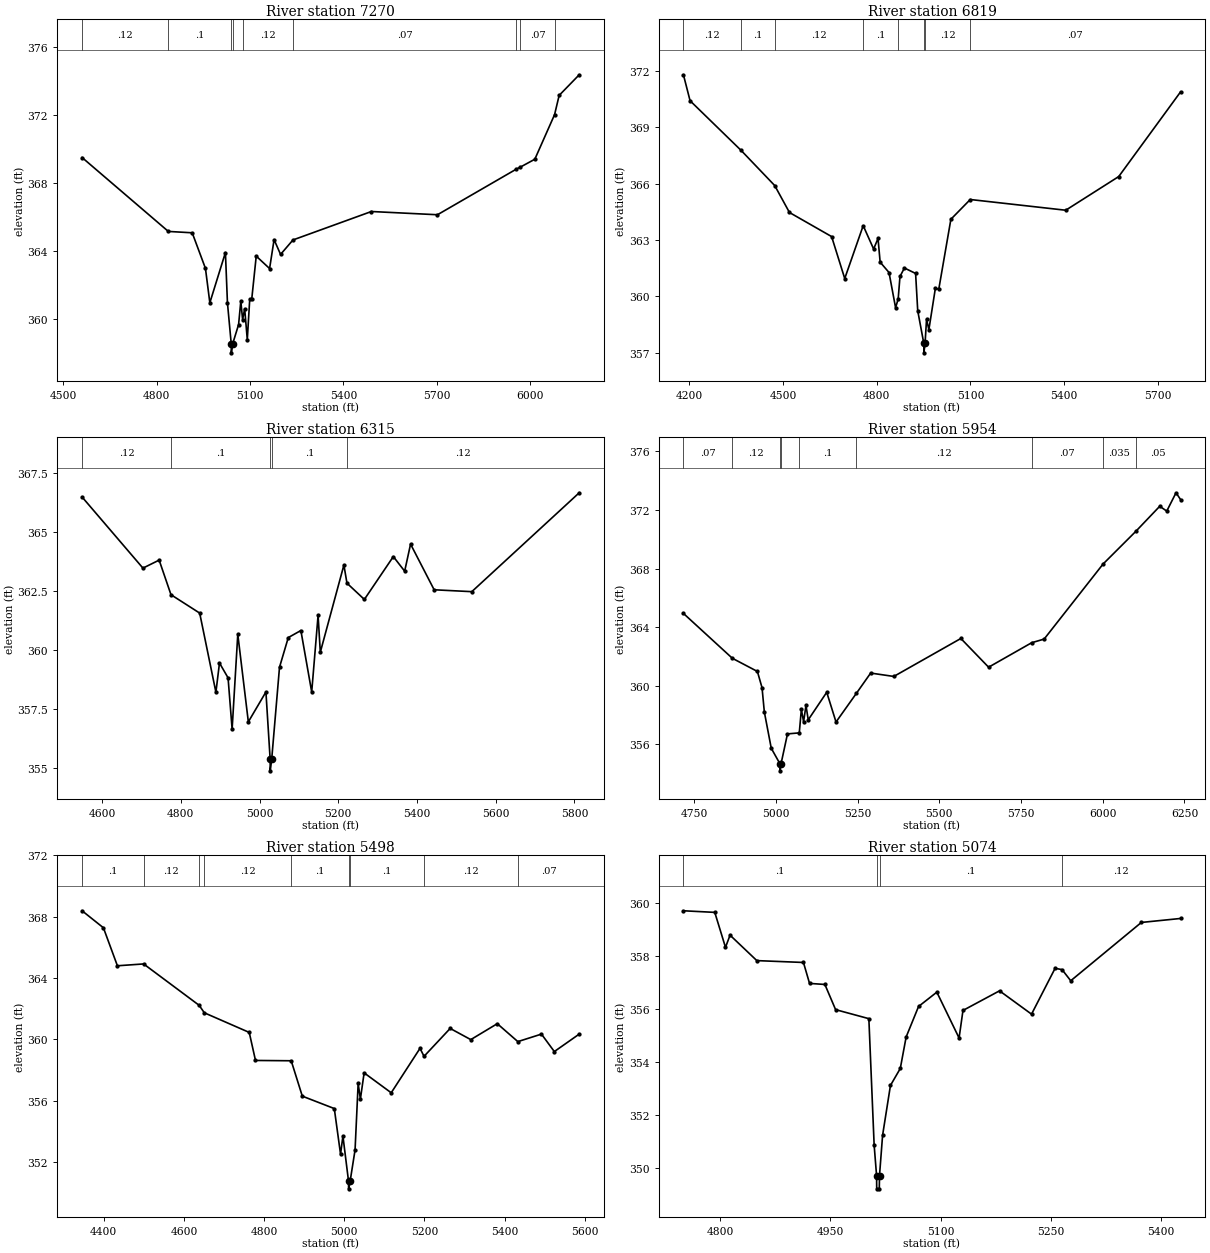
Type RM Length L Ch R = 1,7270,451,451,451
BEGIN DESCRIPTION:
Rocky Creek 4 11.0
END DESCRIPTION:
XS GIS Cut Line= 3
      2555874.99     13816425.01      2555575.00     13816725.00
      2554825.00     13817625.01
#Sta/Elev= 30
  4560.9  369.51  4837.8  365.17  4914.4  365.09  4956.9  363.00  4971.0  360.98
  5021.0  363.93  5027.5  360.98  5039.8  358.54  5040.0  358.04  5043.8  358.54
  5063.3  359.70  5070.4  361.08  5076.2  359.99  5082.8  360.63  5091.2  358.82
  5099.1  361.20  5105.6  361.21  5119.9  363.72  5162.8  362.99  5177.2  364.69
  5198.0  363.82  5237.9  364.67  5489.6  366.34  5701.7  366.15  5954.9  368.83
  5967.9  368.95  6014.2  369.41  6077.6  372.03  6092.3  373.16  6156.7  374.37
#Mann=9,-1,0
  4560.9    0.12       0  4837.8     0.1       0  5039.8    0.05       0
  5043.8     0.1       0  5076.2    0.12       0  5237.9    0.07       0
  5954.9    0.05       0  5967.9    0.07       0  6077.6   0.035       0
Bank Sta=5039.8,5043.8
Exp/Cntr=0.3,0.1

Type RM Length L Ch R = 1,6819,504,504,504
BEGIN DESCRIPTION:
Rocky Creek 4 10.0
END DESCRIPTION:
XS GIS Cut Line= 3
      2555775.03     13816174.97      2555175.00     13816725.00
      2554625.00     13817275.00
#Sta/Elev= 30
  4180.9  371.78  4202.2  370.40  4365.6  367.76  4473.3  365.89  4520.4  364.46
  4655.4  363.18  4697.4  360.95  4756.5  363.76  4789.9  362.52  4804.0  363.08
  4810.8  361.82  4839.2  361.27  4860.2  359.40  4868.5  359.86  4874.3  361.06
  4888.5  361.51  4924.3  361.22  4931.1  359.24  4950.6  357.50  4950.9  357.00
  4954.6  357.50  4959.4  358.79  4966.8  358.23  4987.8  360.45  4998.4  360.37
  5037.3  364.10  5099.3  365.15  5405.0  364.58  5574.7  366.37  5772.7  370.87
#Mann=8,-1,0
  4180.9    0.12       0  4365.6     0.1       0  4473.3    0.12       0
  4756.5     0.1       0  4868.5    0.12       0  4950.6    0.05       0
  4954.6    0.12       0  5099.3    0.07       0
Bank Sta=4950.6,4954.6
Exp/Cntr=0.3,0.1

Type RM Length L Ch R = 1,6315,361,361,361
BEGIN DESCRIPTION:
Rocky Creek 4 9.0
END DESCRIPTION:
XS GIS Cut Line= 3
      2555575.01     13816275.00      2555157.15     13816378.65
      2554424.97     13816775.01
#Sta/Elev= 30
  4549.0  366.49  4703.6  363.47  4744.8  363.81  4774.9  362.34  4847.8  361.56
  4889.0  358.20  4898.1  359.44  4919.9  358.81  4930.2  356.63  4944.6  360.66
  4971.4  356.94  5016.1  358.21  5026.8  355.36  5027.0  354.86  5030.8  355.36
  5050.6  359.26  5072.9  360.52  5104.9  360.82  5132.4  358.21  5148.6  361.46
  5154.3  359.90  5214.2  363.60  5222.0  362.83  5266.2  362.14  5339.8  363.96
  5368.6  363.34  5383.6  364.49  5443.5  362.55  5539.2  362.47  5812.1  366.67
#Mann=5,-1,0
  4549.0    0.12       0  4774.9     0.1       0  5026.8    0.05       0
  5030.8     0.1       0  5222.0    0.12       0
Bank Sta=5026.8,5030.8
Exp/Cntr=0.3,0.1

Type RM Length L Ch R = 1,5954,456,456,456
BEGIN DESCRIPTION:
Rocky Creek 4 8.0
END DESCRIPTION:
XS GIS Cut Line= 3
      2555275.03     13815874.97      2555075.00     13816075.00
      2554175.02     13816924.98
#Sta/Elev= 30
  4717.2  364.94  4866.8  361.88  4943.5  360.98  4957.7  359.87  4964.7  358.22
  4985.9  355.74  5012.0  354.70  5012.3  354.20  5016.0  354.70  5035.5  356.72
  5071.6  356.79  5078.0  358.39  5084.8  357.55  5092.1  358.66  5099.0  357.68
  5155.6  359.56  5184.0  357.53  5246.4  359.49  5290.0  360.87  5360.8  360.64
  5565.9  363.23  5650.8  361.27  5782.5  362.94  5820.7  363.19  6001.0  368.31
  6101.2  370.54  6174.3  372.25  6195.8  371.92  6224.1  373.17  6238.0  372.71
#Mann=9,-1,0
  4717.2    0.07       0  4866.8    0.12       0  5012.0    0.05       0
  5016.0    0.12       0  5071.6     0.1       0  5246.4    0.12       0
  5782.5    0.07       0  6001.0   0.035       0  6101.2    0.05       0
Bank Sta=5012,5016
Exp/Cntr=0.3,0.1

Type RM Length L Ch R = 1,5498,424,424,424
BEGIN DESCRIPTION:
Rocky Creek 4 7.0
END DESCRIPTION:
XS GIS Cut Line= 3
      2555290.66     13815537.97      2554725.00     13815875.00
      2554210.00     13816145.57
#Sta/Elev= 30
  4345.9  368.39  4399.1  367.28  4434.0  364.80  4499.4  364.92  4637.9  362.22
  4650.9  361.73  4762.9  360.45  4778.5  358.62  4867.6  358.60  4895.3  356.29
  4975.1  355.48  4990.7  352.50  4996.6  353.69  5010.6  350.74  5010.8  350.24
  5014.6  350.74  5026.9  352.78  5034.6  357.12  5040.2  356.10  5049.5  357.81
  5117.1  356.51  5188.9  359.41  5199.0  358.89  5264.2  360.71  5315.6  359.98
  5381.7  361.02  5433.0  359.85  5491.9  360.34  5524.0  359.20  5586.1  360.34
#Mann=9,-1,0
  4345.9     0.1       0  4499.4    0.12       0  4637.9    0.07       0
  4650.9    0.12       0  4867.6     0.1       0  5010.6    0.05       0
  5014.6     0.1       0  5199.0    0.12       0  5433.0    0.07       0
Bank Sta=5010.6,5014.6
Exp/Cntr=0.3,0.1

Type RM Length L Ch R = 1,5074,364,364,364
BEGIN DESCRIPTION:
Rocky Creek 4 6.0
END DESCRIPTION:
XS GIS Cut Line= 3
      2554724.97     13815375.02      2554525.00     13815525.00
      2554374.99     13815925.03
#Sta/Elev= 30
  4749.8  359.69  4792.5  359.63  4807.1  358.31  4813.3  358.77  4849.8  357.81
  4913.3  357.74  4921.6  356.95  4942.5  356.91  4957.1  355.96  5002.4  355.62
  5009.6  350.85  5012.9  349.70  5013.1  349.20  5016.6  349.20  5016.9  349.70
  5021.1  351.22  5031.8  353.10  5045.2  353.74  5053.2  354.93  5070.1  356.08
  5095.0  356.62  5125.3  354.89  5130.6  355.93  5180.4  356.67  5224.0  355.79
  5256.1  357.52  5265.6  357.47  5277.4  357.05  5373.6  359.25  5427.0  359.40
#Mann=4,-1,0
  4749.8     0.1       0  5012.9    0.05       0  5016.9     0.1       0
  5265.6    0.12       0
Bank Sta=5012.9,5016.9
Exp/Cntr=0.3,0.1

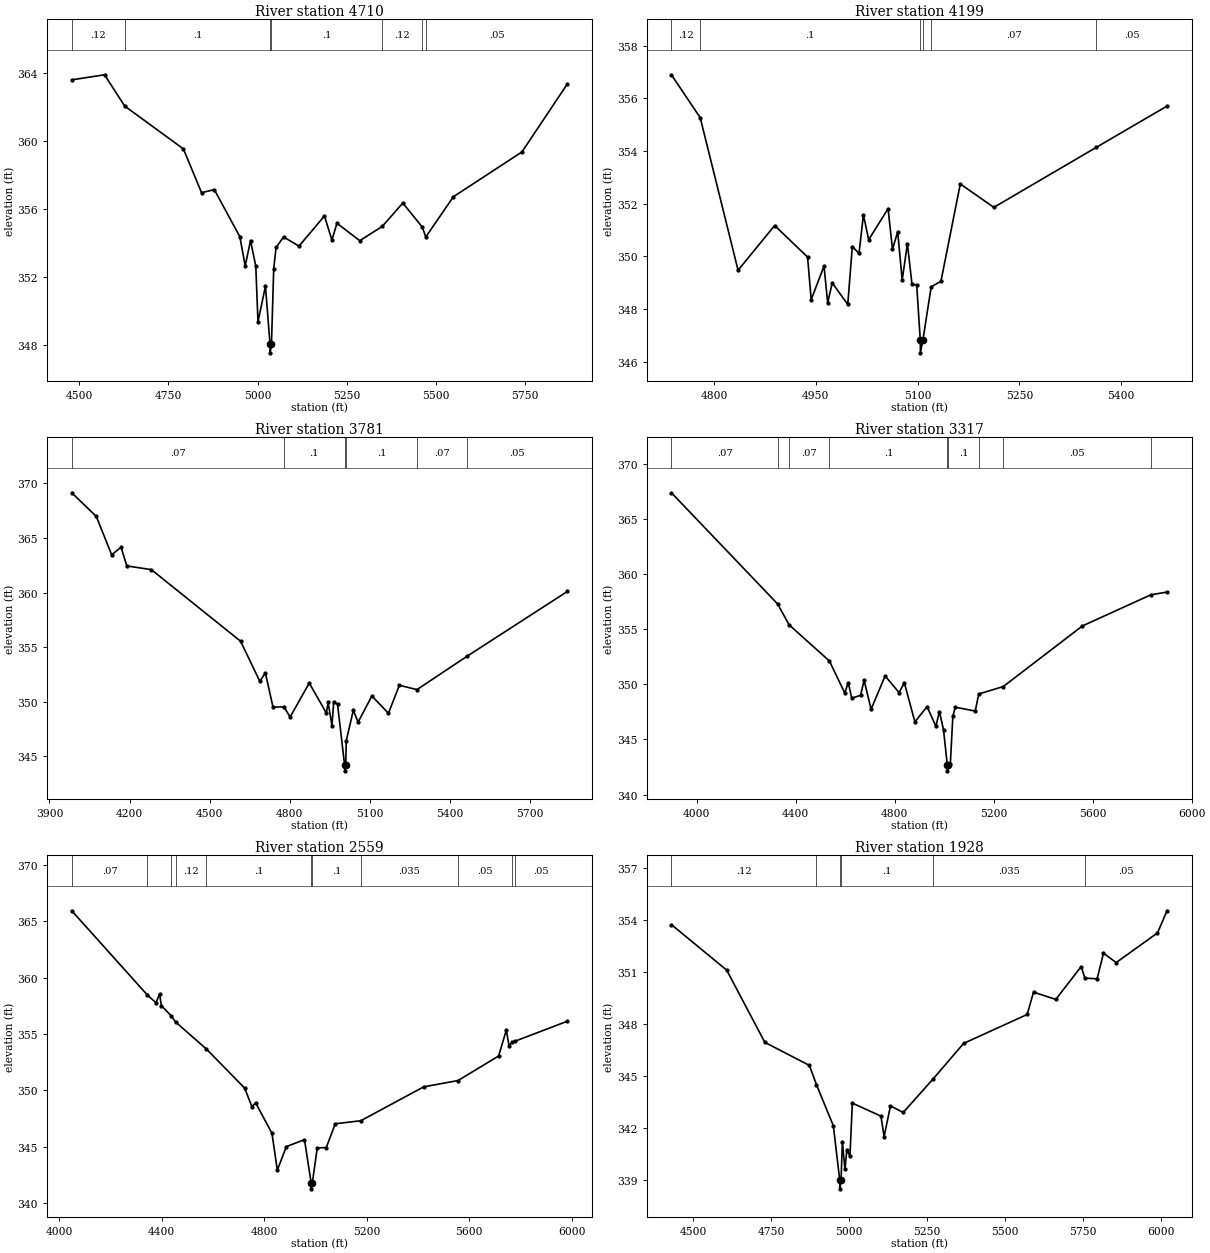
Type RM Length L Ch R = 1,4710,511,511,511
BEGIN DESCRIPTION:
Rocky Creek 4 5.0
END DESCRIPTION:
XS GIS Cut Line= 3
      2554761.12     13814934.69      2554244.65     13815290.58
      2553750.84     13815871.03
#Sta/Elev= 30
  4479.2  363.61  4571.1  363.91  4627.4  362.07  4792.2  359.54  4843.0  356.96
  4878.8  357.14  4950.5  354.36  4965.4  352.64  4980.3  354.14  4995.1  352.62
  5001.2  349.35  5022.2  351.45  5035.0  348.02  5035.3  347.52  5039.0  348.02
  5045.3  352.46  5051.9  353.73  5072.9  354.35  5116.2  353.81  5187.6  355.59
  5208.4  354.17  5222.7  355.16  5286.4  354.13  5349.5  354.97  5407.2  356.35
  5461.6  354.94  5471.7  354.35  5548.9  356.72  5741.1  359.36  5868.5  363.37
#Mann=7,-1,0
  4479.2    0.12       0  4627.4     0.1       0  5035.0    0.05       0
  5039.0     0.1       0  5349.5    0.12       0  5461.6    0.07       0
  5471.7    0.05       0
Bank Sta=5035,5039
Exp/Cntr=0.3,0.1

Type RM Length L Ch R = 1,4199,418,418,418
BEGIN DESCRIPTION:
Rocky Creek 4 4.0
END DESCRIPTION:
XS GIS Cut Line= 3
      2554074.99     13814725.03      2553975.00     13814975.00
      2553625.00     13815275.00
#Sta/Elev= 30
  4737.2  356.90  4779.6  355.27  4835.4  349.47  4889.3  351.17  4937.8  349.97
  4943.1  348.35  4962.0  349.63  4967.4  348.23  4974.1  348.99  4997.0  348.17
  5003.7  350.37  5013.6  350.11  5020.1  351.58  5027.8  350.63  5056.4  351.81
  5062.9  350.27  5070.6  350.93  5077.2  349.10  5084.9  350.48  5091.5  348.96
  5098.6  348.89  5103.8  346.83  5104.0  346.33  5107.8  346.83  5119.9  348.84
  5134.3  349.05  5162.8  352.75  5212.2  351.86  5363.1  354.14  5467.4  355.71
#Mann=6,-1,0
  4737.2    0.12       0  4779.6     0.1       0  5103.8    0.05       0
  5107.8     0.1       0  5119.9    0.07       0  5363.1    0.05       0
Bank Sta=5103.8,5107.8
Exp/Cntr=0.3,0.1

Type RM Length L Ch R = 1,3781,464,464,464
BEGIN DESCRIPTION:
Rocky Creek 4 3.0
END DESCRIPTION:
XS GIS Cut Line= 3
      2554375.01     13813924.99      2553725.00     13814725.00
      2553525.00     13815524.98
#Sta/Elev= 30
  3983.5  369.15  4075.4  366.98  4132.9  363.47  4168.1  364.16  4189.7  362.45
  4281.6  362.11  4615.6  355.55  4687.5  351.88  4708.3  352.65  4737.0  349.51
  4777.7  349.54  4801.0  348.61  4872.6  351.72  4936.7  348.97  4943.2  349.96
  4957.6  347.81  4964.0  349.96  4978.4  349.80  5005.1  344.18  5005.4  343.68
  5009.1  344.18  5011.1  346.43  5037.5  349.22  5055.5  348.14  5107.1  350.54
  5168.9  348.95  5210.1  351.52  5275.8  351.12  5462.3  354.16  5838.9  360.11
#Mann=6,-1,0
  3983.5    0.07       0  4777.7     0.1       0  5005.1    0.05       0
  5009.1     0.1       0  5275.8    0.07       0  5462.3    0.05       0
Bank Sta=5005.1,5009.1
Exp/Cntr=0.3,0.1

Type RM Length L Ch R = 1,3317,758,758,758
BEGIN DESCRIPTION:
Rocky Creek 4 2.0
END DESCRIPTION:
XS GIS Cut Line= 3
      2554174.97     13813775.03      2553375.00     13814525.00
      2553475.00     13815425.02
#Sta/Elev= 30
  3898.4  367.41  4327.4  357.31  4373.6  355.42  4536.9  352.12  4598.6  349.22
  4612.7  350.17  4626.9  348.75  4662.5  349.01  4676.7  350.38  4705.0  347.75
  4761.7  350.77  4817.9  349.26  4839.4  350.14  4881.9  346.60  4931.2  347.98
  4966.8  346.19  4981.0  347.54  4997.5  345.88  5013.0  342.65  5013.3  342.15
  5017.1  342.65  5025.1  342.77  5035.2  347.10  5045.2  347.93  5125.7  347.58
  5139.9  349.13  5239.2  349.81  5558.4  355.31  5835.1  358.14  5900.5  358.39
#Mann=9,-1,0
  3898.4    0.07       0  4327.4    0.12       0  4373.6    0.07       0
  4536.9     0.1       0  5013.0    0.05       0  5017.1     0.1       0
  5139.9    0.07       0  5239.2    0.05       0  5835.1   0.035       0
Bank Sta=5013,5017.1
Exp/Cntr=0.3,0.1

Type RM Length L Ch R = 1,2559,631,631,631
BEGIN DESCRIPTION:
B20287
END DESCRIPTION:
XS GIS Cut Line= 3
      2553858.34     13813413.86      2552983.36     13814226.34
      2553080.43     13814961.23
#Sta/Elev= 30
  4048.5  365.94  4343.3  358.47  4377.3  357.77  4391.5  358.55  4398.3  357.52
  4435.7  356.63  4454.0  356.06  4573.7  353.67  4723.7  350.19  4752.0  348.53
  4766.2  348.89  4830.2  346.18  4851.2  342.90  4886.4  344.99  4957.3  345.61
  4983.5  341.74  4983.8  341.24  4987.7  341.74  5007.1  344.87  5042.3  344.91
  5077.5  347.02  5177.2  347.29  5422.7  350.30  5557.0  350.86  5715.3  353.04
  5745.5  355.35  5756.0  353.93  5768.4  354.27  5778.9  354.35  5983.8  356.13
#Mann=11,-1,0
  4048.5    0.07       0  4343.3    0.12       0  4435.7    0.07       0
  4454.0    0.12       0  4573.7     0.1       0  4983.5    0.05       0
  4987.7     0.1       0  5177.2   0.035       0  5557.0    0.05       0
  5768.4   0.035       0  5778.9    0.05       0
Bank Sta=4983.5,4987.7
Exp/Cntr=0.3,0.1

Type RM Length L Ch R = 1,1928,313,313,313
BEGIN DESCRIPTION:
Rocky Creek 4 1.0
END DESCRIPTION:
XS GIS Cut Line= 3
      2553125.02     13813274.97      2552775.00     13813725.00
      2552974.99     13814724.97
#Sta/Elev= 30
  4430.4  353.74  4607.8  351.11  4730.0  346.94  4872.9  345.61  4895.6  344.50
  4949.9  342.12  4970.3  338.98  4970.6  338.48  4974.6  338.98  4978.8  341.21
  4987.0  339.61  4993.3  340.74  5003.1  340.36  5010.7  343.43  5102.5  342.68
  5112.7  341.50  5133.1  343.27  5173.9  342.89  5270.0  344.83  5367.7  346.88
  5571.6  348.55  5592.0  349.84  5663.4  349.42  5745.0  351.32  5756.7  350.65
  5796.0  350.61  5816.4  352.09  5857.2  351.55  5989.7  353.26  6020.3  354.54
#Mann=6,-1,0
  4430.4    0.12       0  4895.6     0.1       0  4970.3    0.05       0
  4974.6     0.1       0  5270.0   0.035       0  5756.7    0.05       0
Bank Sta=4970.3,4974.6
Exp/Cntr=0.3,0.1

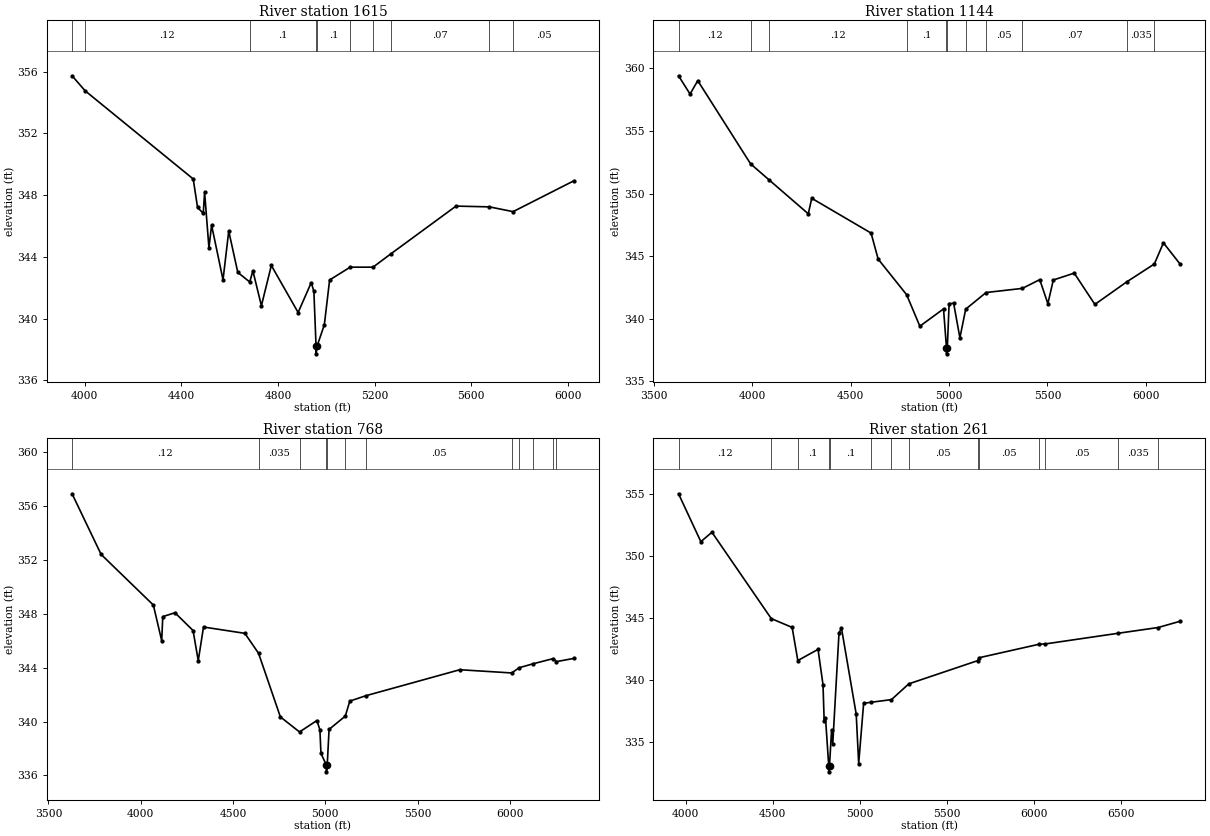
Type RM Length L Ch R = 1,1615,471,471,471
BEGIN DESCRIPTION:
B20286
END DESCRIPTION:
XS GIS Cut Line= 3
      2552913.94     13812733.25      2552462.53     13813795.79
      2552691.49     13814690.82
#Sta/Elev= 30
  3947.0  355.74  4000.8  354.77  4448.7  349.05  4466.8  347.20  4490.4  346.82
  4495.9  348.19  4513.9  344.58  4524.9  346.05  4572.2  342.51  4595.9  345.67
  4633.4  342.99  4682.9  342.37  4695.9  343.09  4731.2  340.83  4772.3  343.44
  4883.3  340.39  4937.6  342.33  4948.5  341.76  4957.5  338.21  4957.8  337.71
  4961.8  338.21  4991.9  339.60  5013.7  342.50  5099.0  343.33  5193.5  343.33
  5266.2  344.18  5537.2  347.29  5675.5  347.24  5773.6  346.93  6025.3  348.93
#Mann=10,-1,0
  3947.0    0.07       0  4000.8    0.12       0  4682.9     0.1       0
  4957.5    0.05       0  4961.8     0.1       0  5099.0    0.07       0
  5193.5    0.12       0  5266.2    0.07       0  5675.5   0.035       0
  5773.6    0.05       0
Bank Sta=4957.5,4961.8
Exp/Cntr=0.3,0.1

Type RM Length L Ch R = 1,1144,376,376,376
BEGIN DESCRIPTION:
B20285
END DESCRIPTION:
XS GIS Cut Line= 3
      2552754.21     13812226.31      2552129.20     13813580.51
      2552386.15     13814608.30
#Sta/Elev= 30
  3624.7  359.41  3683.2  357.95  3722.4  359.02  3991.1  352.37  4084.3  351.10
  4284.3  348.38  4301.8  349.62  4603.5  346.84  4639.5  344.76  4784.0  341.92
  4851.5  339.40  4971.8  340.78  4986.7  337.69  4987.1  337.19  4991.2  337.69
  5000.2  341.20  5023.2  341.23  5055.0  338.47  5084.5  340.76  5188.1  342.09
  5372.6  342.42  5461.0  343.12  5502.2  341.20  5529.9  343.09  5636.2  343.64
  5741.2  341.14  5903.1  342.94  6043.5  344.37  6089.7  346.06  6175.6  344.34
#Mann=11,-1,0
  3624.7    0.12       0  3991.1    0.07       0  4084.3    0.12       0
  4784.0     0.1       0  4986.7    0.05       0  4991.2     0.1       0
  5084.5    0.07       0  5188.1    0.05       0  5372.6    0.07       0
  5903.1   0.035       0  6043.5    0.05       0
Bank Sta=4986.7,4991.2
Exp/Cntr=0.3,0.1

Type RM Length L Ch R = 1,768,507,507,507
BEGIN DESCRIPTION:
B20284
END DESCRIPTION:
XS GIS Cut Line= 3
      2552490.31     13812136.06      2551768.09     13813497.18
      2552316.71     13814538.87
#Sta/Elev= 30
  3628.1  356.91  3785.4  352.41  4068.4  348.65  4113.7  346.00  4119.4  347.79
  4185.4  348.08  4283.5  346.76  4311.6  344.52  4340.1  347.02  4564.2  346.55
  4638.3  345.07  4756.4  340.35  4860.2  339.23  4954.3  340.08  4970.6  339.39
  4976.3  337.64  5005.8  336.77  5006.1  336.27  5010.3  336.77  5020.3  339.42
  5108.4  340.41  5132.5  341.52  5219.6  341.92  5728.5  343.85  6009.7  343.61
  6050.5  344.00  6122.6  344.28  6235.5  344.68  6251.2  344.45  6346.3  344.69
#Mann=12,-1,0
  3628.1    0.12       0  4638.3   0.035       0  4860.2    0.05       0
  5005.8    0.05       0  5010.3    0.05       0  5108.4   0.035       0
  5219.6    0.05       0  6009.7   0.035       0  6050.5    0.05       0
  6122.6   0.035       0  6235.5    0.07       0  6251.2    0.05       0
Bank Sta=5005.8,5010.3
Exp/Cntr=0.3,0.1

Type RM Length L Ch R = 1,261,0,0,0
BEGIN DESCRIPTION:
B20283
END DESCRIPTION:
XS GIS Cut Line= 4
      2552386.11     13812115.27      2551622.25     13812969.40
      2551684.75     13813490.23      2552267.35     13814551.38
#Sta/Elev= 30
  3959.0  355.03  4087.1  351.17  4150.7  351.93  4491.4  344.97  4611.3  344.26
  4643.9  341.59  4760.0  342.49  4788.5  339.64  4795.2  336.69  4802.7  336.99
  4821.3  333.12  4821.6  332.62  4825.8  333.12  4837.8  336.02  4844.5  334.89
  4880.4  343.83  4894.6  344.19  4979.1  337.27  4993.3  333.29  5021.7  338.14
  5066.1  338.23  5181.5  338.44  5280.9  339.71  5676.2  341.58  5685.9  341.82
  6027.9  342.90  6065.7  342.93  6484.0  343.79  6712.0  344.25  6840.0  344.76
#Mann=14,-1,0
  3959.0    0.12       0  4491.4   0.035       0  4643.9     0.1       0
  4821.3    0.05       0  4825.8     0.1       0  5066.1    0.05       0
  5181.5     0.1       0  5280.9    0.05       0  5676.2   0.035       0
  5685.9    0.05       0  6027.9   0.035       0  6065.7    0.05       0
  6484.0   0.035       0  6712.0    0.07       0
Bank Sta=4821.3,4825.8
Exp/Cntr=0.3,0.1

Chan Stop Cuts=-1