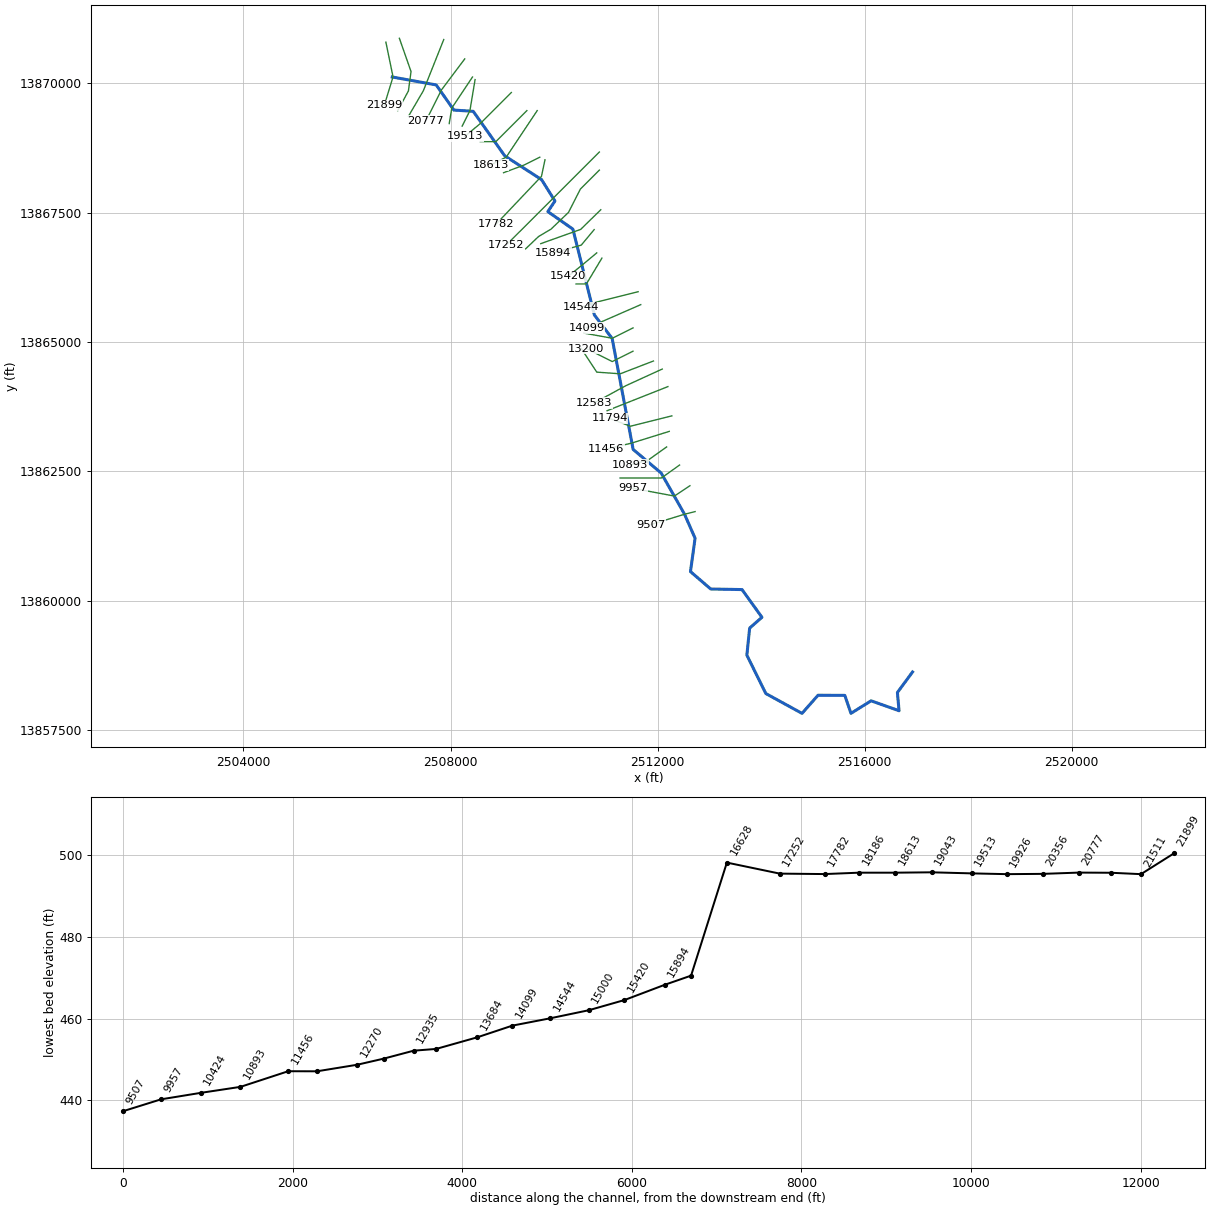
--- Rocky Creek Tributary.prj (project) ---

Proj Title=Rocky Creek Tributary Base Level Engineering
Current Plan=p01
Default Exp/Contr=0.3,0.1
English Units
Geom File=g01
Flow File=f01
Plan File=p01
Y Axis Title=Elevation
X Axis Title(PF)=Main Channel Distance
X Axis Title(XS)=Station
BEGIN DESCRIPTION:
Rocky Creek Tributary
END DESCRIPTION:
DSS Export Rating Curves= 0
DSS Export Rating Curve Sorted= 0
DSS Export Volume Flow Curves= 0
DXF OffsetX= 0
DXF OffsetY= 0
DXF ScaleX= 1
DXF ScaleY= 10

--- Rocky Creek Tributary.p01 (plan) ---

Plan Title=Multiple Run
Short Identifier=Multiple
Geom File=g01
Flow File=f01
Subcritical Flow
K Sum by GR= 0
Std Step Tol= 0.01
Critical Tol= 0.01
Num of Std Step Trials= 20
Max Error Tol= 0.3
Flow Tol Ratio= 0.001
Split Flow NTrial= 30
Split Flow Tol= 0.02
Split Flow Ratio= 0.02
Log Output Level= 0
Friction Slope Method= 1
Unsteady Friction Slope Method= 2
Unsteady Bridges Friction Slope Method= 1
Parabolic Critical Depth
Global Vel Dist=  1 , 1 , 1
Global Log Level= 0
CheckData=True
Encroach Param= -1, 0, 0, 0
BEGIN DESCRIPTION:
Multiple Run
END DESCRIPTION:

--- Rocky Creek Tributary.f01 (steady flow) ---

Flow Title=Multiple
Number of Profiles=7
Profile Names=10-year,25-year,50-year,1pct_min,100-year,1pct_plu,500-year
River Rch & RM= Rocky Creek Trib,Reach-1,21899
     557     885    1176     759    1514    3021    2479
River Rch & RM= Rocky Creek Trib,Reach-1,17252
     704    1133    1519     987    1970    3930    3275
River Rch & RM= Rocky Creek Trib,Reach-1,15000
    1113    1832    2495    1642    3277    6538    5599
River Rch & RM= Rocky Creek Trib,Reach-1,10893
    1219    2010    2739    1803    3598    7178    6149
River Rch & RM= Rocky Creek Trib,Reach-1,4046
    1476    2453    3361    2224    4437    8852    7659
Boundary for River Rch & Prof#=Rocky Creek Trib,Reach-1,1
Up Type=0
Dn Type=3
Dn Slope=0.005
Boundary for River Rch & Prof#=Rocky Creek Trib,Reach-1,2
Up Type=0
Dn Type=3
Dn Slope=0.005
Boundary for River Rch & Prof#=Rocky Creek Trib,Reach-1,3
Up Type=0
Dn Type=3
Dn Slope=0.005
Boundary for River Rch & Prof#=Rocky Creek Trib,Reach-1,4
Up Type=0
Dn Type=3
Dn Slope=0.005
Boundary for River Rch & Prof#=Rocky Creek Trib,Reach-1,5
Up Type=0
Dn Type=3
Dn Slope=0.005
Boundary for River Rch & Prof#=Rocky Creek Trib,Reach-1,6
Up Type=0
Dn Type=3
Dn Slope=0.005
Boundary for River Rch & Prof#=Rocky Creek Trib,Reach-1,7
Up Type=0
Dn Type=3
Dn Slope=0.005

--- Rocky Creek Tributary.g01 (geometry) ---

Geom Title=Existing Conditions
Program Version=4.10

River Reach=Rocky Creek Trib,Reach-1
Reach XY= 30
        2506875.       13870125.      2507723.38     13869971.87
        2508065.     13869485.96      2508439.03     13869461.39
        2509048.     13868600.64       2509758.7      13868141.7
      2510017.41     13867728.33      2509880.06     13867522.71
      2510363.92     13867185.38      2510778.75     13865526.55
      2511123.03     13865069.32      2511528.04     13862926.42
      2512069.81     13862469.56      2512521.18     13861673.42
      2512724.51     13861209.78      2512635.63       13860565.
      2513026.55     13860228.75      2513631.38     13860217.65
      2514016.05     13859681.66      2513778.52     13859473.54
      2513724.68     13858949.89      2514091.48     13858207.77
      2514790.24     13857824.84      2515099.87      13858175.3
      2515616.83     13858172.54      2515735.47     13857825.57
       2516124.9     13858067.72      2516664.69     13857875.86
      2516632.76     13858228.42        2516925.       13858625.

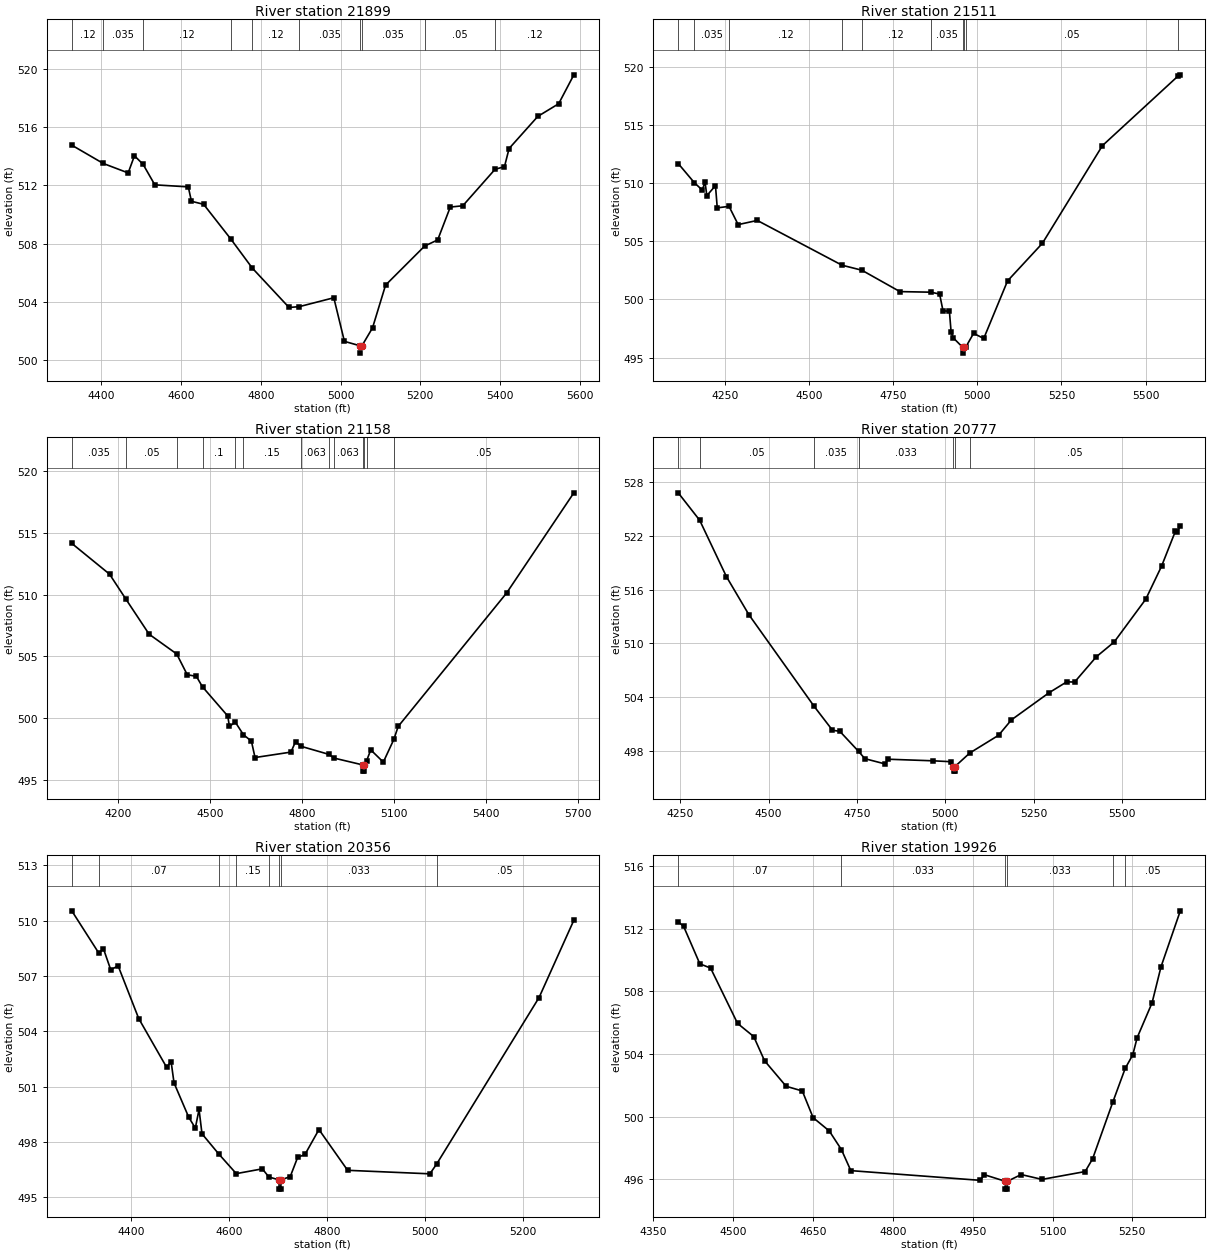
Type RM Length L Ch R = 1 ,21899   ,388,388,388
BEGIN DESCRIPTION:
Rocky Creek Tributary 41.0
END DESCRIPTION:
XS GIS Cut Line= 3
      2506751.51     13870799.09      2506889.94      13870127.9
      2506721.06     13869578.59
#Sta/Elev= 30
  4325.5  514.77  4404.6  513.51    4467  512.86  4482.8  514.04  4504.5  513.45
  4533.9  512.04  4617.9   511.9  4625.8  510.91  4656.4   510.7  4724.4  508.32
  4778.6  506.31  4870.8   503.6  4896.6  503.66  4983.1  504.27  5009.7  501.27
  5049.6  500.96  5049.8  500.46  5053.6  500.96  5080.3   502.2    5113  505.14
  5211.2  507.83  5243.8  508.25  5275.4  510.51  5306.8   510.6  5387.8  513.11
  5411.4  513.29    5423  514.54  5495.1  516.75  5547.4  517.62  5585.5  519.61
#Mann= 10 ,-1 , 0
  4325.5     .12       0  4404.6    .035       0  4504.5     .12       0
  4724.4    .035       0  4778.6     .12       0  4896.6    .035       0
  5049.6    .035       0  5053.6    .035       0  5211.2     .05       0
  5387.8     .12       0
Bank Sta=5049.6,5053.6
XS Rating Curve= 0 ,0
Exp/Cntr=0.3,0.1

Type RM Length L Ch R = 1 ,21511   ,353,353,353
BEGIN DESCRIPTION:
B20302
END DESCRIPTION:
XS GIS Cut Line= 4
      2507012.72     13870872.36      2507237.25     13870230.86
      2507186.84      13869855.1      2506980.64     13869474.78
#Sta/Elev= 30
  4111.7  511.68  4159.4  510.04  4183.1   509.4  4191.3   510.1  4196.6  508.92
  4222.3  509.78  4227.6  507.87  4262.6     508  4289.7  506.43  4346.5  506.79
  4598.2  502.94  4657.1  502.51  4770.2  500.67  4862.2  500.62  4888.1  500.46
  4898.2  499.02  4917.2  498.98  4922.2  497.21  4928.4   496.7  4956.7  495.88
    4957  495.38  4960.7  495.88    4966  495.91    4989  497.08  5019.2  496.64
  5089.9  501.59  5193.3  504.82  5371.7  513.22  5595.4  519.18  5603.1  519.31
#Mann= 10 ,-1 , 0
  4111.7     .12       0  4159.4    .035       0  4262.6     .12       0
  4598.2     .07       0  4657.1     .12       0  4862.2    .035       0
  4956.7     .05       0  4960.7    .035       0    4966     .05       0
  5595.4    .035       0
Bank Sta=4956.7,4960.7
XS Rating Curve= 0 ,0
Exp/Cntr=0.3,0.1

Type RM Length L Ch R = 1 ,21158   ,381,381,381
BEGIN DESCRIPTION:
Rocky Creek Tributary 40.0
END DESCRIPTION:
XS GIS Cut Line= 3
      2507869.62     13870849.49      2507475.53     13869859.69
      2507186.85      13869364.8
#Sta/Elev= 30
  4047.9  514.15  4171.1  511.66  4224.7  509.63  4300.3   506.8  4390.3   505.2
  4424.7  503.52  4454.4  503.39  4474.5  502.54  4556.9  500.18  4562.3  499.34
  4581.6  499.68  4608.2  498.66    4634  498.15  4645.9  496.82  4763.1  497.26
    4778   498.1  4795.8  497.73  4887.8  497.07  4902.9  496.78  4997.9  496.22
  4998.2  495.72  5001.7  495.72  5001.9  496.22    5010  496.56  5023.5  497.44
  5064.5  496.45  5098.7  498.28  5113.1  499.34  5466.7  510.13  5686.2  518.24
#Mann= 13 ,-1 , 0
  4047.9    .035       0  4224.7     .05       0  4390.3    .035       0
  4474.5      .1       0  4581.6     .05       0  4608.2     .15       0
  4795.8    .063       0  4887.8     .15       0  4902.9    .063       0
  4997.9    .063       0  5001.9    .063       0    5010    .033       0
  5098.7     .05       0
Bank Sta=4997.9,5001.9
XS Rating Curve= 0 ,0
Exp/Cntr=0.3,0.1

Type RM Length L Ch R = 1 ,20777   ,421,421,421
BEGIN DESCRIPTION:
Rocky Creek Tributary 39.0
END DESCRIPTION:
XS GIS Cut Line= 3
        2508275.     13870474.99        2507825.       13869875.
      2507525.01     13869275.01
#Sta/Elev= 30
  4244.5  526.81  4305.2  523.75    4381  517.45  4444.5  513.21    4629  502.99
    4681  500.32  4701.8   500.2  4754.7  497.97  4772.6  497.15    4831  496.55
  4837.2  497.09  4966.4  496.91  5016.9  496.81  5023.2  496.26  5023.5  495.76
    5027  495.76  5027.2  496.26  5069.8  497.79    5151  499.76  5187.4  501.48
  5293.6   504.5  5343.9  505.72  5366.2   505.7  5427.7  508.52    5478  510.16
  5567.5  514.94  5612.2  518.62  5651.3  522.52  5656.9  522.41  5665.3  523.16
#Mann= 7 ,-1 , 0
  4244.5    .035       0  4305.2     .05       0    4629    .035       0
  4754.7    .033       0  5023.2    .033       0  5027.2    .033       0
  5069.8     .05       0
Bank Sta=5023.2,5027.2
XS Rating Curve= 0 ,0
Exp/Cntr=0.3,0.1

Type RM Length L Ch R = 1 ,20356   ,430,430,430
BEGIN DESCRIPTION:
Rocky Creek Tributary 38.0
END DESCRIPTION:
XS GIS Cut Line= 3
      2508424.97     13870124.96        2508025.       13869525.
        2507975.       13869225.
#Sta/Elev= 30
  4278.5  510.54  4333.9  508.24  4343.1  508.49  4358.1  507.34  4373.1  507.56
  4415.2   504.7  4472.3  502.05  4481.3  502.37  4487.3  501.21  4517.3  499.35
  4530.8  498.76  4538.4  499.77  4544.4  498.45  4578.5  497.36  4614.4  496.29
  4667.6  496.55  4680.9  496.11  4701.6  495.95  4701.9  495.45  4705.4  495.45
  4705.6  495.95  4724.6  496.13  4739.7  497.17  4754.7  497.33  4783.2  498.68
  4841.8  496.47  5009.7  496.28  5023.3   496.8  5232.7  505.84  5303.7  510.03
#Mann= 8 ,-1 , 0
  4278.5    .035       0  4333.9     .07       0  4578.5    .033       0
  4614.4     .15       0  4680.9    .033       0  4701.6    .033       0
  4705.6    .033       0  5023.3     .05       0
Bank Sta=4701.6,4705.6
XS Rating Curve= 0 ,0
Exp/Cntr=0.3,0.1

Type RM Length L Ch R = 1 ,19926   ,413,413,413
BEGIN DESCRIPTION:
Rocky Creek Tributary 37.0
END DESCRIPTION:
XS GIS Cut Line= 3
        2508475.     13870075.01        2508375.       13869475.
        2508225.     13869174.99
#Sta/Elev= 30
  4396.5  512.43  4406.6  512.14  4437.1  509.75  4457.3  509.48    4508  505.95
  4538.4  505.11  4558.7  503.57  4599.3  501.94  4629.7  501.64    4650  499.94
  4680.4  499.09  4703.2   497.9  4720.9  496.56  4964.2  495.94  4971.8   496.3
  5011.2  495.88  5011.4  495.38  5014.9  495.38  5015.2  495.88  5041.1  496.31
  5080.3     496  5161.3   496.5  5175.3  497.31  5213.1  500.91  5236.6  503.08
  5250.8  503.94  5259.1  505.04  5287.1  507.26  5303.9  509.56  5340.2  513.13
#Mann= 6 ,-1 , 0
  4396.5     .07       0  4703.2    .033       0  5011.2    .033       0
  5015.2    .033       0  5213.1     .07       0  5236.6     .05       0
Bank Sta=5011.2,5015.2
XS Rating Curve= 0 ,0
Exp/Cntr=0.3,0.1

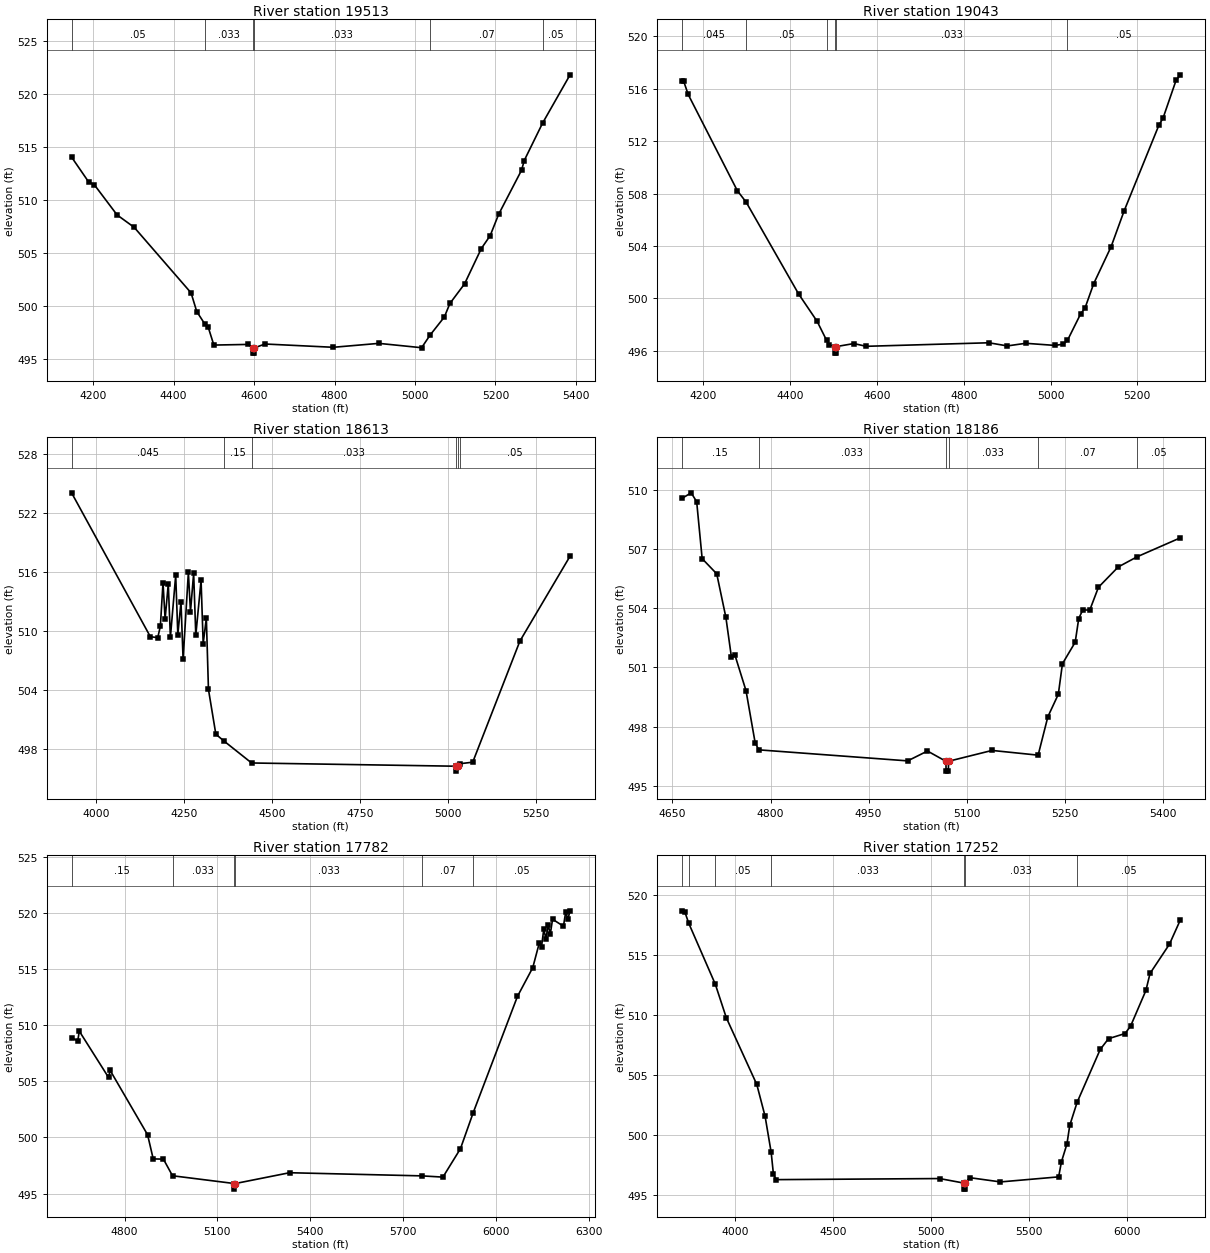
Type RM Length L Ch R = 1 ,19513   ,470,470,470
BEGIN DESCRIPTION:
Rocky Creek Tributary 36.0
END DESCRIPTION:
XS GIS Cut Line= 3
      2509175.01     13869825.01        2508575.       13869225.
      2508275.04     13868975.03
#Sta/Elev= 30
  4146.4  514.05  4188.8  511.71    4203  511.44  4259.5   508.6    4302  507.43
  4443.4  501.25  4457.5  499.49  4477.1  498.34  4485.8  498.04    4500  496.33
  4584.8  496.39    4597  496.07  4597.2  495.57  4600.7  495.57    4601  496.07
  4627.2  496.43  4796.9  496.12  4910.1  496.49  5016.4  496.08  5037.7  497.28
    5073  498.98  5086.7  500.25  5123.2   502.1  5164.8  505.43  5186.9  506.65
  5207.8  508.65    5265  512.83  5271.5  513.73    5317  517.25  5385.4  521.81
#Mann= 6 ,-1 , 0
  4146.4     .05       0  4477.1    .033       0    4597    .033       0
    4601    .033       0  5037.7     .07       0    5317     .05       0
Bank Sta=4597,4601
XS Rating Curve= 0 ,0
Exp/Cntr=0.3,0.1

Type RM Length L Ch R = 1 ,19043   ,430,430,430
BEGIN DESCRIPTION:
Rocky Creek Tributary 35.0
END DESCRIPTION:
XS GIS Cut Line= 3
      2509475.02     13869475.02        2508875.       13868875.
      2508574.96       13868875.
#Sta/Elev= 30
  4150.8  516.59  4154.4  516.59    4165  515.56  4278.1  508.23  4298.7  507.34
  4419.5  500.34    4462  498.26  4483.7  496.82  4490.2  496.47  4502.4  496.33
  4502.6  495.83  4506.1  495.83  4506.4  496.33  4546.8  496.56  4575.1  496.35
  4857.9  496.62  4900.4  496.38  4942.8  496.58  5009.4  496.42  5029.4  496.51
  5038.9   496.8  5069.4  498.83  5079.4  499.27  5099.4  501.13  5139.4  503.94
  5169.4  506.67  5249.4   513.2  5259.4  513.78  5289.4  516.66  5299.4  517.06
#Mann= 6 ,-1 , 0
  4150.8    .045       0  4298.7     .05       0  4483.7    .033       0
  4502.4    .033       0  4506.4    .033       0  5038.9     .05       0
Bank Sta=4502.4,4506.4
XS Rating Curve= 0 ,0
Exp/Cntr=0.3,0.1

Type RM Length L Ch R = 1 ,18613   ,427,427,427
BEGIN DESCRIPTION:
Rocky Creek Tributary 34.0
END DESCRIPTION:
XS GIS Cut Line= 3
      2509675.01     13869475.01        2509075.       13868575.
      2508774.99     13868424.99
#Sta/Elev= 30
  3929.7  524.08  4153.6  509.43  4174.6  509.33  4182.1   510.5  4189.6  514.94
  4195.6  511.24  4204.6  514.81  4210.6  509.37  4225.7  515.69  4231.7  509.65
  4240.7  512.95  4246.7  507.12  4261.7  515.97  4267.7  511.98  4276.7  515.88
  4282.8  509.58  4297.8  515.17  4303.8  508.73  4312.8  511.33  4318.8  504.06
  4339.8   499.5  4362.4  498.82  4441.5  496.57  5023.4  496.24  5023.6  495.74
  5027.4  496.24  5034.8   496.5  5070.1  496.65  5204.2  508.98  5346.8  517.63
#Mann= 6 ,-1 , 0
  3929.7    .045       0  4362.4     .15       0  4441.5    .033       0
  5023.4    .033       0  5027.4    .033       0  5034.8     .05       0
Bank Sta=5023.4,5027.4
XS Rating Curve= 0 ,0
Exp/Cntr=0.3,0.1

Type RM Length L Ch R = 1 ,18186   ,404,404,404
BEGIN DESCRIPTION:
Rocky Creek Tributary 33.0
END DESCRIPTION:
XS GIS Cut Line= 3
      2509725.03     13868575.01        2509425.       13868425.
      2509025.04     13868275.01
#Sta/Elev= 30
  4664.6  509.58  4678.6  509.86    4687  509.41  4695.4  506.52  4717.7  505.75
  4731.7  503.54  4740.1  501.54  4745.7  501.61  4762.5  499.82  4776.4  497.19
  4781.9  496.82  5009.8  496.26  5040.1  496.76  5068.3  496.24  5068.6  495.74
  5072.1  495.74  5072.3  496.24  5138.9  496.79  5209.4  496.55  5224.3   498.5
  5240.3  499.64  5246.6  501.19  5266.1  502.28  5271.5  503.48  5277.7  503.92
  5288.4  503.91  5301.7  505.07    5332   506.1  5361.1  506.62  5427.2  507.58
#Mann= 6 ,-1 , 0
  4664.6     .15       0  4781.9    .033       0  5068.3    .033       0
  5072.3    .033       0  5209.4     .07       0  5361.1     .05       0
Bank Sta=5068.3,5072.3
XS Rating Curve= 0 ,0
Exp/Cntr=0.3,0.1

Type RM Length L Ch R = 1 ,17782   ,530,530,530
BEGIN DESCRIPTION:
Rocky Creek Tributary 32.0
END DESCRIPTION:
XS GIS Cut Line= 3
      2509825.01     13868525.05      2509757.54     13868205.46
      2508874.97     13867274.97
#Sta/Elev= 30
  4629.2  508.89    4649  508.58  4654.1  509.46  4748.5  505.34  4753.6  505.97
  4874.5  500.24  4892.7  498.09  4925.6  498.07    4955  496.59    5154   495.9
  5154.3   495.4    5158   495.9  5332.8  496.86  5759.4  496.58  5827.9  496.47
  5884.5     499  5925.6   502.2  6068.6  512.56  6117.9  515.11  6139.3  517.34
  6146.2  516.97  6153.5  518.53  6160.4  517.68  6167.7  518.91  6174.6  518.11
  6181.8  519.42    6217   518.8  6224.3  520.08  6231.2  519.41  6238.3  520.17
#Mann= 6 ,-1 , 0
  4629.2     .15       0    4955    .033       0    5154    .033       0
    5158    .033       0  5759.4     .07       0  5925.6     .05       0
Bank Sta=5154,5158
XS Rating Curve= 0 ,0
Exp/Cntr=0.3,0.1

Type RM Length L Ch R = 1 ,17252   ,624,624,624
BEGIN DESCRIPTION:
Rocky Creek Tributary 31.0
END DESCRIPTION:
XS GIS Cut Line= 3
      2510874.97     13868674.97        2509975.       13867775.
      2509075.03     13866875.03
#Sta/Elev= 30
  3727.6  518.67  3741.7  518.59    3762  517.63  3897.6  512.56  3953.8  509.77
  4109.4  504.22  4151.8  501.57  4182.9  498.56  4194.3  496.76  4208.4   496.3
  5042.8  496.39  5168.1  496.01  5168.3  495.51  5171.8  495.51  5172.1  496.01
  5198.3  496.46  5353.9  496.11  5650.9  496.53    5665  497.78  5693.3  499.27
  5707.5  500.81  5745.1  502.73    5863  507.13  5905.5  508.03  5990.3  508.46
  6018.6  509.09  6096.4  512.04  6117.6  513.46  6216.6  515.89  6273.1  517.94
#Mann= 7 ,-1 , 0
  3727.6     .05       0    3762    .035       0  3897.6     .05       0
  4182.9    .033       0  5168.1    .033       0  5172.1    .033       0
  5745.1     .05       0
Bank Sta=5168.1,5172.1
XS Rating Curve= 0 ,0
Exp/Cntr=0.3,0.1

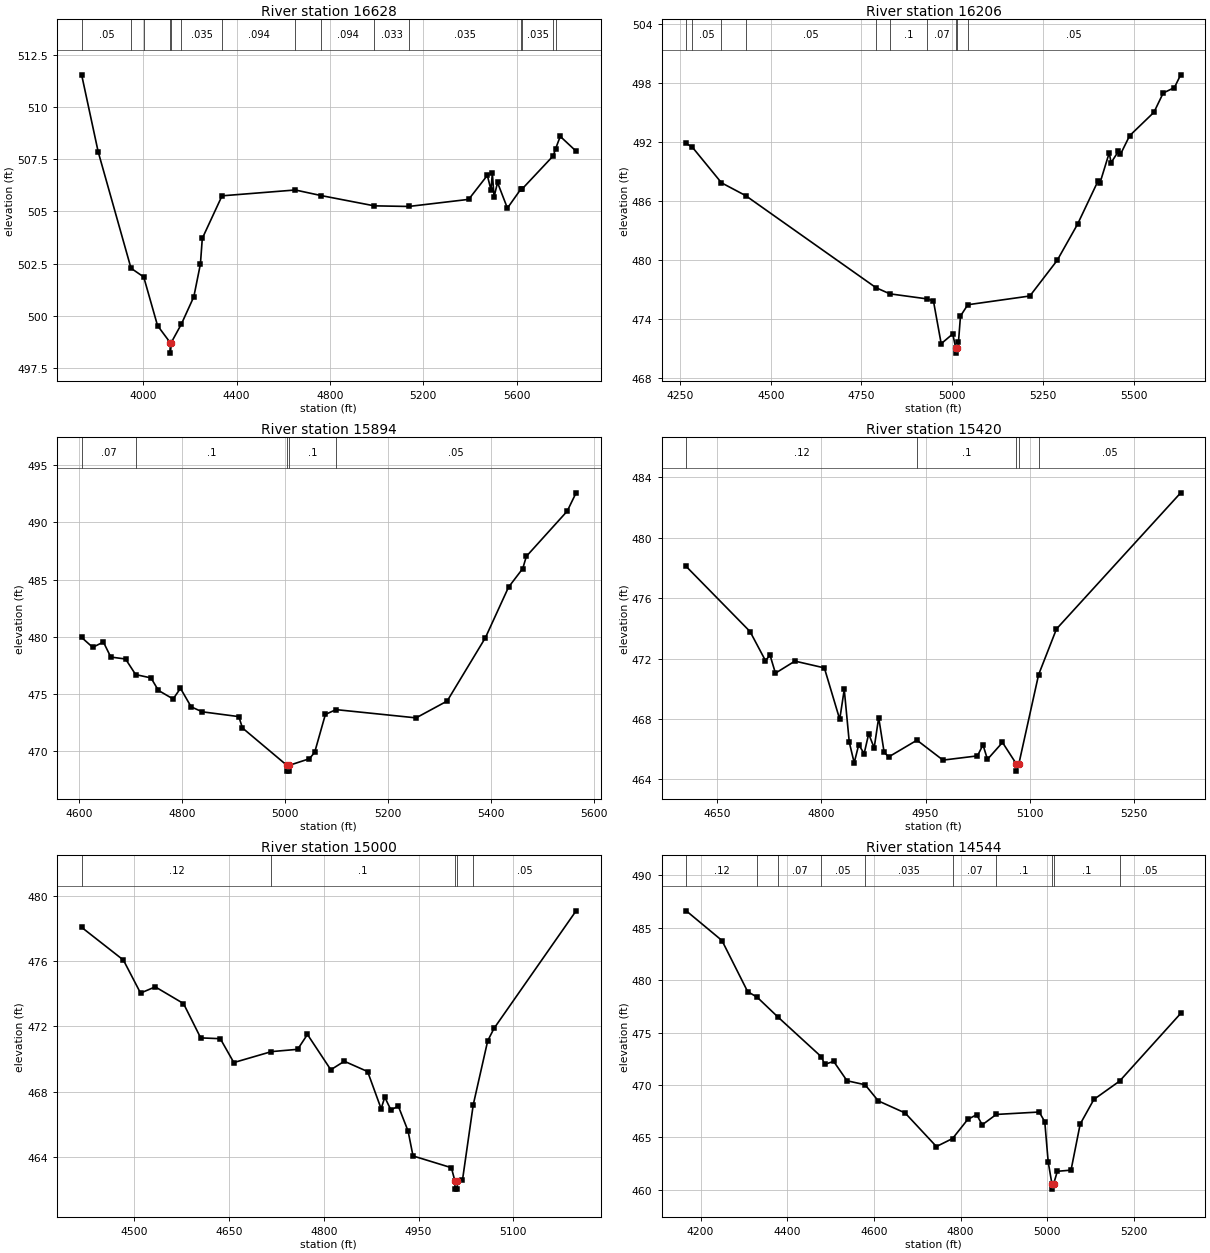
Type RM Length L Ch R = 1 ,16628   ,422,422,422
BEGIN DESCRIPTION:
Rocky Creek Tributary 30.0
END DESCRIPTION:
XS GIS Cut Line= 6
      2510874.99     13868324.99      2510508.53     13867958.53
      2510279.93     13867508.94      2509940.83      13867183.6
      2509701.54     13867042.38      2509450.55     13866803.29
#Sta/Elev= 30
  3735.7  511.55  3806.4  507.87  3947.3  502.28  4001.8  501.86    4061  499.53
  4115.5  498.71  4115.8  498.21  4119.5  498.71  4163.1   499.6  4216.5  500.91
  4244.8  502.48  4252.9  503.71  4337.5  505.75  4651.6  506.03  4763.2  505.76
  4990.2  505.27  5137.7  505.24  5394.7  505.58  5474.7  506.73  5490.3  506.03
  5496.2  506.83  5503.6  505.69  5518.3  506.39  5560.7  505.16  5618.3  506.07
  5624.8  506.09  5757.4  507.67  5767.1     508  5787.2   508.6  5855.2  507.89
#Mann= 15 ,-1 , 0
  3735.7     .05       0  3947.3    .035       0  4001.8     .05       0
  4115.5    .033       0  4119.5     .05       0  4163.1    .035       0
  4337.5    .094       0  4651.6     .05       0  4763.2    .094       0
  4990.2    .033       0  5137.7    .035       0  5618.3     .05       0
  5624.8    .035       0  5757.4     .05       0  5767.1    .035       0
Bank Sta=4115.5,4119.5
XS Rating Curve= 0 ,0
Exp/Cntr=0.3,0.1

Type RM Length L Ch R = 1 ,16206   ,312,312,312
BEGIN DESCRIPTION:
Rocky Creek Tributary 29.0
END DESCRIPTION:
XS GIS Cut Line= 3
       2510903.1     13867559.32      2510513.63     13867179.01
       2509743.8     13866904.08
#Sta/Elev= 30
  4267.3  491.84  4284.2  491.46  4364.4  487.84  4430.8  486.54  4790.1  477.17
  4828.1  476.55  4931.6  476.03  4948.2  475.82  4969.5  471.48  5001.3  472.47
  5009.7  471.02    5010  470.52  5013.7  471.02  5017.1  471.64  5022.6  474.29
  5042.8  475.44  5213.7  476.33  5288.9  479.95  5345.2  483.64  5401.4  488.02
  5406.8  487.82  5432.2  490.88  5437.5  489.89  5457.7  491.05    5463  490.72
  5488.5  492.63  5555.4  495.01  5580.9  496.97  5611.7  497.52  5629.1  498.82
#Mann= 10 ,-1 , 0
  4267.3     .07       0  4284.2     .05       0  4364.4     .07       0
  4430.8     .05       0  4790.1     .07       0  4828.1      .1       0
  4931.6     .07       0  5009.7     .05       0  5013.7     .07       0
  5042.8     .05       0
Bank Sta=5009.7,5013.7
XS Rating Curve= 0 ,0
Exp/Cntr=0.3,0.1

Type RM Length L Ch R = 1 ,15894   ,474,474,474
BEGIN DESCRIPTION:
Rocky Creek Tributary 28.0
END DESCRIPTION:
XS GIS Cut Line= 3
      2510775.01     13867175.01        2510525.       13866875.
      2509975.02       13866725.
#Sta/Elev= 30
  4605.5  479.94    4627  479.08  4647.8  479.54  4662.1  478.23  4690.8  478.06
  4710.4   476.7  4740.2  476.41  4754.6  475.32  4783.2  474.57  4797.5   475.5
  4818.3  473.88  4839.8  473.45  4910.8  473.03  4917.9  472.04  5004.4  468.77
  5004.6  468.27  5008.1  468.27  5008.4  468.77  5047.9  469.35  5058.2  469.91
    5079  473.22  5099.7  473.64  5255.2  472.92  5315.6  474.39  5389.9  479.92
  5434.8  484.33  5462.5  485.96  5469.4  487.02  5548.8  490.97  5566.1  492.57
#Mann= 5 ,-1 , 0
  4605.5     .07       0  4710.4      .1       0  5004.4     .05       0
  5008.4      .1       0  5099.7     .05       0
Bank Sta=5004.4,5008.4
XS Rating Curve= 0 ,0
Exp/Cntr=0.3,0.1

Type RM Length L Ch R = 1 ,15420   ,420,420,420
BEGIN DESCRIPTION:
Rocky Creek Tributary 27.0
END DESCRIPTION:
XS GIS Cut Line= 3
      2510824.97     13866724.97        2510525.       13866475.
      2510275.02     13866275.01
#Sta/Elev= 30
    4606   478.1  4697.7  473.79  4719.9  471.86  4726.4  472.23  4734.2  471.03
  4762.2  471.83  4804.5  471.38  4826.6  467.97  4833.1  469.95  4840.3  466.46
  4847.4  465.09  4853.9  466.29  4861.7   465.7  4868.2  467.01  4876.1  466.08
  4882.6  468.09  4890.4  465.79  4896.9  465.48  4937.6  466.59    4975  465.27
  5024.5  465.55  5032.5  466.28  5038.9  465.32  5060.5  466.44  5080.1  465.04
  5080.4  464.54  5084.1  465.04  5112.4  470.93  5138.1  473.96  5316.6  482.98
#Mann= 5 ,-1 , 0
    4606     .12       0  4937.6      .1       0  5080.1     .05       0
  5084.1      .1       0  5112.4     .05       0
Bank Sta=5080.1,5084.1
XS Rating Curve= 0 ,0
Exp/Cntr=0.3,0.1

Type RM Length L Ch R = 1 ,15000   ,456,456,456
BEGIN DESCRIPTION:
Rocky Creek Tributary 26.0
END DESCRIPTION:
XS GIS Cut Line= 3
      2510925.01     13866625.01        2510625.       13866125.
      2510425.01       13866125.
#Sta/Elev= 30
  4416.4  478.06  4482.5  476.06  4509.7  474.04    4533  474.42  4577.7   473.4
  4604.9   471.3    4636  471.25  4657.4  469.79    4717  470.46  4758.5   470.6
    4774  471.51    4811  469.35  4832.4  469.87  4869.3  469.24  4890.7  466.97
  4896.5  467.67  4906.2  466.89  4917.9  467.13  4933.4   465.6  4941.2  464.08
    5002  463.36  5007.5  462.55  5007.8  462.05  5011.3  462.05  5011.5  462.55
  5019.5  462.59  5036.6  467.21  5059.5  471.12  5069.5  471.88  5199.5  479.07
#Mann= 5 ,-1 , 0
  4416.4     .12       0    4717      .1       0  5007.5     .05       0
  5011.5      .1       0  5036.6     .05       0
Bank Sta=5007.5,5011.5
XS Rating Curve= 0 ,0
Exp/Cntr=0.3,0.1

Type RM Length L Ch R = 1 ,14544   ,445,445,445
BEGIN DESCRIPTION:
Rocky Creek Tributary 25.0
END DESCRIPTION:
XS GIS Cut Line= 3
      2511624.97     13865974.99        2510825.       13865775.
      2510525.02     13865675.01
#Sta/Elev= 30
    4167   486.6  4249.4  483.77  4308.7   478.9  4330.8  478.36    4378   476.5
  4478.9  472.68  4486.5  471.96  4507.1  472.25    4538   470.4  4579.7  470.02
  4610.2  468.48    4672  467.33  4744.2  464.13  4781.4  464.89  4816.4  466.71
    4837  467.17  4849.9   466.2  4882.3  467.19  4981.3  467.42  4994.2   466.5
  5002.1  462.67  5010.7  460.57  5010.9  460.07  5014.7  460.57  5023.2  461.77
  5054.8  461.88  5075.9  466.27  5107.5  468.62  5166.9  470.37  5307.8  476.82
#Mann= 10 ,-1 , 0
    4167     .12       0  4330.8     .05       0    4378     .07       0
  4478.9     .05       0  4579.7    .035       0  4781.4     .07       0
  4882.3      .1       0  5010.7     .05       0  5014.7      .1       0
  5166.9     .05       0
Bank Sta=5010.7,5014.7
XS Rating Curve= 0 ,0
Exp/Cntr=0.3,0.1

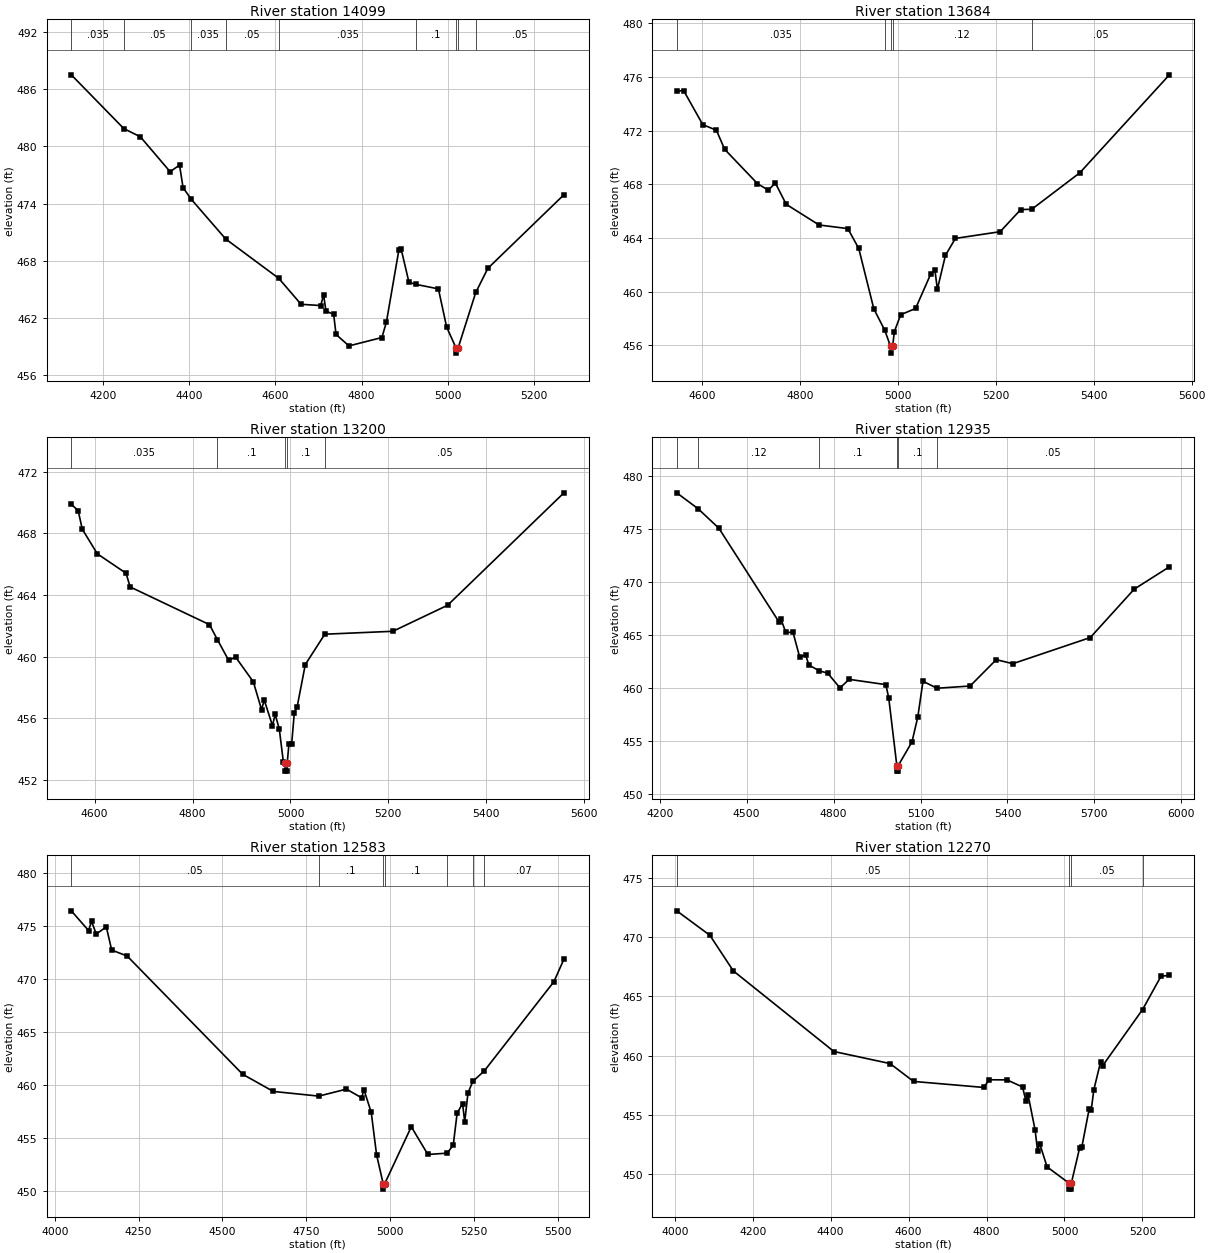
Type RM Length L Ch R = 1 ,14099   ,415,415,415
BEGIN DESCRIPTION:
Rocky Creek Tributary 24.0
END DESCRIPTION:
XS GIS Cut Line= 3
      2511674.99     13865724.99        2510875.       13865375.
      2510624.96     13865274.98
#Sta/Elev= 30
  4126.8  487.52  4248.6  481.87    4287  481.01    4356  477.34  4377.8  478.04
    4386  475.67  4404.7  474.46  4484.9  470.27  4607.9  466.14  4659.7  463.41
  4705.3  463.28  4711.9  464.42  4717.4   462.7  4735.3  462.35  4740.8  460.24
  4770.8  459.04  4847.2  459.92  4857.7  461.56  4886.6  469.14    4892  469.17
  4909.9  465.72  4926.6   465.5  4978.2  465.03  4997.3  461.02  5019.5  458.78
  5019.8  458.28  5023.6  458.78  5064.8  464.65  5092.9  467.19  5269.3  474.92
#Mann= 9 ,-1 , 0
  4126.8    .035       0  4248.6     .05       0  4404.7    .035       0
  4484.9     .05       0  4607.9    .035       0  4926.6      .1       0
  5019.5     .05       0  5023.6      .1       0  5064.8     .05       0
Bank Sta=5019.5,5023.6
XS Rating Curve= 0 ,0
Exp/Cntr=0.3,0.1

Type RM Length L Ch R = 1 ,13684   ,484,484,484
BEGIN DESCRIPTION:
Rocky Creek Tributary 23.0
END DESCRIPTION:
XS GIS Cut Line= 3
      2511524.98     13865274.99        2511125.       13865075.
      2510575.01       13865175.
#Sta/Elev= 30
  4548.3  474.93  4562.3  474.98  4601.4  472.44  4629.3  472.02  4646.1   470.6
  4713.2  468.04  4735.5  467.55  4749.5   468.1  4771.9   466.5    4839  464.96
  4897.7  464.69    4920  463.21  4950.8  458.71  4973.3   457.1    4985  455.91
  4985.3  455.41  4989.2  455.91  4992.7  457.01  5005.7  458.27  5036.1  458.74
  5066.6  461.27  5075.5  461.62  5080.6  460.17  5097.1   462.7  5117.5  463.96
  5208.9  464.46  5250.9  466.11  5273.4  466.13  5371.6  468.85  5554.5  476.15
#Mann= 5 ,-1 , 0
  4548.3    .035       0  4973.3     .12       0    4985     .05       0
  4989.2     .12       0  5273.4     .05       0
Bank Sta=4985,4989.2
XS Rating Curve= 0 ,0
Exp/Cntr=0.3,0.1

Type RM Length L Ch R = 1 ,13200   ,265,265,265
BEGIN DESCRIPTION:
Rocky Creek Tributary 22.0
END DESCRIPTION:
XS GIS Cut Line= 3
      2511525.04     13864825.02        2511125.       13864625.
      2510624.98     13864875.01
#Sta/Elev= 30
  4552.3  469.89  4566.3  469.49  4574.7  468.28  4605.5  466.68  4664.1  465.42
  4672.5  464.53  4834.6  462.08  4850.9   461.1  4873.8  459.76  4887.8  459.98
  4924.1  458.37  4940.9  456.57  4946.5  457.18  4963.2  455.53  4968.8  456.25
  4977.2   455.3  4985.6  453.14    4989  453.07  4989.3  452.57    4993  452.57
  4993.3  453.07  4996.8  454.32  5002.4  454.32  5007.9  456.37  5013.5  456.72
  5030.3  459.49  5070.1  461.46  5209.2  461.65    5321  463.34  5558.6  470.64
#Mann= 5 ,-1 , 0
  4552.3    .035       0  4850.9      .1       0    4989     .05       0
  4993.3      .1       0  5070.1     .05       0
Bank Sta=4989,4993.3
XS Rating Curve= 0 ,0
Exp/Cntr=0.3,0.1

Type RM Length L Ch R = 1 ,12935   ,352,352,352
BEGIN DESCRIPTION:
B20301
END DESCRIPTION:
XS GIS Cut Line= 4
      2511920.43     13864635.82      2511278.88     13864388.37
      2510825.22     13864420.44       2510519.1     13864886.49
#Sta/Elev= 30
  4258.8  478.43  4332.7  476.92    4404  475.09  4610.7  466.27  4618.3  466.49
  4635.3  465.24  4659.9  465.26  4682.6  462.95  4704.1  463.09  4714.5  462.16
  4750.6  461.62  4779.8  461.39    4822     460  4853.6  460.81  4980.4  460.31
  4990.4  459.04  5018.3  452.64  5018.6  452.14  5022.3  452.14  5022.6  452.64
  5070.6  454.91  5090.7  457.27  5108.5  460.63  5156.8  459.97  5271.1  460.18
  5361.3  462.67  5418.6  462.29  5685.9  464.76  5837.4  469.33  5958.8  471.44
#Mann= 6 ,-1 , 0
  4258.8     .05       0  4332.7     .12       0  4750.6      .1       0
  5018.3     .05       0  5022.6      .1       0  5156.8     .05       0
Bank Sta=5018.3,5022.6
XS Rating Curve= 0 ,0
Exp/Cntr=0.3,0.1

Type RM Length L Ch R = 1 ,12583   ,313,313,313
BEGIN DESCRIPTION:
Rocky Creek Tributary 21.0
END DESCRIPTION:
XS GIS Cut Line= 3
      2512089.92       13864480.      2511388.85     13864159.25
      2510775.01       13863825.
#Sta/Elev= 30
  4049.2  476.44  4100.7  474.58  4109.6  475.45  4123.7  474.25  4153.6  474.93
  4169.7  472.74  4215.8  472.18  4560.5  461.03    4652  459.41  4787.8  458.97
  4870.1  459.63  4915.6  458.81  4922.2  459.59  4944.1  457.44  4960.2  453.42
  4979.9   450.7  4980.2   450.2  4984.2   450.7  5063.7  456.08  5113.1  453.47
  5171.1  453.59  5188.9  454.37  5200.5  457.37  5216.6  458.27  5223.1  456.54
  5232.8  459.27  5247.4  460.36  5281.6  461.35  5489.2  469.76  5519.1  471.88
#Mann= 7 ,-1 , 0
  4049.2     .05       0  4787.8      .1       0  4979.9     .05       0
  4984.2      .1       0  5171.1     .07       0  5247.4      .1       0
  5281.6     .07       0
Bank Sta=4979.9,4984.2
XS Rating Curve= 0 ,0
Exp/Cntr=0.3,0.1

Type RM Length L Ch R = 1 ,12270   ,476,476,476
BEGIN DESCRIPTION:
Rocky Creek Tributary 20.0
END DESCRIPTION:
XS GIS Cut Line= 3
      2512199.91     13864140.91        2511275.       13863775.
      2511025.02     13863675.01
#Sta/Elev= 30
  4005.3  472.24  4090.3  470.17  4150.4  467.16  4408.5  460.34  4552.6  459.32
  4612.8  457.81  4793.2   457.3  4806.4  457.95  4852.6  457.94  4892.4  457.34
  4901.3  456.14  4906.7  456.66  4924.7   453.7    4931  451.93  4936.4  452.55
  4955.4  450.58  5011.9   449.2  5012.4   448.7  5017.2   448.7  5017.6   449.2
    5039   452.2  5044.4  452.23  5063.2  455.45  5068.6  455.37  5075.4  457.11
  5092.9  459.49  5098.2  459.15  5200.4  463.89  5247.7  466.71  5269.2  466.78
#Mann= 4 ,-1 , 0
  4005.3     .05       0  5011.9     .05       0  5017.6     .05       0
  5200.4      .1       0
Bank Sta=5011.9,5017.6
XS Rating Curve= 0 ,0
Exp/Cntr=0.3,0.1

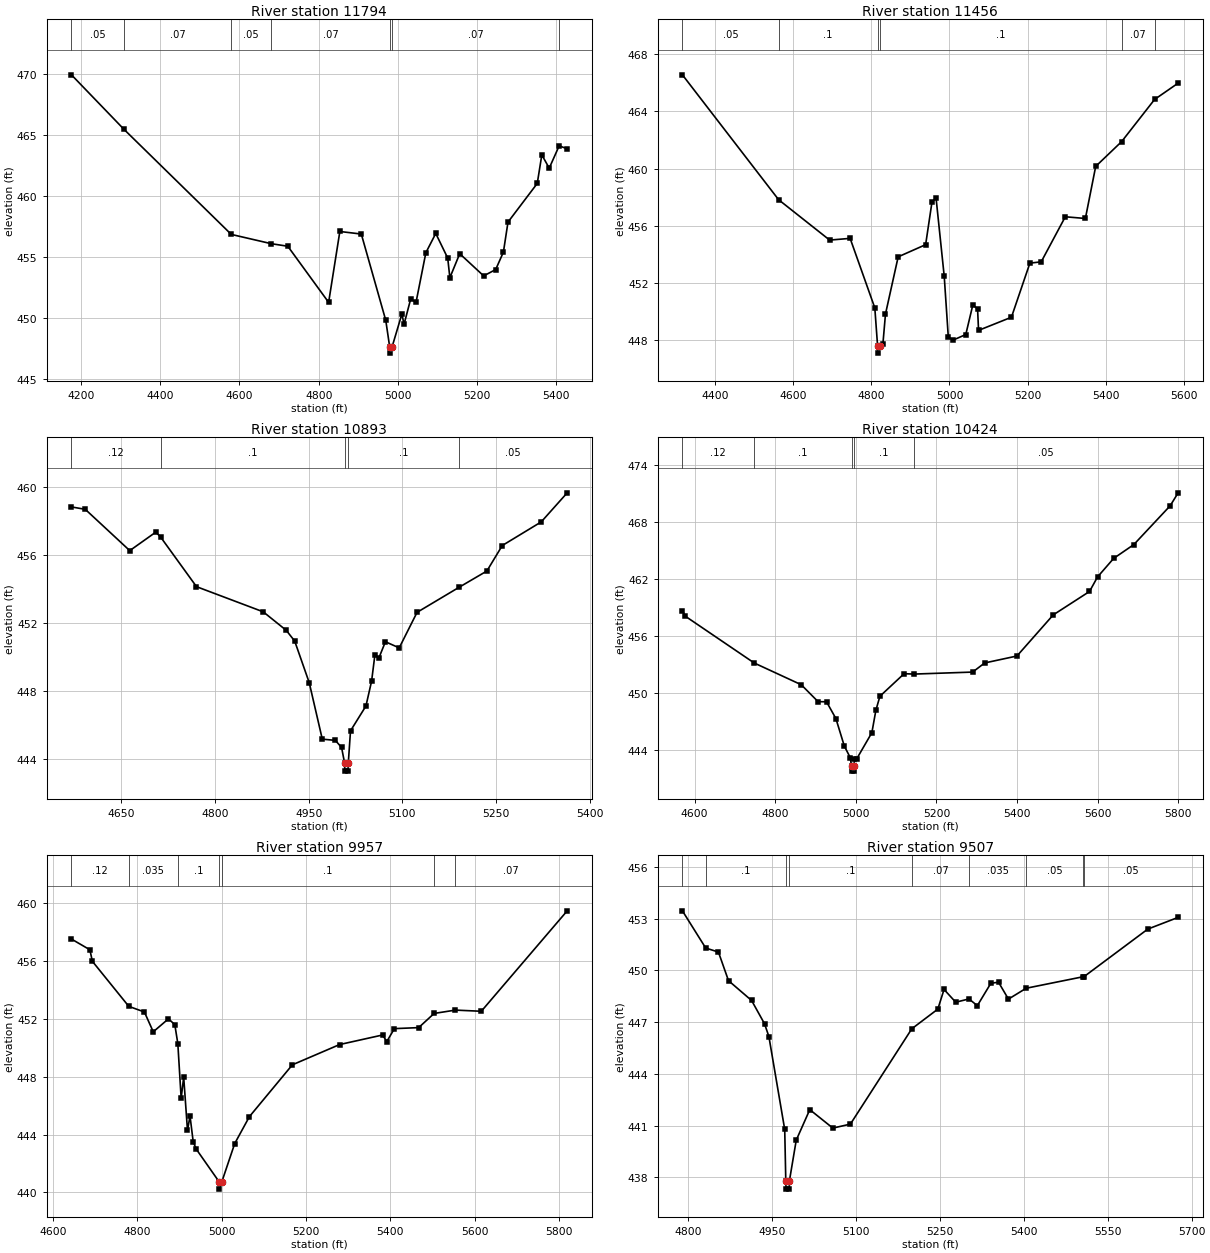
Type RM Length L Ch R = 1 ,11794   ,338,338,338
BEGIN DESCRIPTION:
Rocky Creek Tributary 19.0
END DESCRIPTION:
XS GIS Cut Line= 3
        2512275.       13863575.        2511475.       13863375.
      2511075.02     13863524.99
#Sta/Elev= 30
  4175.7   469.9  4308.1  465.44  4579.3  456.82  4680.2  456.06    4722  455.85
  4825.1  451.25  4853.4  457.06  4907.6  456.85  4969.4  449.77  4979.3  447.59
  4979.8  447.09  4985.2  447.59  5010.1   450.3  5015.5  449.45  5032.4  451.54
  5045.7  451.24  5070.6  455.32  5095.6   456.9  5125.8  454.88  5131.2  453.27
  5156.1  455.24  5216.6  453.42  5246.9  453.94  5266.4  455.37    5278  457.83
  5351.9     461  5363.4  463.34  5382.1  462.25  5407.2  464.08  5427.5  463.84
#Mann= 7 ,-1 , 0
  4175.7     .05       0  4308.1     .07       0  4579.3     .05       0
  4680.2     .07       0  4979.3     .05       0  4985.2     .07       0
  5407.2     .07       0
Bank Sta=4979.3,4985.2
XS Rating Curve= 0 ,0
Exp/Cntr=0.3,0.1

Type RM Length L Ch R = 1 ,11456   ,563,563,563
BEGIN DESCRIPTION:
Rocky Creek Tributary 18.0
END DESCRIPTION:
XS GIS Cut Line= 3
      2512224.95     13863274.99      2511503.41     13863050.32
      2511003.94     13862931.18
#Sta/Elev= 30
  4316.3  466.56  4562.7  457.83  4693.3  455.01  4745.7  455.13  4808.9  450.27
    4816  447.61  4816.5  447.11    4822  447.61  4829.5  447.72  4836.2  449.84
  4868.7  453.84    4939  454.69  4955.1  457.64  4965.6  457.98  4986.6  452.48
    4997  448.25  5009.3  448.02  5041.8  448.41  5059.9  450.49    5072  450.19
  5074.5   448.7  5158.7  449.62  5205.9   453.4  5234.9  453.49  5296.6  456.64
    5348  456.52  5374.4  460.16  5440.7  461.89  5525.2  464.84  5585.5  465.98
#Mann= 6 ,-1 , 0
  4316.3     .05       0  4562.7      .1       0    4816     .05       0
    4822      .1       0  5440.7     .07       0  5525.2      .1       0
Bank Sta=4816,4822
XS Rating Curve= 0 ,0
Exp/Cntr=0.3,0.1

Type RM Length L Ch R = 1 ,10893   ,469,469,469
BEGIN DESCRIPTION:
Rocky Creek Tributary 17.0
END DESCRIPTION:
XS GIS Cut Line= 3
      2512174.99     13862974.99        2511825.       13862725.
        2511475.       13862625.
#Sta/Elev= 30
  4569.9  458.82    4592  458.68  4663.3  456.25  4705.1  457.34  4712.7  457.05
  4770.2  454.13  4877.1  452.65    4914  451.56  4927.5  450.93  4950.8  448.48
  4971.7  445.16  4992.6  445.09  5002.6  444.67  5007.3  443.78  5007.8  443.28
  5012.9  443.28  5013.4  443.78  5016.9  445.65  5041.6  447.11  5050.7  448.58
  5055.9   450.1  5062.4  449.94  5072.8  450.89  5094.9  450.53  5123.5  452.62
  5191.1   454.1  5235.3  455.05    5260  456.55  5322.4  457.94    5364  459.65
#Mann= 5 ,-1 , 0
  4569.9     .12       0  4712.7      .1       0  5007.3     .05       0
  5013.4      .1       0  5191.1     .05       0
Bank Sta=5007.3,5013.4
XS Rating Curve= 0 ,0
Exp/Cntr=0.3,0.1

Type RM Length L Ch R = 1 ,10424   ,467,467,467
BEGIN DESCRIPTION:
Rocky Creek Tributary 16.0
END DESCRIPTION:
XS GIS Cut Line= 3
      2512424.97     13862624.98        2512075.       13862375.
      2511274.98       13862375.
#Sta/Elev= 30
  4569.6  458.68  4576.9  458.09    4748  453.17  4864.5  450.89  4906.3  449.11
  4927.2   449.1  4950.5  447.33  4971.4  444.44  4986.2  443.22  4989.3  442.31
  4989.8  441.81  4994.9  441.81  4995.4  442.31  4996.6  443.11  5002.2  443.11
  5039.7  445.85  5049.7  448.21  5059.7  449.68  5119.7  452.05    5144  452.01
  5289.7  452.22  5319.7  453.18  5399.7  453.91  5489.7  458.23  5579.7  460.69
  5599.7  462.22  5639.7  464.17  5689.7  465.62  5779.7  469.69  5799.7  471.06
#Mann= 5 ,-1 , 0
  4569.6     .12       0    4748      .1       0  4989.3     .05       0
  4995.4      .1       0    5144     .05       0
Bank Sta=4989.3,4995.4
XS Rating Curve= 0 ,0
Exp/Cntr=0.3,0.1

Type RM Length L Ch R = 1 ,9957    ,450,450,450
BEGIN DESCRIPTION:
Rocky Creek Tributary 15.0
END DESCRIPTION:
XS GIS Cut Line= 3
      2512625.01       13862225.        2512325.       13862025.
        2511525.       13862175.
#Sta/Elev= 30
  4644.3  457.51  4687.9  456.77  4693.9  455.97  4780.1  452.86  4817.1  452.47
  4838.1   451.1  4874.2     452  4889.2  451.59  4896.3  450.29  4904.2  446.51
  4910.2  447.97  4919.2  444.29  4925.2  445.28  4932.8  443.49  4940.3  442.98
  4994.3  440.73  4994.8  440.23  5000.5  440.73  5031.1  443.38  5065.9  445.24
  5167.7  448.82  5279.6  450.22  5381.3  450.88  5391.5  450.43  5409.3  451.32
  5466.9  451.39  5503.5  452.37  5553.9   452.6  5615.3  452.52  5818.8  459.46
#Mann= 7 ,-1 , 0
  4644.3     .12       0  4780.1    .035       0  4896.3      .1       0
  4994.3     .05       0  5000.5      .1       0  5503.5     .05       0
  5553.9     .07       0
Bank Sta=4994.3,5000.5
XS Rating Curve= 0 ,0
Exp/Cntr=0.3,0.1

Type RM Length L Ch R = 1 ,9507    ,449,449,449
BEGIN DESCRIPTION:
Rocky Creek Tributary 14.0
END DESCRIPTION:
XS GIS Cut Line= 3
      2512724.96     13861724.99        2512525.       13861675.
      2511874.99       13861475.
#Sta/Elev= 30
  4789.7  453.45  4831.4  451.29  4854.1  451.06  4872.1   449.4  4913.4  448.25
  4936.5   446.9  4944.3  446.16  4972.6  440.77  4974.5  437.81    4975  437.31
  4980.6  437.31  4981.1  437.81  4993.2  440.15  5017.4  441.92  5058.6  440.85
    5090  441.08  5199.8  446.61  5246.3  447.75  5257.4  448.89  5278.3  448.15
    5302  448.34  5316.9  447.95  5341.1  449.25  5354.8  449.31  5372.5  448.33
  5404.2  448.96  5506.4  449.63  5507.1  449.62  5621.6  452.39  5675.9  453.07
#Mann= 9 ,-1 , 0
  4789.7     .12       0  4831.4      .1       0  4974.5     .05       0
  4981.1      .1       0  5199.8     .07       0    5302    .035       0
  5404.2     .05       0  5506.4     .07       0  5507.1     .05       0
Bank Sta=4974.5,4981.1
XS Rating Curve= 0 ,0
Exp/Cntr=0.3,0.1