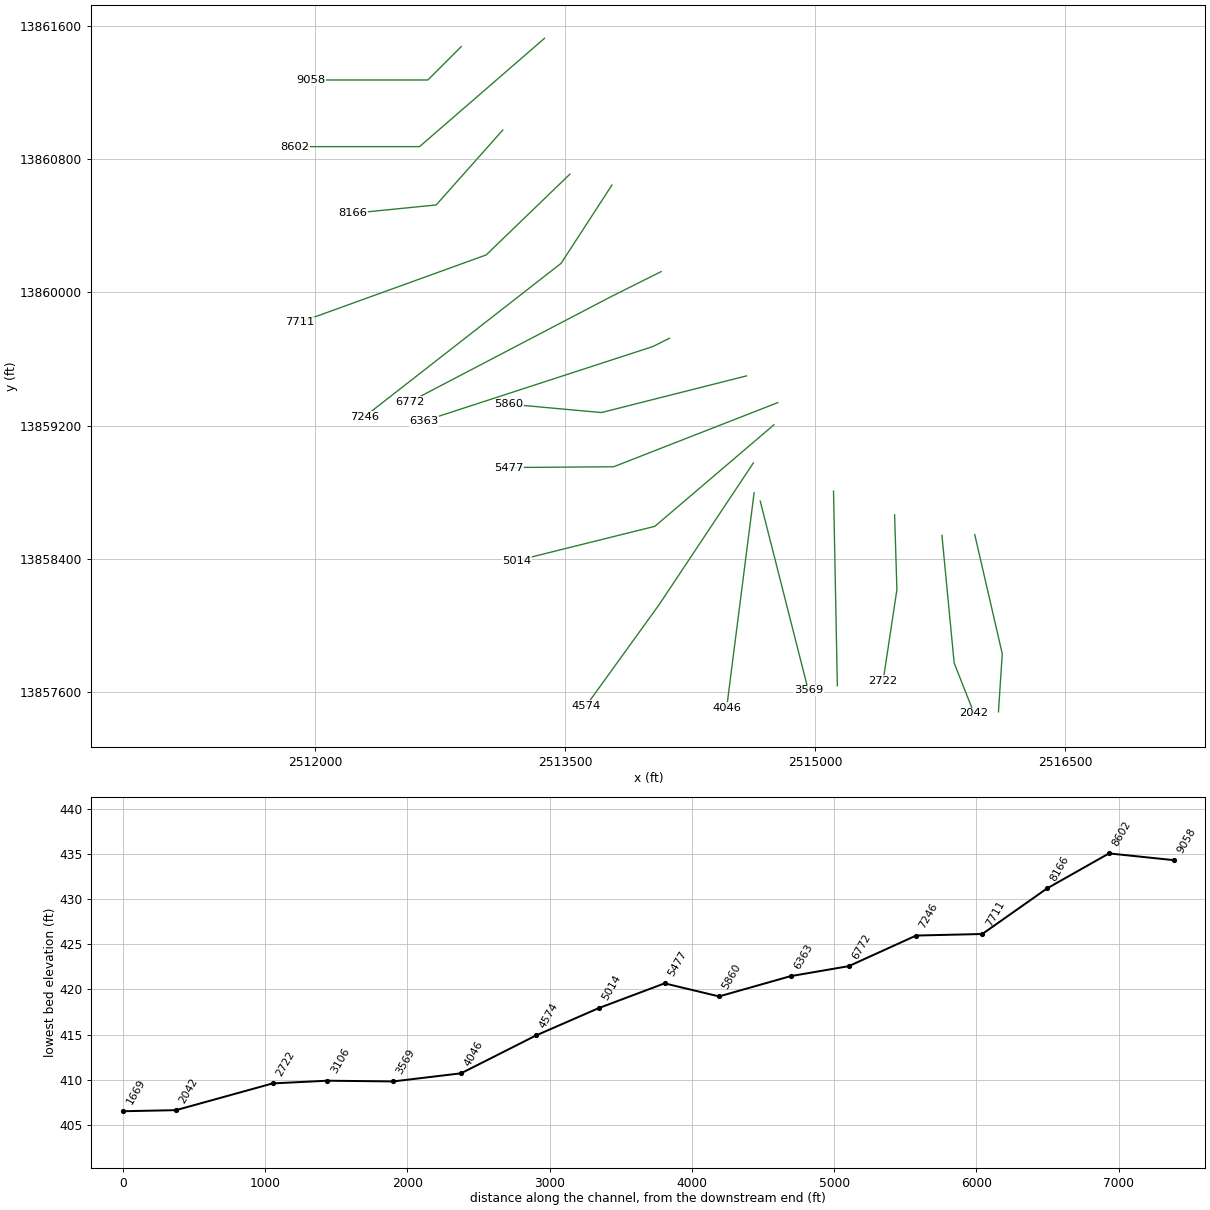
HEC-RAS study Rocky Creek Tributary.prj: Rocky Creek Tributary Base Level Engineering

--- Rocky Creek Tributary.g01 (geometry) --- (continued)

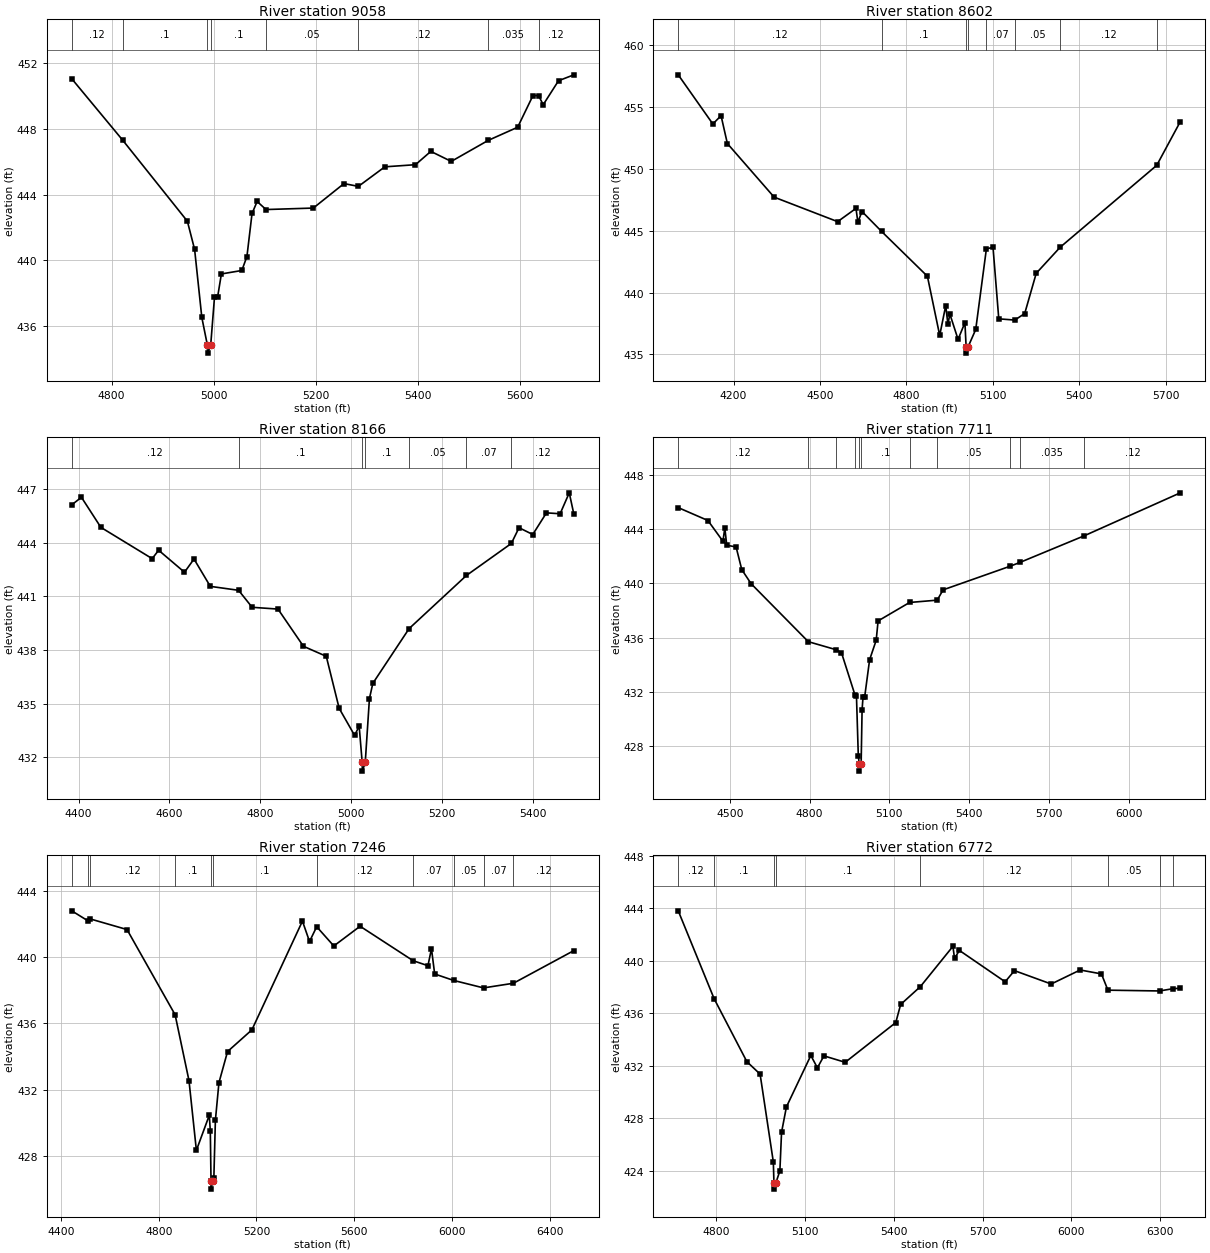
Type RM Length L Ch R = 1 ,9058    ,456,456,456
BEGIN DESCRIPTION:
Rocky Creek Tributary 13.0
END DESCRIPTION:
XS GIS Cut Line= 3
      2512875.03     13861475.03        2512675.       13861275.
      2511974.99       13861275.
#Sta/Elev= 30
  4722.2  451.06  4822.2  447.31  4948.5  442.39  4962.7  440.67  4976.8  436.53
  4987.6  434.86  4988.1  434.36  4994.2  434.86  5001.6  437.76  5007.6  437.76
  5015.1  439.18  5055.1  439.39  5065.1  440.24  5075.1  442.86  5085.1  443.59
  5102.5   443.1  5195.1  443.19  5255.1  444.68  5283.3  444.51  5335.1   445.7
  5395.1  445.83  5425.1  446.64  5465.1  446.03  5537.5  447.31  5595.1  448.11
  5625.1  450.04    5636  450.04  5645.1  449.48  5675.1  450.94  5705.1   451.3
#Mann= 8 ,-1 , 0
  4722.2     .12       0  4822.2      .1       0  4987.6     .05       0
  4994.2      .1       0  5102.5     .05       0  5283.3     .12       0
  5537.5    .035       0    5636     .12       0
Bank Sta=4987.6,4994.2
XS Rating Curve= 0 ,0
Exp/Cntr=0.3,0.1

Type RM Length L Ch R = 1 ,8602    ,436,436,436
BEGIN DESCRIPTION:
Rocky Creek Tributary 12.0
END DESCRIPTION:
XS GIS Cut Line= 3
      2513374.97     13861524.97        2512625.       13860875.
      2511875.03       13860875.
#Sta/Elev= 30
    4008  457.59  4128.1  453.62  4156.6  454.29  4178.5  452.04  4340.8  447.71
  4561.2  445.73  4624.8   446.8  4631.4  445.69  4645.7  446.55  4713.7  444.94
  4872.7  441.32  4915.4  436.54  4936.3  438.95  4943.9  437.43  4950.6  438.27
  4979.1  436.22  5002.9  437.57  5007.1  435.61  5007.6  435.11  5013.8  435.61
  5040.4  437.02  5077.4  443.53  5100.4  443.66  5120.4  437.88    5176  437.78
  5210.4  438.31  5250.4  441.56  5333.3  443.66  5668.6  450.28  5750.4  453.81
#Mann= 8 ,-1 , 0
    4008     .12       0  4713.7      .1       0  5007.1     .05       0
  5013.8      .1       0  5077.4     .07       0    5176     .05       0
  5333.3     .12       0  5668.6     .05       0
Bank Sta=5007.1,5013.8
XS Rating Curve= 0 ,0
Exp/Cntr=0.3,0.1

Type RM Length L Ch R = 1 ,8166    ,455,455,455
BEGIN DESCRIPTION:
Rocky Creek Tributary 11.0
END DESCRIPTION:
XS GIS Cut Line= 3
      2513125.02     13860975.02        2512725.       13860525.
        2512225.       13860475.
#Sta/Elev= 30
  4385.1  446.11  4406.4  446.53  4449.1  444.85    4562   443.1  4576.2  443.57
  4633.1  442.34    4654  443.08  4689.9  441.55  4752.1  441.33  4781.9  440.38
  4838.8  440.28  4894.8   438.2    4945  437.64  4973.4  434.73  5007.3  433.22
  5017.4  433.73    5024  431.72  5024.5  431.22  5030.8  431.72    5040  435.28
  5047.5  436.13  5127.3  439.19  5253.4  442.16  5352.2  443.95  5369.1  444.83
  5399.3  444.45  5429.4  445.66  5459.5  445.61  5479.6  446.78  5489.7  445.59
#Mann= 7 ,-1 , 0
  4385.1     .12       0  4752.1      .1       0    5024     .05       0
  5030.8      .1       0  5127.3     .05       0  5253.4     .07       0
  5352.2     .12       0
Bank Sta=5024,5030.8
XS Rating Curve= 0 ,0
Exp/Cntr=0.3,0.1

Type RM Length L Ch R = 1 ,7711    ,465,465,465
BEGIN DESCRIPTION:
Rocky Creek Tributary 10.0
END DESCRIPTION:
XS GIS Cut Line= 3
      2513527.71     13860710.02        2513025.       13860225.
      2511906.06     13859820.36
#Sta/Elev= 30
    4306  445.58  4417.6  444.63  4474.2   443.1  4481.2  444.09  4488.4  442.81
  4523.6  442.68    4545  441.01  4580.2  439.97  4795.2   435.7  4897.7  435.12
  4919.8   434.9  4971.3  431.74  4976.4  431.66  4983.3  427.27  4987.1  426.66
  4987.6  426.16  4993.9  426.66  4997.5  430.69  5001.1  431.63  5007.2  431.63
  5025.8  434.37  5050.5   435.8  5057.7  437.23  5176.2  438.59  5279.9  438.76
  5302.3  439.52  5555.5  441.27  5591.1  441.54  5833.8  443.51  6194.4  446.67
#Mann= 11 ,-1 , 0
    4306     .12       0  4795.2      .1       0  4897.7     .05       0
  4971.3      .1       0  4987.1     .05       0  4993.9      .1       0
  5176.2     .07       0  5279.9     .05       0  5555.5     .12       0
  5591.1    .035       0  5833.8     .12       0
Bank Sta=4987.1,4993.9
XS Rating Curve= 0 ,0
Exp/Cntr=0.3,0.1

Type RM Length L Ch R = 1 ,7246    ,474,474,474
BEGIN DESCRIPTION:
Rocky Creek Tributary 9.0
END DESCRIPTION:
XS GIS Cut Line= 3
      2513779.93     13860644.66        2513475.       13860175.
      2512295.74     13859255.07
#Sta/Elev= 30
  4443.9  442.78  4510.8  442.17  4519.7  442.29  4670.1  441.65    4867  436.51
  4923.8  432.54  4954.1  428.33    5007  430.45  5011.1   429.5    5014  426.49
  5014.5  425.99  5020.9  426.49  5025.6  426.65  5031.9  430.14  5046.4  432.41
  5081.7  434.29  5181.4   435.6  5388.3  442.16  5417.3  440.93  5446.7  441.82
  5516.8  440.66  5624.4  441.85  5841.5  439.77  5902.1  439.47  5916.6  440.49
  5929.7  438.97  6007.5  438.58  6129.7  438.13    6252  438.41  6499.5  440.38
#Mann= 11 ,-1 , 0
  4443.9      .1       0  4510.8    .035       0  4519.7     .12       0
    4867      .1       0    5014     .05       0  5020.9      .1       0
  5446.7     .12       0  5841.5     .07       0  6007.5     .05       0
  6129.7     .07       0    6252     .12       0
Bank Sta=5014,5020.9
XS Rating Curve= 0 ,0
Exp/Cntr=0.3,0.1

Type RM Length L Ch R = 1 ,6772    ,409,409,409
BEGIN DESCRIPTION:
Rocky Creek Tributary 8.0
END DESCRIPTION:
XS GIS Cut Line= 3
      2514074.97     13860124.98        2513775.       13859975.
      2512568.24     13859344.11
#Sta/Elev= 30
  4671.1  443.81  4792.4  437.11  4903.1  432.31  4947.8  431.36  4992.5  424.67
  4994.6  423.09  4995.1  422.59  5001.5  423.09  5014.7  423.99  5020.3  426.92
  5036.8  428.86  5119.3  432.78  5141.5  431.84  5163.6  432.75  5235.5  432.26
  5406.4  435.29  5422.9  436.67  5489.5  438.03  5599.5   441.1  5605.1  440.19
  5621.5  440.79  5776.1   438.4  5807.6  439.25  5931.8  438.23  6029.7   439.3
  6101.6     439  6123.5  437.76  6297.9   437.7  6342.7  437.87  6368.2  437.91
#Mann= 8 ,-1 , 0
  4671.1     .12       0  4792.4      .1       0  4994.6     .05       0
  5001.5      .1       0  5489.5     .12       0  6123.5     .05       0
  6297.9     .07       0  6342.7     .12       0
Bank Sta=4994.6,5001.5
XS Rating Curve= 0 ,0
Exp/Cntr=0.3,0.1

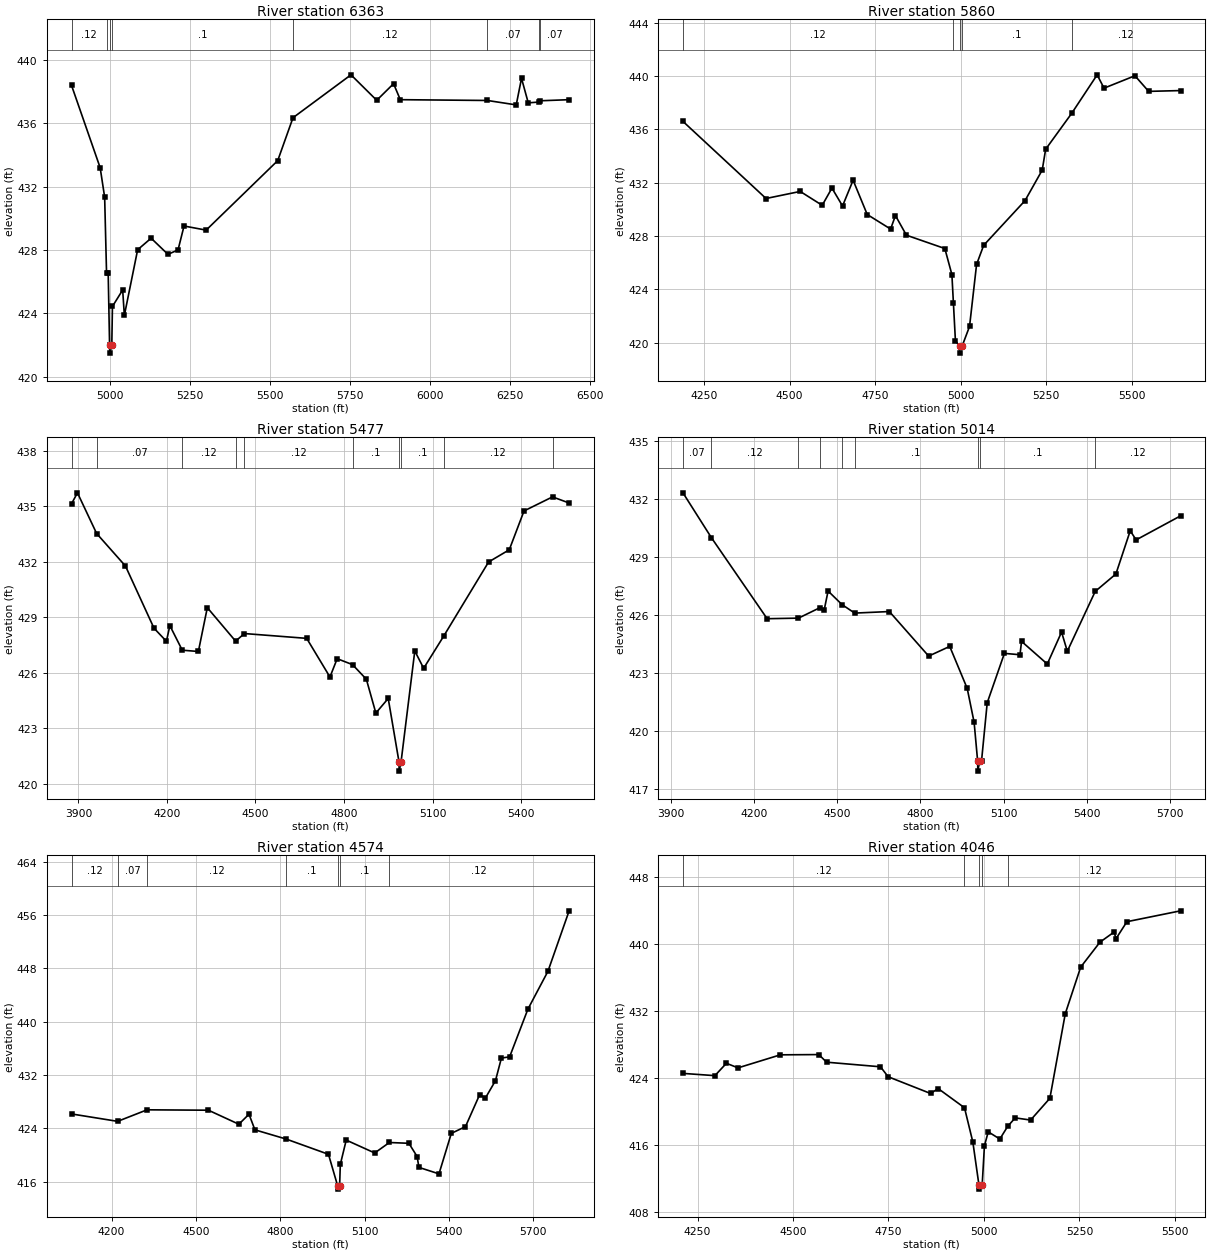
Type RM Length L Ch R = 1 ,6363    ,503,503,503
BEGIN DESCRIPTION:
Rocky Creek Tributary 7.0
END DESCRIPTION:
XS GIS Cut Line= 3
      2514124.98     13859724.99        2514025.       13859675.
      2512653.59     13859228.65
#Sta/Elev= 30
  4880.4  438.39  4969.8  433.19  4983.8  431.33  4989.7  426.56  4994.8  426.56
  4999.2  421.98  4999.7  421.48  5006.1  421.98  5008.1  424.43  5040.1  425.47
  5045.3  423.86  5086.8  428.01  5128.9  428.74  5181.5  427.72    5213     428
  5231.7  429.51  5300.8  429.25  5524.3  433.64    5572  436.35  5753.1  439.06
  5833.5  437.45  5886.1   438.5  5907.1  437.49  6179.2  437.44  6269.2  437.16
  6285.7  438.84  6306.7  437.29  6340.4  437.34  6343.3  437.42  6434.4  437.49
#Mann= 8 ,-1 , 0
  4880.4     .12       0  4989.7      .1       0  4999.2     .05       0
  5006.1      .1       0    5572     .12       0  6179.2     .07       0
  6340.4     .12       0  6343.3     .07       0
Bank Sta=4999.2,5006.1
XS Rating Curve= 0 ,0
Exp/Cntr=0.3,0.1

Type RM Length L Ch R = 1 ,5860    ,383,383,383
BEGIN DESCRIPTION:
B20300
END DESCRIPTION:
XS GIS Cut Line= 3
      2514587.37     13859499.01      2513716.68     13859279.05
      2513162.21     13859329.46
#Sta/Elev= 30
    4188   436.6  4430.9  430.82  4530.8  431.35  4595.1  430.31  4623.6   431.6
  4654.6  430.26  4685.5  432.19  4726.8  429.62  4795.1  428.53  4809.3  429.54
  4841.3  428.07  4953.7  427.07  4974.3  425.12  4978.8  422.96  4984.6  420.17
  4996.8  419.73  4997.3  419.23  5003.8  419.73  5025.9  421.23  5046.5  425.88
  5067.2  427.31  5188.1  430.66  5238.4  432.95  5248.4  434.51  5324.5   437.2
    5399  440.09  5419.1  439.09  5509.5  440.02  5549.6  438.85  5642.8  438.91
#Mann= 5 ,-1 , 0
    4188     .12       0  4978.8      .1       0  4996.8     .05       0
  5003.8      .1       0  5324.5     .12       0
Bank Sta=4996.8,5003.8
XS Rating Curve= 0 ,0
Exp/Cntr=0.3,0.1

Type RM Length L Ch R = 1 ,5477    ,463,463,463
BEGIN DESCRIPTION:
B20299
END DESCRIPTION:
XS GIS Cut Line= 3
      2514775.16      13859338.6        2513790.      13858953.7
       2513162.2     13858949.12
#Sta/Elev= 30
  3876.9  435.14  3896.9  435.73  3961.9  433.53  4059.6  431.77  4156.2  428.41
  4198.3   427.7  4209.9  428.55  4251.9  427.22  4306.5  427.15  4336.8  429.52
  4432.6  427.71  4462.5  428.12  4673.4  427.86  4752.2  425.77  4776.7  426.76
  4828.6  426.44  4875.5  425.65  4907.7  423.82  4949.6  424.61  4986.1  421.18
  4986.6  420.68  4993.1  421.18  5039.6  427.18  5069.6  426.24  5137.1  427.97
  5289.6  431.99  5359.6  432.65  5409.6  434.75  5506.1  435.51  5562.4  435.18
#Mann= 10 ,-1 , 0
  3876.9     .12       0  3961.9     .07       0  4251.9     .12       0
  4432.6     .07       0  4462.5     .12       0  4828.6      .1       0
  4986.1     .05       0  4993.1      .1       0  5137.1     .12       0
  5506.1      .1       0
Bank Sta=4986.1,4993.1
XS Rating Curve= 0 ,0
Exp/Cntr=0.3,0.1

Type RM Length L Ch R = 1 ,5014    ,440,440,440
BEGIN DESCRIPTION:
B20298
END DESCRIPTION:
XS GIS Cut Line= 3
      2514752.26     13859205.71      2514037.45     13858596.28
      2513209.01     13858390.32
#Sta/Elev= 30
  3944.3   432.3    4047  429.98  4247.7   425.8  4360.6  425.83  4436.6  426.36
  4453.2  426.25  4467.3  427.23  4517.4  426.53  4563.1  426.09  4688.1  426.17
  4829.7  423.87  4905.6  424.37  4968.6   422.2  4993.5  420.45  5006.3  418.43
  5006.8  417.93  5013.3  418.43  5020.1  418.44  5040.7  421.46  5102.6  424.01
  5158.8  423.94  5164.4  424.63  5257.1  423.46  5308.6  425.11  5329.3  424.12
  5429.9  427.21  5504.4  428.11    5556  430.34  5577.3  429.87  5737.3  431.11
#Mann= 9 ,-1 , 0
  3944.3     .07       0    4047     .12       0  4360.6     .07       0
  4436.6     .12       0  4517.4     .07       0  4563.1      .1       0
  5006.3     .05       0  5013.3      .1       0  5429.9     .12       0
Bank Sta=5006.3,5013.3
XS Rating Curve= 0 ,0
Exp/Cntr=0.3,0.1

Type RM Length L Ch R = 1 ,4574    ,528,528,528
BEGIN DESCRIPTION:
B20297
END DESCRIPTION:
XS GIS Cut Line= 3
      2514628.58     13858976.63      2514064.94     13858128.88
      2513625.24     13857519.71
#Sta/Elev= 30
  4057.8  426.17  4221.7  425.06  4326.3  426.79  4544.5  426.73  4652.7  424.63
  4688.8  426.13  4709.8  423.79  4820.6  422.41  4971.4  420.12  5003.9   415.4
  5004.4   414.9    5011   415.4  5013.5   418.6  5034.5  422.25  5135.8  420.32
    5188  421.89  5257.3  421.77  5286.7  419.78  5292.9  418.16  5364.3  417.19
  5408.2  423.26  5458.5  424.27  5508.8  429.05  5529.6  428.57  5565.2  431.16
  5586.3  434.55  5615.5  434.73  5680.5  441.88  5751.7  447.55  5827.1  456.62
#Mann= 7 ,-1 , 0
  4057.8     .12       0  4221.7     .07       0  4326.3     .12       0
  4820.6      .1       0  5003.9     .05       0    5011      .1       0
    5188     .12       0
Bank Sta=5003.9,5011
XS Rating Curve= 0 ,0
Exp/Cntr=0.3,0.1

Type RM Length L Ch R = 1 ,4046    ,477,477,477
BEGIN DESCRIPTION:
B20296
END DESCRIPTION:
XS GIS Cut Line= 2
      2514633.15     13858797.91      2514468.19     13857505.69
#Sta/Elev= 30
  4211.9  424.53  4295.5  424.26  4325.7  425.74    4356  425.19  4466.9  426.75
  4567.7  426.78  4587.8  425.87    4729  425.32  4749.1  424.13    4860  422.13
  4880.2  422.71    4949  420.42  4970.9  416.31  4986.8  411.19  4987.3  410.69
  4995.3  411.19  5001.2  415.88  5011.2  417.54  5041.5  416.68  5062.3  418.21
  5081.8  419.21  5122.1  418.95  5172.5  421.55  5212.9  431.68  5253.2  437.24
  5303.6  440.22  5340.6  441.43  5345.7  440.64  5374.2  442.67  5514.6  443.97
#Mann= 5 ,-1 , 0
  4211.9     .12       0    4949      .1       0  4986.8     .05       0
  4995.3      .1       0  5062.3     .12       0
Bank Sta=4986.8,4995.3
XS Rating Curve= 0 ,0
Exp/Cntr=0.3,0.1

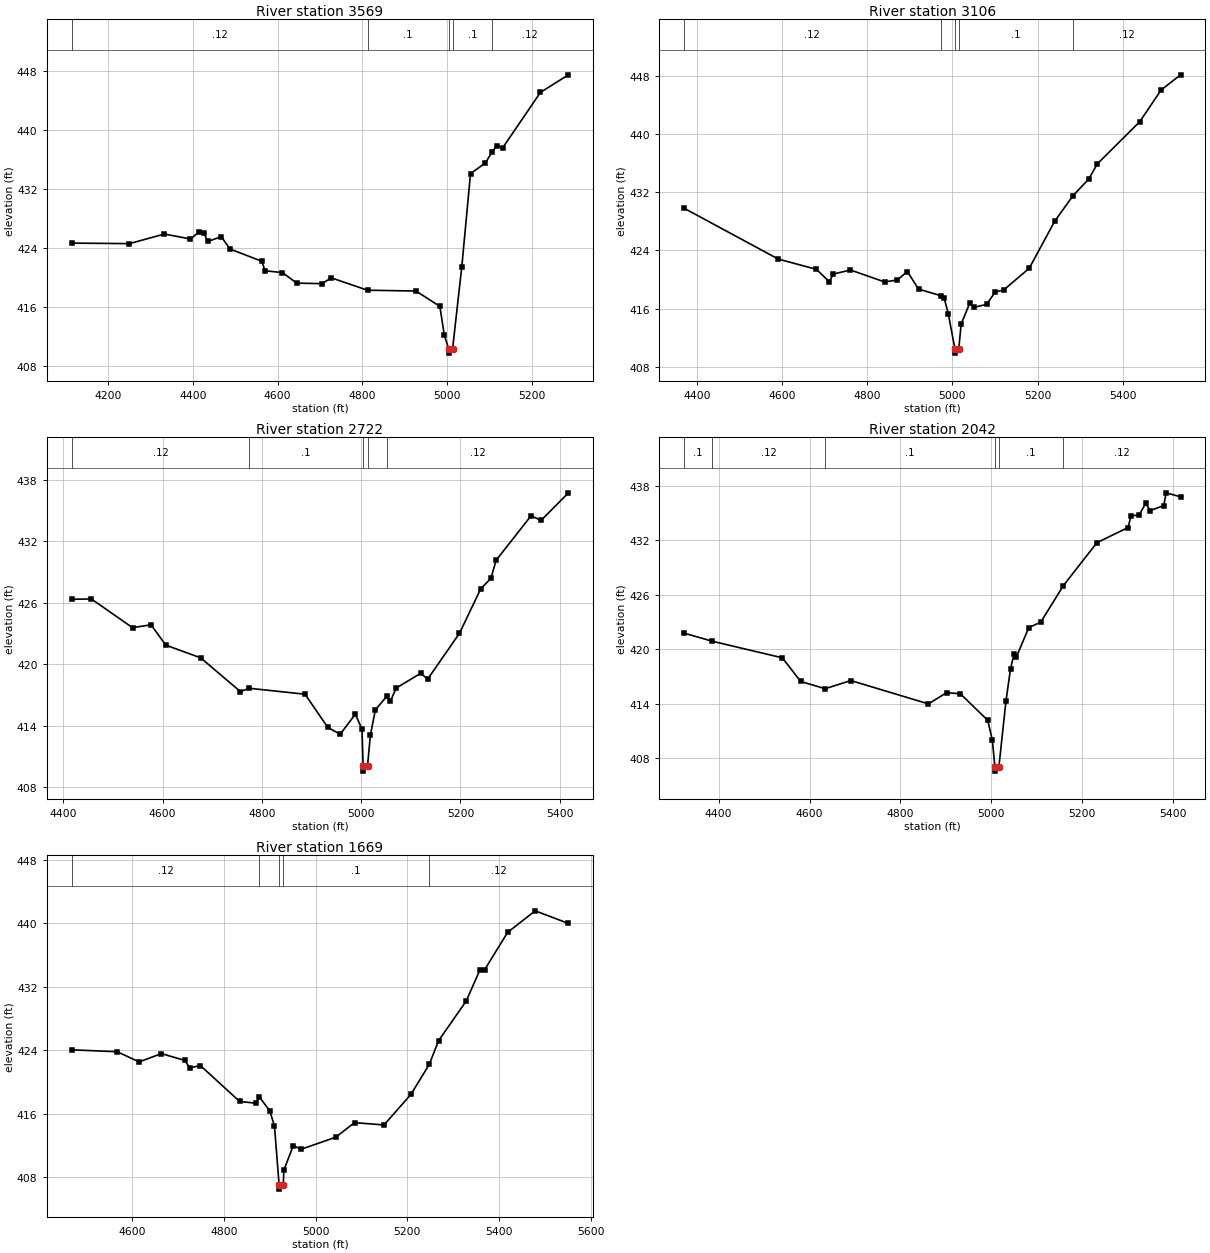
Type RM Length L Ch R = 1 ,3569    ,463,463,463
BEGIN DESCRIPTION:
B20295
END DESCRIPTION:
XS GIS Cut Line= 2
      2514669.82     13858747.48       2514958.5     13857611.07
#Sta/Elev= 30
  4113.6  424.69  4250.3  424.62  4332.8  425.92  4394.1  425.25  4415.4  426.24
  4425.7  426.09  4435.1  424.91    4467  425.56  4487.6  423.89    4563  422.22
  4570.1  420.94  4611.4   420.7  4644.9  419.27  4704.3   419.2  4726.8  419.98
  4812.1  418.31  4926.4   418.2  4982.8  416.12  4993.2  412.25    5004  410.29
  5004.5  409.79  5012.6  410.29  5034.4   421.4  5055.1   434.1  5090.1  435.54
  5106.5  437.08    5117  437.85  5131.1   437.6  5220.1   445.1  5286.1  447.48
#Mann= 5 ,-1 , 0
  4113.6     .12       0  4812.1      .1       0    5004     .05       0
  5012.6      .1       0  5106.5     .12       0
Bank Sta=5004,5012.6
XS Rating Curve= 0 ,0
Exp/Cntr=0.3,0.1

Type RM Length L Ch R = 1 ,3106    ,384,384,384
BEGIN DESCRIPTION:
B20294
END DESCRIPTION:
XS GIS Cut Line= 2
      2515109.72     13858807.04      2515132.62     13857639.27
#Sta/Elev= 30
  4368.3  429.84  4590.4  422.82  4680.4   421.4  4710.4   419.7  4720.4  420.76
  4760.4  421.31  4840.4  419.67  4870.4  419.93  4894.1   421.1  4920.4  418.68
  4972.5  417.78  4980.5  417.49  4990.5  415.24  5006.1  410.37  5006.6  409.87
  5014.8  410.37  5020.5  413.87  5040.5  416.71  5050.5  416.17  5080.5  416.58
  5100.5  418.28  5120.5  418.56  5180.5  421.54  5240.5  428.03  5283.4  431.53
  5320.5  433.83  5340.5  435.91  5440.5  441.73  5490.6  446.08  5536.3  448.17
#Mann= 5 ,-1 , 0
  4368.3     .12       0  4972.5      .1       0  5006.1     .05       0
  5014.8      .1       0  5283.4     .12       0
Bank Sta=5006.1,5014.8
XS Rating Curve= 0 ,0
Exp/Cntr=0.3,0.1

Type RM Length L Ch R = 1 ,2722    ,680,680,680
BEGIN DESCRIPTION:
B20293
END DESCRIPTION:
XS GIS Cut Line= 3
      2515476.31     13858664.98      2515490.05     13858215.95
      2515407.56      13857670.6
#Sta/Elev= 30
  4416.6  426.33  4456.6  426.36  4539.5  423.56  4576.7  423.84  4606.7  421.85
  4676.7  420.62  4756.7  417.33  4774.7  417.65    4887  417.07  4932.8  413.83
  4957.8  413.17  4988.2  415.12  5001.6  413.68    5004  410.07  5004.5  409.57
  5012.8  410.07  5018.5  413.06  5028.6  415.54  5051.2  416.85    5059   416.4
  5070.5  417.67  5119.6   419.1  5134.2  418.56    5198  423.01    5241  427.37
  5261.2  428.36  5271.9  430.14  5342.2  434.47  5362.4  434.02  5417.4  436.71
#Mann= 5 ,-1 , 0
  4416.6     .12       0  4774.7      .1       0    5004     .05       0
  5012.8      .1       0  5051.2     .12       0
Bank Sta=5004,5012.8
XS Rating Curve= 0 ,0
Exp/Cntr=0.3,0.1

Type RM Length L Ch R = 1 ,2042    ,373,373,373
BEGIN DESCRIPTION:
B20292
END DESCRIPTION:
XS GIS Cut Line= 3
      2515760.41     13858541.29      2515833.73     13857776.04
      2515952.87     13857473.61
#Sta/Elev= 30
    4323   421.8  4386.4  420.89  4540.3  419.07  4580.5  416.47  4634.4  415.67
    4691  416.57  4861.7     414  4901.9  415.24  4932.1  415.11  4992.3  412.19
  5002.4  410.04    5008   407.1  5008.5   406.6  5016.9   407.1  5032.5  414.33
  5042.6  417.89  5050.1  419.48  5055.1  419.14  5082.7   422.4  5108.9  422.99
    5159  427.03  5232.6  431.74  5301.1  433.41  5307.8  434.69  5325.5   434.8
  5340.1  436.06  5349.9  435.28  5379.7  435.82  5385.1  437.23  5416.8  436.79
#Mann= 6 ,-1 , 0
    4323      .1       0  4386.4     .12       0  4634.4      .1       0
    5008     .05       0  5016.9      .1       0    5159     .12       0
Bank Sta=5008,5016.9
XS Rating Curve= 0 ,0
Exp/Cntr=0.3,0.1

Type RM Length L Ch R = 1 ,1669    ,409,409,409
BEGIN DESCRIPTION:
B20291
END DESCRIPTION:
XS GIS Cut Line= 3
      2515957.44      13858545.9      2516122.42     13857831.03
       2516099.5     13857482.74
#Sta/Elev= 30
  4468.3  424.04  4567.7   423.8  4615.6  422.52  4664.2  423.56  4715.5   422.7
  4725.8  421.75    4749  422.06  4834.5  417.54  4869.5  417.31  4877.8  418.08
  4900.3  416.35  4910.5  414.44  4920.7  406.98  4921.2  406.48  4929.6  406.98
  4931.1  408.89  4951.6  411.97  4967.9  411.49  5043.9  413.02    5085  414.86
  5149.2  414.57    5208  418.43  5247.8   422.2  5268.1  425.19  5328.3  430.19
  5358.3  434.12  5368.4  434.13  5418.5  438.84  5478.6  441.56    5551  439.97
#Mann= 5 ,-1 , 0
  4468.3     .12       0  4877.8      .1       0  4920.7     .05       0
  4929.6      .1       0  5247.8     .12       0
Bank Sta=4920.7,4929.6
XS Rating Curve= 0 ,0
Exp/Cntr=0.3,0.1