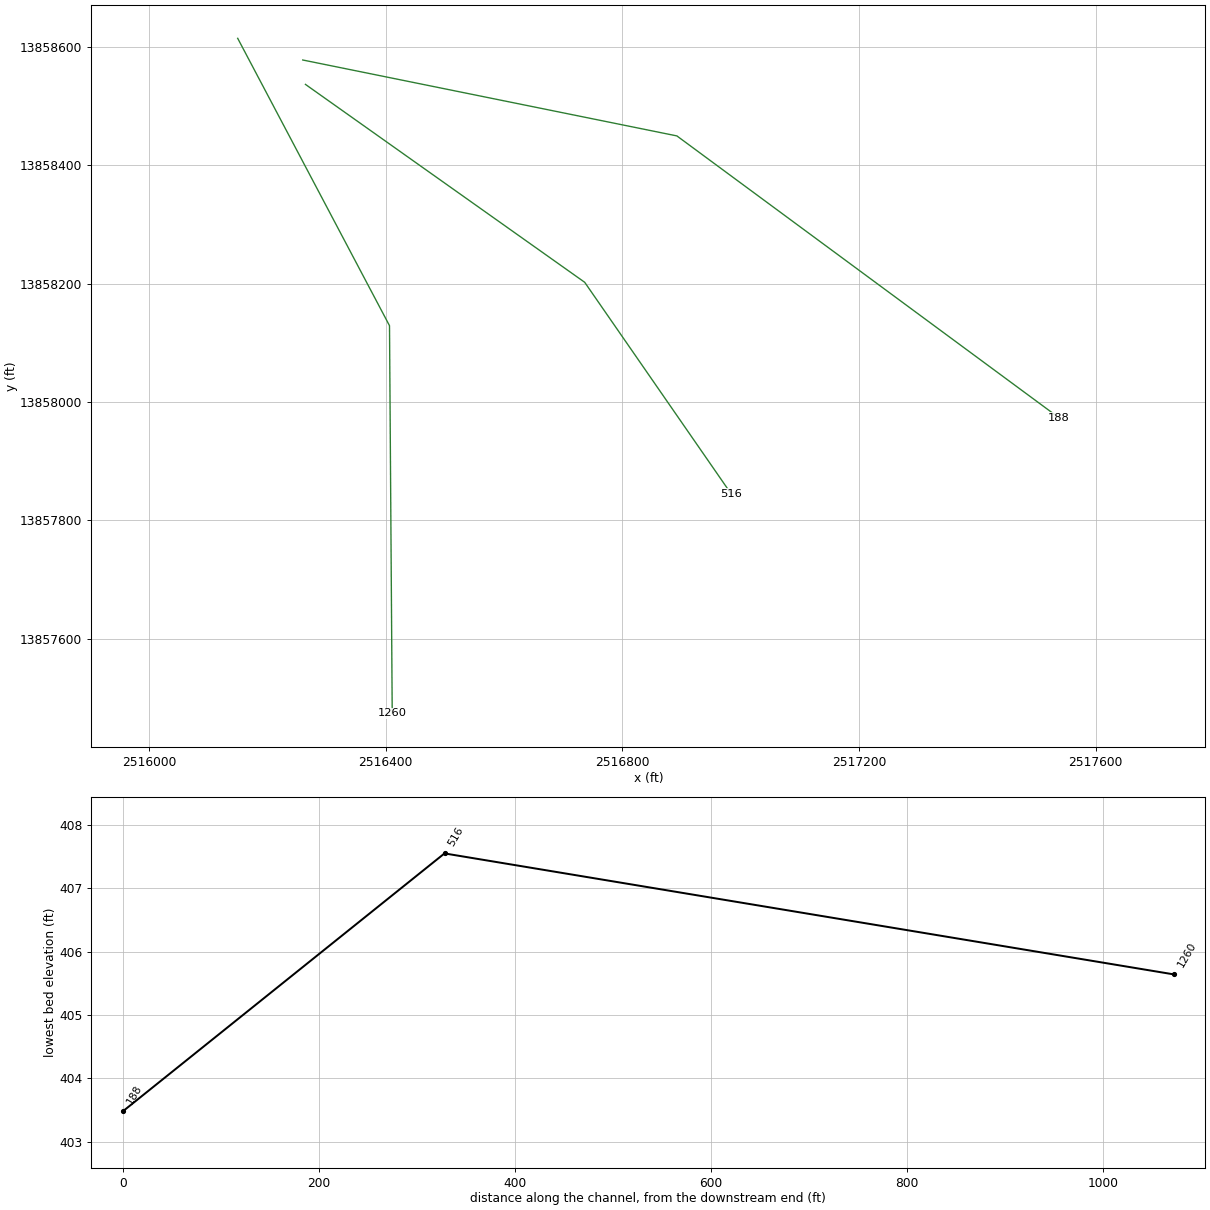
HEC-RAS study Rocky Creek Tributary.prj: Rocky Creek Tributary Base Level Engineering

--- Rocky Creek Tributary.g01 (geometry) --- (continued)

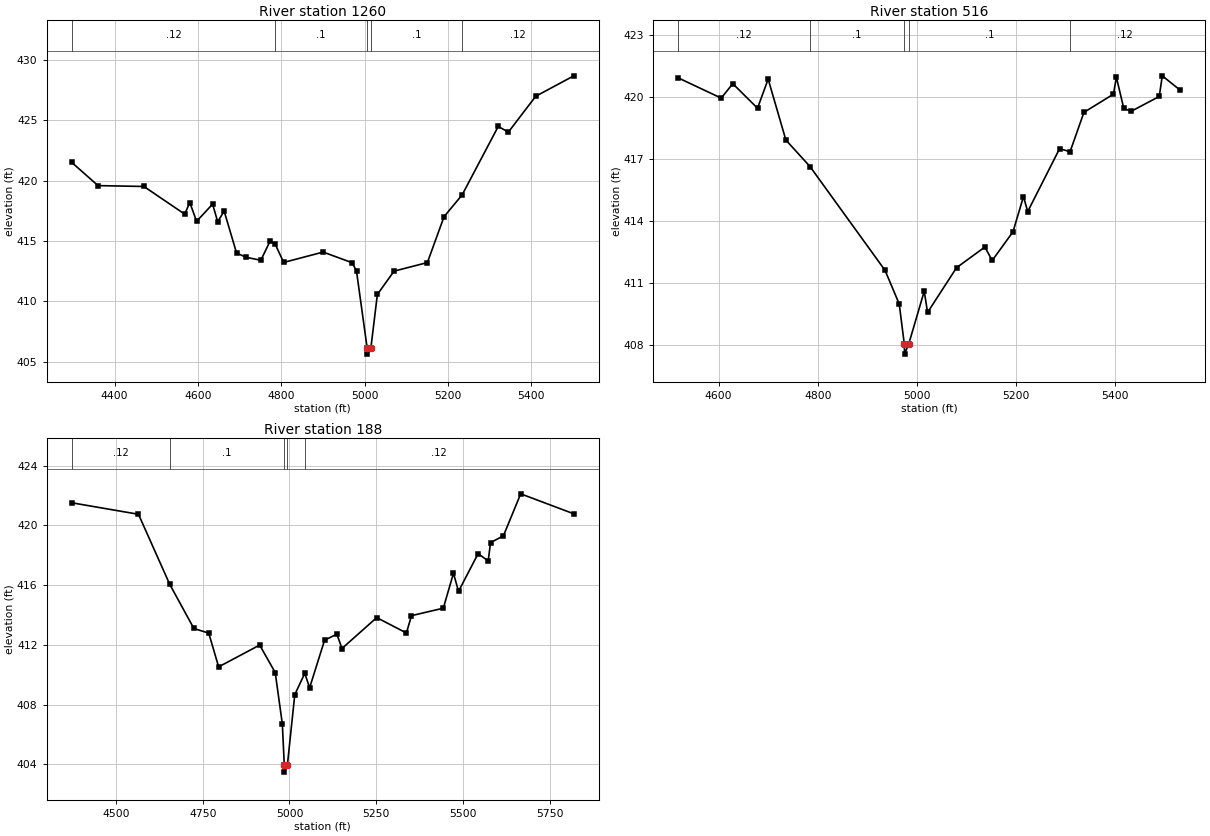
Type RM Length L Ch R = 1 ,1260    ,744,744,744
BEGIN DESCRIPTION:
B20290
END DESCRIPTION:
XS GIS Cut Line= 3
      2516149.93     13858614.57      2516406.52     13858128.88
       2516411.1     13857473.59
#Sta/Elev= 30
  4297.4  421.51  4360.4  419.59  4470.5  419.52  4568.3  417.23  4580.6  418.19
  4596.9  416.63  4635.3  418.06  4647.5   416.6    4663  417.48  4692.8  414.01
  4715.4  413.66    4751  413.41    4773  414.98  4785.4  414.75  4805.8  413.23
  4900.6  414.09  4970.6   413.2  4980.6   412.5  5006.1  406.14  5006.6  405.64
    5015  406.14  5030.6  410.58  5070.6  412.51  5150.6  413.22  5190.6  417.02
  5234.1  418.83  5320.6  424.49  5344.9  424.02  5410.6  426.99    5502  428.68
#Mann= 5 ,-1 , 0
  4297.4     .12       0  4785.4      .1       0  5006.1     .05       0
    5015      .1       0  5234.1     .12       0
Bank Sta=5006.1,5015
XS Rating Curve= 0 ,0
Exp/Cntr=0.3,0.1

Type RM Length L Ch R = 1 ,516     ,328,328,328
BEGIN DESCRIPTION:
B20289
END DESCRIPTION:
XS GIS Cut Line= 3
      2516264.44     13858536.73      2516736.45      13858202.2
      2516983.92     13857844.74
#Sta/Elev= 30
  4518.5  420.94  4605.2  419.96  4628.6  420.66  4678.5  419.47    4700  420.88
  4735.7  417.93  4784.5  416.64  4935.9  411.61  4964.5  409.98  4974.7  408.05
  4975.2  407.55  4983.8  408.05    5015   410.6  5021.7  409.57  5080.2  411.74
  5137.3  412.74  5152.2  412.09  5194.1  413.48  5215.3  415.19  5223.8  414.46
  5288.2  417.51  5309.3  417.36  5337.3  419.27  5396.8  420.15  5402.8  420.97
  5417.7  419.46  5432.6  419.32  5489.3  420.04  5495.4  421.04  5531.8  420.34
#Mann= 5 ,-1 , 0
  4518.5     .12       0  4784.5      .1       0  4974.7     .05       0
  4983.8      .1       0  5309.3     .12       0
Bank Sta=4974.7,4983.8
XS Rating Curve= 0 ,0
Exp/Cntr=0.3,0.1

Type RM Length L Ch R = 1 ,188     ,0,0,0
BEGIN DESCRIPTION:
B20288
END DESCRIPTION:
XS GIS Cut Line= 3
      2516259.87     13858577.96      2516892.25     13858449.65
      2517538.35     13857973.09
#Sta/Elev= 30
  4372.1  421.52  4564.5  420.75  4654.6  416.06  4724.3   413.1  4767.2  412.79
  4795.7  410.53    4914  411.99  4958.9  410.15  4979.4  406.71    4985  403.98
  4985.5  403.48  4994.1  403.98  5015.3  408.67  5044.2   410.1  5058.1  409.13
  5101.3  412.32  5136.8  412.72  5151.4  411.76  5251.6  413.83  5337.3   412.8
  5351.9  413.96  5443.7  414.46    5473   416.8  5487.6  415.59    5544  418.11
  5573.2  417.63  5579.9  418.85  5617.1  419.31  5666.9  422.12  5820.2  420.78
#Mann= 5 ,-1 , 0
  4372.1     .12       0  4654.6      .1       0    4985     .05       0
  4994.1      .1       0  5044.2     .12       0
Bank Sta=4985,4994.1
XS Rating Curve= 0 ,0
Exp/Cntr=0.3,0.1

Chan Stop Cuts=-1
Use User Specified Reach Order=0
Composite Channel Slope=5