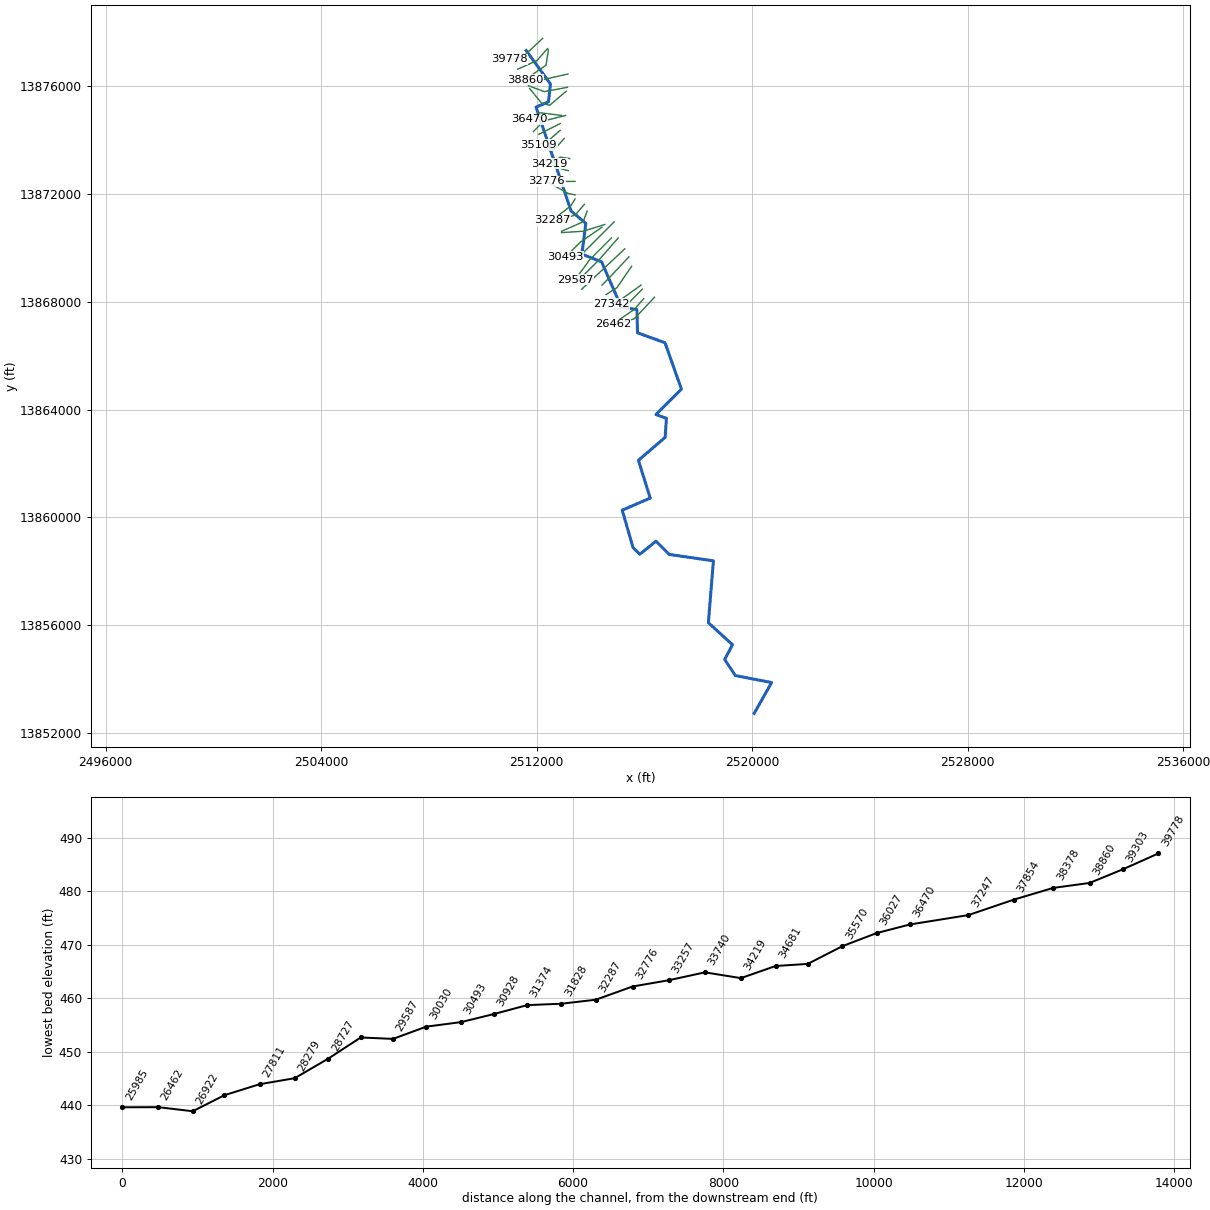
--- Rocky Creek.prj (project) ---

Proj Title=Rocky Creek Base Level Engineering
Current Plan=p01
Default Exp/Contr=0.3,0.1
English Units
Geom File=g01
Flow File=f01
Plan File=p01
Y Axis Title=Elevation
X Axis Title(PF)=Main Channel Distance
X Axis Title(XS)=Station
BEGIN DESCRIPTION:
Rocky Creek
END DESCRIPTION:
DSS Export Rating Curves= 0
DSS Export Rating Curve Sorted= 0
DSS Export Volume Flow Curves= 0
DXF OffsetX= 0
DXF OffsetY= 0
DXF ScaleX= 1
DXF ScaleY= 10

--- Rocky Creek.p01 (plan) ---

Plan Title=Multiple Run
Short Identifier=Multiple
Geom File=g01
Flow File=f01
Subcritical Flow
K Sum by GR= 0
Std Step Tol= 0.01
Critical Tol= 0.01
Num of Std Step Trials= 20
Max Error Tol= 0.3
Flow Tol Ratio= 0.001
Split Flow NTrial= 30
Split Flow Tol= 0.02
Split Flow Ratio= 0.02
Log Output Level= 0
Friction Slope Method= 1
Unsteady Friction Slope Method= 2
Unsteady Bridges Friction Slope Method= 1
Parabolic Critical Depth
Global Vel Dist=  1 , 1 , 1
Global Log Level= 0
CheckData=True
Encroach Param= -1, 0, 0, 0
BEGIN DESCRIPTION:
Multiple Run
END DESCRIPTION:

--- Rocky Creek.f01 (steady flow) ---

Flow Title=Multiple
Number of Profiles=7
Profile Names=10-year,25-year,50-year,1pct_min,100-year,1pct_plu,500-year
River Rch & RM= Rocky Creek,Reach-1,39778
     664    1064    1425     924    1843    3678    3054
River Rch & RM= Rocky Creek,Reach-1,36470
    1195    1965    2673    1757    3506    6995    5972
River Rch & RM= Rocky Creek,Reach-1,30493
    1414    2336    3189    2101    4191    8363    7174
River Rch & RM= Rocky Creek,Reach-1,24125
    1592    2646    3626    2397    4783    9544    8248
River Rch & RM= Rocky Creek,Reach-1,23663
    1806    3020    4155    2758    5503   10979    9560
River Rch & RM= Rocky Creek,Reach-1,22750
    1920    3206    4404    2917    5820   11613   10073
River Rch & RM= Rocky Creek,Reach-1,13997
    1975    3298    4532    3002    5989   11951   10365
River Rch & RM= Rocky Creek,Reach-1,9950
    2865    4853    6733    4498    8975   17908   15803
River Rch & RM= Rocky Creek,Reach-1,8171
    2889    4889    6778    4525    9028   18013   15868
River Rch & RM= Rocky Creek,Reach-1,6538
    3007    5098    7077    4729    9436   18828   16625
River Rch & RM= Rocky Creek,Reach-1,5460
    3046    5159    7156    4778    9534   19023   16768
Boundary for River Rch & Prof#=Rocky Creek,Reach-1,1
Up Type=0
Dn Type=3
Dn Slope=0.005
Boundary for River Rch & Prof#=Rocky Creek,Reach-1,2
Up Type=0
Dn Type=3
Dn Slope=0.005
Boundary for River Rch & Prof#=Rocky Creek,Reach-1,3
Up Type=0
Dn Type=3
Dn Slope=0.005
Boundary for River Rch & Prof#=Rocky Creek,Reach-1,4
Up Type=0
Dn Type=3
Dn Slope=0.005
Boundary for River Rch & Prof#=Rocky Creek,Reach-1,5
Up Type=0
Dn Type=3
Dn Slope=0.005
Boundary for River Rch & Prof#=Rocky Creek,Reach-1,6
Up Type=0
Dn Type=3
Dn Slope=0.005
Boundary for River Rch & Prof#=Rocky Creek,Reach-1,7
Up Type=0
Dn Type=3
Dn Slope=0.005

--- Rocky Creek.g01 (geometry) ---

Geom Title=Existing Conditions
Program Version=4.10

River Reach=Rocky Creek     ,Reach-1
Reach XY= 30
      2511611.18     13877334.43      2512511.62     13876090.95
      2512438.12      13875429.4      2511975.81     13875235.34
      2513278.07     13871376.43      2513823.12     13870919.32
      2513678.75     13869776.55      2514411.35     13869488.33
      2515144.42     13867804.46      2515722.09     13867717.09
       2515744.4     13866854.34      2516764.61      13866485.1
      2517373.91     13864764.46      2516426.78     13863818.87
       2516817.4     13863678.37      2516769.17     13862972.69
      2515777.05     13862119.14      2516216.01     13860717.93
      2515176.61     13860268.96      2515577.24     13858880.93
      2515828.41     13858632.77       2516428.3     13859116.92
        2516925.       13858625.      2518561.78     13858388.34
      2518375.07     13856090.37      2519271.48     13855273.54
      2518978.67     13854726.58      2519376.46     13854128.52
      2520723.12     13853869.29        2520075.       13852725.

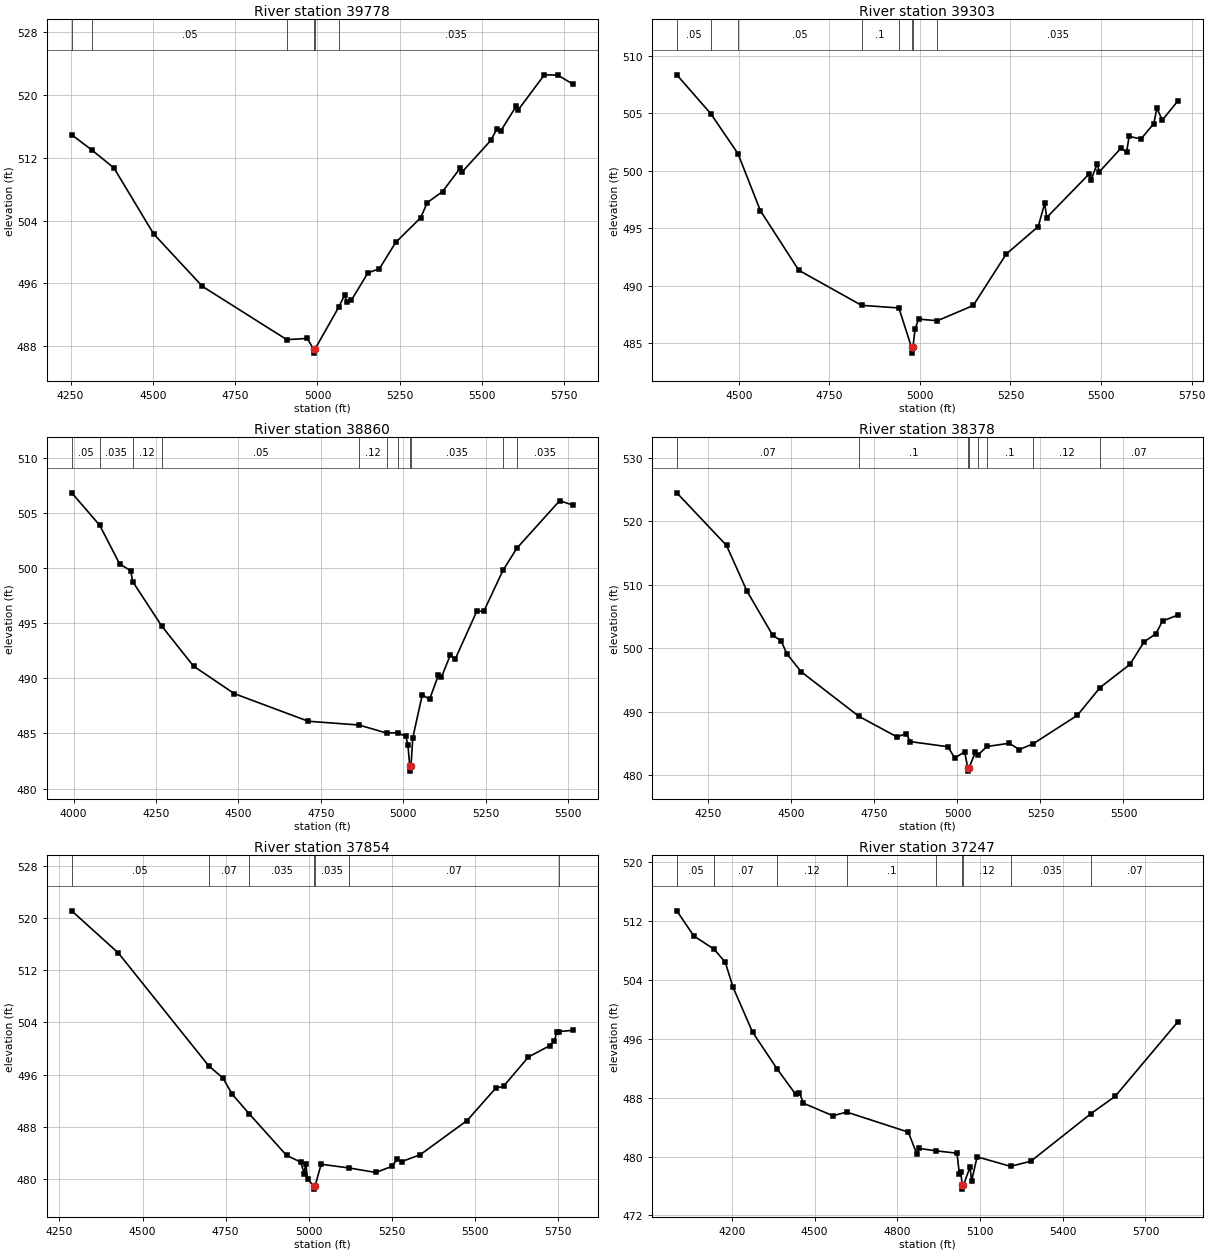
Type RM Length L Ch R = 1 ,39778   ,475,475,475
BEGIN DESCRIPTION:
E21656
END DESCRIPTION:
XS GIS Cut Line= 3
       2512223.7     13877787.69      2511488.67     13877101.66
      2510980.83     13877009.88
#Sta/Elev= 30
  4253.4  514.94  4316.3  512.94  4381.7  510.71  4501.9  502.33  4650.4  495.62
  4906.8  488.83    4969  488.98  4988.3  487.61  4988.5  487.11  4992.3  487.61
  5064.5  492.96  5082.3  494.49  5089.1  493.69  5103.3  493.87  5153.1  497.33
  5188.3  497.87  5237.6  501.22  5313.4  504.36  5333.7   506.3    5380   507.7
  5433.5  510.68  5438.6  510.16  5526.8  514.23  5545.7  515.73  5557.3  515.46
  5604.3  518.62  5609.3  518.08  5689.4  522.58    5730  522.55  5774.9  521.42
#Mann= 6 ,-1 , 0
  4253.4     .12       0  4316.3     .05       0  4906.8      .1       0
  4988.3     .05       0  4992.3      .1       0  5064.5    .035       0
Bank Sta=4988.3,4992.3
XS Rating Curve= 0 ,0
Exp/Cntr=0.3,0.1

Type RM Length L Ch R = 1 ,39303   ,443,443,443
BEGIN DESCRIPTION:
E21655
END DESCRIPTION:
XS GIS Cut Line= 3
      2512407.49     13877407.94      2511997.08     13876954.65
      2511292.63     13876642.24
#Sta/Elev= 30
  4329.2  508.35  4422.9  504.97    4498  501.49  4559.8  496.53  4665.9  491.34
  4839.1  488.29  4942.1  488.06    4977  484.63  4977.3  484.13    4981  484.63
  4986.7  486.24  4996.8  487.09  5048.5  486.95  5147.4  488.28  5238.3  492.75
  5326.7  495.15  5344.5  497.17    5350  495.93  5466.4   499.7  5471.8  499.16
  5489.6  500.62  5495.1   499.9  5555.6  501.99  5570.4   501.6  5577.4  502.99
  5610.3  502.77  5645.7  504.11    5654  505.45    5669  504.41  5711.3  506.05
#Mann= 8 ,-1 , 0
  4329.2     .05       0  4422.9    .035       0    4498     .05       0
  4839.1      .1       0  4942.1     .12       0    4977     .05       0
    4981     .12       0  5048.5    .035       0
Bank Sta=4977,4981
XS Rating Curve= 0 ,0
Exp/Cntr=0.3,0.1

Type RM Length L Ch R = 1 ,38860   ,482,482,482
BEGIN DESCRIPTION:
E21654
END DESCRIPTION:
XS GIS Cut Line= 3
      2512438.12     13877358.98      2512346.23     13876789.26
      2511569.16     13876256.93
#Sta/Elev= 30
  3994.3  506.86  4079.1  503.92  4140.1  500.38  4173.3  499.79  4179.2   498.8
  4267.3  494.76  4363.7  491.12  4487.3  488.62  4711.9  486.11  4865.4  485.77
  4949.2  485.04  4982.5  485.07  5007.8  484.73  5013.9  483.99  5019.4  482.08
  5019.6  481.58  5023.4  482.08  5028.8  484.61  5057.7  488.53  5079.6  488.09
  5106.6   490.3  5115.4   490.1  5142.6  492.12  5157.4  491.75  5223.1  496.12
    5244  496.09  5302.4  499.82  5344.5  501.83  5474.2  506.14  5513.3  505.76
#Mann= 11 ,-1 , 0
  3994.3     .05       0  4079.1    .035       0  4179.2     .12       0
  4267.3     .05       0  4865.4     .12       0  4949.2     .05       0
  4982.5    .035       0  5019.4    .035       0  5023.4    .035       0
  5302.4     .12       0  5344.5    .035       0
Bank Sta=5019.4,5023.4
XS Rating Curve= 0 ,0
Exp/Cntr=0.3,0.1

Type RM Length L Ch R = 1 ,38378   ,524,524,524
BEGIN DESCRIPTION:
E21653
END DESCRIPTION:
XS GIS Cut Line= 2
      2513160.97     13876464.62      2511690.78      13876127.7
#Sta/Elev= 30
  4154.8  524.47  4304.5  516.19  4366.1     509  4443.6  502.05  4468.7   501.2
  4486.5  499.11  4529.4   496.3  4703.1  489.29  4817.5  486.06  4845.1  486.53
  4858.5   485.3  4971.4   484.5  4991.9  482.72  5021.8   483.7    5031  481.16
  5031.2  480.66    5035  481.16  5053.5  483.61  5062.4  483.23    5089  484.54
  5155.6  485.04  5186.8  484.06  5227.9  484.96  5361.3  489.45  5429.5  493.82
  5519.4  497.46  5562.3  501.02  5597.2  502.27  5617.7  504.29  5663.1  505.21
#Mann= 8 ,-1 , 0
  4154.8     .07       0  4703.1      .1       0    5031     .05       0
    5035      .1       0  5062.4     .12       0    5089      .1       0
  5227.9     .12       0  5429.5     .07       0
Bank Sta=5031,5035
XS Rating Curve= 0 ,0
Exp/Cntr=0.3,0.1

Type RM Length L Ch R = 1 ,37854   ,607,607,607
BEGIN DESCRIPTION:
E21652
END DESCRIPTION:
XS GIS Cut Line= 3
      2513142.51     13875968.44      2512284.98     13875809.18
      2511690.78     13876029.71
#Sta/Elev= 30
    4287   521.1  4426.9  514.66  4699.1  497.35  4742.2  495.46  4769.5  493.01
  4820.9     490    4933  483.64  4976.1   482.6  4985.8  480.86  4990.9  482.34
  4996.4  479.97  5014.8  478.97    5015  478.47  5018.8  478.97  5037.1  482.28
    5120  481.72  5201.8  481.02  5248.8  481.94  5265.8  483.02  5279.2  482.69
  5334.6  483.73  5475.8  488.97  5561.5  493.91  5585.8  494.24  5660.5  498.72
  5724.5  500.44  5738.4   501.2  5745.8  502.53  5753.1  502.61    5793  502.79
#Mann= 7 ,-1 , 0
    4287     .05       0  4699.1     .07       0  4820.9    .035       0
  5014.8    .035       0  5018.8    .035       0    5120     .07       0
  5753.1     .12       0
Bank Sta=5014.8,5018.8
XS Rating Curve= 0 ,0
Exp/Cntr=0.3,0.1

Type RM Length L Ch R = 1 ,37247   ,777,777,777
BEGIN DESCRIPTION:
E21651
END DESCRIPTION:
XS GIS Cut Line= 4
       2513099.7     13875827.58      2512480.99     13875300.77
      2512180.85     13875386.52      2511739.88     13875919.36
#Sta/Elev= 30
  4000.1   513.4  4061.7  509.99  4135.2  508.19    4176  506.42  4203.4  503.07
  4274.8  496.92  4364.1   491.9  4430.7  488.48    4445  488.68  4459.3  487.25
  4565.8  485.55  4616.8  486.04  4839.7  483.32  4870.9  480.33  4879.4   481.1
  4941.4  480.77  5016.5  480.45    5025  477.56  5030.2  477.89  5035.3  476.07
  5035.6  475.57  5039.3  476.07    5064   478.6  5069.2  476.65  5089.3  479.96
  5210.5  478.67  5284.1  479.36  5502.8  485.85  5590.2  488.19  5816.5  498.28
#Mann= 9 ,-1 , 0
  4000.1     .05       0  4135.2     .07       0  4364.1     .12       0
  4616.8      .1       0  4941.4     .12       0  5035.3     .05       0
  5039.3     .12       0  5210.5    .035       0  5502.8     .07       0
Bank Sta=5035.3,5039.3
XS Rating Curve= 0 ,0
Exp/Cntr=0.3,0.1

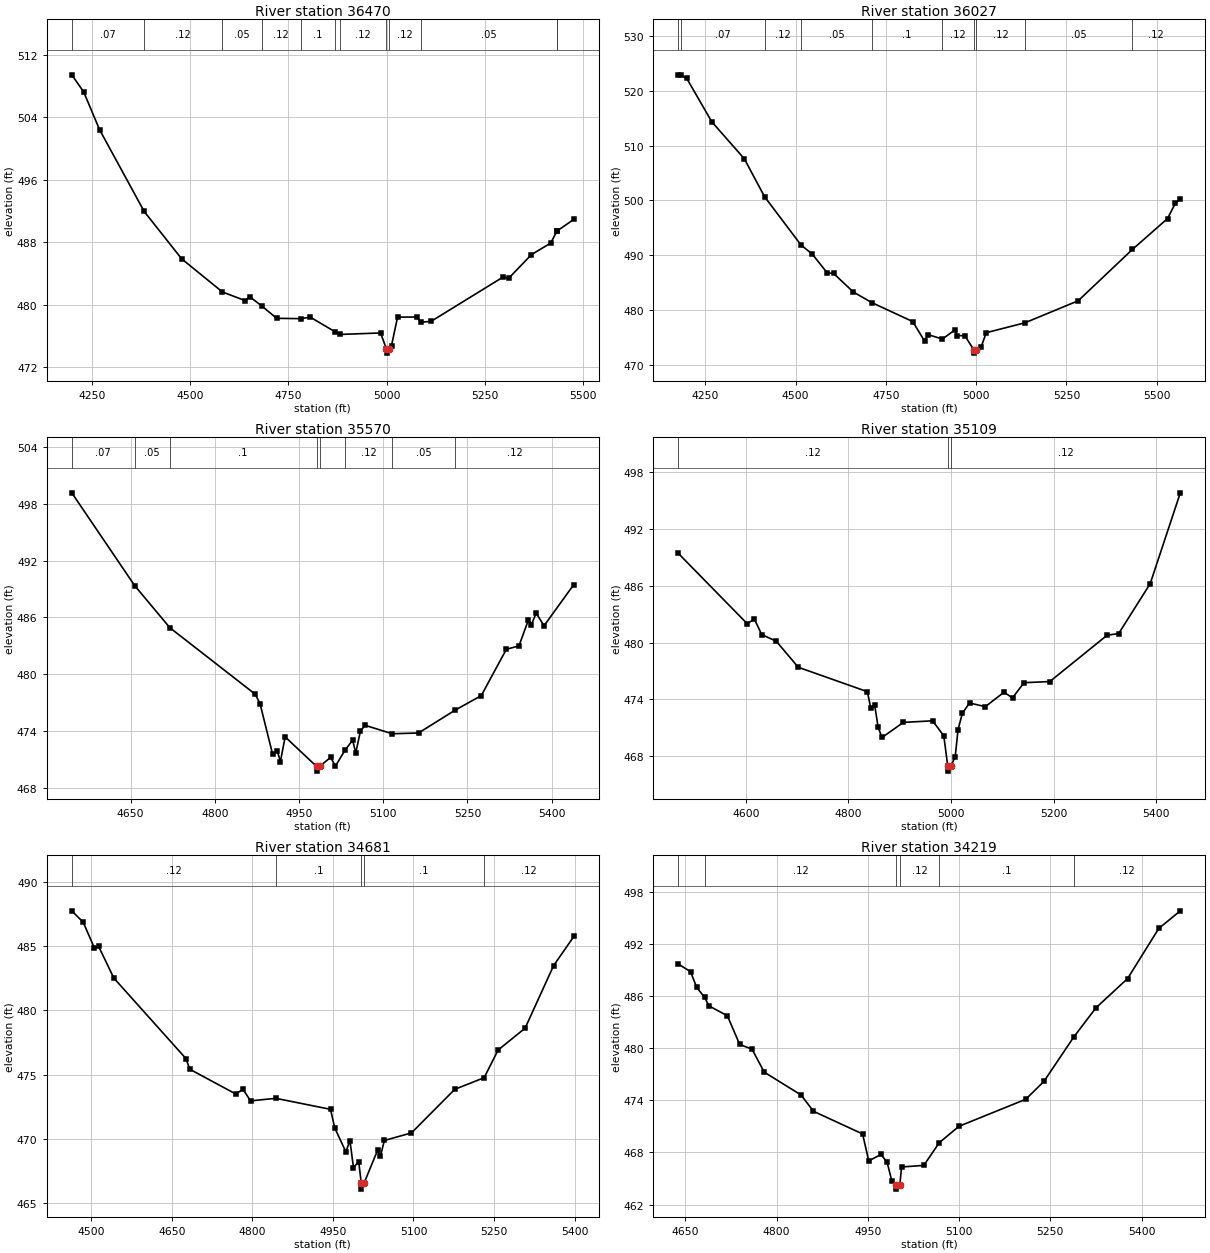
Type RM Length L Ch R = 1 ,36470   ,443,443,443
BEGIN DESCRIPTION:
Rocky Creek 66.0
END DESCRIPTION:
XS GIS Cut Line= 3
      2512925.03       13874925.        2512125.       13875025.
      2511724.96     13874774.98
#Sta/Elev= 30
  4198.6  509.41  4228.9  507.23  4269.2  502.41  4382.9  491.94  4478.3  485.88
  4582.2  481.64  4639.5  480.54  4652.1  481.01  4681.8  479.87  4720.2  478.27
  4781.5  478.23  4805.8  478.42  4868.7  476.55  4881.1  476.21  4984.7   476.4
  4999.7  474.32  5000.1  473.82  5004.9  474.32  5012.5  474.79  5027.9  478.42
  5076.2  478.44  5087.5  477.79  5112.8  477.87  5295.5  483.52  5310.9   483.4
  5368.7  486.42  5417.6  487.89    5434  489.47  5434.5  489.46  5476.6  490.93
#Mann= 12 ,-1 , 0
  4198.6     .07       0  4382.9     .12       0  4582.2     .05       0
  4681.8     .12       0  4781.5      .1       0  4868.7     .05       0
  4881.1     .12       0  4999.7     .05       0  5004.9     .12       0
  5087.5     .05       0    5434     .12       0  5434.5     .07       0
Bank Sta=4999.7,5004.9
XS Rating Curve= 0 ,0
Exp/Cntr=0.3,0.1

Type RM Length L Ch R = 1 ,36027   ,457,457,457
BEGIN DESCRIPTION:
Rocky Creek 65.0
END DESCRIPTION:
XS GIS Cut Line= 3
      2513075.01       13874925.        2512275.       13874725.
      2511875.01     13874325.01
#Sta/Elev= 30
  4174.9  522.87  4182.4  522.75  4198.1  522.26  4267.7  514.33  4357.9  507.59
    4414  500.68  4514.9  491.89    4546  490.24  4587.2  486.84  4605.3  486.71
  4659.4  483.35  4711.5  481.39  4824.3  477.95  4857.8  474.33  4865.5   475.6
  4906.6  474.77  4940.3  476.42    4948  475.41  4968.6  475.37  4994.4  472.71
  4994.8  472.21  4999.6  472.71  5013.7  473.33  5027.8  475.93  5135.3  477.74
  5282.4  481.74  5432.5  491.08  5529.9  496.71  5551.1  499.45  5565.2  500.33
#Mann= 10 ,-1 , 0
  4174.9     .05       0  4182.4     .07       0    4414     .12       0
  4514.9     .05       0  4711.5      .1       0  4906.6     .12       0
  4994.4     .05       0  4999.6     .12       0  5135.3     .05       0
  5432.5     .12       0
Bank Sta=4994.4,4999.6
XS Rating Curve= 0 ,0
Exp/Cntr=0.3,0.1

Type RM Length L Ch R = 1 ,35570   ,461,461,461
BEGIN DESCRIPTION:
Rocky Creek 64.0
END DESCRIPTION:
XS GIS Cut Line= 3
      2512874.98     13874624.99        2512475.       13874425.
      2512075.01       13874225.
#Sta/Elev= 30
  4545.1  499.17  4657.1  489.37  4719.9  484.91  4872.1  477.88  4880.5  476.88
  4902.9  471.54  4911.2  471.89  4916.8  470.77  4925.2  473.38  4981.1  470.26
  4981.6  469.76  4986.7  470.26  5006.3  471.22  5014.7  470.28  5031.5  471.94
  5045.4  473.03    5051  471.68  5059.4  474.02  5067.8   474.6    5116  473.71
  5162.8  473.79  5227.9   476.2  5274.6  477.74  5319.3  482.64  5341.7  482.99
  5358.5  485.72    5364  485.25  5372.4  486.46  5386.4  485.12  5439.5  489.48
#Mann= 8 ,-1 , 0
  4545.1     .07       0  4657.1     .05       0  4719.9      .1       0
  4981.1     .05       0  4986.7      .1       0  5031.5     .12       0
    5116     .05       0  5227.9     .12       0
Bank Sta=4981.1,4986.7
XS Rating Curve= 0 ,0
Exp/Cntr=0.3,0.1

Type RM Length L Ch R = 1 ,35109   ,428,428,428
BEGIN DESCRIPTION:
Rocky Creek 63.0
END DESCRIPTION:
XS GIS Cut Line= 3
      2512874.97     13874374.98        2512475.       13874025.
      2512074.99     13873824.99
#Sta/Elev= 30
  4468.3  489.42  4602.6     482  4616.8  482.47    4631  480.85  4659.5  480.14
  4702.2   477.4    4837  474.82  4843.6  473.09  4851.2  473.41  4857.9  471.09
  4865.5  469.99  4907.2  471.58  4964.2  471.75    4986  470.16  4993.7  466.94
  4994.1  466.44  4999.3  466.94  5008.2  467.95  5013.7  470.81  5022.1  472.54
  5036.1  473.63  5066.9  473.24  5103.2  474.76    5120  474.17  5142.3  475.77
  5192.6  475.89  5304.4  480.78  5326.8  480.95  5388.3  486.22    5447   495.8
#Mann= 3 ,-1 , 0
  4468.3     .12       0  4993.7     .05       0  4999.3     .12       0
Bank Sta=4993.7,4999.3
XS Rating Curve= 0 ,0
Exp/Cntr=0.3,0.1

Type RM Length L Ch R = 1 ,34681   ,462,462,462
BEGIN DESCRIPTION:
Rocky Creek 62.0
END DESCRIPTION:
XS GIS Cut Line= 3
      2513025.02     13874075.02        2512675.       13873675.
      2512275.05     13873625.01
#Sta/Elev= 30
  4463.9  487.78  4485.3  486.88  4506.2  484.86  4513.8  485.01  4542.2  482.53
  4676.5  476.24  4683.6  475.41  4769.1  473.48  4782.8  473.84  4796.6  472.94
  4843.7  473.14  4945.6  472.28  4953.2  470.85  4974.1  468.96  4981.7  469.84
  4988.3  467.73    4998   468.2  5002.7  466.55  5003.2  466.05  5008.3  466.55
  5033.2  469.09  5038.3   468.6  5045.8  469.85  5096.2  470.44  5176.8  473.84
  5231.5  474.75  5257.5  476.91  5307.8  478.62  5360.8   483.5  5398.5  485.78
#Mann= 5 ,-1 , 0
  4463.9     .12       0  4843.7      .1       0  5002.7     .05       0
  5008.3      .1       0  5231.5     .12       0
Bank Sta=5002.7,5008.3
XS Rating Curve= 0 ,0
Exp/Cntr=0.3,0.1

Type RM Length L Ch R = 1 ,34219   ,479,479,479
BEGIN DESCRIPTION:
Rocky Creek 61.0
END DESCRIPTION:
XS GIS Cut Line= 3
      2513224.95     13873325.01        2512875.       13873375.
        2512475.       13873125.
#Sta/Elev= 30
  4638.4  489.69  4658.6  488.81  4668.7     487  4681.8  485.84  4688.9  484.87
  4719.2  483.73  4739.4  480.43  4759.6  479.89  4779.8  477.24  4840.4  474.61
  4860.6  472.74  4941.4  470.13  4951.5  467.03  4971.7  467.77  4981.8  466.85
  4989.4  464.73  4996.5  464.28    4997  463.78  5002.6  464.28  5005.5  466.33
    5042  466.51  5067.5  469.13  5099.8  471.01  5209.5  474.12  5239.5  476.18
  5288.6   481.3    5325  484.65  5376.9  488.01  5428.2  493.78  5463.6  495.81
#Mann= 6 ,-1 , 0
  4638.4     .07       0  4681.8     .12       0  4996.5     .05       0
  5002.6     .12       0  5067.5      .1       0  5288.6     .12       0
Bank Sta=4996.5,5002.6
XS Rating Curve= 0 ,0
Exp/Cntr=0.3,0.1

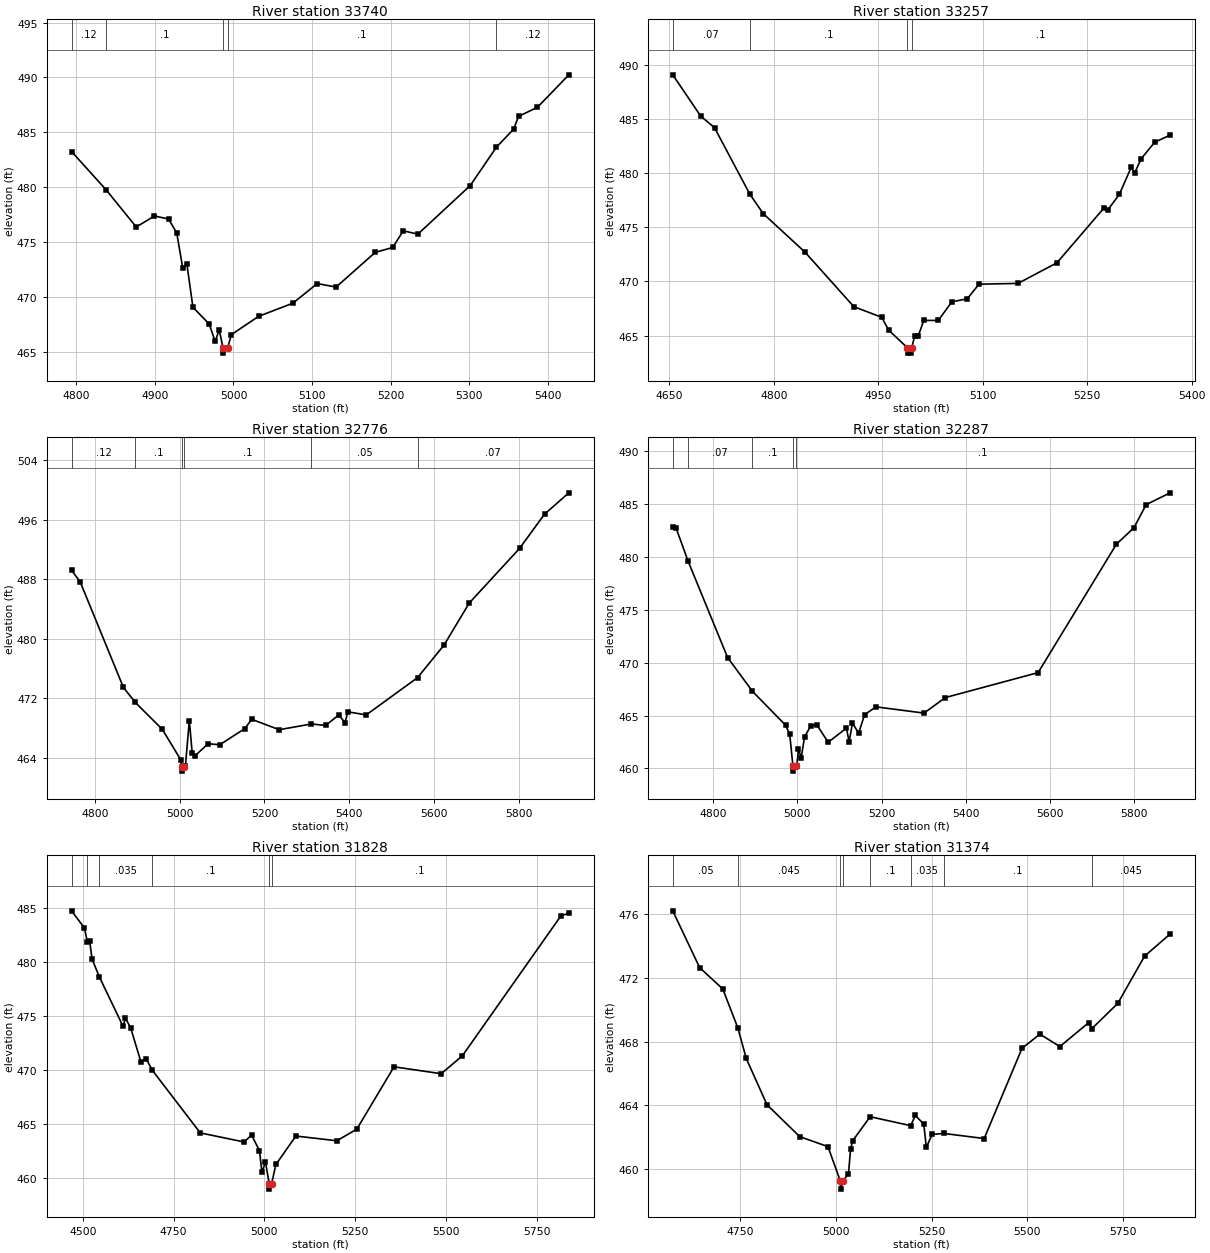
Type RM Length L Ch R = 1 ,33740   ,483,483,483
BEGIN DESCRIPTION:
Rocky Creek 60.0
END DESCRIPTION:
XS GIS Cut Line= 3
      2513174.96     13872875.01        2512975.       13872925.
      2512575.01       13873075.
#Sta/Elev= 30
  4793.8  483.24  4837.8  479.75  4876.2  476.36  4899.4  477.36  4917.4  477.09
  4927.8   475.8  4935.5  472.59  4940.6  473.03  4948.4  469.04    4969  467.52
  4976.7  465.93  4981.9  466.99  4986.6  465.36  4987.1  464.86  4992.7  465.36
  4997.3  466.54  5031.9  468.21  5075.6  469.41  5106.7   471.2  5130.7  470.88
  5180.6  474.05  5202.8  474.49  5216.2  476.01  5234.9  475.71  5301.6  480.14
  5334.9  483.64  5356.8  485.28    5363  486.44  5387.1  487.27  5427.1  490.23
#Mann= 5 ,-1 , 0
  4793.8     .12       0  4837.8      .1       0  4986.6     .05       0
  4992.7      .1       0  5334.9     .12       0
Bank Sta=4986.6,4992.7
XS Rating Curve= 0 ,0
Exp/Cntr=0.3,0.1

Type RM Length L Ch R = 1 ,33257   ,481,481,481
BEGIN DESCRIPTION:
Rocky Creek 59.0
END DESCRIPTION:
XS GIS Cut Line= 3
      2513425.04       13872475.        2513075.       13872475.
      2512725.04     13872574.99
#Sta/Elev= 30
    4655  489.09    4695  485.29    4715   484.2  4765.5  478.08    4785  476.26
    4845   472.7    4915  467.67    4955  466.69    4965   465.5  4991.9  463.88
  4992.4  463.38  4997.6  463.38  4998.1  463.88  5002.5     465  5007.6     465
  5015.4   466.4  5036.2   466.4  5055.7  468.12  5077.8   468.4  5094.7  469.75
  5150.6  469.82  5206.5  471.72  5274.1  476.79  5279.3  476.58  5296.2  478.05
  5313.1  480.53  5318.3  480.04  5327.4  481.33  5346.9  482.86    5369  483.52
#Mann= 4 ,-1 , 0
    4655     .07       0  4765.5      .1       0  4991.9     .05       0
  4998.1      .1       0
Bank Sta=4991.9,4998.1
XS Rating Curve= 0 ,0
Exp/Cntr=0.3,0.1

Type RM Length L Ch R = 1 ,32776   ,489,489,489
BEGIN DESCRIPTION:
Rocky Creek 58.0
END DESCRIPTION:
XS GIS Cut Line= 3
      2513424.95     13871975.01        2513175.       13872025.
      2512374.98     13872475.01
#Sta/Elev= 30
  4745.1  489.22  4765.4  487.67  4867.4  473.47  4895.6  471.44  4959.2  467.83
  5002.9  463.71  5004.9  462.71  5005.4  462.21  5011.1  462.71  5013.7  462.95
  5022.9  469.01  5029.6  464.68  5035.4  464.23  5067.2  465.89  5094.7  465.76
  5153.9  467.93  5169.9  469.18  5234.9  467.78  5310.9  468.55  5344.2  468.35
  5375.1  469.75  5390.1  468.74  5396.8  470.18  5440.1  469.77  5561.1  474.78
  5623.7  479.17    5683  484.81  5801.6  492.15  5860.5  496.76  5917.9  499.63
#Mann= 6 ,-1 , 0
  4745.1     .12       0  4895.6      .1       0  5004.9     .05       0
  5011.1      .1       0  5310.9     .05       0  5561.1     .07       0
Bank Sta=5004.9,5011.1
XS Rating Curve= 0 ,0
Exp/Cntr=0.3,0.1

Type RM Length L Ch R = 1 ,32287   ,459,459,459
BEGIN DESCRIPTION:
Rocky Creek 57.0
END DESCRIPTION:
XS GIS Cut Line= 3
      2513425.02     13871825.03        2513275.       13871575.
      2512575.01     13871025.01
#Sta/Elev= 30
  4703.9   482.8  4711.7  482.75    4740  479.64  4834.2  470.49  4893.3  467.29
  4972.2  464.08  4981.9  463.22  4989.4  460.24  4989.9  459.74  4995.7  460.24
  4998.7  460.24  5002.7  461.84  5009.1     461  5017.2  462.99  5031.6     464
  5046.1  464.13  5073.2  462.47  5116.6  463.81    5123  462.52    5131  464.29
  5145.5  463.33  5159.9  465.09  5187.1  465.82    5301  465.23  5351.6   466.7
  5572.1  469.06  5758.2  481.21  5799.9  482.77  5828.8  484.95  5885.7  486.07
#Mann= 5 ,-1 , 0
  4703.9     .12       0    4740     .07       0  4893.3      .1       0
  4989.4     .05       0  4995.7      .1       0
Bank Sta=4989.4,4995.7
XS Rating Curve= 0 ,0
Exp/Cntr=0.3,0.1

Type RM Length L Ch R = 1 ,31828   ,454,454,454
BEGIN DESCRIPTION:
Rocky Creek 56.0
END DESCRIPTION:
XS GIS Cut Line= 3
        2513775.       13871625.        2513425.       13871225.
      2512624.96     13870974.99
#Sta/Elev= 30
    4469  484.72  4504.6  483.13  4512.4  481.88  4518.8  481.97  4525.5  480.26
  4545.8   478.6  4610.9  474.04  4617.5  474.79  4631.8  473.91  4660.2  470.74
  4674.5  471.06  4690.8  470.01  4823.5  464.19    4944  463.35  4964.9  463.98
  4986.7  462.54  4993.4  460.53  5003.1  461.52  5013.4  459.49  5013.9  458.99
    5020  459.49  5031.9  461.27  5086.9   463.9  5199.6  463.46  5254.6  464.53
  5357.2   470.3  5487.2  469.66  5545.3  471.31  5817.2  484.27  5838.7  484.49
#Mann= 6 ,-1 , 0
    4469     .05       0  4512.4     .07       0  4545.8    .035       0
  4690.8      .1       0  5013.4     .05       0    5020      .1       0
Bank Sta=5013.4,5020
XS Rating Curve= 0 ,0
Exp/Cntr=0.3,0.1

Type RM Length L Ch R = 1 ,31374   ,446,446,446
BEGIN DESCRIPTION:
Rocky Creek 55.0
END DESCRIPTION:
XS GIS Cut Line= 3
      2513874.99     13871374.99        2513725.       13870975.
        2512925.       13870625.
#Sta/Elev= 30
  4573.2  476.22  4643.5  472.65    4704  471.31  4743.7  468.84  4765.4  466.94
  4819.7  464.03  4905.2  462.03    4979   461.4  5011.5  459.23    5012  458.73
  5018.1  459.23  5032.7   459.7  5038.2  461.26    5044  461.78  5089.3  463.28
  5195.5  462.72  5207.4  463.36  5229.6  462.82  5236.2  461.35  5251.4  462.17
  5281.7  462.23  5387.5  461.91  5486.5  467.58  5533.3  468.47  5585.5  467.69
  5661.1   469.2  5669.3  468.82  5736.8   470.4  5806.9  473.37  5873.6  474.76
#Mann= 8 ,-1 , 0
  4573.2     .05       0  4743.7    .045       0  5011.5    .045       0
  5018.1    .045       0  5089.3      .1       0  5195.5    .035       0
  5281.7      .1       0  5669.3    .045       0
Bank Sta=5011.5,5018.1
XS Rating Curve= 0 ,0
Exp/Cntr=0.3,0.1

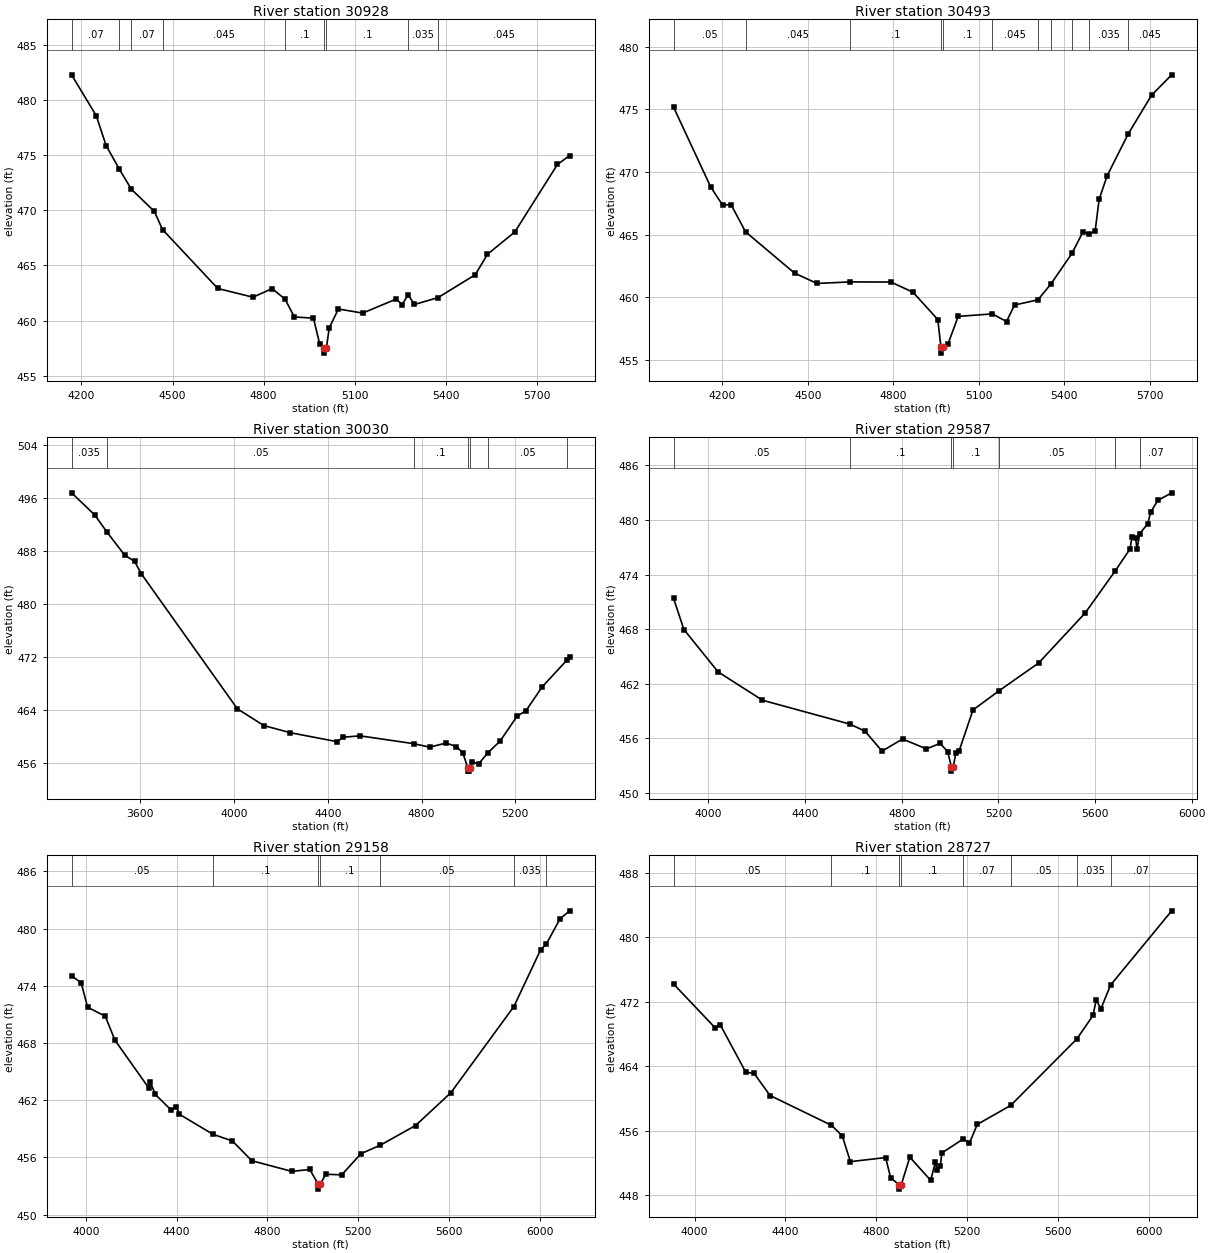
Type RM Length L Ch R = 1 ,30928   ,435,435,435
BEGIN DESCRIPTION:
Rocky Creek 54.0
END DESCRIPTION:
XS GIS Cut Line= 3
      2514525.02     13870875.01        2513725.       13870625.
      2512925.04       13870575.
#Sta/Elev= 30
  4167.6  482.28  4248.8  478.58  4281.3  475.87  4324.7  473.73  4364.8   471.9
    4440   469.9  4467.1  468.25    4649  462.91  4764.8  462.12  4827.7   462.9
  4870.3  461.95    4901  460.33  4963.9  460.22  4984.3  457.89  4999.6  457.55
  5000.1  457.05  5006.7  457.55  5015.8  459.33  5045.9  461.05    5126  460.68
  5236.2  461.95  5256.3  461.45  5275.5  462.35  5296.3  461.46    5374  462.08
  5496.7  464.16  5536.8  466.01    5627  468.04  5767.3  474.16  5807.3  474.96
#Mann= 9 ,-1 , 0
  4167.6     .07       0  4324.7     .05       0  4364.8     .07       0
  4467.1    .045       0  4870.3      .1       0  4999.6     .05       0
  5006.7      .1       0  5275.5    .035       0    5374    .045       0
Bank Sta=4999.6,5006.7
XS Rating Curve= 0 ,0
Exp/Cntr=0.3,0.1

Type RM Length L Ch R = 1 ,30493   ,463,463,463
BEGIN DESCRIPTION:
Rocky Creek 53.0
END DESCRIPTION:
XS GIS Cut Line= 3
      2514425.01     13870775.01        2513625.       13870225.
      2513074.97     13869674.97
#Sta/Elev= 30
  4028.5  475.16  4158.4  468.82  4200.3  467.36  4230.1   467.4  4280.9  465.23
  4453.2  461.93  4531.8  461.11  4648.8  461.23  4791.7  461.22  4869.4   460.4
    4956  458.23  4966.9  456.05  4967.4  455.55  4974.9  456.05  4991.9  456.28
  5027.6  458.48  5147.7  458.68  5197.3  458.07  5225.6  459.39  5307.6   459.8
  5352.7  461.05    5427   463.5    5466  465.24  5488.2  465.03  5508.5   465.3
  5522.6  467.83  5550.9  469.71  5623.7     473  5706.4  476.12  5777.2  477.75
#Mann= 11 ,-1 , 0
  4028.5     .05       0  4280.9    .045       0  4648.8      .1       0
  4966.9     .05       0  4974.9      .1       0  5147.7    .045       0
  5307.6     .05       0  5352.7    .035       0    5427     .05       0
  5488.2    .035       0  5623.7    .045       0
Bank Sta=4966.9,4974.9
XS Rating Curve= 0 ,0
Exp/Cntr=0.3,0.1

Type RM Length L Ch R = 1 ,30030   ,443,443,443
BEGIN DESCRIPTION:
Rocky Creek 52.0
END DESCRIPTION:
XS GIS Cut Line= 3
      2514875.03     13870975.03        2513675.       13869775.
        2513275.       13869625.
#Sta/Elev= 30
  3307.4  496.74  3406.4  493.39  3457.6  490.85  3533.7  487.33  3576.1  486.39
  3604.4  484.53  4014.6  464.11  4127.7  461.58  4240.8   460.5  4438.8  459.16
  4467.1  459.83  4537.8  460.03  4767.9  458.84  4834.8  458.32  4905.5  458.95
  4947.9  458.41  4976.2  457.48    4997   455.2  4997.5   454.7  5004.5   454.7
    5005   455.2  5014.3  456.02  5044.6  455.83  5082.9  457.47  5135.3  459.24
  5207.4  462.99  5245.7  463.84  5314.2  467.41  5419.6  471.45  5431.7  471.95
#Mann= 7 ,-1 , 0
  3307.4    .035       0  3457.6     .05       0  4767.9      .1       0
    4997     .05       0    5005      .1       0  5082.9     .05       0
  5419.6    .035       0
Bank Sta=4997,5005
XS Rating Curve= 0 ,0
Exp/Cntr=0.3,0.1

Type RM Length L Ch R = 1 ,29587   ,429,429,429
BEGIN DESCRIPTION:
Rocky Creek 51.0
END DESCRIPTION:
XS GIS Cut Line= 3
      2514775.03     13870375.03        2513975.       13869575.
      2513424.98     13868824.97
#Sta/Elev= 30
  3855.8  471.38  3898.3  467.97  4039.7  463.32  4223.5   460.2  4586.3  457.57
  4647.8   456.8  4718.5  454.61  4803.4  455.94  4902.4  454.85  4958.9  455.46
  4990.3  454.55  5005.1  452.91  5005.6  452.41  5013.3  452.91  5023.9  454.38
  5036.8  454.58  5094.9  459.13  5203.4  461.25  5366.6  464.29  5558.8  469.77
  5684.4  474.44  5744.8  476.82  5753.2  478.14  5767.9  478.01  5774.1  476.84
  5785.2   478.5  5818.1  479.59  5830.5  480.87  5859.8  482.15  5917.3  482.99
#Mann= 7 ,-1 , 0
  3855.8     .05       0  4586.3      .1       0  5005.1     .05       0
  5013.3      .1       0  5203.4     .05       0  5684.4    .035       0
  5785.2     .07       0
Bank Sta=5005.1,5013.3
XS Rating Curve= 0 ,0
Exp/Cntr=0.3,0.1

Type RM Length L Ch R = 1 ,29158   ,431,431,431
BEGIN DESCRIPTION:
Rocky Creek 50.0
END DESCRIPTION:
XS GIS Cut Line= 3
      2515024.98     13870374.97        2514325.       13869575.
      2513525.03     13868775.03
#Sta/Elev= 30
  3937.3  475.04  3979.5  474.32    4008  471.75  4085.8  470.81  4128.5  468.29
  4277.5  463.28  4284.2  463.93    4306  462.61  4376.2  460.97  4398.1  461.33
  4412.3  460.53    4560  458.43  4645.8  457.73  4731.2  455.66  4907.7  454.54
  4986.5  454.74  5024.5  453.18    5025  452.68  5032.7  453.18  5056.8  454.24
  5127.6  454.18  5212.4   456.4    5297  457.28  5452.8  459.35  5608.4  462.79
  5885.9  471.82  6004.4   477.8  6028.1  478.34  6089.2  481.02  6131.6  481.86
#Mann= 7 ,-1 , 0
  3937.3     .05       0    4560      .1       0  5024.5     .05       0
  5032.7      .1       0    5297     .05       0  5885.9    .035       0
  6028.1     .05       0
Bank Sta=5024.5,5032.7
XS Rating Curve= 0 ,0
Exp/Cntr=0.3,0.1

Type RM Length L Ch R = 1 ,28727   ,448,448,448
BEGIN DESCRIPTION:
Rocky Creek 49.0
END DESCRIPTION:
XS GIS Cut Line= 3
      2515274.99     13869974.99        2514475.       13869225.
      2513674.97     13868474.97
#Sta/Elev= 30
    3908  474.18  4091.9  468.72  4113.4  469.12  4226.2  463.22  4261.9  463.11
  4332.7  460.35  4603.2  456.65  4650.7  455.34  4686.3  452.14  4841.7  452.65
  4863.2  450.17  4901.5  449.23    4902  448.73  4909.9  449.23  4948.1  452.69
    5040  449.82    5061  452.12  5068.3  451.07  5082.5  451.65  5089.3  453.22
  5184.3  454.98    5210   454.4  5245.1  456.76  5392.4  459.12  5683.6  467.37
  5754.6  470.28  5768.8   472.2  5789.8  471.12  5831.9  474.05  6101.2  483.27
#Mann= 8 ,-1 , 0
    3908     .05       0  4603.2      .1       0  4901.5     .05       0
  4909.9      .1       0  5184.3     .07       0  5392.4     .05       0
  5683.6    .035       0  5831.9     .07       0
Bank Sta=4901.5,4909.9
XS Rating Curve= 0 ,0
Exp/Cntr=0.3,0.1

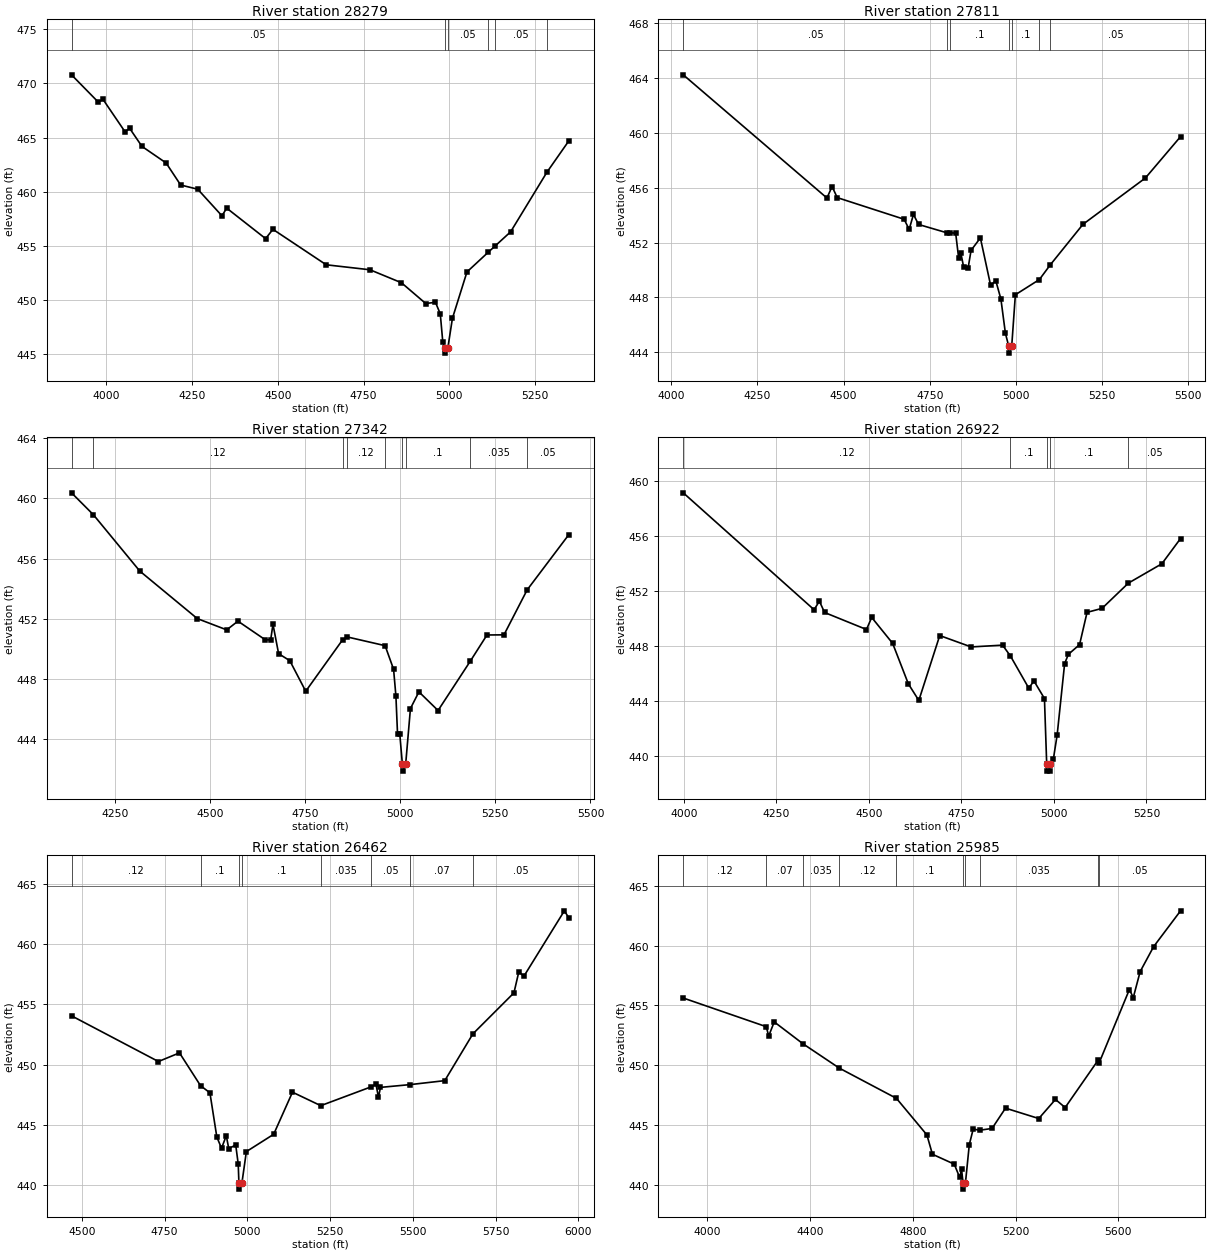
Type RM Length L Ch R = 1 ,28279   ,468,468,468
BEGIN DESCRIPTION:
Rocky Creek 48.0
END DESCRIPTION:
XS GIS Cut Line= 3
      2515424.99     13869674.98        2514675.       13868875.
      2514425.01     13868625.01
#Sta/Elev= 30
  3898.6   470.8  3976.5  468.28  3990.6  468.52  4054.2  465.55  4068.3  465.84
    4104  464.18  4174.3  462.65  4216.8  460.61  4266.6  460.22  4337.2  457.76
  4351.1  458.47  4464.5  455.65  4485.9  456.51  4641.3  453.23  4768.8  452.77
  4860.6  451.57  4931.4  449.65  4959.8  449.76  4973.9  448.69  4981.2  446.09
  4987.5  445.56    4988  445.06    4996  445.56  5009.3  448.28  5051.7  452.57
    5114   454.4  5133.1  454.95    5179  456.28  5284.8  461.79  5348.7  464.69
#Mann= 6 ,-1 , 0
  3898.6     .05       0  4987.5     .05       0    4996     .05       0
    5114     .07       0  5133.1     .05       0  5284.8     .07       0
Bank Sta=4987.5,4996
XS Rating Curve= 0 ,0
Exp/Cntr=0.3,0.1

Type RM Length L Ch R = 1 ,27811   ,469,469,469
BEGIN DESCRIPTION:
Rocky Creek 47.0
END DESCRIPTION:
XS GIS Cut Line= 3
      2515525.02     13869325.03        2514975.       13868525.
      2514574.97     13868274.98
#Sta/Elev= 30
  4034.8  464.24  4451.6  455.25  4466.5  456.09  4481.4  455.28  4675.5   453.7
  4690.1  452.96  4702.6  454.05  4717.4  453.32  4801.2   452.7  4808.7  452.71
    4825  452.69  4833.8  450.85  4839.9  451.24  4847.9  450.25  4860.9  450.11
  4869.7  451.43  4896.7  452.34  4926.5  448.87  4941.4  449.22  4956.3  447.87
  4969.3  445.38    4979  444.43  4979.5  443.93  4987.6  444.43  4998.2  448.19
  5067.9   449.3  5099.4  450.37  5194.3  453.33  5375.4  456.71  5477.4  459.73
#Mann= 7 ,-1 , 0
  4034.8     .05       0  4801.2     .07       0  4808.7      .1       0
    4979     .05       0  4987.6      .1       0  5067.9     .07       0
  5099.4     .05       0
Bank Sta=4979,4987.6
XS Rating Curve= 0 ,0
Exp/Cntr=0.3,0.1

Type RM Length L Ch R = 1 ,27342   ,420,420,420
BEGIN DESCRIPTION:
Rocky Creek 46.0
END DESCRIPTION:
XS GIS Cut Line= 3
      2515874.99     13868624.99        2515175.       13868125.
      2514775.03     13867925.01
#Sta/Elev= 30
  4135.7  460.37  4193.3  458.91  4315.1  455.17  4466.3  452.01  4543.7  451.26
  4573.2  451.84  4644.5  450.61  4659.2  450.59  4665.3  451.63  4680.1  449.68
  4709.6  449.21  4751.4  447.18  4848.1  450.59  4860.5  450.79  4960.1  450.21
  4982.4  448.64  4988.5  446.87  4992.8  444.33  4998.7  444.33  5005.4  442.37
  5005.9  441.87  5014.3  442.37  5026.7  446.03    5049  447.14  5099.3   445.9
  5184.6   449.2  5227.9  450.92  5272.6  450.93  5333.6  453.92  5443.1  457.59
#Mann= 9 ,-1 , 0
  4135.7     .07       0  4193.3     .12       0  4848.1      .1       0
  4860.5     .12       0  4960.1      .1       0  5005.4     .05       0
  5014.3      .1       0  5184.6    .035       0  5333.6     .05       0
Bank Sta=5005.4,5014.3
XS Rating Curve= 0 ,0
Exp/Cntr=0.3,0.1

Type RM Length L Ch R = 1 ,26922   ,460,460,460
BEGIN DESCRIPTION:
Rocky Creek 45.0
END DESCRIPTION:
XS GIS Cut Line= 3
      2515924.99     13868474.99        2515225.       13867775.
      2514874.99       13867725.
#Sta/Elev= 30
  3998.5  459.16    4352  450.64  4366.2  451.27  4380.3  450.44  4493.5   449.2
  4507.6  450.08  4564.2  448.19  4606.6  445.24  4634.9  444.03  4691.4  448.76
  4776.3  447.93  4861.2  448.06  4882.4  447.27  4931.9  444.93    4946  445.45
  4974.3  444.17  4980.4  439.38  4980.9  438.88  4988.9  438.88  4989.4  439.38
  4998.5  439.78  5008.6  441.51  5028.8  446.71  5038.9  447.39  5069.2   448.1
  5089.4  450.45  5129.9  450.74    5201  452.58  5291.5  453.99    5342  455.83
#Mann= 5 ,-1 , 0
  3998.5     .12       0  4882.4      .1       0  4980.4     .05       0
  4989.4      .1       0    5201     .05       0
Bank Sta=4980.4,4989.4
XS Rating Curve= 0 ,0
Exp/Cntr=0.3,0.1

Type RM Length L Ch R = 1 ,26462   ,477,477,477
BEGIN DESCRIPTION:
Rocky Creek 44.0
END DESCRIPTION:
XS GIS Cut Line= 3
      2515975.03     13868125.03        2515625.       13867725.
      2514824.98     13867174.99
#Sta/Elev= 30
  4468.7  454.05  4731.2  450.25  4794.8  450.97  4858.5  448.24  4886.8  447.65
  4907.7  443.97  4921.9  443.04  4936.2  444.08  4943.8     443  4964.7  443.32
  4972.3  441.73  4974.4  440.14  4974.9  439.64  4983.4  440.14  4996.9  442.76
  5079.4   444.2  5136.2   447.7  5221.7  446.58  5374.3  448.15  5388.6  448.35
    5396  447.28  5402.1   448.1  5491.6  448.33  5596.3  448.66  5681.3  452.55
  5805.3  455.96  5820.2  457.73  5835.1  457.33  5957.6  462.78  5971.1   462.2
#Mann= 8 ,-1 , 0
  4468.7     .12       0  4858.5      .1       0  4974.4     .05       0
  4983.4      .1       0  5221.7    .035       0  5374.3     .05       0
  5491.6     .07       0  5681.3     .05       0
Bank Sta=4974.4,4983.4
XS Rating Curve= 0 ,0
Exp/Cntr=0.3,0.1

Type RM Length L Ch R = 1 ,25985   ,490,490,490
BEGIN DESCRIPTION:
Rocky Creek 43.0
END DESCRIPTION:
XS GIS Cut Line= 3
      2516375.03     13868175.03        2515625.       13867375.
      2514824.98       13867125.
#Sta/Elev= 30
  3907.3  455.62  4230.2  453.22  4239.7  452.44  4261.2  453.62    4373  451.79
  4514.5  449.75  4736.7  447.22  4855.2  444.16  4876.7  442.54  4961.7  441.71
  4982.7   440.6    4990  441.27    4996  440.12  4996.5  439.62  5005.1  440.12
  5020.2  443.35  5035.4  444.65  5060.1  444.55  5108.7   444.7  5161.1   446.4
  5290.5  445.53  5355.4  447.13  5393.1  446.45  5521.2  450.41    5525  450.17
    5643  456.33  5658.2  455.66  5684.9  457.83  5737.3  459.92  5842.1  462.92
#Mann= 10 ,-1 , 0
  3907.3     .12       0  4230.2     .07       0    4373    .035       0
  4514.5     .12       0  4736.7      .1       0    4996     .05       0
  5005.1      .1       0  5060.1    .035       0  5521.2     .07       0
    5525     .05       0
Bank Sta=4996,5005.1
XS Rating Curve= 0 ,0
Exp/Cntr=0.3,0.1