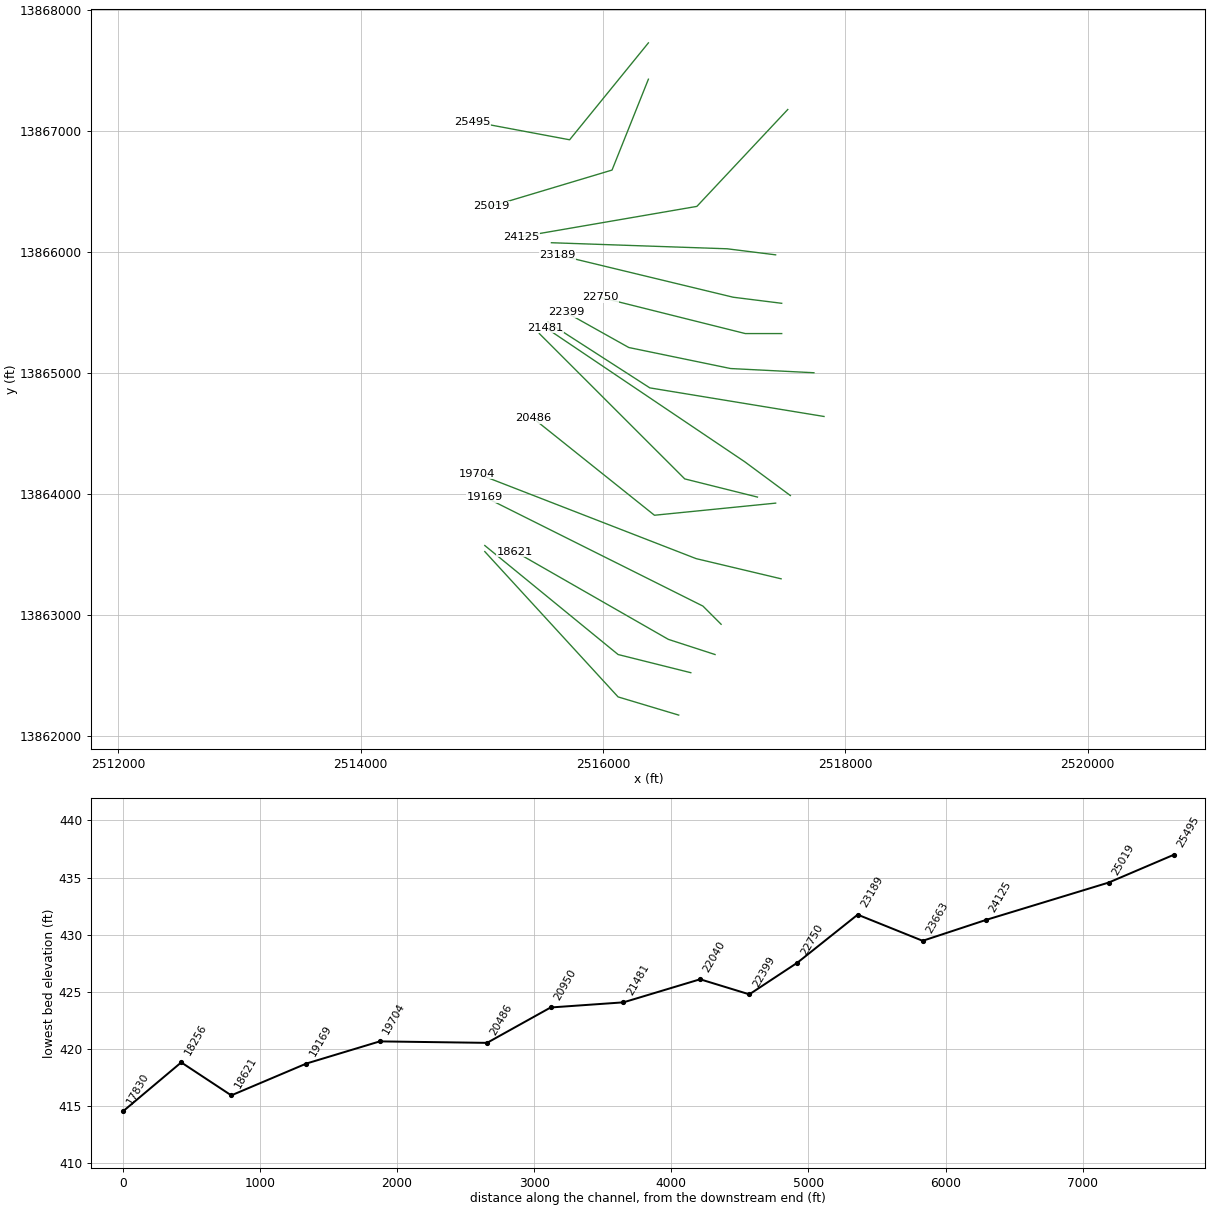
HEC-RAS study Rocky Creek.prj: Rocky Creek Base Level Engineering

--- Rocky Creek.g01 (geometry) --- (continued)

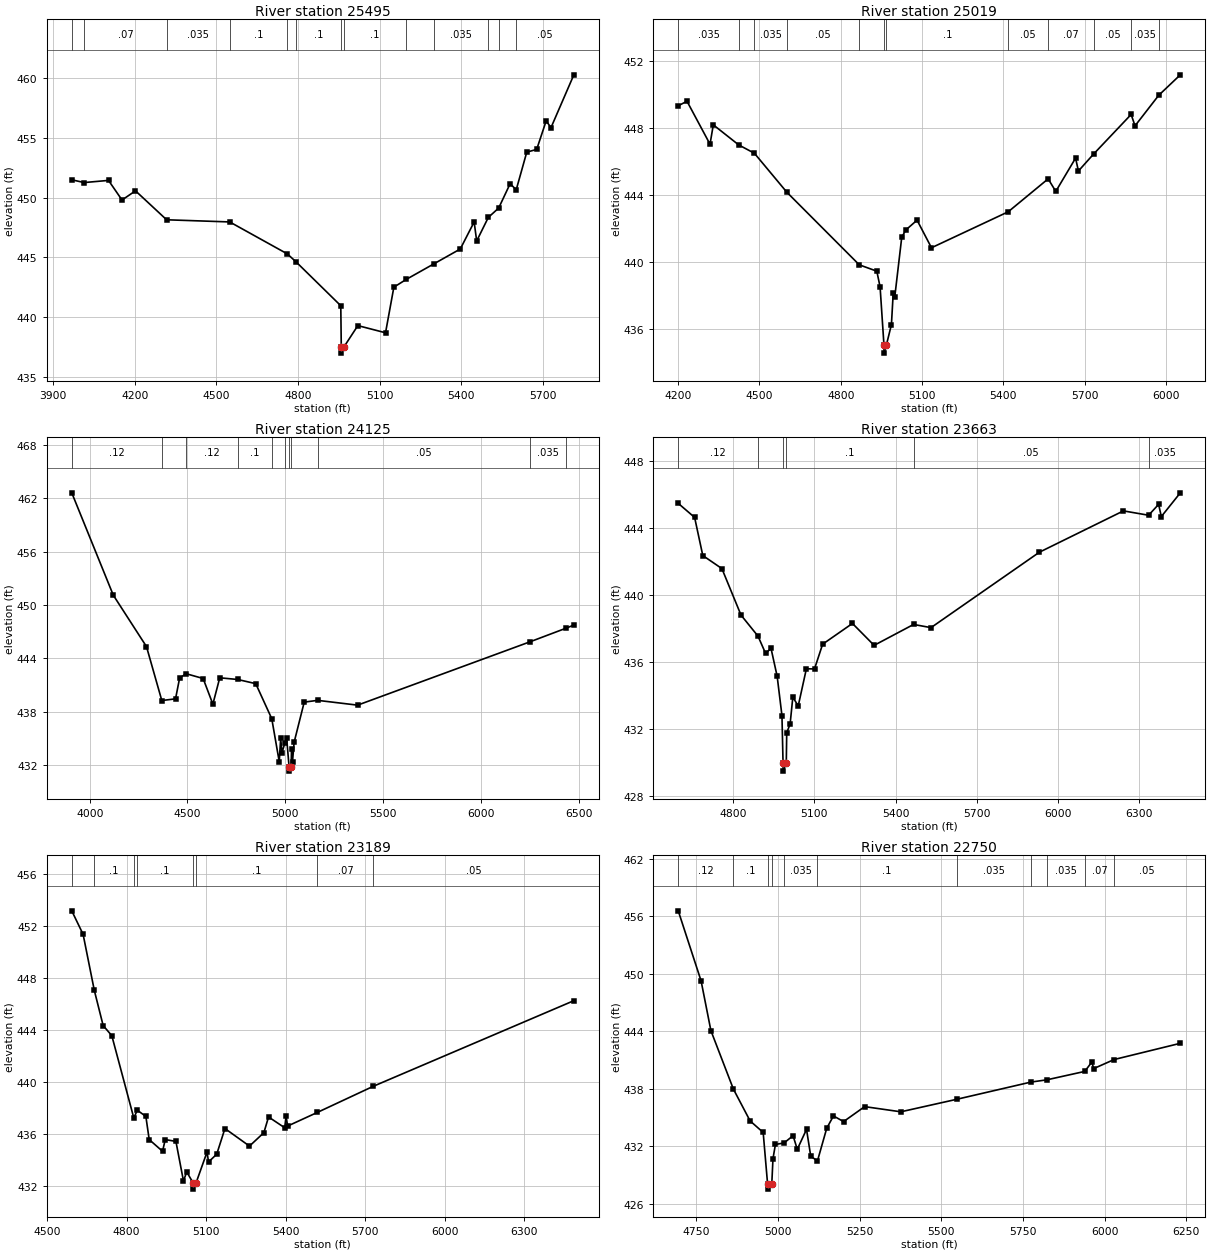
Type RM Length L Ch R = 1 ,25495   ,476,476,476
BEGIN DESCRIPTION:
Rocky Creek 42.0
END DESCRIPTION:
XS GIS Cut Line= 3
      2516374.98     13867724.98        2515725.       13866925.
      2514924.99       13867075.
#Sta/Elev= 30
  3968.8  451.48  4014.5  451.25  4103.8  451.43  4153.4  449.79  4202.9  450.56
  4317.3  448.14  4549.1  447.96  4760.8  445.29  4792.6  444.63  4957.2  440.96
    4959   437.5  4959.5     437  4968.3   437.5  5019.9   439.3  5121.6   438.7
  5152.2  442.51  5198.6  443.17  5299.4  444.46  5396.3   445.7  5447.2  447.96
  5456.5  446.37  5499.3  448.34  5537.3  449.12  5579.5  451.16  5601.7  450.64
  5640.5  453.79    5677  454.02  5711.7   456.4  5729.6  455.84  5813.5  460.25
#Mann= 13 ,-1 , 0
  3968.8     .12       0  4014.5     .07       0  4317.3    .035       0
  4549.1      .1       0  4760.8    .035       0  4792.6      .1       0
    4959     .05       0  4968.3      .1       0  5198.6     .05       0
  5299.4    .035       0  5499.3     .05       0  5537.3    .035       0
  5601.7     .05       0
Bank Sta=4959,4968.3
XS Rating Curve= 0 ,0
Exp/Cntr=0.3,0.1

Type RM Length L Ch R = 1 ,25019   ,894,894,894
BEGIN DESCRIPTION:
Rocky Creek 41.0
END DESCRIPTION:
XS GIS Cut Line= 3
      2516375.01     13867425.03        2516075.       13866675.
      2515075.04     13866375.01
#Sta/Elev= 30
  4200.7  449.35    4233  449.62  4317.9  447.05    4330  448.21  4423.7  447.01
  4481.6  446.51  4601.3  444.18  4868.4  439.84  4933.1  439.46  4945.2  438.52
  4959.4  435.06  4959.9  434.56  4968.7  435.06    4987  436.27  4993.7  438.17
  4999.1  437.89    5025  441.48  5039.8  441.92  5081.6  442.51  5134.7  440.86
  5417.7  443.01    5565  444.98  5593.2  444.23  5666.2  446.22  5676.7  445.45
  5732.5  446.46  5871.1  448.83  5885.5  448.15  5973.1  449.98  6052.5   451.2
#Mann= 12 ,-1 , 0
  4200.7    .035       0  4423.7     .05       0  4481.6    .035       0
  4601.3     .05       0  4868.4      .1       0  4959.4     .05       0
  4968.7      .1       0  5417.7     .05       0    5565     .07       0
  5732.5     .05       0  5871.1    .035       0  5973.1     .05       0
Bank Sta=4959.4,4968.7
XS Rating Curve= 0 ,0
Exp/Cntr=0.3,0.1

Type RM Length L Ch R = 1 ,24125   ,462,462,462
BEGIN DESCRIPTION:
Rocky Creek 40.0
END DESCRIPTION:
XS GIS Cut Line= 3
      2517524.99     13867174.98        2516775.       13866375.
      2515324.96     13866124.99
#Sta/Elev= 30
  3908.1  462.63  4120.3  451.11  4290.3  445.31  4368.6  439.24  4438.8  439.43
  4459.8  441.78  4493.1  442.26    4580  441.72  4629.8  438.83    4665   441.8
  4756.8  441.61  4849.1  441.14  4931.1  437.19  4969.3  432.35  4976.6  434.97
  4983.4  433.38  4997.8  434.44  5007.2  434.99  5019.6  431.79  5020.1  431.29
  5030.3  431.79  5032.1  433.79  5037.1  432.36  5045.3  434.53    5097  439.06
  5165.6  439.26    5370  438.72  6253.9  445.87  6437.8   447.4  6476.1  447.74
#Mann= 11 ,-1 , 0
  3908.1     .12       0  4368.6     .07       0  4493.1     .12       0
  4756.8      .1       0  4931.1     .12       0  4997.8      .1       0
  5019.6     .05       0  5030.3      .1       0  5165.6     .05       0
  6253.9    .035       0  6437.8     .05       0
Bank Sta=5019.6,5030.3
XS Rating Curve= 0 ,0
Exp/Cntr=0.3,0.1

Type RM Length L Ch R = 1 ,23663   ,474,474,474
BEGIN DESCRIPTION:
Rocky Creek 39.0
END DESCRIPTION:
XS GIS Cut Line= 3
        2517425.       13865975.        2517025.       13866025.
      2515574.98       13866075.
#Sta/Elev= 30
  4597.3  445.47  4657.8  444.63    4688  442.35  4758.5  441.57  4829.1  438.79
  4891.9  437.53  4919.8   436.5  4939.9   436.8  4962.6  435.13  4980.3  432.78
  4984.3  429.96  4984.8  429.46  4996.3  429.96  4997.9  431.76  5010.4  432.27
  5020.4  433.88  5040.4  433.36  5070.5  435.58  5100.5  435.57  5130.5  437.05
  5240.6  438.29  5320.6  436.98  5466.3  438.23  5530.7  438.04    5931  442.55
  6241.2  445.02  6334.2  444.76  6371.2  445.41  6381.2  444.68  6451.3   446.1
#Mann= 6 ,-1 , 0
  4597.3     .12       0  4891.9      .1       0  4984.3     .05       0
  4996.3      .1       0  5466.3     .05       0  6334.2    .035       0
Bank Sta=4984.3,4996.3
XS Rating Curve= 0 ,0
Exp/Cntr=0.3,0.1

Type RM Length L Ch R = 1 ,23189   ,439,439,439
BEGIN DESCRIPTION:
Rocky Creek 38.0
END DESCRIPTION:
XS GIS Cut Line= 3
      2517474.97       13865575.        2517075.       13865625.
      2515625.03     13865974.99
#Sta/Elev= 30
  4593.3  453.15  4636.1  451.34  4678.4  447.03  4711.7  444.33  4744.4  443.55
  4827.4  437.22  4840.5  437.82  4872.9  437.34  4885.5  435.56  4935.9  434.66
    4946  435.56  4986.3  435.42  5014.8  432.38  5027.2  433.07  5050.6  432.25
  5051.1  431.75  5062.7  432.25  5103.7   434.6  5109.5  433.84  5140.4  434.44
  5171.3  436.41  5263.9  435.06  5318.2  436.09  5335.9   437.3  5396.8  436.47
    5402  437.36  5407.9   436.6  5520.2  437.65  5731.4  439.66    6488  446.24
#Mann= 8 ,-1 , 0
  4593.3     .12       0  4678.4      .1       0  4827.4    .035       0
  4840.5      .1       0  5050.6     .05       0  5062.7      .1       0
  5520.2     .07       0  5731.4     .05       0
Bank Sta=5050.6,5062.7
XS Rating Curve= 0 ,0
Exp/Cntr=0.3,0.1

Type RM Length L Ch R = 1 ,22750   ,351,351,351
BEGIN DESCRIPTION:
Rocky Creek 37.0
END DESCRIPTION:
XS GIS Cut Line= 3
      2517474.97       13865325.        2517175.       13865325.
      2515975.01       13865625.
#Sta/Elev= 30
  4694.7  456.56  4764.7  449.25  4794.7  444.07  4863.5  437.98  4914.7  434.66
  4954.7  433.46  4968.3  428.05  4968.8  427.55    4981  428.05  4984.7  430.72
  4992.2  432.21  5018.5  432.36  5046.2  433.12  5059.1   431.7  5087.4  433.78
  5100.3  430.99  5120.8  430.48  5149.3   433.9  5169.9  435.18  5200.8  434.59
  5265.3  436.15  5376.1  435.61  5546.7  436.91  5774.4  438.71  5822.5  438.94
  5939.1  439.82    5961  440.81  5966.2  440.11  6029.1  441.06  6231.6  442.75
#Mann= 11 ,-1 , 0
  4694.7     .12       0  4863.5      .1       0  4968.3     .05       0
    4981      .1       0  5018.5    .035       0  5120.8      .1       0
  5546.7    .035       0  5774.4     .07       0  5822.5    .035       0
  5939.1     .07       0  6029.1     .05       0
Bank Sta=4968.3,4981
XS Rating Curve= 0 ,0
Exp/Cntr=0.3,0.1

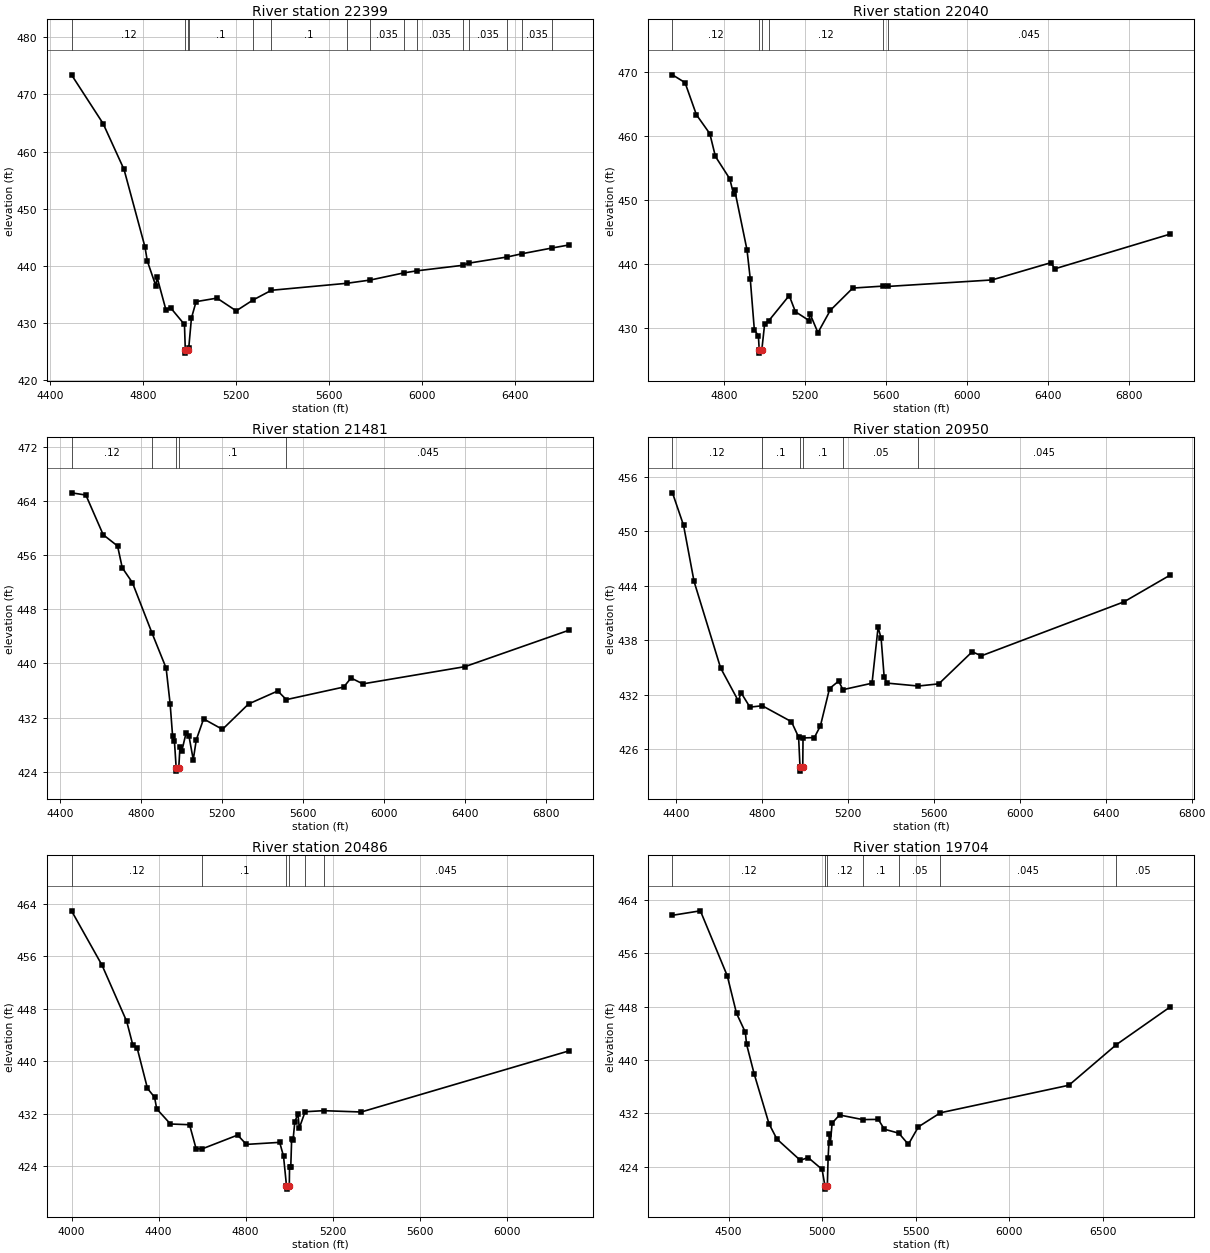
Type RM Length L Ch R = 1 ,22399   ,359,359,359
BEGIN DESCRIPTION:
B20208
END DESCRIPTION:
XS GIS Cut Line= 4
      2517741.04     13865001.55      2517053.52     13865036.27
      2516213.24     13865209.89      2515693.77     13865500.79
#Sta/Elev= 30
  4491.2  473.43  4627.4   464.9  4717.5  456.88  4807.6  443.35  4817.7  440.89
  4854.8  436.49  4859.8  438.05  4897.8  432.37  4917.8  432.71  4977.9  429.78
  4981.5  425.27    4982  424.77  4994.2  425.27  4996.3  425.67  5007.9  430.89
  5027.9  433.77    5118  434.39  5200.8  432.16  5272.5  434.04  5352.7  435.76
  5677.3  436.98  5778.5  437.55  5923.1   438.8  5980.9  439.17    6178  440.13
  6202.8   440.5  6369.7  441.59  6432.3  442.15  6561.4  443.15    6633  443.67
#Mann= 15 ,-1 , 0
  4491.2     .12       0  4981.5     .05       0  4994.2     .12       0
  4996.3      .1       0  5272.5    .035       0  5352.7      .1       0
  5677.3     .07       0  5778.5    .035       0  5923.1     .07       0
  5980.9    .035       0    6178     .07       0  6202.8    .035       0
  6369.7     .07       0  6432.3    .035       0  6561.4     .07       0
Bank Sta=4981.5,4994.2
XS Rating Curve= 0 ,0
Exp/Cntr=0.3,0.1

Type RM Length L Ch R = 1 ,22040   ,559,559,559
BEGIN DESCRIPTION:
B20207
END DESCRIPTION:
XS GIS Cut Line= 3
      2517824.35     13864640.44      2516386.85     13864876.55
      2515546.57     13865418.22
#Sta/Elev= 30
  4545.4   469.6  4607.5  468.38  4663.7  463.36    4730   460.4  4757.6  456.84
  4828.5  453.35  4847.4  450.93  4852.5  451.65  4913.8  442.22  4929.8  437.71
  4950.1   429.7  4969.9  428.83  4974.2  426.59  4974.7  426.09  4986.9  426.59
  5000.8  430.62  5020.5  431.12  5122.4  435.09  5152.8  432.57    5220  431.19
  5225.1  432.24  5264.3  429.29  5325.1  432.77  5436.5  436.26  5586.8  436.57
  5611.5  436.52  6124.3  437.53  6414.7  440.22  6435.8  439.28  7001.9  444.67
#Mann= 6 ,-1 , 0
  4545.4     .12       0  4974.2     .05       0  4986.9     .12       0
  5020.5     .12       0  5586.8      .1       0  5611.5    .045       0
Bank Sta=4974.2,4986.9
XS Rating Curve= 0 ,0
Exp/Cntr=0.3,0.1

Type RM Length L Ch R = 1 ,21481   ,531,531,531
BEGIN DESCRIPTION:
Rocky Creek 34.0
END DESCRIPTION:
XS GIS Cut Line= 3
      2517546.57     13863987.67      2517171.58     13864265.44
      2515524.99       13865375.
#Sta/Elev= 30
  4457.3  465.25  4528.1  464.92  4613.6  459.05  4684.5  457.38  4707.6  454.16
  4757.7  451.96  4854.8  444.47    4924  439.32    4944  433.97    4956  429.24
    4965  428.49  4973.6  424.57  4974.1  424.07  4986.4  424.57  4992.2   427.6
    5001  427.01    5022  429.65  5036.9  429.22  5057.9  425.76  5072.9  428.71
  5108.9   431.8  5201.9  430.25  5330.8  434.01  5474.8  435.93  5516.9  434.65
  5800.1  436.51  5836.3  437.85  5894.5  436.98  6398.2  439.53  6909.5   444.9
#Mann= 5 ,-1 , 0
  4457.3     .12       0  4854.8      .1       0  4973.6     .05       0
  4986.4      .1       0  5516.9    .045       0
Bank Sta=4973.6,4986.4
XS Rating Curve= 0 ,0
Exp/Cntr=0.3,0.1

Type RM Length L Ch R = 1 ,20950   ,464,464,464
BEGIN DESCRIPTION:
Rocky Creek 33.0
END DESCRIPTION:
XS GIS Cut Line= 3
      2517275.02       13863975.        2516675.       13864125.
      2515475.03     13865324.97
#Sta/Elev= 30
  4381.4  454.23    4433  450.66  4481.9  444.49  4605.6  434.97  4688.1  431.35
    4701  432.24  4742.2  430.66  4799.7  430.81  4935.5  429.06    4969  427.36
  4975.4  424.12  4975.9  423.62  4988.3  424.12  4989.6  427.27  5042.3  427.31
  5070.6   428.6    5113   432.7  5155.4  433.52  5175.6  432.58    5311  433.29
  5339.3  439.45  5353.4  438.23  5367.6  433.95  5381.7   433.3  5526.6  432.98
  5622.1  433.22  5777.7  436.75  5820.1   436.3  6484.8  442.24  6696.9  445.14
#Mann= 6 ,-1 , 0
  4381.4     .12       0  4799.7      .1       0  4975.4     .05       0
  4988.3      .1       0  5175.6     .05       0  5526.6    .045       0
Bank Sta=4975.4,4988.3
XS Rating Curve= 0 ,0
Exp/Cntr=0.3,0.1

Type RM Length L Ch R = 1 ,20486   ,782,782,782
BEGIN DESCRIPTION:
Rocky Creek 32.0
END DESCRIPTION:
XS GIS Cut Line= 3
      2517424.99       13863925.        2516425.       13863825.
      2515425.01       13864625.
#Sta/Elev= 30
  3999.5  462.95  4140.2  454.63  4253.3  446.09  4280.9  442.55    4301  442.07
  4348.7  435.88  4381.4  434.52  4391.4  432.75  4454.3  430.45  4542.2  430.34
  4572.3  426.69  4599.7  426.65  4763.3  428.76  4803.5  427.34  4956.7  427.65
  4974.3  425.54    4988  421.02  4988.5  420.52  5000.9  421.02    5002   423.9
  5007.7   423.9  5011.7  428.14  5018.1  427.99  5026.1  430.74  5040.5  432.04
  5046.9  429.84  5073.6  432.32  5158.4  432.48  5331.8  432.28  6285.1  441.58
#Mann= 6 ,-1 , 0
  3999.5     .12       0  4599.7      .1       0    4988     .05       0
  5000.9      .1       0  5073.6     .05       0  5158.4    .045       0
Bank Sta=4988,5000.9
XS Rating Curve= 0 ,0
Exp/Cntr=0.3,0.1

Type RM Length L Ch R = 1 ,19704   ,535,535,535
BEGIN DESCRIPTION:
Rocky Creek 31.0
END DESCRIPTION:
XS GIS Cut Line= 3
       2517470.2     13863300.16       2516768.8     13863466.83
      2514963.28     13864168.21
#Sta/Elev= 30
  4200.1  461.72  4349.3  462.39  4493.2  452.64  4542.5  447.02  4589.8  444.17
    4596  442.42  4637.1  437.92  4716.4  430.45  4758.5  428.16  4883.8  424.97
  4925.4  425.39  5000.2  423.61  5015.2  421.15  5015.7  420.65  5028.2  421.15
  5032.4  425.36    5039  428.86  5044.4  427.56  5053.8  430.55  5093.4  431.77
  5217.1  431.08  5300.6  431.11  5332.8  429.64  5410.4  429.04  5461.5  427.36
  5515.1  429.99  5632.8   432.1  6319.8  436.23  6573.7  442.32    6858  447.91
#Mann= 7 ,-1 , 0
  4200.1     .12       0  5015.2     .05       0  5028.2     .12       0
  5217.1      .1       0  5410.4     .05       0  5632.8    .045       0
  6573.7     .05       0
Bank Sta=5015.2,5028.2
XS Rating Curve= 0 ,0
Exp/Cntr=0.3,0.1

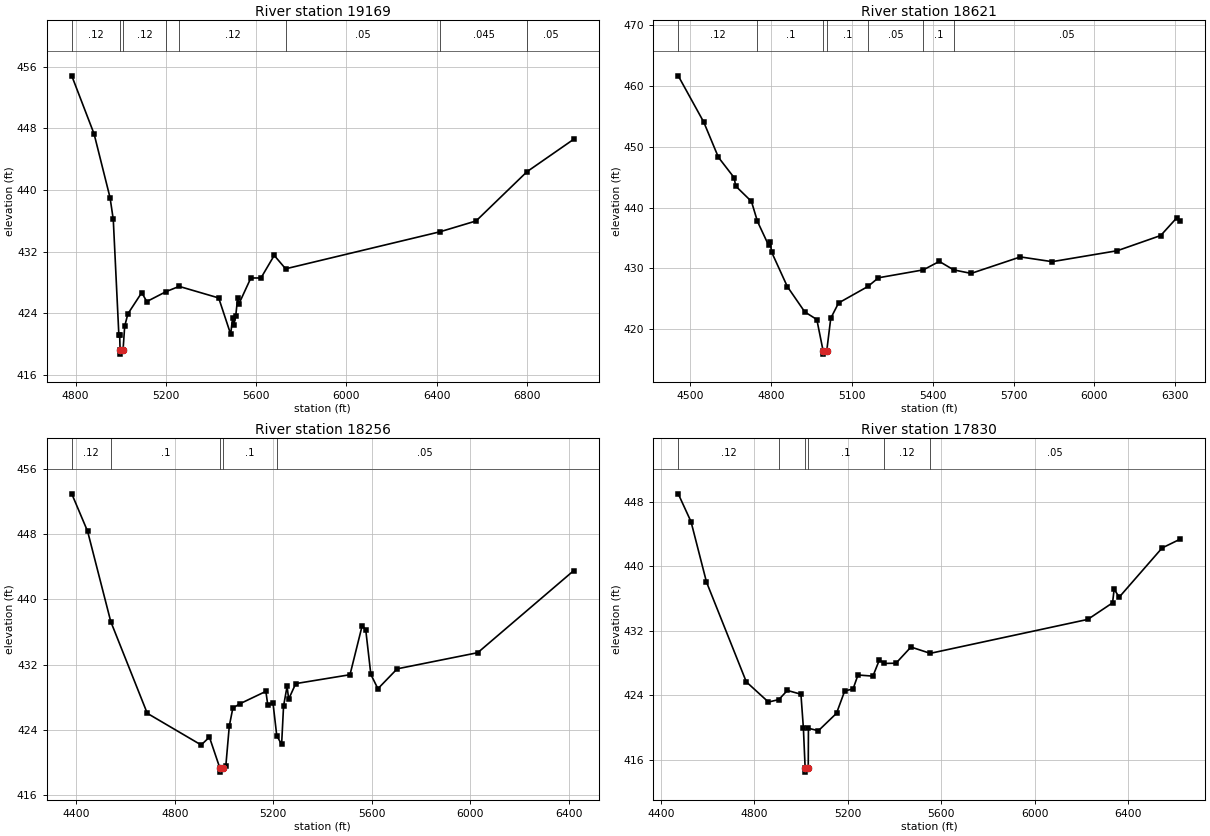
Type RM Length L Ch R = 1 ,19169   ,548,548,548
BEGIN DESCRIPTION:
Rocky Creek 30.0
END DESCRIPTION:
XS GIS Cut Line= 3
      2516975.03     13862924.97        2516825.       13863075.
      2515025.03     13863974.99
#Sta/Elev= 30
  4783.3  454.82  4882.3  447.27    4953     439  4967.2  436.18  4991.9  421.22
  4995.5  421.22  4997.4  419.21  4997.9  418.71  5010.4  419.21  5017.8  422.33
  5031.8  423.93  5093.3  426.69  5115.7  425.53  5201.9  426.83  5259.1   427.5
  5434.3     426  5487.4  421.29  5495.8  423.39  5501.4  422.52  5509.8  423.67
  5518.1  425.93  5523.7  425.22  5576.8  428.59  5621.6  428.59  5680.3  431.52
  5730.9  429.78  6415.5  434.59  6574.7  435.99  6800.3  442.38  7007.9   446.6
#Mann= 8 ,-1 , 0
  4783.3     .12       0  4997.4     .05       0  5010.4     .12       0
  5201.9      .1       0  5259.1     .12       0  5730.9     .05       0
  6415.5    .045       0  6800.3     .05       0
Bank Sta=4997.4,5010.4
XS Rating Curve= 0 ,0
Exp/Cntr=0.3,0.1

Type RM Length L Ch R = 1 ,18621   ,365,365,365
BEGIN DESCRIPTION:
Rocky Creek 29.0
END DESCRIPTION:
XS GIS Cut Line= 3
      2516924.97     13862675.01      2516539.63     13862800.16
      2515274.98     13863525.01
#Sta/Elev= 30
  4456.1  461.67  4550.7  454.07  4605.1  448.28  4663.8  444.91    4669  443.56
  4727.7  441.02  4750.1  437.73  4791.6  433.79  4796.9   434.3    4803  432.65
  4860.8  427.03  4925.6  422.86  4970.3  421.61  4993.8  416.42  4994.3  415.92
    5007  416.42    5022  421.82    5051  424.33  5159.7  427.04  5198.9  428.47
  5365.3  429.77  5424.8  431.16  5477.9  429.77  5542.8  429.19  5725.5   431.9
  5843.4  431.12  6085.1  432.92  6246.2  435.42  6305.2   438.3  6318.9  437.79
#Mann= 7 ,-1 , 0
  4456.1     .12       0  4750.1      .1       0  4993.8     .05       0
    5007      .1       0  5159.7     .05       0  5365.3      .1       0
  5477.9     .05       0
Bank Sta=4993.8,5007
XS Rating Curve= 0 ,0
Exp/Cntr=0.3,0.1

Type RM Length L Ch R = 1 ,18256   ,426,426,426
BEGIN DESCRIPTION:
Rocky Creek 28.0
END DESCRIPTION:
XS GIS Cut Line= 3
      2516725.01       13862525.        2516125.       13862675.
      2515025.03     13863574.97
#Sta/Elev= 30
    4381  452.92  4445.4  448.32  4539.3  437.27  4687.7  426.02  4906.7  422.14
  4940.2   423.1  4982.6  419.31  4983.1  418.81  4995.8  419.31  5006.7  419.52
    5021  424.47  5035.4  426.66  5064.1  427.19  5169.6  428.71  5177.5  426.98
  5198.3  427.33  5213.8  423.28  5233.5   422.2  5241.4  426.91  5255.7  429.32
  5262.2  427.76  5290.9  429.66  5511.3  430.75  5560.8  436.76  5575.2  436.27
    5596  430.79  5624.7  429.03  5702.9  431.47  6030.3  433.45  6420.7  443.52
#Mann= 5 ,-1 , 0
    4381     .12       0  4539.3      .1       0  4982.6     .05       0
  4995.8      .1       0  5213.8     .05       0
Bank Sta=4982.6,4995.8
XS Rating Curve= 0 ,0
Exp/Cntr=0.3,0.1

Type RM Length L Ch R = 1 ,17830   ,410,410,410
BEGIN DESCRIPTION:
Rocky Creek 27.0
END DESCRIPTION:
XS GIS Cut Line= 3
      2516625.02     13862174.99        2516125.       13862325.
      2515025.01     13863524.98
#Sta/Elev= 30
  4474.3  448.95  4529.1   445.5  4595.3  438.03  4765.8  425.68  4860.6  423.18
  4905.1  423.49  4941.5  424.62  4999.7  424.15  5010.2  419.97  5017.7  415.01
  5018.2  414.51    5031  415.01  5031.8  419.94  5074.3  419.63    5152  421.79
  5187.2  424.56  5222.9   424.8  5243.9  426.53    5308  426.39  5335.8  428.41
  5355.3  427.96  5406.7  427.99  5470.8  429.99  5553.4  429.21    6228  433.41
  6334.1  435.46  6340.9  437.15  6362.5  436.16  6546.2  442.25  6624.2  443.35
#Mann= 6 ,-1 , 0
  4474.3     .12       0  4905.1      .1       0  5017.7     .05       0
    5031      .1       0  5355.3     .12       0  5553.4     .05       0
Bank Sta=5017.7,5031
XS Rating Curve= 0 ,0
Exp/Cntr=0.3,0.1