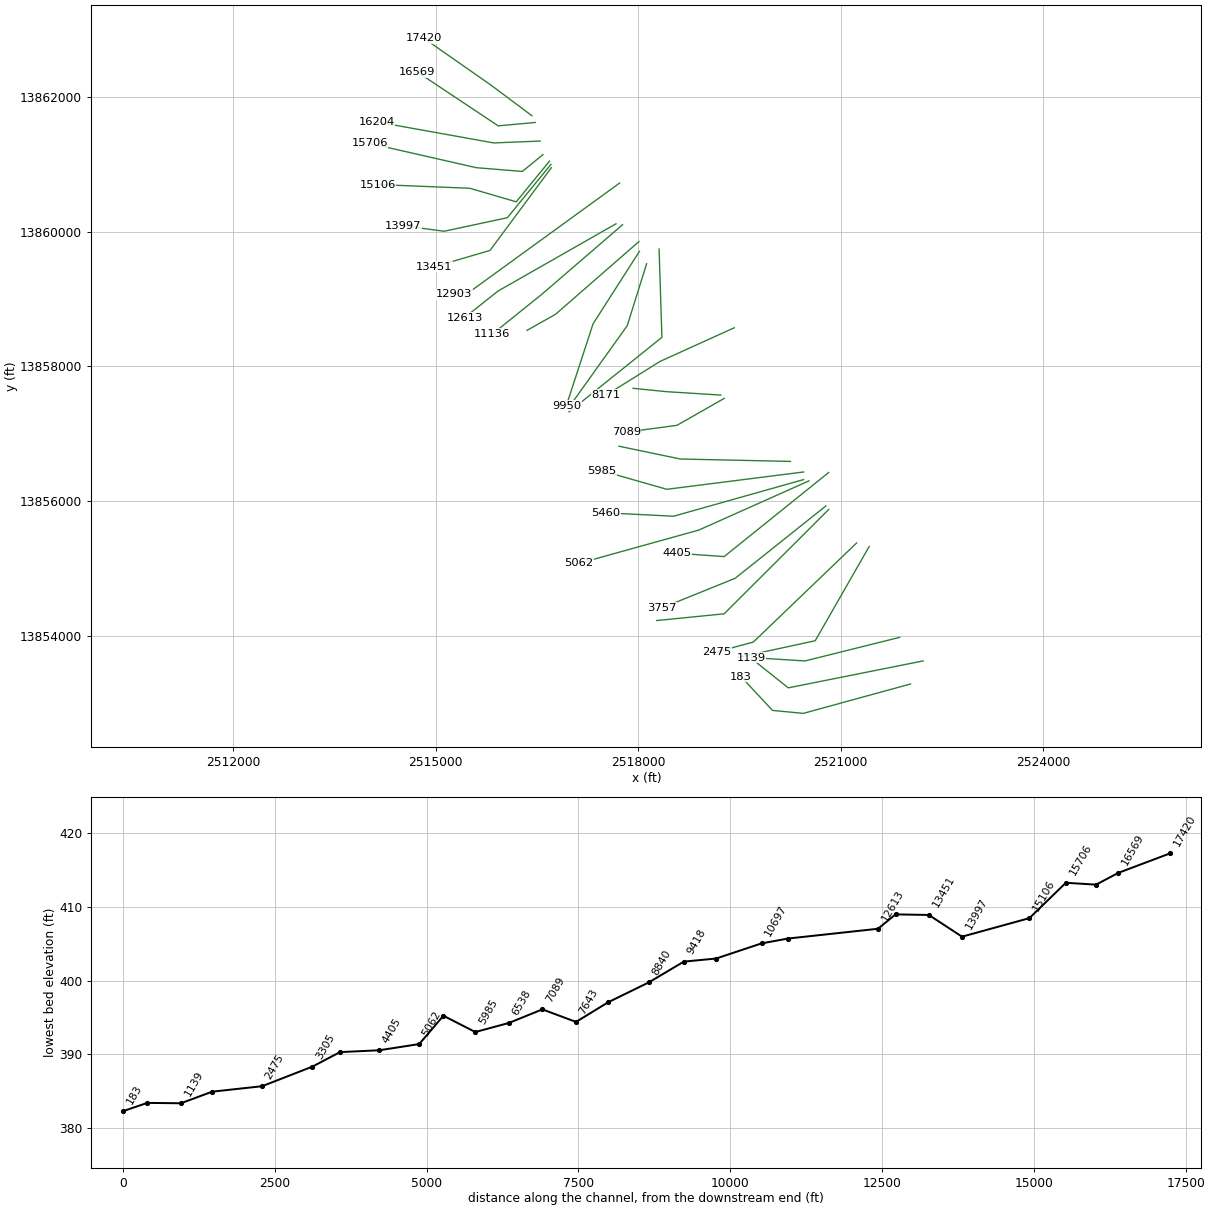
HEC-RAS study Rocky Creek.prj: Rocky Creek Base Level Engineering

--- Rocky Creek.g01 (geometry) --- (continued)

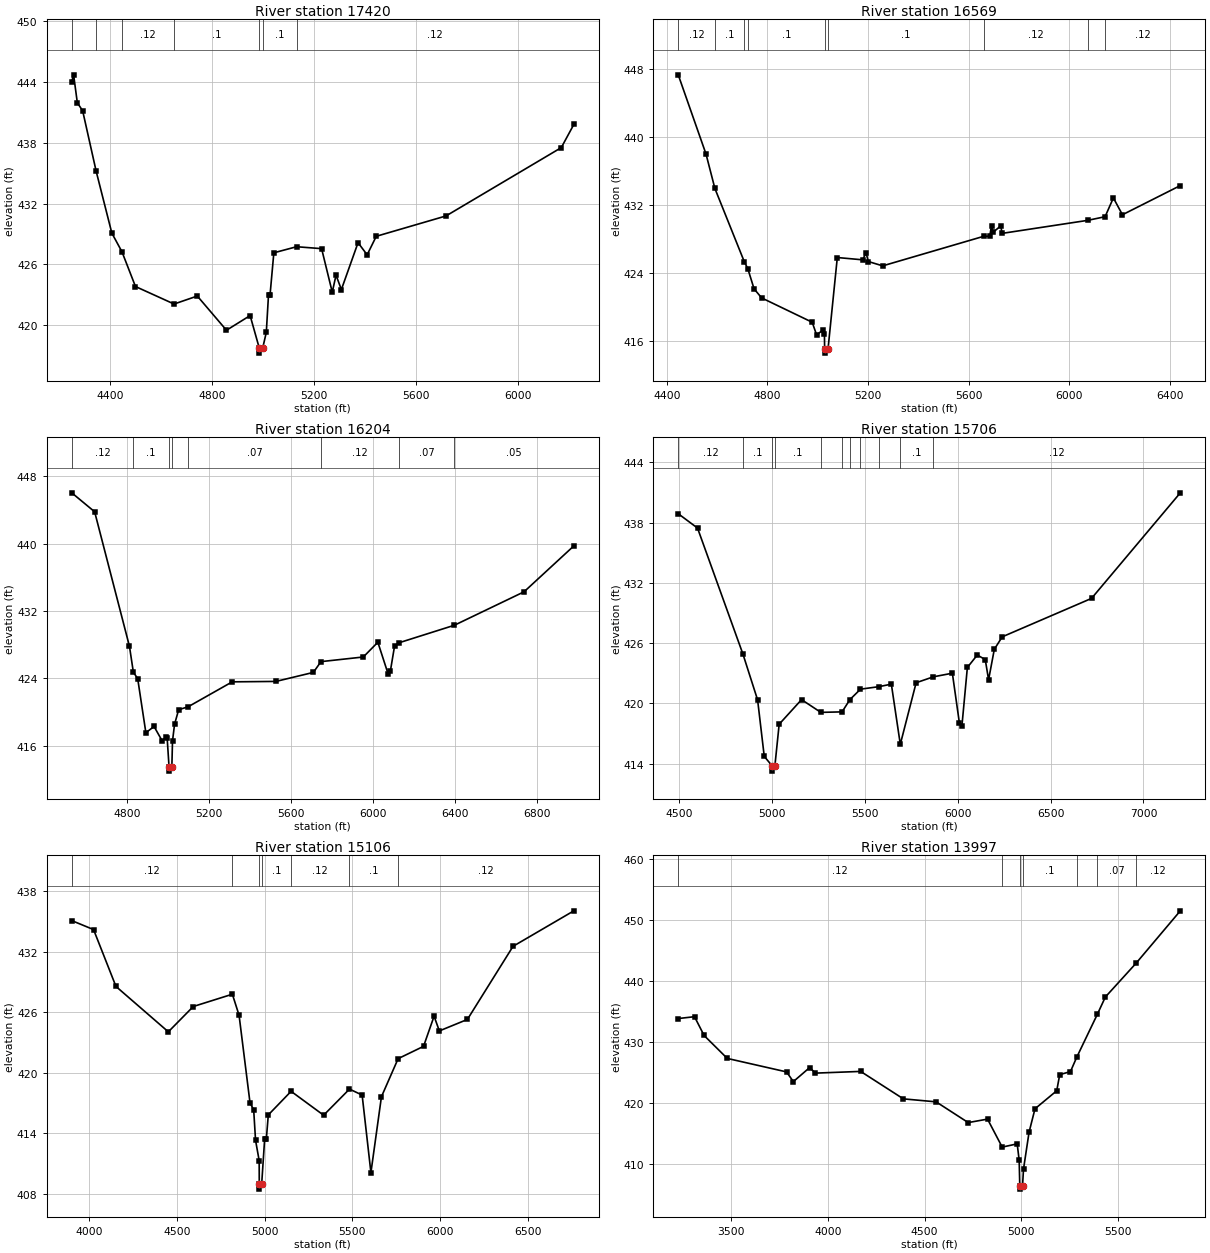
Type RM Length L Ch R = 1 ,17420   ,851,851,851
BEGIN DESCRIPTION:
Rocky Creek 26.0
END DESCRIPTION:
XS GIS Cut Line= 3
      2516424.96     13861725.03        2515825.       13862175.
      2514825.01     13862874.99
#Sta/Elev= 30
    4250  444.05  4257.2  444.72  4271.8  441.96  4292.7  441.17  4345.8  435.19
  4407.2  429.09  4447.2  427.23    4500  423.81  4651.5  422.08  4742.7  422.87
  4857.2  419.49    4950  420.94  4985.9  417.73  4986.4  417.23  4999.4  417.73
  5013.5  419.28  5022.2  422.99  5028.3  423.01  5043.1  427.14  5132.4  427.74
  5230.6  427.55  5272.4  423.25  5287.2  424.93  5308.2  423.51  5373.6  428.14
  5409.3  426.94  5445.1  428.77  5718.8  430.78  6171.3  437.53  6220.6  439.82
#Mann= 7 ,-1 , 0
    4250     .12       0  4345.8      .1       0  4447.2     .12       0
  4651.5      .1       0  4985.9     .05       0  4999.4      .1       0
  5132.4     .12       0
Bank Sta=4985.9,4999.4
XS Rating Curve= 0 ,0
Exp/Cntr=0.3,0.1

Type RM Length L Ch R = 1 ,16569   ,365,365,365
BEGIN DESCRIPTION:
Rocky Creek 25.0
END DESCRIPTION:
XS GIS Cut Line= 3
        2516475.       13861625.        2515925.       13861575.
      2514724.99     13862375.01
#Sta/Elev= 30
  4445.8  447.31  4556.2  437.99  4591.4  433.95  4707.9  425.36  4722.5  424.49
    4747  422.15  4777.2  421.08    4978  418.22  4995.6  416.72  5020.6  417.32
  5026.6  416.84  5027.3  415.09  5027.8  414.59  5040.9  415.09  5077.7  425.83
  5178.3  425.56  5191.9  426.38  5200.9  425.36    5258  424.85  5658.7  428.32
  5683.1  428.33  5690.6  429.59  5696.6  428.79  5726.7  429.55  5732.7  428.67
  6072.4   430.2  6141.5  430.63  6174.4  432.84  6210.4  430.86  6440.3  434.29
#Mann= 9 ,-1 , 0
  4445.8     .12       0  4591.4      .1       0  4707.9     .12       0
  4722.5      .1       0  5027.3     .05       0  5040.9      .1       0
  5658.7     .12       0  6072.4     .07       0  6141.5     .12       0
Bank Sta=5027.3,5040.9
XS Rating Curve= 0 ,0
Exp/Cntr=0.3,0.1

Type RM Length L Ch R = 1 ,16204   ,498,498,498
BEGIN DESCRIPTION:
B20206
END DESCRIPTION:
XS GIS Cut Line= 3
       2516546.6     13861348.78      2515859.08       13861321.
      2514122.96      13861633.5
#Sta/Elev= 30
  4530.1  446.04  4641.8  443.79  4811.9  427.81  4830.9  424.74    4852  423.99
    4892  417.56    4932   418.3  4972.1  416.57  4991.1  417.08  4996.1  416.88
  5005.2   413.5  5005.7     413  5018.9   413.5  5022.1  416.58  5032.1  418.56
  5052.1  420.29  5098.4  420.64  5313.8   423.6  5527.1  423.65    5710  424.72
  5747.2     426  5953.9  426.55    6025   428.3  6075.8  424.49    6086  424.86
  6106.3  427.81  6128.5  428.24  6398.8  430.32    6739  434.29  6982.2  439.74
#Mann= 8 ,-1 , 0
  4530.1     .12       0  4830.9      .1       0  5005.2     .05       0
  5018.9      .1       0  5098.4     .07       0  5747.2     .12       0
  6128.5     .07       0  6398.8     .05       0
Bank Sta=5005.2,5018.9
XS Rating Curve= 0 ,0
Exp/Cntr=0.3,0.1

Type RM Length L Ch R = 1 ,15706   ,600,600,600
BEGIN DESCRIPTION:
B20205
END DESCRIPTION:
XS GIS Cut Line= 4
      2516588.26      13861147.4      2516282.69     13860897.39
      2515602.13     13860952.94      2514019.41     13861313.91
#Sta/Elev= 30
  4497.3  438.88  4601.1  437.45  4845.8  424.88  4924.3  420.34    4960  414.72
  5003.4  413.75  5003.9  413.25  5017.1  413.75  5040.3  417.92  5160.7  420.37
  5264.5   419.1  5378.7  419.15  5420.7  420.37  5477.8  421.41  5576.9  421.66
  5643.8  421.91  5691.9  415.92  5777.1  422.05  5869.7  422.64    5972     423
  6009.7  418.06  6023.3  417.73  6052.7  423.57  6105.9  424.81  6148.9  424.36
  6166.9  422.35  6197.7  425.38  6240.1  426.62  6720.8  430.45  7198.3  440.96
#Mann= 11 ,-1 , 0
  4497.3     .12       0  4845.8      .1       0  5003.4     .05       0
  5017.1      .1       0  5264.5     .12       0  5378.7     .07       0
  5420.7     .12       0  5477.8     .07       0  5576.9     .12       0
  5691.9      .1       0  5869.7     .12       0
Bank Sta=5003.4,5017.1
XS Rating Curve= 0 ,0
Exp/Cntr=0.3,0.1

Type RM Length L Ch R = 1 ,15106   ,1109,1109,1109
BEGIN DESCRIPTION:
B20204
END DESCRIPTION:
XS GIS Cut Line= 4
      2516685.46     13861050.16      2516192.41       13860446.
      2515504.91     13860647.39      2514138.44     13860702.88
#Sta/Elev= 30
  3900.5  435.09  4024.8   434.2  4152.6  428.56  4451.3  424.06  4593.5  426.57
  4816.5  427.79  4854.8   425.7  4917.3     417  4938.1  416.34  4948.7  413.31
  4969.4  411.29    4970  408.96  4970.5  408.46  4983.7  408.96  5000.6  413.41
  5010.3  413.44  5021.5  415.82  5151.5  418.16  5337.1  415.79  5484.5  418.38
  5556.7  417.79  5606.8   410.1  5666.8  417.62    5762   421.4    5907  422.62
  5967.1  425.61  5997.1  424.15  6157.2  425.29  6417.5  432.54  6764.3  436.06
#Mann= 7 ,-1 , 0
  3900.5     .12       0  4816.5      .1       0    4970     .05       0
  4983.7      .1       0  5151.5     .12       0  5484.5      .1       0
    5762     .12       0
Bank Sta=4970,4983.7
XS Rating Curve= 0 ,0
Exp/Cntr=0.3,0.1

Type RM Length L Ch R = 1 ,13997   ,546,546,546
BEGIN DESCRIPTION:
B20203
END DESCRIPTION:
XS GIS Cut Line= 4
      2516706.28     13861001.54      2516060.46     13860209.89
      2515122.96      13860008.5      2514511.87     13860091.83
#Sta/Elev= 30
  3225.9  433.92  3310.1  434.22  3359.7  431.14  3479.6  427.38  3786.2  425.17
  3821.4  423.58  3906.1  425.89  3934.8  424.97  4169.6  425.25  4390.5  420.75
    4560  420.26    4726  416.86  4825.9  417.43  4901.8  412.84  4979.3  413.37
  4989.6  410.69  4992.8  406.45  4993.3  405.95  5006.9  406.45    5012  409.23
  5040.7  415.27  5071.4  419.12  5183.9  422.08  5199.3  424.72  5254.9  425.22
  5286.9  427.54  5394.7  434.66  5435.5  437.45  5594.4  442.99  5823.2  451.58
#Mann= 7 ,-1 , 0
  3225.9     .12       0  4901.8      .1       0  4992.8     .05       0
  5006.9      .1       0  5286.9    .035       0  5394.7     .07       0
  5594.4     .12       0
Bank Sta=4992.8,5006.9
XS Rating Curve= 0 ,0
Exp/Cntr=0.3,0.1

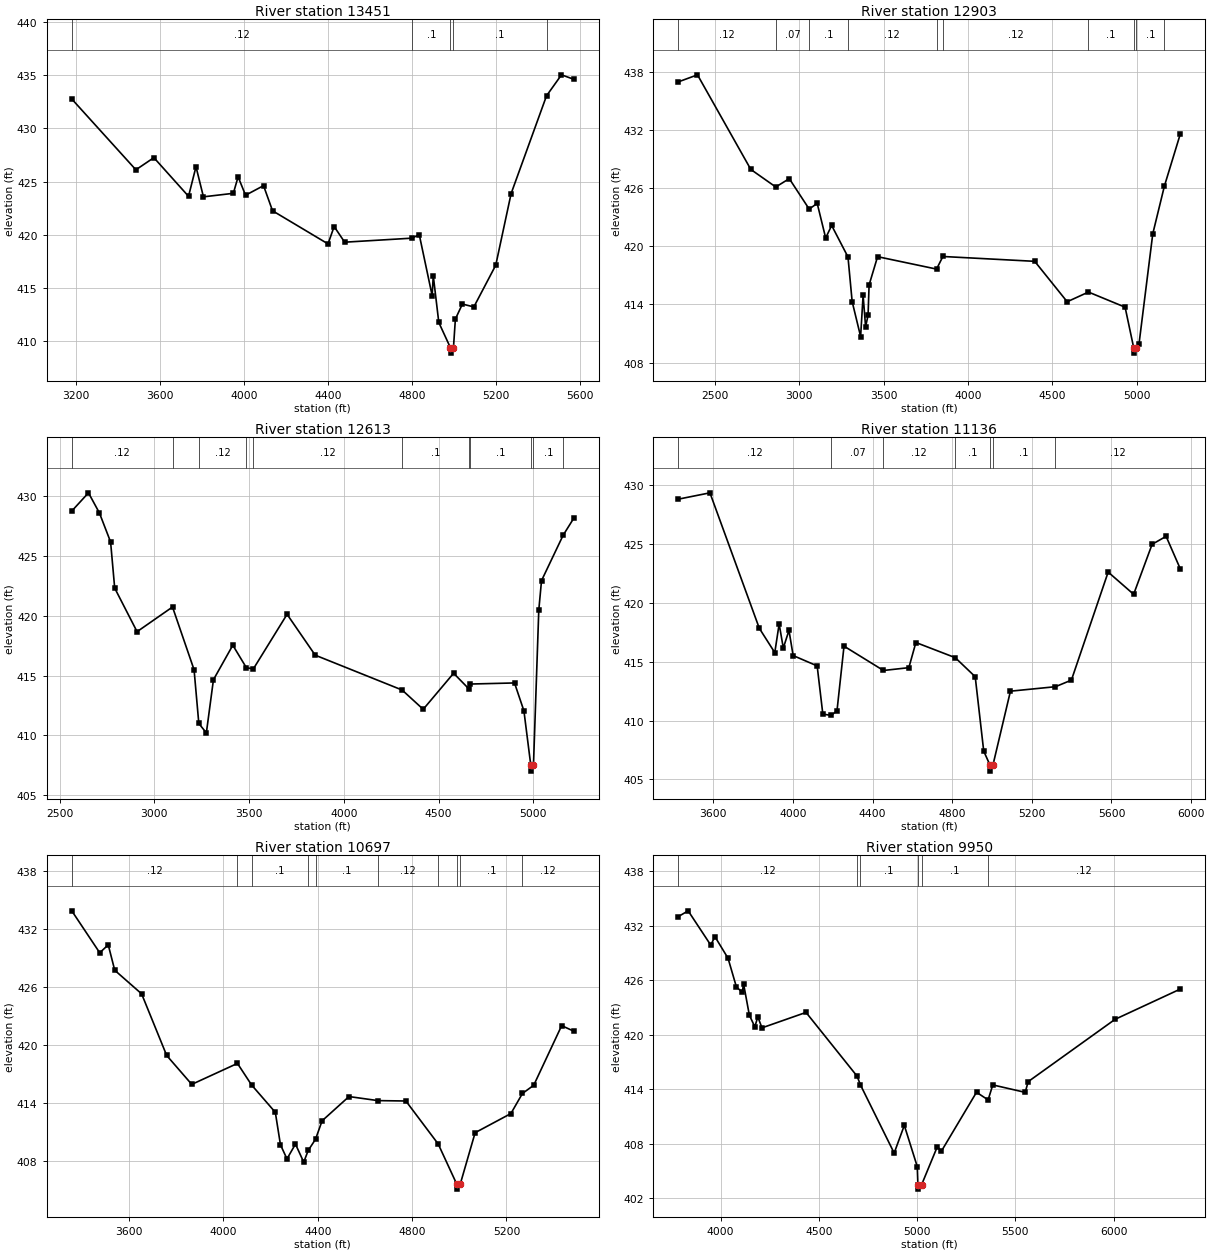
Type RM Length L Ch R = 1 ,13451   ,548,548,548
BEGIN DESCRIPTION:
B20202
END DESCRIPTION:
XS GIS Cut Line= 3
      2516713.23     13860952.93      2515803.52     13859723.77
      2514978.54     13859481.13
#Sta/Elev= 30
  3180.9  432.76    3486  426.11  3571.6  427.25  3736.5  423.62    3772   426.4
  3807.4  423.57  3949.7   423.9  3972.4  425.45  4007.8  423.72  4093.4  424.62
  4136.3  422.26  4400.2  419.15  4429.4  420.78  4479.5  419.31  4800.5  419.69
  4834.3  420.03  4895.8  414.29    4901  416.17  4927.4  411.77  4982.9  409.39
  4983.4  408.89  4997.1  409.39  5006.3  412.09  5039.6   413.5  5094.2  413.23
  5198.4  417.15  5271.4  423.87    5440  433.06  5511.2  435.03    5570  434.61
#Mann= 5 ,-1 , 0
  3180.9     .12       0  4800.5      .1       0  4982.9     .05       0
  4997.1      .1       0    5440     .07       0
Bank Sta=4982.9,4997.1
XS Rating Curve= 0 ,0
Exp/Cntr=0.3,0.1

Type RM Length L Ch R = 1 ,12903   ,290,290,290
BEGIN DESCRIPTION:
Rocky Creek 20.0
END DESCRIPTION:
XS GIS Cut Line= 3
      2517725.02     13860725.02        2515525.       13859125.
      2515274.97     13859074.99
#Sta/Elev= 30
  2283.6  436.95  2397.6  437.68  2713.7  427.92  2861.5  426.11  2941.7  426.97
  3059.6  423.83  3107.1  424.42  3157.3  420.85  3192.8  422.14  3289.5  418.89
  3314.2  414.29  3364.4  410.68  3379.1  414.94  3393.8   411.7  3408.5  412.86
  3414.6     416  3464.9  418.92  3814.3  417.64    3852  418.94  4396.1  418.44
  4588.5  414.27  4714.6  415.27  4931.7  413.71  4983.3  409.47  4983.8  408.97
  4997.5  409.47  5014.1  409.91  5095.7  421.28  5164.7  426.21  5258.9  431.58
#Mann= 10 ,-1 , 0
  2283.6     .12       0  2861.5     .07       0  3059.6      .1       0
  3289.5     .12       0  3814.3      .1       0    3852     .12       0
  4714.6      .1       0  4983.3     .05       0  4997.5      .1       0
  5164.7     .12       0
Bank Sta=4983.3,4997.5
XS Rating Curve= 0 ,0
Exp/Cntr=0.3,0.1

Type RM Length L Ch R = 1 ,12613   ,1477,1477,1477
BEGIN DESCRIPTION:
Rocky Creek 19.0
END DESCRIPTION:
XS GIS Cut Line= 3
      2517671.58     13860119.61      2515921.58     13859119.61
      2515425.03     13858725.02
#Sta/Elev= 30
  2563.8  428.73    2652  430.25  2709.7  428.57  2768.7  426.15  2790.3   422.3
  2908.4  418.66  3095.5  420.72  3209.3  415.48  3234.3     411  3274.1  410.21
  3311.5  414.65  3413.7  417.53  3485.8  415.64  3522.8  415.57  3700.1  420.11
  3848.5   416.7  4307.3  413.79  4418.6  412.18    4579  415.19  4658.8   413.9
    4668  414.29  4900.5  414.38  4950.1  412.05  4986.3  407.52  4986.8  407.02
  5000.5  407.52  5028.6  420.47    5043  422.92  5157.1  426.71  5213.6  428.14
#Mann= 11 ,-1 , 0
  2563.8     .12       0  3095.5     .07       0  3234.3     .12       0
  3485.8     .07       0  3522.8     .12       0  4307.3      .1       0
  4658.8     .12       0    4668      .1       0  4986.3     .05       0
  5000.5      .1       0  5157.1     .12       0
Bank Sta=4986.3,5000.5
XS Rating Curve= 0 ,0
Exp/Cntr=0.3,0.1

Type RM Length L Ch R = 1 ,11136   ,439,439,439
BEGIN DESCRIPTION:
Rocky Creek 18.0
END DESCRIPTION:
XS GIS Cut Line= 3
      2517768.78      13860105.7        2516575.       13859075.
      2515839.12     13858481.43
#Sta/Elev= 30
  3423.4  428.83  3582.7  429.37  3830.7  417.85  3908.5  415.78  3930.4  418.22
  3951.3  416.17  3979.8  417.67  4000.7  415.53  4121.4  414.65  4149.9  410.55
  4192.1  410.44  4221.1  410.84  4256.3  416.33  4454.5  414.26  4582.1   414.5
  4617.4  416.64  4815.2  415.35  4915.5  413.73  4958.3   407.4  4990.1   406.2
  4990.6   405.7  5004.4   406.2  5092.5   412.5  5318.6  412.88  5398.8  413.44
  5583.5  422.63  5711.5  420.74  5804.2  424.99  5874.6  425.67    5946   422.9
#Mann= 7 ,-1 , 0
  3423.4     .12       0  4192.1     .07       0  4454.5     .12       0
  4815.2      .1       0  4990.1     .05       0  5004.4      .1       0
  5318.6     .12       0
Bank Sta=4990.1,5004.4
XS Rating Curve= 0 ,0
Exp/Cntr=0.3,0.1

Type RM Length L Ch R = 1 ,10697   ,747,747,747
BEGIN DESCRIPTION:
Rocky Creek 17.0
END DESCRIPTION:
XS GIS Cut Line= 3
      2518011.82     13859855.69        2516775.       13858775.
      2516352.16     13858536.29
#Sta/Elev= 30
  3357.7  433.84  3476.2   429.5  3512.3  430.32  3539.8  427.69  3653.7  425.25
    3760  418.87  3866.3  415.88  4059.9  418.05  4119.8  415.82  4220.4  412.99
  4242.2  409.63  4269.8  408.17  4305.8   409.7  4340.9  407.83  4359.7  409.04
  4390.8   410.2  4418.7  412.11  4532.7  414.62  4655.4   414.2  4773.8  414.16
  4910.8  409.71  4989.7  405.54  4990.2  405.04    5004  405.54  5067.3  410.88
  5218.9  412.86  5267.8  414.94  5315.7  415.79  5434.1  421.96  5485.7  421.38
#Mann= 10 ,-1 , 0
  3357.7     .12       0  4059.9     .07       0  4119.8      .1       0
  4359.7     .07       0  4390.8      .1       0  4655.4     .12       0
  4910.8      .1       0  4989.7     .05       0    5004      .1       0
  5267.8     .12       0
Bank Sta=4989.7,5004
XS Rating Curve= 0 ,0
Exp/Cntr=0.3,0.1

Type RM Length L Ch R = 1 ,9950    ,532,532,532
BEGIN DESCRIPTION:
Rocky Creek 15.0
END DESCRIPTION:
XS GIS Cut Line= 3
      2518018.78     13859709.86       2517331.3      13858633.5
      2516935.74     13857419.07
#Sta/Elev= 30
  3784.7  432.98  3835.1  433.62  3950.1  429.85  3971.3  430.78  4038.1   428.4
  4080.4  425.26  4110.8  424.64  4116.8  425.62  4146.4  422.15  4174.3  420.85
  4189.6  421.95  4210.7  420.74  4434.9  422.44  4694.7  415.42  4711.5  414.47
  4883.3  406.96  4934.9  410.01  5000.8  405.47    5004  403.49  5004.5  402.99
  5023.2  403.49    5103  407.67  5123.4  407.16  5302.2  413.65  5361.2  412.81
    5385  414.46  5549.9  413.64  5565.1  414.82  6007.3  421.68  6339.1  425.01
#Mann= 6 ,-1 , 0
  3784.7     .12       0  4694.7     .07       0  4711.5      .1       0
    5004     .05       0  5023.2      .1       0  5361.2     .12       0
Bank Sta=5004,5023.2
XS Rating Curve= 0 ,0
Exp/Cntr=0.3,0.1

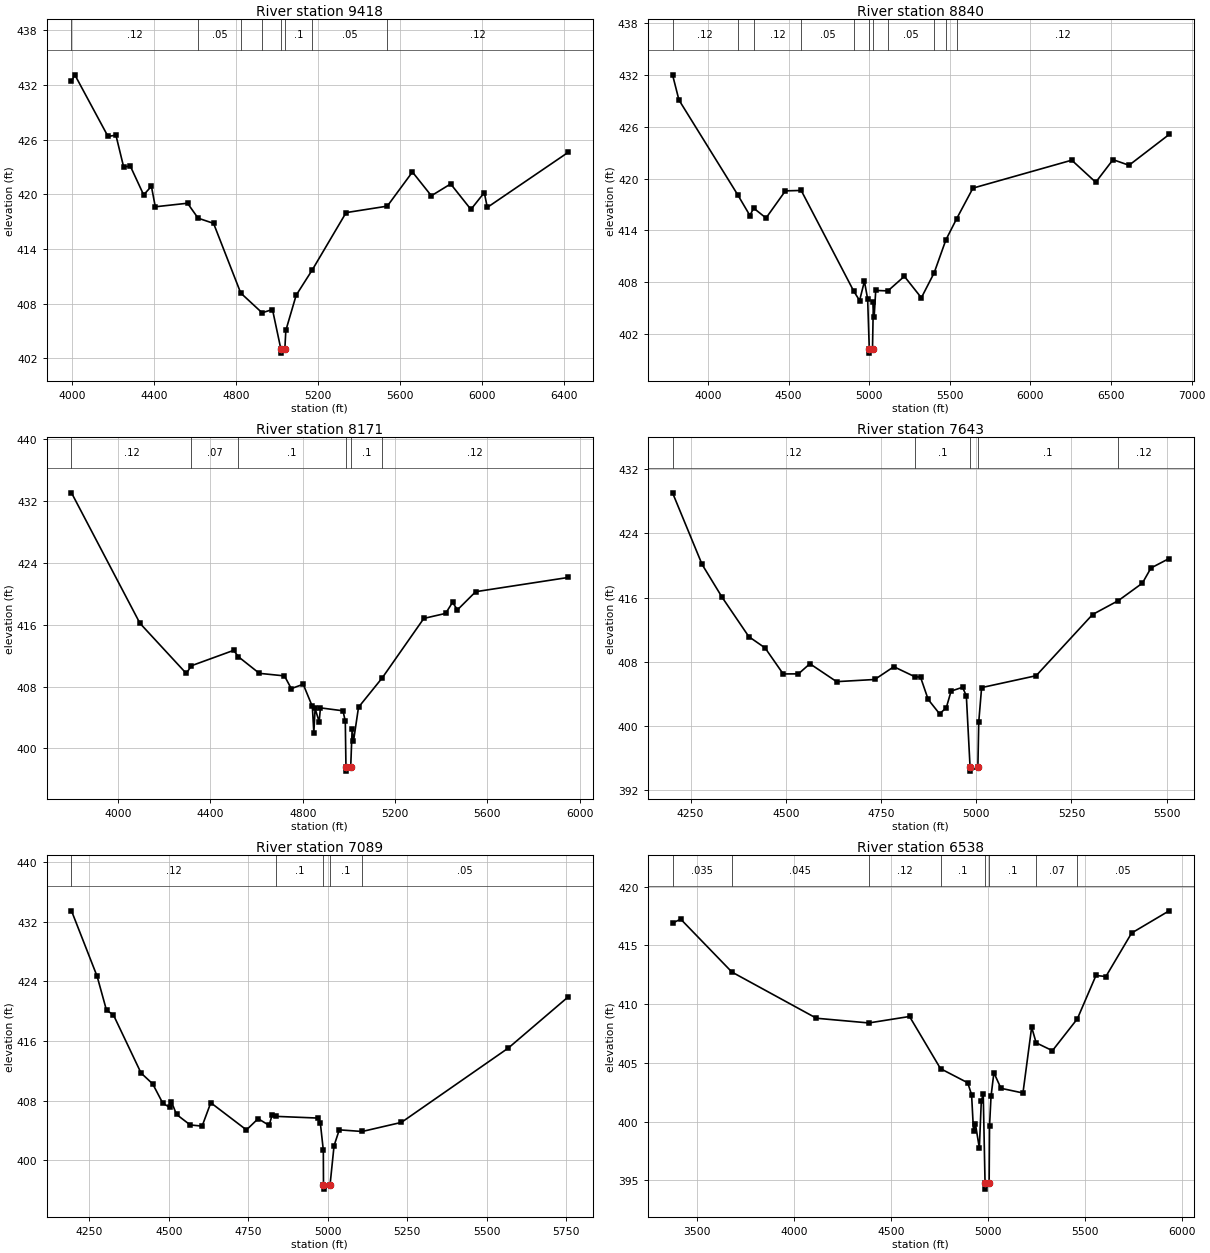
Type RM Length L Ch R = 1 ,9418    ,578,578,578
BEGIN DESCRIPTION:
Rocky Creek 14.0
END DESCRIPTION:
XS GIS Cut Line= 3
      2518124.99     13859524.98      2517838.24     13858605.72
      2516991.65     13857419.11
#Sta/Elev= 30
  3997.3  432.43  4013.5  433.13  4175.4  426.36  4213.8  426.51  4251.5  423.01
    4284  423.11    4349  419.95  4386.8  420.89  4405.8  418.64  4562.9  419.03
  4614.4  417.39  4689.8  416.82  4822.3  409.17  4926.3     407    4977  407.36
  5017.4  403.07  5017.9  402.57  5037.4  403.07  5042.1  405.06  5092.5  408.93
  5171.6  411.73  5335.9     418  5536.6  418.71  5659.2  422.46  5751.4  419.85
  5845.6  421.15  5944.3  418.35  6009.5   420.2  6024.2  418.57  6417.9  424.61
#Mann= 8 ,-1 , 0
  3997.3     .12       0  4614.4     .05       0  4822.3     .12       0
  4926.3      .1       0  5017.4     .05       0  5037.4      .1       0
  5171.6     .05       0  5536.6     .12       0
Bank Sta=5017.4,5037.4
XS Rating Curve= 0 ,0
Exp/Cntr=0.3,0.1

Type RM Length L Ch R = 1 ,8840    ,669,669,669
BEGIN DESCRIPTION:
Rocky Creek 13.0
END DESCRIPTION:
XS GIS Cut Line= 3
      2518310.46     13859744.64      2518352.13     13858432.11
      2516974.97     13857324.97
#Sta/Elev= 30
    3780  432.03  3819.7  429.11  4184.7   418.1  4259.9  415.71    4283  416.57
  4359.9  415.42    4480  418.57    4578  418.62  4903.9  406.94  4940.2  405.85
  4970.2  408.09  4990.2  406.02  5000.3  400.25  5000.8  399.75  5020.3  400.25
  5025.6  405.67  5030.7  403.99  5040.3  407.02  5115.9  406.97  5217.8  408.66
  5323.4  406.17  5402.9  409.07  5475.6  412.89  5542.5  415.35  5643.4  418.89
  6256.2  422.13    6405  419.57  6512.2  422.19  6611.4  421.54  6860.2  425.11
#Mann= 11 ,-1 , 0
    3780     .12       0  4184.7     .07       0    4283     .12       0
    4578     .05       0  4903.9      .1       0  5000.3     .05       0
  5020.3      .1       0  5115.9     .05       0  5402.9     .12       0
  5475.6     .05       0  5542.5     .12       0
Bank Sta=5000.3,5020.3
XS Rating Curve= 0 ,0
Exp/Cntr=0.3,0.1

Type RM Length L Ch R = 1 ,8171    ,528,528,528
BEGIN DESCRIPTION:
Rocky Creek 12.0
END DESCRIPTION:
XS GIS Cut Line= 3
      2519425.02     13858575.01        2518325.       13858075.
      2517525.02     13857575.01
#Sta/Elev= 30
  3797.7  433.09  4094.3   416.2  4295.3   409.7  4316.9   410.7  4500.7   412.7
    4520  411.89  4611.7  409.72  4720.4  409.39  4750.1  407.74  4801.7  408.31
  4841.3  405.43  4847.8  402.05  4853.3  405.17  4870.9  403.44  4876.4  405.25
  4974.2  404.87  4984.1   403.5    4987  397.56  4987.5  397.06  5007.5  397.56
  5013.7  402.48  5019.6  400.93  5041.4  405.33  5144.6  409.15  5324.4  416.83
  5418.8  417.48  5448.8  418.91  5470.1  417.94  5549.1  420.29  5949.4  422.13
#Mann= 6 ,-1 , 0
  3797.7     .12       0  4316.9     .07       0    4520      .1       0
    4987     .05       0  5007.5      .1       0  5144.6     .12       0
Bank Sta=4987,5007.5
XS Rating Curve= 0 ,0
Exp/Cntr=0.3,0.1

Type RM Length L Ch R = 1 ,7643    ,554,554,554
BEGIN DESCRIPTION:
Rocky Creek 11.0
END DESCRIPTION:
XS GIS Cut Line= 3
      2519224.98       13857575.        2518425.       13857625.
      2517925.03       13857675.
#Sta/Elev= 30
  4202.6  429.05  4280.2  420.13  4332.8  416.04    4403  411.14  4445.6  409.74
  4493.1   406.5  4533.2  406.51  4563.3  407.77  4633.4  405.54  4733.6  405.81
  4783.7   407.4    4839  406.15  4853.8   406.1  4873.9  403.32  4903.9  401.53
  4921.5   402.3    4934  404.36  4964.1  404.84  4974.1  403.77  4983.9   394.9
  4984.4   394.4  5004.4   394.9  5006.7  400.53  5014.2   404.8  5157.4  406.28
  5305.6   413.9  5373.3  415.63  5436.3   417.8  5458.9  419.69  5506.6  420.87
#Mann= 5 ,-1 , 0
  4202.6     .12       0    4839      .1       0  4983.9     .05       0
  5004.4      .1       0  5373.3     .12       0
Bank Sta=4983.9,5004.4
XS Rating Curve= 0 ,0
Exp/Cntr=0.3,0.1

Type RM Length L Ch R = 1 ,7089    ,551,551,551
BEGIN DESCRIPTION:
Rocky Creek 10.0
END DESCRIPTION:
XS GIS Cut Line= 3
      2519275.04     13857525.02        2518575.       13857125.
      2517825.01       13857025.
#Sta/Elev= 30
  4193.7  433.47  4274.4  424.67  4303.9  420.11  4325.5  419.51  4412.6  411.69
  4449.3  410.23    4481  407.64  4502.6  407.08  4508.3  407.83  4524.2  406.13
  4567.3  404.72  4604.8  404.56  4632.1   407.7  4744.4  404.05  4781.1  405.56
  4815.7  404.66    4825  406.04  4837.5  405.87  4970.5  405.64  4976.9  404.98
  4986.3  401.32  4986.8   396.6  4987.3   396.1  5007.3   396.6  5020.1  401.93
  5036.5  404.06  5108.6  403.84    5232  405.06  5568.7  415.05  5756.6   421.9
#Mann= 5 ,-1 , 0
  4193.7     .12       0  4837.5      .1       0  4986.8     .05       0
  5007.3      .1       0  5108.6     .05       0
Bank Sta=4986.8,5007.3
XS Rating Curve= 0 ,0
Exp/Cntr=0.3,0.1

Type RM Length L Ch R = 1 ,6538    ,553,553,553
BEGIN DESCRIPTION:
Rocky Creek 9.0
END DESCRIPTION:
XS GIS Cut Line= 3
      2520257.18     13856589.29        2518625.       13856625.
       2517715.7     13856814.97
#Sta/Elev= 30
    3372   416.9  3414.2  417.23  3678.2  412.73  4114.4   408.8  4384.4   408.4
  4594.5  408.95  4754.3  404.51  4894.5  403.31  4914.5   402.3  4924.6  399.17
  4934.6  399.78  4954.6  397.75  4964.6  401.74  4974.6  402.37    4984  394.76
  4984.5  394.26  5005.1  394.76  5007.1  399.63  5014.8  402.15  5029.6  404.17
  5065.9  402.84  5179.5  402.44  5224.4  408.04  5247.6  406.71  5331.5  406.04
  5460.1  408.75  5556.2  412.44  5607.3  412.35  5740.1  416.05  5933.5  417.94
#Mann= 8 ,-1 , 0
    3372    .035       0  3678.2    .045       0  4384.4     .12       0
  4754.3      .1       0    4984     .05       0  5005.1      .1       0
  5247.6     .07       0  5460.1     .05       0
Bank Sta=4984,5005.1
XS Rating Curve= 0 ,0
Exp/Cntr=0.3,0.1

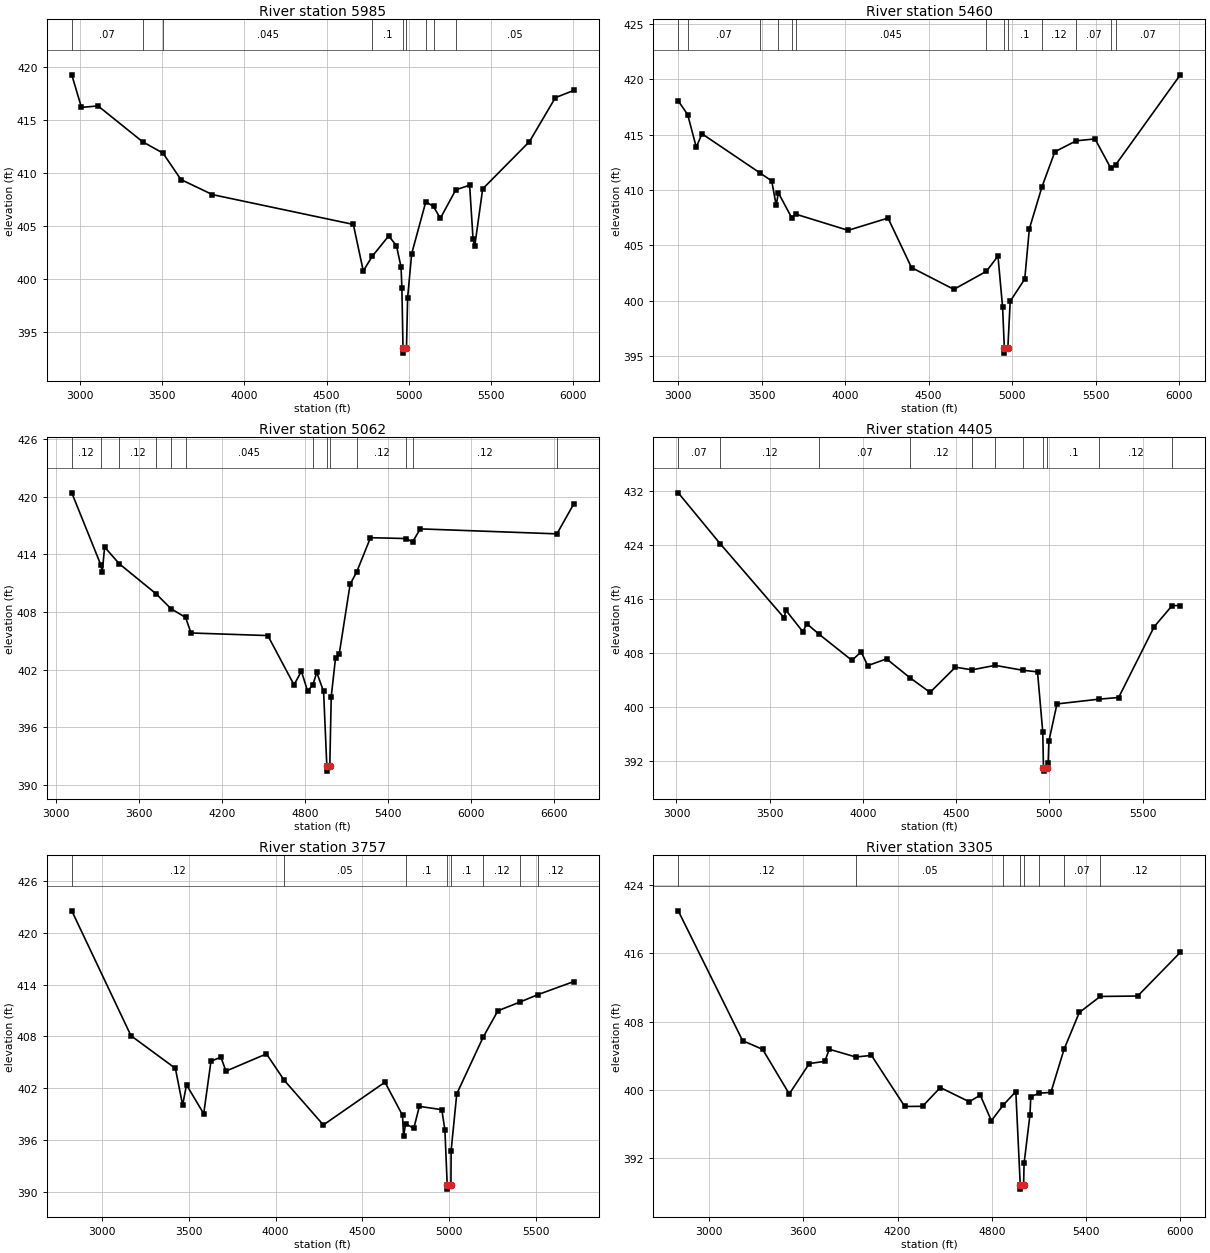
Type RM Length L Ch R = 1 ,5985    ,525,525,525
BEGIN DESCRIPTION:
Rocky Creek 8.0
END DESCRIPTION:
XS GIS Cut Line= 3
      2520453.37     13856432.29        2518425.       13856175.
       2517455.7      13856451.9
#Sta/Elev= 30
  2951.2  419.26    3010  416.19  3110.8  416.33  3381.3  412.96  3505.8  411.88
  3614.8  409.39  3806.4  407.97  4663.2  405.16  4723.7  400.77  4777.2  402.14
  4878.3  404.08  4925.3  403.15  4953.3  401.15  4958.3  399.21  4965.1  393.53
  4965.6  393.03  4986.3  393.53  4993.3  398.26  5017.9   402.4  5103.9   407.3
  5150.7  406.85  5192.1  405.73  5286.1  408.42  5370.2  408.86    5391  403.79
  5401.4  403.12  5449.6  408.51  5734.2  412.97  5891.6  417.11  6003.9  417.79
#Mann= 9 ,-1 , 0
  2951.2     .07       0  3381.3    .035       0  3505.8    .045       0
  4777.2      .1       0  4965.1     .05       0  4986.3      .1       0
  5103.9     .05       0  5150.7     .12       0  5286.1     .05       0
Bank Sta=4965.1,4986.3
XS Rating Curve= 0 ,0
Exp/Cntr=0.3,0.1

Type RM Length L Ch R = 1 ,5460    ,398,398,398
BEGIN DESCRIPTION:
Rocky Creek 7.0
END DESCRIPTION:
XS GIS Cut Line= 3
       2520453.4     13856319.45        2518525.       13855775.
      2517525.04       13855825.
#Sta/Elev= 30
  3001.4  418.06  3057.7  416.83  3109.3  413.87  3143.3  415.09    3490  411.55
  3560.9  410.82  3587.5  408.62  3600.8  409.74  3679.7  407.51  3705.5  407.81
  4018.1  406.35    4257  407.46  4397.6  402.98  4651.1  401.01  4845.6  402.64
    4915  404.02  4942.8  399.39    4953  395.74  4953.5  395.24  4974.3  395.74
  4988.2  399.93  5075.3  401.94  5102.8  406.48  5178.7   410.3  5255.5  413.46
  5383.5  414.45  5495.8  414.62  5590.8  411.96  5619.1  412.27  6006.4  420.42
#Mann= 13 ,-1 , 0
  3001.4     .12       0  3057.7     .07       0    3490    .035       0
  3600.8    .045       0  3679.7    .035       0  3705.5    .045       0
  4845.6      .1       0    4953     .05       0  4974.3      .1       0
  5178.7     .12       0  5383.5     .07       0  5590.8     .12       0
  5619.1     .07       0
Bank Sta=4953,4974.3
XS Rating Curve= 0 ,0
Exp/Cntr=0.3,0.1

Type RM Length L Ch R = 1 ,5062    ,657,657,657
BEGIN DESCRIPTION:
Rocky Creek 6.0
END DESCRIPTION:
XS GIS Cut Line= 3
       2520531.9     13856299.83      2518898.09     13855568.79
      2517124.97     13855074.99
#Sta/Elev= 30
  3115.1  420.43  3324.5  412.94  3335.7  412.21  3352.7  414.77  3458.6  413.03
  3725.2  409.89  3831.7  408.35  3938.3  407.43  3977.2  405.81  4532.6  405.54
  4722.1   400.4  4775.5  401.81  4820.7  399.74  4859.4  400.43  4886.5   401.7
    4936  399.71  4959.5   391.9    4960   391.4  4980.8   391.9  4991.3  399.18
  5022.4  403.21    5049  403.61  5127.8  410.89  5175.9  412.19    5275  415.75
  5534.2  415.66  5579.3   415.3  5634.8  416.67  6623.2  416.15  6745.6  419.29
#Mann= 13 ,-1 , 0
  3115.1     .12       0  3324.5     .07       0  3458.6     .12       0
  3725.2     .07       0  3831.7    .035       0  3938.3    .045       0
  4859.4      .1       0  4959.5     .05       0  4980.8      .1       0
  5175.9     .12       0  5534.2     .07       0  5579.3     .12       0
  6623.2     .07       0
Bank Sta=4959.5,4980.8
XS Rating Curve= 0 ,0
Exp/Cntr=0.3,0.1

Type RM Length L Ch R = 1 ,4405    ,648,648,648
BEGIN DESCRIPTION:
Rocky Creek 5.0
END DESCRIPTION:
XS GIS Cut Line= 3
      2520825.01     13856425.01        2519275.       13855175.
      2518575.03       13855225.
#Sta/Elev= 30
  3009.4  431.69  3234.6  424.16    3578  413.19    3586  414.37  3677.4  411.17
  3699.5  412.33    3765  410.79  3941.1  406.93  3990.6  408.18  4025.8  406.15
  4126.6  407.15  4252.2  404.36  4360.1   402.2    4496  405.92  4585.4  405.53
  4709.1  406.19  4856.6  405.47  4936.4  405.23  4964.7  396.31  4968.4  391.06
  4968.9  390.56  4989.7  391.06  4993.5  391.72  4997.4  394.97  5040.8  400.49
  5267.6   401.2  5371.6  401.44  5562.1  411.89  5658.3  415.02  5702.4  415.03
#Mann= 11 ,-1 , 0
  3009.4     .07       0  3234.6     .12       0    3765     .07       0
  4252.2     .12       0  4585.4     .05       0  4709.1    .045       0
  4856.6      .1       0  4968.4     .05       0  4989.7      .1       0
  5267.6     .12       0  5658.3     .07       0
Bank Sta=4968.4,4989.7
XS Rating Curve= 0 ,0
Exp/Cntr=0.3,0.1

Type RM Length L Ch R = 1 ,3757    ,452,452,452
BEGIN DESCRIPTION:
B20201
END DESCRIPTION:
XS GIS Cut Line= 3
       2520782.1     13855926.94      2519437.78     13854852.47
      2518349.28     13854411.18
#Sta/Elev= 30
    2824  422.53  3165.5  408.07  3421.6  404.29  3463.3  400.03  3485.7  402.38
  3584.9  399.04  3626.8  405.12  3684.2  405.59    3713  403.97  3946.8  405.97
  4048.9  402.92  4274.9  397.74  4630.1  402.69  4731.4  398.86  4737.3  396.45
  4749.8   397.9  4796.3  397.33  4828.5  399.89    4958  399.51  4975.8  397.18
  4989.2  390.81  4989.7  390.31  5010.6  390.81  5011.9  394.78  5044.3  401.34
  5197.1  407.93  5281.7  410.96  5407.7  411.96  5512.5  412.83  5719.5  414.34
#Mann= 8 ,-1 , 0
    2824     .12       0  4048.9     .05       0  4749.8      .1       0
  4989.2     .05       0  5010.6      .1       0  5197.1     .12       0
  5407.7     .07       0  5512.5     .12       0
Bank Sta=4989.2,5010.6
XS Rating Curve= 0 ,0
Exp/Cntr=0.3,0.1

Type RM Length L Ch R = 1 ,3305    ,830,830,830
BEGIN DESCRIPTION:
Rocky Creek 4.0
END DESCRIPTION:
XS GIS Cut Line= 3
      2520824.99     13855874.99        2519275.       13854325.
      2518275.01       13854225.
#Sta/Elev= 30
  2803.8  420.98  3213.9  405.75  3341.2  404.74  3510.9  399.51  3638.2  403.07
  3737.2  403.33  3765.5  404.75  3934.8  403.84  4034.2  404.03  4246.3  398.04
  4359.4  398.06  4472.6  400.26  4656.4   398.6  4727.1  399.36  4797.8  396.37
  4873.4  398.21  4953.4  399.78  4981.6  388.85  4982.1  388.35    5003  388.85
  5005.9  391.36  5043.6  397.08  5048.6  399.19  5103.5   399.6  5176.7  399.69
  5260.8  404.76  5357.6  409.06  5490.9  410.94  5729.5  410.99  6000.8  416.11
#Mann= 8 ,-1 , 0
  2803.8     .12       0  3934.8     .05       0  4873.4      .1       0
  4981.6     .05       0    5003      .1       0  5103.5     .12       0
  5260.8     .07       0  5490.9     .12       0
Bank Sta=4981.6,5003
XS Rating Curve= 0 ,0
Exp/Cntr=0.3,0.1

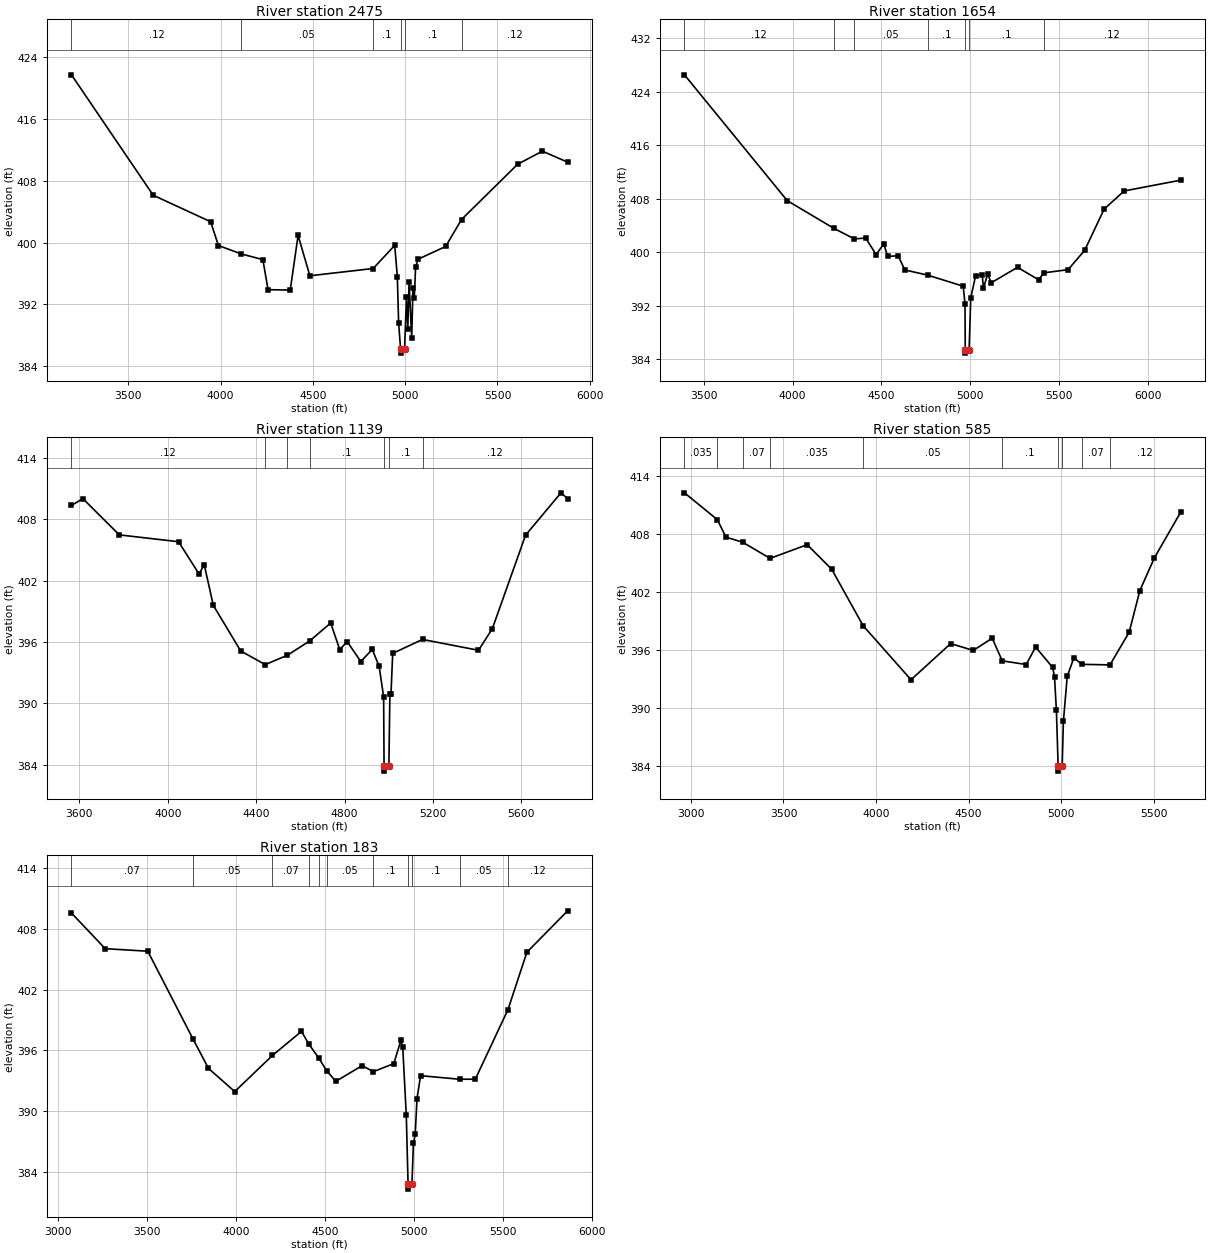
Type RM Length L Ch R = 1 ,2475    ,821,821,821
BEGIN DESCRIPTION:
B20200
END DESCRIPTION:
XS GIS Cut Line= 3
       2521238.4     13855377.46      2519707.63     13853905.56
      2519162.99     13853758.36
#Sta/Elev= 30
  3192.5   421.7  3635.2  406.12  3946.4  402.69  3988.6  399.61  4113.1  398.52
  4229.2  397.79  4257.5   393.9  4377.6  393.85  4420.1  400.92  4483.9   395.7
  4826.8  396.64  4943.6  399.63  4957.8  395.55  4964.7   389.6  4975.4  386.19
  4975.9  385.69  4996.8  386.19  5007.2  392.91  5014.4  388.84  5021.3   394.9
  5035.5  387.69  5042.4  394.07  5049.6  392.79  5056.6  396.84  5070.7  397.85
  5219.4  399.49  5305.4  402.98  5609.9  410.14  5743.6  411.82  5880.3   410.4
#Mann= 6 ,-1 , 0
  3192.5     .12       0  4113.1     .05       0  4826.8      .1       0
  4975.4     .05       0  4996.8      .1       0  5305.4     .12       0
Bank Sta=4975.4,4996.8
XS Rating Curve= 0 ,0
Exp/Cntr=0.3,0.1

Type RM Length L Ch R = 1 ,1654    ,515,515,515
BEGIN DESCRIPTION:
Rocky Creek 3.0
END DESCRIPTION:
XS GIS Cut Line= 3
        2521425.       13855325.        2520625.       13853925.
      2519475.02       13853675.
#Sta/Elev= 30
  3392.4  426.53  3970.4  407.73  4233.2  403.58  4348.4  402.01    4411  402.15
    4470  399.68  4513.2  401.26  4534.8  399.39  4593.8  399.51  4631.3  397.38
    4760   396.6  4959.5  394.95  4969.6  392.34    4971  385.45  4971.5  384.95
  4992.7  385.45    5002  393.22  5029.4  396.52  5066.3  396.66  5073.4  394.68
    5097  396.74  5117.4  395.47  5264.8  397.77  5383.5  395.91  5412.4  396.94
  5549.3  397.42  5642.4  400.31  5751.9  406.47  5864.5  409.18  6181.7  410.79
#Mann= 7 ,-1 , 0
  3392.4     .12       0  4233.2     .07       0  4348.4     .05       0
    4760      .1       0    4971     .05       0  4992.7      .1       0
  5412.4     .12       0
Bank Sta=4971,4992.7
XS Rating Curve= 0 ,0
Exp/Cntr=0.3,0.1

Type RM Length L Ch R = 1 ,1139    ,554,554,554
BEGIN DESCRIPTION:
Rocky Creek 2.0
END DESCRIPTION:
XS GIS Cut Line= 3
      2521875.04     13853975.01        2520475.       13853625.
      2519674.99       13853675.
#Sta/Elev= 30
  3564.7  409.35  3616.3  410.01  3781.2  406.47  4049.2   405.8    4142  402.64
  4165.2  403.57  4206.4  399.58  4330.1  395.13  4441.2  393.79    4542  394.71
  4642.9  396.11  4737.3  397.86  4778.5  395.26    4812  396.04  4873.8  394.09
  4925.4  395.27  4956.3  393.65  4976.9  390.66  4978.9  383.88  4979.4  383.38
  5000.6  383.88  5005.3  390.94  5010.3  390.94  5017.9  394.89  5152.9  396.25
  5406.1  395.19  5468.7   397.3    5619  406.44  5779.3  410.58  5809.4  410.01
#Mann= 7 ,-1 , 0
  3564.7     .12       0  4441.2      .1       0    4542    .035       0
  4642.9      .1       0  4978.9     .05       0  5000.6      .1       0
  5152.9     .12       0
Bank Sta=4978.9,5000.6
XS Rating Curve= 0 ,0
Exp/Cntr=0.3,0.1

Type RM Length L Ch R = 1 ,585     ,402,402,402
BEGIN DESCRIPTION:
Rocky Creek 1.0
END DESCRIPTION:
XS GIS Cut Line= 3
      2522224.96     13853624.99        2520225.       13853225.
      2519724.99     13853625.01
#Sta/Elev= 30
    2965   412.3  3142.6  409.52  3189.3   407.7    3279  407.18  3427.8   405.5
  3627.8  406.92  3760.4  404.37  3930.3  398.51  4188.7  392.91  4402.9  396.66
  4525.3  395.95  4627.2  397.22  4681.5  394.87  4810.8  394.49  4861.8   396.3
  4953.6  394.19  4963.8  393.24    4974  389.73  4983.5  383.93    4984  383.43
  5005.2  383.93  5011.8   388.6  5032.6  393.26  5068.6   395.2  5110.3  394.51
  5263.4  394.45  5367.1  397.84  5424.8  402.16  5503.2  405.55  5644.9  410.28
#Mann= 10 ,-1 , 0
    2965    .035       0  3142.6     .12       0    3279     .07       0
  3427.8    .035       0  3930.3     .05       0  4681.5      .1       0
  4983.5     .05       0  5005.2      .1       0  5110.3     .07       0
  5263.4     .12       0
Bank Sta=4983.5,5005.2
XS Rating Curve= 0 ,0
Exp/Cntr=0.3,0.1

Type RM Length L Ch R = 1 ,183     ,0,0,0
BEGIN DESCRIPTION:
B20199
END DESCRIPTION:
XS GIS Cut Line= 4
      2522038.09     13853282.46      2520448.48     13852845.81
      2519992.19     13852889.96      2519526.29     13853390.19
#Sta/Elev= 30
  3074.2  409.58  3264.1  406.06  3503.3  405.81  3757.8  397.13  3844.8  394.23
  3992.4  391.94  4204.5  395.51  4367.8  397.89  4407.3  396.68  4466.5  395.21
  4508.7  394.02  4560.7  392.95  4708.8   394.5  4772.3  393.91  4886.9   394.7
  4927.1  397.01  4937.2  396.33  4957.3  389.59  4967.2   382.8  4967.7   382.3
    4989   382.8  4997.4  386.82  5007.5   387.7  5017.5  391.25  5037.6  393.51
  5256.5  393.16  5345.4  393.16  5529.1  400.04  5635.6  405.71  5864.7   409.8
#Mann= 11 ,-1 , 0
  3074.2     .07       0  3757.8     .05       0  4204.5     .07       0
  4407.3     .05       0  4466.5     .07       0  4508.7     .05       0
  4772.3      .1       0  4967.2     .05       0    4989      .1       0
  5256.5     .05       0  5529.1     .12       0
Bank Sta=4967.2,4989
XS Rating Curve= 0 ,0
Exp/Cntr=0.3,0.1

Chan Stop Cuts=-1
Use User Specified Reach Order=0
Composite Channel Slope=5