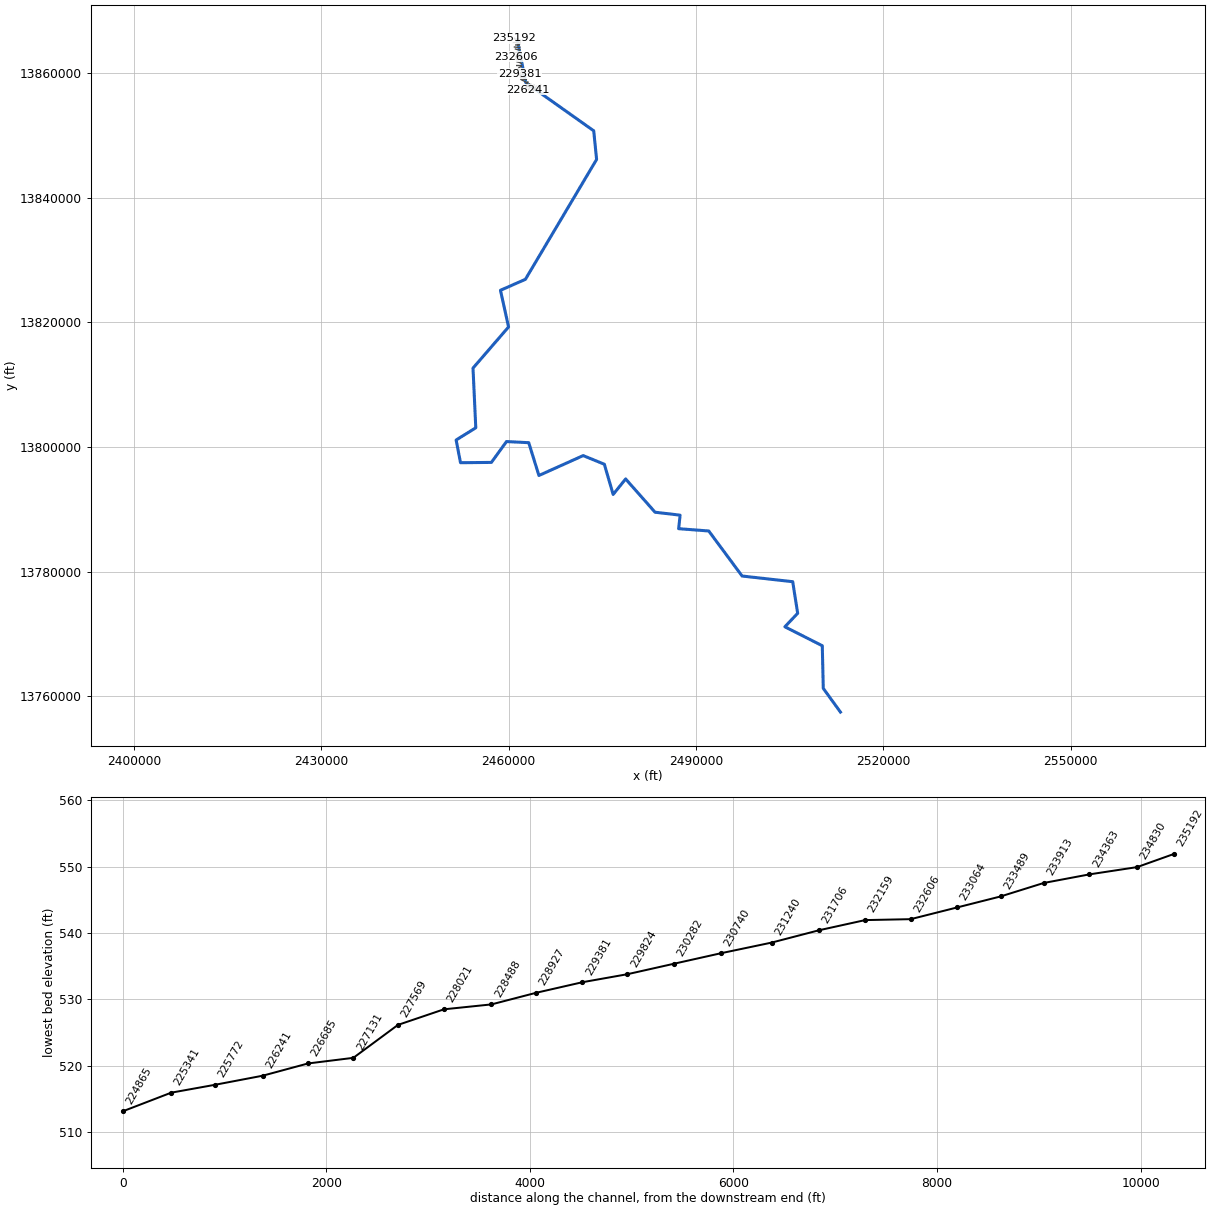
--- SANDY FORK.prj (project) ---

Proj Title=SANDY FORK Base Level Engineering
Current Plan=p01
Default Exp/Contr=0.3,0.1
English Units
Geom File=g01
Flow File=f01
Plan File=p01
Y Axis Title=Elevation
X Axis Title(PF)=Main Channel Distance
X Axis Title(XS)=Station
BEGIN DESCRIPTION:
SANDY FORK
END DESCRIPTION:
DSS Export Rating Curves= 0
DSS Export Rating Curve Sorted= 0
DSS Export Volume Flow Curves= 0
DXF OffsetX= 0
DXF OffsetY= 0
DXF ScaleX= 1
DXF ScaleY= 10

--- SANDY FORK.p01 (plan) ---

Plan Title=Multiple Run
Short Identifier=Multiple
Geom File=g01
Flow File=f01
Subcritical Flow
K Sum by GR= 0
Std Step Tol= 0.01
Critical Tol= 0.01
Num of Std Step Trials= 20
Max Error Tol= 0.3
Flow Tol Ratio= 0.001
Split Flow NTrial= 30
Split Flow Tol= 0.02
Split Flow Ratio= 0.02
Log Output Level= 0
Friction Slope Method= 1
Unsteady Friction Slope Method= 2
Unsteady Bridges Friction Slope Method= 1
Parabolic Critical Depth
Global Vel Dist=  1 , 1 , 1
Global Log Level= 0
CheckData=True
Encroach Param= -1, 0, 0, 0
BEGIN DESCRIPTION:
Multiple Run
END DESCRIPTION:

--- SANDY FORK.f01 (steady flow) ---

Flow Title=Multiple
Number of Profiles=7
Profile Names=10-year,25-year,50-year,1pct_min,100-year,1pct_plu,500-year
River Rch & RM= SANDY FORK,Reach-1,235192
     641    1027    1373     889    1773    3538    2930
River Rch & RM= SANDY FORK,Reach-1,234830
    1080    1781    2428    1600    3193    6371    5471
River Rch & RM= SANDY FORK,Reach-1,233913
    1263    2091    2857    1885    3762    7505    6464
River Rch & RM= SANDY FORK,Reach-1,228021
    1411    2348    3221    2133    4255    8490    7361
River Rch & RM= SANDY FORK,Reach-1,227131
    2282    3900    5446    3668    7319   14603   13102
River Rch & RM= SANDY FORK,Reach-1,221755
    3027    5225    7344    4974    9925   19804   17971
River Rch & RM= SANDY FORK,Reach-1,218020
    3129    5403    7596    5146   10268   20487   18596
River Rch & RM= SANDY FORK,Reach-1,217189
    3064    5259    7361    4963    9902   19758   17763
River Rch & RM= SANDY FORK,Reach-1,209127
    4065    7021    9871    6678   13324   26585   24063
River Rch & RM= SANDY FORK,Reach-1,204937
    4099    7068    9926    6706   13381   26698   24103
River Rch & RM= SANDY FORK,Reach-1,203540
    4096    7051    9890    6673   13315   26567   23920
River Rch & RM= SANDY FORK,Reach-1,198037
    4212    7253   10175    6866   13700   27335   24615
River Rch & RM= SANDY FORK,Reach-1,196911
    4173    7173   10051    6773   13514   26965   24217
River Rch & RM= SANDY FORK,Reach-1,193475
    5205    9004   12671    8573   17104   34128   30886
River Rch & RM= SANDY FORK,Reach-1,190798
    5331    9228   12992    8793   17545   35007   31707
River Rch & RM= SANDY FORK,Reach-1,189108
    5332    9226   12986    8787   17532   34981   31666
River Rch & RM= SANDY FORK,Reach-1,188551
    5278    9110   12800    8645   17248   34415   31035
River Rch & RM= SANDY FORK,Reach-1,184276
    5184    8924   12516    8436   16833   33586   30172
River Rch & RM= SANDY FORK,Reach-1,181435
    5363    9237   12960    8739   17436   34790   31272
River Rch & RM= SANDY FORK,Reach-1,180273
    5366    9238   12958    8735   17428   34774   31239
River Rch & RM= SANDY FORK,Reach-1,178995
    5403    9305   13055    8802   17562   35041   31491
River Rch & RM= SANDY FORK,Reach-1,178695
    6048   10438   14666    9901   19754   39415   35505
River Rch & RM= SANDY FORK,Reach-1,174449
    6129   10578   14861   10031   20015   39935   35966
River Rch & RM= SANDY FORK,Reach-1,173089
    6155   10624   14928   10078   20108   40121   36142
River Rch & RM= SANDY FORK,Reach-1,171861
    6183   10670   14991   10118   20188   40280   36271
River Rch & RM= SANDY FORK,Reach-1,169952
    6246   10779   15144   10221   20394   40691   36641
River Rch & RM= SANDY FORK,Reach-1,169322
    6801   11767   16563   11199   22344   44583   40282
River Rch & RM= SANDY FORK,Reach-1,168566
    6883   11921   16790   11360   22665   45224   40912
River Rch & RM= SANDY FORK,Reach-1,166850
    6926   11985   16870   11406   22758   45408   41025
River Rch & RM= SANDY FORK,Reach-1,160287
    6997   12112   17054   11533   23012   45916   41503
River Rch & RM= SANDY FORK,Reach-1,159143
    7068   12226   17206   11629   23204   46298   41800
River Rch & RM= SANDY FORK,Reach-1,157767
    7093   12264   17254   11658   23260   46411   41874
River Rch & RM= SANDY FORK,Reach-1,154972
    7105   12265   17235   11631   23206   46302   41671
River Rch & RM= SANDY FORK,Reach-1,148898
    7641   13195   18548   12519   24978   49837   44860
River Rch & RM= SANDY FORK,Reach-1,140928
    7541   13001   18256   12307   24556   48997   44004
River Rch & RM= SANDY FORK,Reach-1,140164
    7701   13279   18649   12573   25087   50055   44960
River Rch & RM= SANDY FORK,Reach-1,133404
    7970   13757   19333   13043   26024   51924   46696
River Rch & RM= SANDY FORK,Reach-1,132137
    8040   13864   19471   13127   26192   52260   46932
River Rch & RM= SANDY FORK,Reach-1,125009
    8043   13864   19465   13119   26176   52228   46874
River Rch & RM= SANDY FORK,Reach-1,120057
    8085   13932   19557   13179   26295   52465   47066
River Rch & RM= SANDY FORK,Reach-1,118247
    8245   14218   19970   13464   26863   53599   48134
River Rch & RM= SANDY FORK,Reach-1,113413
    8571   14784   20769   14003   27940   55748   50068
River Rch & RM= SANDY FORK,Reach-1,109594
    8875   15316   21525   14519   28968   57799   51946
River Rch & RM= SANDY FORK,Reach-1,107380
    9119   15742   22126   14926   29780   59419   53411
River Rch & RM= SANDY FORK,Reach-1,103099
    9143   15781   22179   14960   29849   59557   53525
River Rch & RM= SANDY FORK,Reach-1,101693
    9288   16031   22532   15197   30323   60502   54370
River Rch & RM= SANDY FORK,Reach-1,95396
    9270   15987   22456   15137   30201   60260   54083
River Rch & RM= SANDY FORK,Reach-1,89765
    9291   16022   22505   15169   30267   60390   54196
River Rch & RM= SANDY FORK,Reach-1,89040
    9420   16248   22827   15389   30705   61265   55001
River Rch & RM= SANDY FORK,Reach-1,84369
   10740   18568   26130   17643   35203   70239   63239
River Rch & RM= SANDY FORK,Reach-1,81042
   11732   20303   28597   19323   38554   76926   69349
River Rch & RM= SANDY FORK,Reach-1,76811
   12078   20908   29455   19906   39718   79249   71465
River Rch & RM= SANDY FORK,Reach-1,73015
   12482   21561   30337   20477   40856   81519   73299
River Rch & RM= SANDY FORK,Reach-1,71168
   12063   20867   29382   19847   39600   79013   71179
River Rch & RM= SANDY FORK,Reach-1,69261
   12464   21511   30248   20404   40711   81229   72944
River Rch & RM= SANDY FORK,Reach-1,62292
   12024   20780   29241   19738   39382   78577   70687
River Rch & RM= SANDY FORK,Reach-1,60937
   12486   21538   30276   20416   40736   81278   72938
River Rch & RM= SANDY FORK,Reach-1,58638
   12193   21089   29693   20055   40015   79840   71908
River Rch & RM= SANDY FORK,Reach-1,55658
   12850   22165   31157   21009   41918   83637   75041
River Rch & RM= SANDY FORK,Reach-1,52208
   13140   22663   31857   21480   42858   85512   76711
River Rch & RM= SANDY FORK,Reach-1,44635
   13172   22716   31929   21526   42950   85697   76863
River Rch & RM= SANDY FORK,Reach-1,41065
   13177   22723   31936   21530   42957   85711   76866
River Rch & RM= SANDY FORK,Reach-1,40001
   13702   23638   33235   22413   44719   89227   80066
River Rch & RM= SANDY FORK,Reach-1,38122
   13812   23832   33511   22600   45093   89973   80747
River Rch & RM= SANDY FORK,Reach-1,31353
   13850   23890   33585   22646   45185   90156   80877
River Rch & RM= SANDY FORK,Reach-1,27625
   13930   23999   33711   22711   45314   90413   80964
River Rch & RM= SANDY FORK,Reach-1,14301
   13922   23982   33684   22691   45274   90334   80876
River Rch & RM= SANDY FORK,Reach-1,11162
   13922   23963   33641   22650   45192   90170   80644
River Rch & RM= SANDY FORK,Reach-1,9718
   14144   24350   34189   23022   45934   91650   81985
Boundary for River Rch & Prof#=SANDY FORK,Reach-1,1
Up Type=0
Dn Type=3
Dn Slope=0.0006
Boundary for River Rch & Prof#=SANDY FORK,Reach-1,2
Up Type=0
Dn Type=3
Dn Slope=0.0006
Boundary for River Rch & Prof#=SANDY FORK,Reach-1,3
Up Type=0
Dn Type=3
Dn Slope=0.0006
Boundary for River Rch & Prof#=SANDY FORK,Reach-1,4
Up Type=0
Dn Type=3
Dn Slope=0.0006
Boundary for River Rch & Prof#=SANDY FORK,Reach-1,5
Up Type=0
Dn Type=3
Dn Slope=0.0006
Boundary for River Rch & Prof#=SANDY FORK,Reach-1,6
Up Type=0
Dn Type=3
Dn Slope=0.0006
Boundary for River Rch & Prof#=SANDY FORK,Reach-1,7
Up Type=0
Dn Type=3
Dn Slope=0.0006

--- SANDY FORK.g01 (geometry) ---

Geom Title=Existing Conditions
Program Version=4.10

River Reach=SANDY FORK      ,Reach-1
Reach XY= 30
      2461373.61     13865426.08      2462733.13     13858518.93
      2473608.72     13850792.32      2474074.73     13846190.11
      2462669.35     13826930.63      2458678.27     13825173.64
      2459972.76     13819280.93      2454278.61     13812673.52
      2454724.61     13803090.16      2451578.55     13801123.53
      2452278.61      13797476.5      2457223.45     13797528.75
      2459644.99     13800875.06      2463205.38     13800695.48
       2464835.7      13795425.7      2471923.45     13798621.25
      2475314.41     13797235.05      2476722.56     13792380.39
       2478723.6     13794871.81      2483433.28     13789528.05
      2487445.03      13789055.7      2487218.81     13786882.85
      2492035.06     13786514.39      2497372.45     13779280.73
      2505481.17     13778367.24      2506274.48     13773290.88
      2504228.27     13771126.36      2510217.14     13768081.21
      2510377.05     13761230.84        2513125.       13757425.

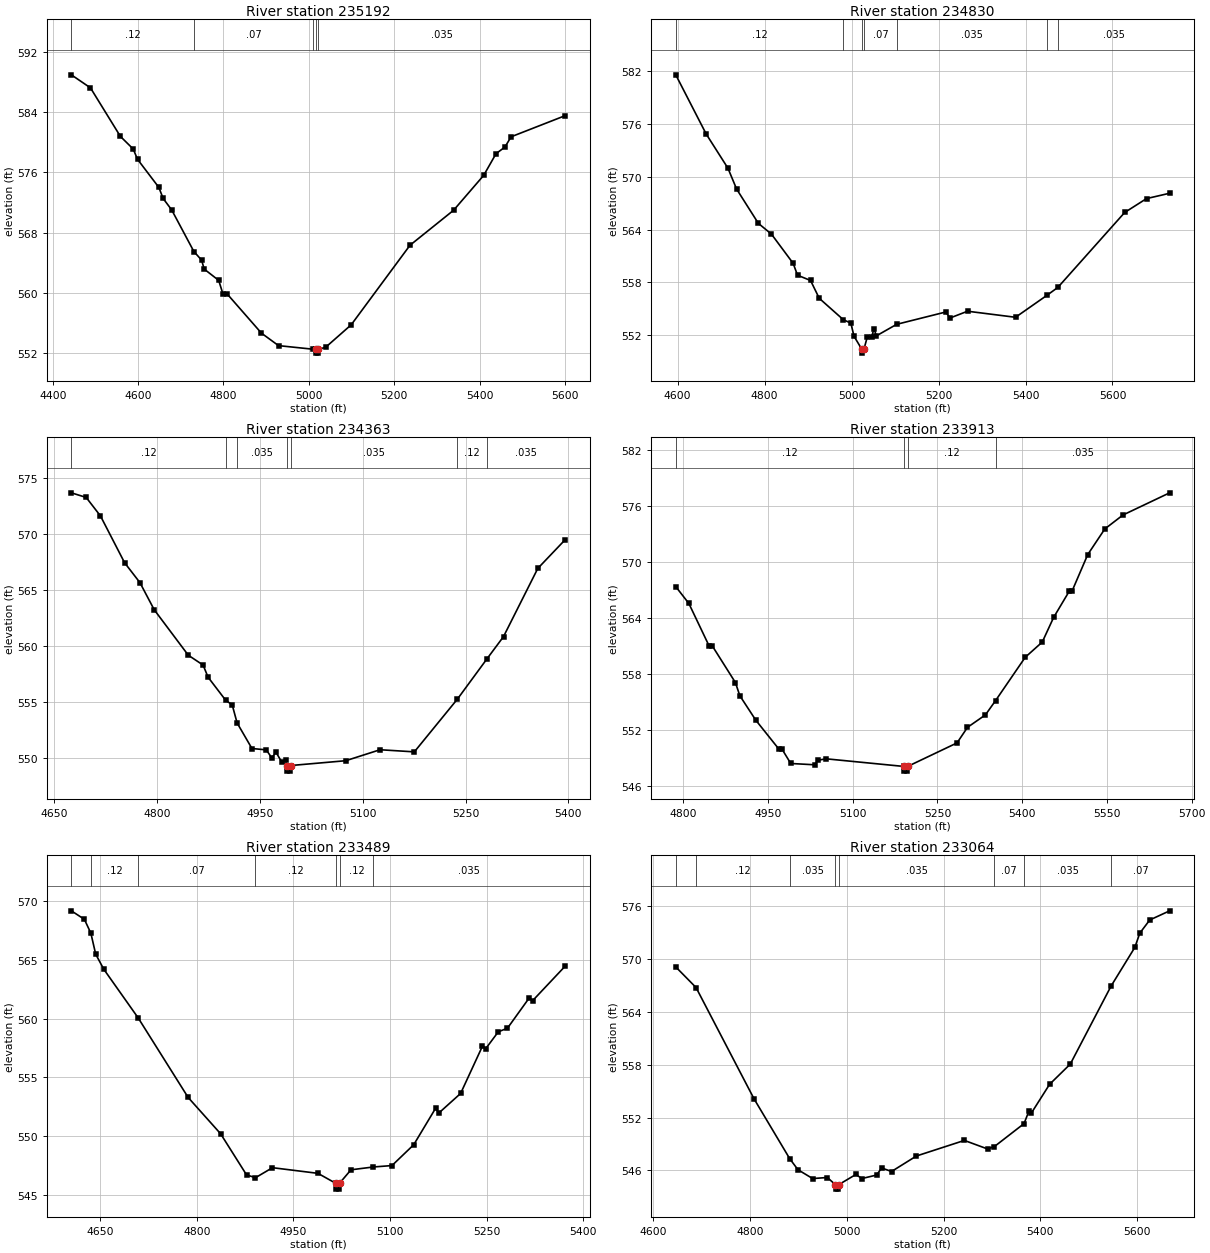
Type RM Length L Ch R = 1 ,235192  ,362,362,362
BEGIN DESCRIPTION:
E21657
END DESCRIPTION:
XS GIS Cut Line= 3
      2461929.73     13865323.22      2461134.98     13865366.02
      2460911.96     13865650.13
#Sta/Elev= 30
  4443.7  589.02  4488.5  587.28  4558.6  580.81  4588.6  579.13  4598.7  577.76
  4648.7  574.01  4658.7  572.54  4678.8  571.01  4730.8  565.46  4748.9  564.32
  4754.8  563.13  4788.9  561.62  4798.9   559.8    4809  559.79  4889.1  554.58
  4929.1  552.92    5010  552.44  5017.3  552.42  5017.5  551.92    5021  551.92
  5021.3  552.42  5039.3  552.69  5099.4   555.7  5237.1   566.3  5339.3  570.97
  5409.8  575.62  5438.7  578.51  5459.5  579.39    5474  580.76  5600.8  583.58
#Mann= 5 ,-1 , 0
  4443.7     .12       0  4730.8     .07       0    5010    .035       0
  5017.3     .05       0  5021.3    .035       0
Bank Sta=5017.3,5021.3
XS Rating Curve= 0 ,0
Exp/Cntr=0.3,0.1

Type RM Length L Ch R = 1 ,234830  ,467,467,467
BEGIN DESCRIPTION:
SANDY FORK 213.0
END DESCRIPTION:
XS GIS Cut Line= 3
      2461875.05       13865025.        2461475.       13865025.
      2460741.98     13864960.48
#Sta/Elev= 30
  4595.6  581.62  4665.6  574.88  4715.6  570.99  4735.6  568.61  4785.6  564.71
  4815.6  563.49  4865.6  560.16  4875.6  558.81  4905.6  558.21  4925.6  556.18
  4981.1  553.74  4998.2  553.36  5005.7  551.85  5022.8  550.44  5023.3  549.94
  5028.7  550.44  5035.8  551.72  5045.8  551.78  5051.8  552.73  5056.8   551.9
  5103.7  553.22  5216.5  554.62  5226.5  553.94  5266.7  554.71  5377.1  554.02
    5449  556.51  5474.4  557.42  5628.1  565.95  5678.3  567.53  5731.5  568.14
#Mann= 7 ,-1 , 0
  4595.6     .12       0  4981.1     .07       0  5022.8     .05       0
  5028.7     .07       0  5103.7    .035       0    5449     .07       0
  5474.4    .035       0
Bank Sta=5022.8,5028.7
XS Rating Curve= 0 ,0
Exp/Cntr=0.3,0.1

Type RM Length L Ch R = 1 ,234363  ,450,450,450
BEGIN DESCRIPTION:
SANDY FORK 212.0
END DESCRIPTION:
XS GIS Cut Line= 3
      2461774.98     13864774.98        2461525.       13864575.
      2461125.03       13864575.
#Sta/Elev= 30
  4675.3   573.7  4696.9  573.29  4717.7  571.64  4752.9  567.46  4775.3  565.68
  4796.1  563.26  4845.8   559.2  4867.4  558.32  4874.6  557.24  4900.4  555.17
  4909.8  554.77    4917  553.15  4938.6  550.87  4959.4  550.75  4967.4  550.05
  4973.8  550.52  4981.8  549.69  4988.2  549.84  4989.2  549.35  4989.7  548.85
  4994.7  548.85  4995.2  549.35  5075.4  549.78  5125.4  550.76  5175.4  550.57
  5238.3  555.29  5281.1  558.86  5305.4  560.86  5355.4  566.95  5395.4  569.52
#Mann= 7 ,-1 , 0
  4675.3     .12       0  4900.4     .07       0    4917    .035       0
  4989.2    .035       0  4995.2    .035       0  5238.3     .12       0
  5281.1    .035       0
Bank Sta=4989.2,4995.2
XS Rating Curve= 0 ,0
Exp/Cntr=0.3,0.1

Type RM Length L Ch R = 1 ,233913  ,424,424,424
BEGIN DESCRIPTION:
SANDY FORK 211.0
END DESCRIPTION:
XS GIS Cut Line= 3
      2461774.98     13864224.99        2461575.       13864175.
       2460910.9     13864249.55
#Sta/Elev= 30
  4786.6  567.36  4809.8  565.55  4845.8  560.97    4851  561.02  4892.2  557.06
    4900  555.65  4928.3  553.02  4969.5  549.89  4974.7  549.91  4990.2  548.37
  5032.8  548.23  5037.8  548.72  5053.1  548.87    5191  548.05  5191.5  547.55
  5196.5  547.55    5197  548.05  5284.6  550.58  5303.1  552.25  5334.9  553.59
  5352.9  555.13  5405.3  559.77  5435.5  561.41  5455.6  564.05  5483.3  566.87
  5488.3  566.89    5516   570.8  5546.2  573.55  5578.4  575.05    5661  577.43
#Mann= 4 ,-1 , 0
  4786.6     .12       0    5191     .05       0    5197     .12       0
  5352.9    .035       0
Bank Sta=5191,5197
XS Rating Curve= 0 ,0
Exp/Cntr=0.3,0.1

Type RM Length L Ch R = 1 ,233489  ,425,425,425
BEGIN DESCRIPTION:
SANDY FORK 210.0
END DESCRIPTION:
XS GIS Cut Line= 3
      2461825.03       13863775.        2461425.       13863825.
      2461075.05     13863924.99
#Sta/Elev= 30
  4605.1  569.14  4625.3  568.42  4635.4  567.24  4642.9  565.46  4655.5  564.18
  4708.9  560.05  4786.5   553.3  4836.9  550.22  4877.2  546.73  4891.1  546.49
  4917.5  547.34  4988.1  546.86  5015.6  546.02  5016.1  545.52  5021.2  545.52
  5021.7  546.02  5039.4  547.16  5074.3   547.4  5103.1  547.52  5136.9  549.29
  5170.7  552.37  5175.9  551.98  5209.7  553.64  5243.5  557.64  5248.7  557.44
  5268.2  558.87  5282.5  559.18  5316.3  561.75  5321.5  561.51  5372.2  564.45
#Mann= 7 ,-1 , 0
  4605.1     .07       0  4635.4     .12       0  4708.9     .07       0
  4891.1     .12       0  5015.6     .05       0  5021.7     .12       0
  5074.3    .035       0
Bank Sta=5015.6,5021.7
XS Rating Curve= 0 ,0
Exp/Cntr=0.3,0.1

Type RM Length L Ch R = 1 ,233064  ,458,458,458
BEGIN DESCRIPTION:
SANDY FORK 209.0
END DESCRIPTION:
XS GIS Cut Line= 3
      2461775.03       13863375.        2461425.       13863425.
      2460774.97     13863274.99
#Sta/Elev= 30
  4646.4   569.1  4688.3  566.76  4808.1  554.13    4882  547.32    4899  546.07
  4929.3  545.07  4959.6  545.19  4976.5  544.37    4977  543.87  4982.5  543.87
    4983  544.37  5018.8  545.54  5030.8  545.07  5061.6  545.47  5071.8  546.28
  5092.3  545.87  5143.7  547.63  5242.9   549.4  5290.8  548.43  5305.1  548.71
  5366.2  551.31  5376.3  552.73  5381.4  552.51    5419  555.77  5461.8  558.07
  5546.1  566.93  5595.2  571.32  5605.5  572.94    5626  574.43  5667.1  575.47
#Mann= 8 ,-1 , 0
  4646.4     .07       0  4688.3     .12       0    4882    .035       0
  4976.5    .035       0    4983    .035       0  5305.1     .07       0
  5366.2    .035       0  5546.1     .07       0
Bank Sta=4976.5,4983
XS Rating Curve= 0 ,0
Exp/Cntr=0.3,0.1

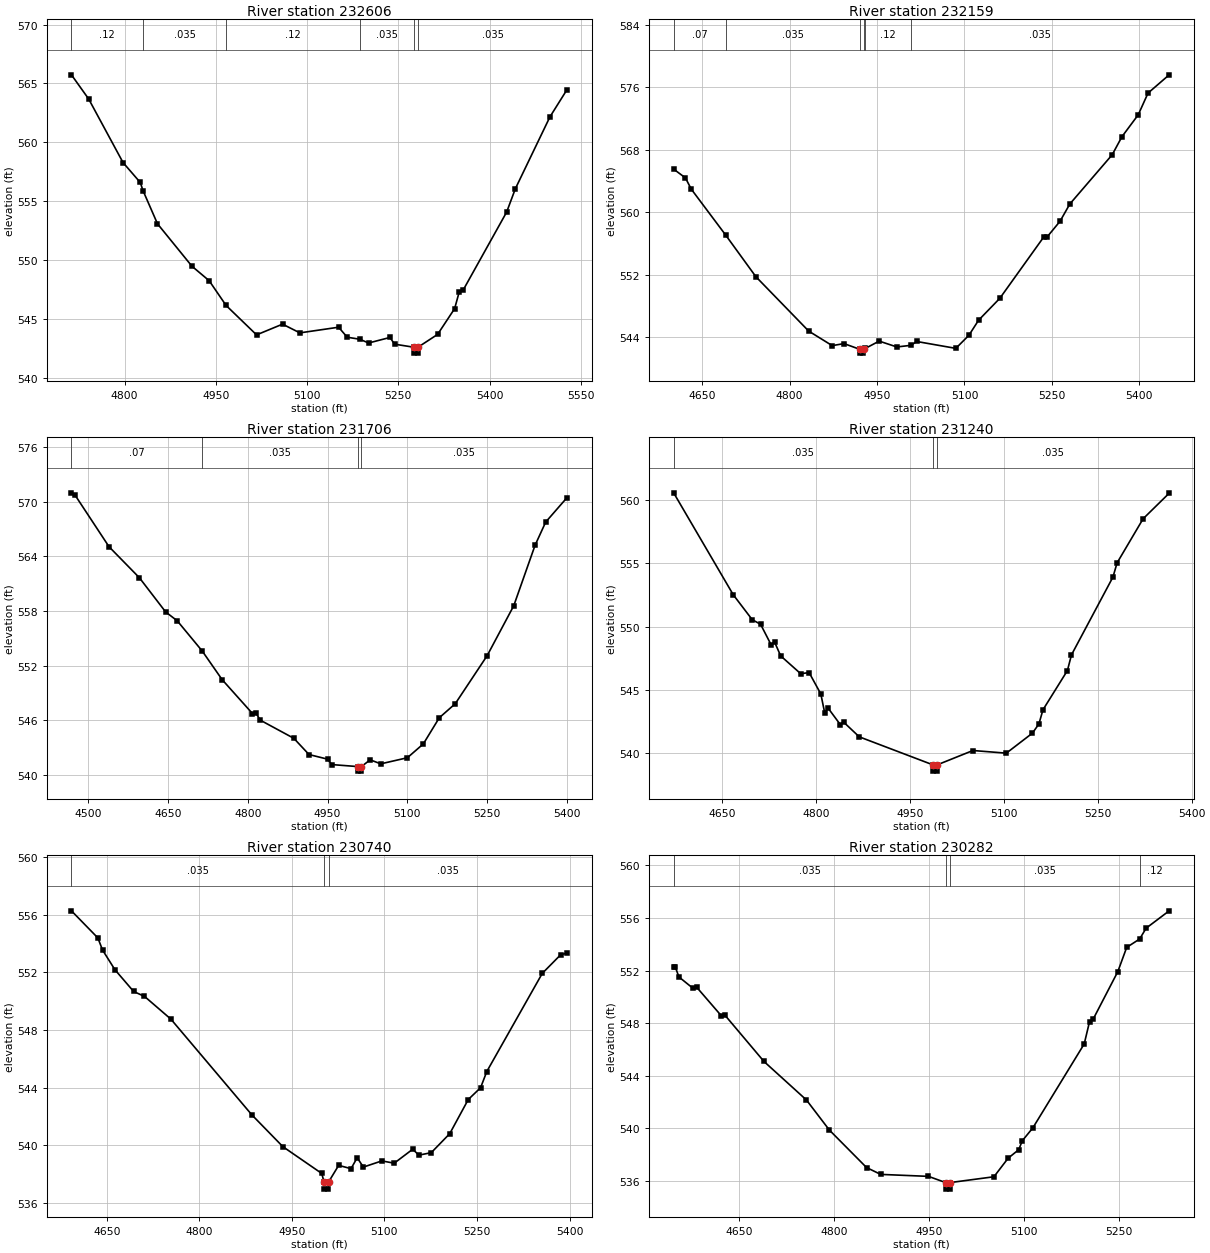
Type RM Length L Ch R = 1 ,232606  ,447,447,447
BEGIN DESCRIPTION:
SANDY FORK 208.0
END DESCRIPTION:
XS GIS Cut Line= 3
      2461724.99     13863224.99        2461525.       13863025.
      2461125.03     13862675.03
#Sta/Elev= 30
  4712.8  565.73  4741.1  563.68  4797.6  558.28  4825.9  556.59  4830.4   555.9
  4854.2  553.08  4910.8  549.48  4939.1  548.25  4966.9  546.15    5017  543.65
  5059.7  544.56  5088.2  543.82  5151.8   544.3    5166  543.45  5186.6  543.28
  5201.1  542.96  5236.2  543.43  5243.8  542.86  5275.7   542.6  5276.2   542.1
  5281.7   542.1  5282.2   542.6  5314.5  543.69  5342.5  545.88  5350.1  547.31
  5356.8  547.48    5428  554.08  5442.2  556.05  5499.1  562.16  5527.1  564.47
#Mann= 6 ,-1 , 0
  4712.8     .12       0  4830.4    .035       0  4966.9     .12       0
  5186.6    .035       0  5275.7     .05       0  5282.2    .035       0
Bank Sta=5275.7,5282.2
XS Rating Curve= 0 ,0
Exp/Cntr=0.3,0.1

Type RM Length L Ch R = 1 ,232159  ,453,453,453
BEGIN DESCRIPTION:
SANDY FORK 207.0
END DESCRIPTION:
XS GIS Cut Line= 3
      2461875.02       13862675.        2461475.       13862625.
      2461075.04     13862425.02
#Sta/Elev= 30
    4601  565.53  4621.2  564.41  4631.3  562.96  4690.1   557.1  4742.1  551.75
  4832.8  544.78  4873.1  542.92  4893.3  543.18    4920  542.46  4920.5  541.96
  4926.5  541.96    4927  542.46  4929.8  542.56  4953.7   543.5    4984  542.75
  5008.2  542.96  5018.1  543.45  5085.2  542.57  5107.6  544.24  5124.3  546.18
  5160.7  548.98  5236.1  556.84  5241.7  556.83  5264.1  558.86  5280.8  561.06
  5353.5  567.37  5370.3  569.69  5398.2  572.49    5415  575.27  5451.3  577.61
#Mann= 6 ,-1 , 0
    4601     .07       0  4690.1    .035       0    4920     .05       0
    4927    .035       0  4929.8     .12       0  5008.2    .035       0
Bank Sta=4920,4927
XS Rating Curve= 0 ,0
Exp/Cntr=0.3,0.1

Type RM Length L Ch R = 1 ,231706  ,466,466,466
BEGIN DESCRIPTION:
SANDY FORK 206.0
END DESCRIPTION:
XS GIS Cut Line= 3
      2462025.02     13862575.01        2461625.       13862225.
      2461225.03       13862225.
#Sta/Elev= 30
  4468.5  570.98  4475.6   570.7  4539.2  565.06  4596.2  561.66  4645.5  557.91
  4667.4  556.93  4714.4  553.61  4751.8  550.47  4808.8  546.75  4815.4  546.83
    4823  546.04  4886.6  544.03  4915.1  542.25  4950.2  541.74  4957.8  541.15
  5006.5  540.93    5007  540.43  5013.1  540.43  5013.6  540.93    5030  541.67
    5050  541.23    5100   541.9    5130  543.42    5160  546.29    5190  547.83
    5250  553.11    5300  558.59    5340  565.22    5360  567.77    5400  570.45
#Mann= 4 ,-1 , 0
  4468.5     .07       0  4714.4    .035       0  5006.5    .035       0
  5013.6    .035       0
Bank Sta=5006.5,5013.6
XS Rating Curve= 0 ,0
Exp/Cntr=0.3,0.1

Type RM Length L Ch R = 1 ,231240  ,500,500,500
BEGIN DESCRIPTION:
SANDY FORK 205.0
END DESCRIPTION:
XS GIS Cut Line= 3
        2462075.       13861625.        2461675.       13861775.
      2461325.01       13861875.
#Sta/Elev= 30
  4572.9  560.57  4668.1  552.51  4698.4  550.54  4711.7  550.18  4728.7  548.54
    4734  548.78  4743.8  547.68  4775.8  546.27  4789.2  546.36  4807.9  544.67
  4814.1  543.17  4819.4  543.56    4839  542.25  4844.4  542.44  4869.3  541.28
  4986.7  539.07  4987.2  538.57  4993.4  538.57  4993.9  539.07  5050.8   540.2
  5104.1  539.99  5145.7  541.57  5156.1   542.3  5162.6  543.42  5201.6  546.52
  5208.1  547.76  5274.4  553.92  5280.9  555.03  5322.5  558.52  5364.1  560.54
#Mann= 3 ,-1 , 0
  4572.9    .035       0  4986.7    .035       0  4993.9    .035       0
Bank Sta=4986.7,4993.9
XS Rating Curve= 0 ,0
Exp/Cntr=0.3,0.1

Type RM Length L Ch R = 1 ,230740  ,458,458,458
BEGIN DESCRIPTION:
SANDY FORK 204.0
END DESCRIPTION:
XS GIS Cut Line= 3
      2462074.99       13861225.        2461675.       13861275.
      2461275.01       13861275.
#Sta/Elev= 30
  4592.8  556.28  4635.6   554.4  4643.2  553.56  4663.3  552.19  4693.6  550.68
  4711.2  550.34    4754  548.76  4885.1  542.12  4935.4  539.91  4998.4  538.05
  5002.2  537.46  5002.7  536.96  5009.1  536.96  5009.6  537.46  5025.9  538.61
  5045.9  538.38  5055.9  539.14  5065.9  538.49  5095.9  538.92  5115.9  538.76
  5145.9  539.73  5155.9  539.32  5175.9  539.49  5205.9  540.81  5235.9  543.18
  5255.9     544  5265.9  545.12  5355.9  551.94  5385.9  553.24  5395.9  553.34
#Mann= 3 ,-1 , 0
  4592.8    .035       0  5002.2    .035       0  5009.6    .035       0
Bank Sta=5002.2,5009.6
XS Rating Curve= 0 ,0
Exp/Cntr=0.3,0.1

Type RM Length L Ch R = 1 ,230282  ,458,458,458
BEGIN DESCRIPTION:
SANDY FORK 203.0
END DESCRIPTION:
XS GIS Cut Line= 3
      2462025.03     13861125.02        2461625.       13860925.
      2461474.98     13860624.96
#Sta/Elev= 30
  4546.3  552.25  4549.1  552.25  4554.7  551.52  4577.1  550.65  4582.7  550.74
  4621.8  548.56  4627.4  548.61  4688.9   545.1    4756  542.17  4792.3  539.88
    4851  537.03  4873.4  536.51  4948.8  536.36  4975.8  535.89  4976.3  535.39
  4982.8  535.39  4983.3  535.89  5052.2  536.33  5074.6  537.74  5091.4  538.39
    5097  539.07  5113.7  540.05  5194.8  546.43  5203.2  548.12  5208.8   548.3
  5247.9  551.93  5261.9  553.77  5282.4  554.41  5292.6  555.23    5329  556.55
#Mann= 4 ,-1 , 0
  4546.3    .035       0  4975.8    .035       0  4983.3    .035       0
  5282.4     .12       0
Bank Sta=4975.8,4983.3
XS Rating Curve= 0 ,0
Exp/Cntr=0.3,0.1

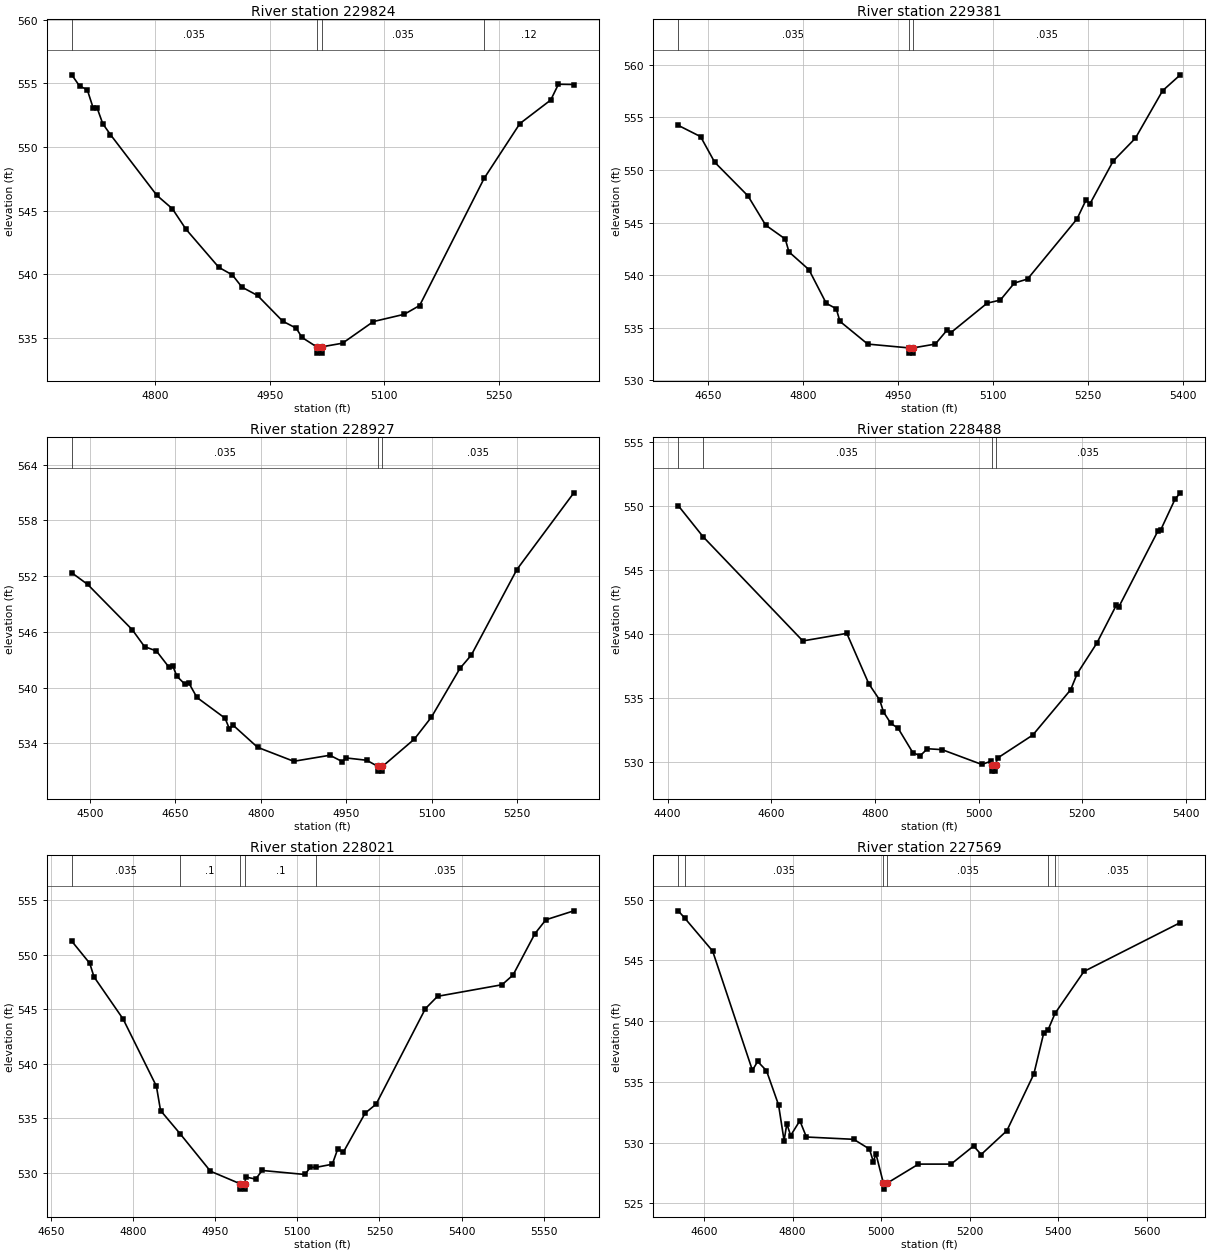
Type RM Length L Ch R = 1 ,229824  ,443,443,443
BEGIN DESCRIPTION:
SANDY FORK 202.0
END DESCRIPTION:
XS GIS Cut Line= 3
      2462175.01       13860625.        2461875.       13860575.
      2461525.01       13860625.
#Sta/Elev= 30
  4690.7  555.67  4700.9  554.79    4711   554.5  4718.6  553.09  4723.7   553.1
  4731.3  551.83  4741.4  550.97  4802.2   546.2  4822.5  545.15  4840.2  543.55
  4883.3  540.55  4901.1  539.95  4913.7  538.99    4934  538.34    4967  536.32
  4984.7  535.77  4992.3  535.04  5011.3  534.31  5011.8  533.81  5018.3  533.81
  5018.8  534.31  5045.4  534.59  5085.8  536.29  5126.2  536.86  5146.4  537.55
  5230.9  547.54  5277.7  551.84  5318.1  553.69  5328.2  554.93  5348.4  554.91
#Mann= 4 ,-1 , 0
  4690.7    .035       0  5011.3    .035       0  5018.8    .035       0
  5230.9     .12       0
Bank Sta=5011.3,5018.8
XS Rating Curve= 0 ,0
Exp/Cntr=0.3,0.1

Type RM Length L Ch R = 1 ,229381  ,454,454,454
BEGIN DESCRIPTION:
SANDY FORK 201.0
END DESCRIPTION:
XS GIS Cut Line= 3
      2462225.02     13860525.03        2462025.       13860175.
      2461724.97     13859924.97
#Sta/Elev= 30
  4602.4  554.24  4637.7  553.17    4660  550.74  4712.6  547.54  4740.6  544.76
  4771.6  543.44  4777.4  542.22    4809  540.53  4836.4  537.33  4852.2  536.82
    4858  535.62  4901.9  533.46  4966.5   533.1    4967   532.6  4973.6   532.6
  4974.1   533.1  5008.8  533.46    5027  534.76  5033.5  534.55  5090.8  537.35
  5111.6  537.64  5133.8  539.26  5154.6  539.64  5232.7  545.34    5247  547.14
  5253.5  546.81    5290  550.85  5325.1  553.02  5368.1  557.53  5396.1  559.04
#Mann= 3 ,-1 , 0
  4602.4    .035       0  4966.5    .035       0  4974.1    .035       0
Bank Sta=4966.5,4974.1
XS Rating Curve= 0 ,0
Exp/Cntr=0.3,0.1

Type RM Length L Ch R = 1 ,228927  ,439,439,439
BEGIN DESCRIPTION:
SANDY FORK 200.0
END DESCRIPTION:
XS GIS Cut Line= 3
      2462475.03     13860125.03        2462075.       13859775.
      2461725.05       13859775.
#Sta/Elev= 30
  4468.3  552.37  4496.3  551.11  4574.6  546.23    4596  544.42  4616.9  543.95
  4638.7  542.22  4645.3  542.38  4652.9  541.23  4667.2  540.35  4673.8   540.5
  4688.1  538.94  4737.4  536.71    4745  535.58  4751.7  535.95  4794.4  533.58
    4858  532.07  4921.5  532.72  4943.4  532.03    4950  532.43  4986.1  532.18
    5006  531.51  5006.5  531.01  5013.2  531.01  5013.7  531.51  5069.8  534.46
  5099.8  536.83  5149.8  542.07  5169.8  543.51  5249.8  552.72  5349.8  560.98
#Mann= 3 ,-1 , 0
  4468.3    .035       0    5006    .035       0  5013.7    .035       0
Bank Sta=5006,5013.7
XS Rating Curve= 0 ,0
Exp/Cntr=0.3,0.1

Type RM Length L Ch R = 1 ,228488  ,467,467,467
BEGIN DESCRIPTION:
SANDY FORK 199.0
END DESCRIPTION:
XS GIS Cut Line= 3
      2462675.01     13859825.01        2462275.       13859425.
      2461875.02       13859375.
#Sta/Elev= 30
  4420.4  550.02  4468.3  547.59  4660.8  539.44  4745.7  540.03  4788.1  536.09
  4809.3  534.81  4816.4  533.89  4830.5     533  4844.7  532.61    4873  530.71
  4887.1  530.46  4901.3  531.01  4929.5  530.94  5006.3  529.78  5023.9  530.04
    5025  529.76  5025.5  529.26  5032.3  529.26  5032.8  529.76  5036.5  530.28
  5104.5  532.08  5177.6  535.62  5190.2  536.88    5228  539.26  5265.8  542.24
  5270.8  542.12  5346.4  548.07  5351.4  548.12  5379.1  550.53  5389.2  551.02
#Mann= 4 ,-1 , 0
  4420.4     .07       0  4468.3    .035       0    5025    .035       0
  5032.8    .035       0
Bank Sta=5025,5032.8
XS Rating Curve= 0 ,0
Exp/Cntr=0.3,0.1

Type RM Length L Ch R = 1 ,228021  ,452,452,452
BEGIN DESCRIPTION:
SANDY FORK 198.0
END DESCRIPTION:
XS GIS Cut Line= 4
      2462824.98       13859025.        2462525.       13859075.
       2462516.1     13859069.07      2461913.91     13859087.85
#Sta/Elev= 30
  4687.9  551.23  4720.8   549.2  4728.4  547.97  4781.7   544.1  4842.5  537.95
  4850.1  535.72  4885.7   533.6  4941.3  530.16  4995.1  529.02  4995.6  528.52
  5003.5  528.52    5004  529.02  5005.8  529.63  5023.8  529.44  5035.8  530.23
  5113.9  529.86  5123.9  530.53  5133.6  530.51  5163.9   530.8  5173.9  532.21
  5183.9  531.89  5223.9  535.48  5243.9   536.3    5334  545.05  5356.2  546.18
    5474  547.24  5494.1  548.13  5534.1  551.92  5554.1  553.19  5605.2  554.01
#Mann= 5 ,-1 , 0
  4687.9    .035       0  4885.7      .1       0  4995.1     .05       0
    5004      .1       0  5133.6    .035       0
Bank Sta=4995.1,5004
XS Rating Curve= 0 ,0
Exp/Cntr=0.3,0.1

Type RM Length L Ch R = 1 ,227569  ,438,438,438
BEGIN DESCRIPTION:
SANDY FORK 197.0
END DESCRIPTION:
XS GIS Cut Line= 5
      2463075.36     13858613.89      2462860.07     13858542.71
        2462675.       13858675.      2462669.79     13858672.02
      2462061.47     13858962.84
#Sta/Elev= 30
  4541.4  549.08  4556.1  548.48  4619.1  545.77    4709  535.95  4720.8  536.68
  4740.8  535.92  4768.1   533.1  4780.6  530.16  4786.8  531.55  4795.4  530.58
  4816.2   531.8    4831  530.46  4937.9  530.27  4973.5  529.47  4982.1  528.44
  4988.3  529.06  5004.9  526.67  5005.4  526.17  5013.8  526.67  5084.3  528.23
  5157.9  528.23  5208.8  529.72  5225.9  529.02    5284  530.98  5344.9  535.64
  5367.5  539.06  5376.7  539.25    5393  540.65  5458.2  544.09  5675.9  548.11
#Mann= 6 ,-1 , 0
  4541.4     .12       0  4556.1    .035       0  5004.9    .035       0
  5013.8    .035       0  5376.7      .1       0    5393    .035       0
Bank Sta=5004.9,5013.8
XS Rating Curve= 0 ,0
Exp/Cntr=0.3,0.1

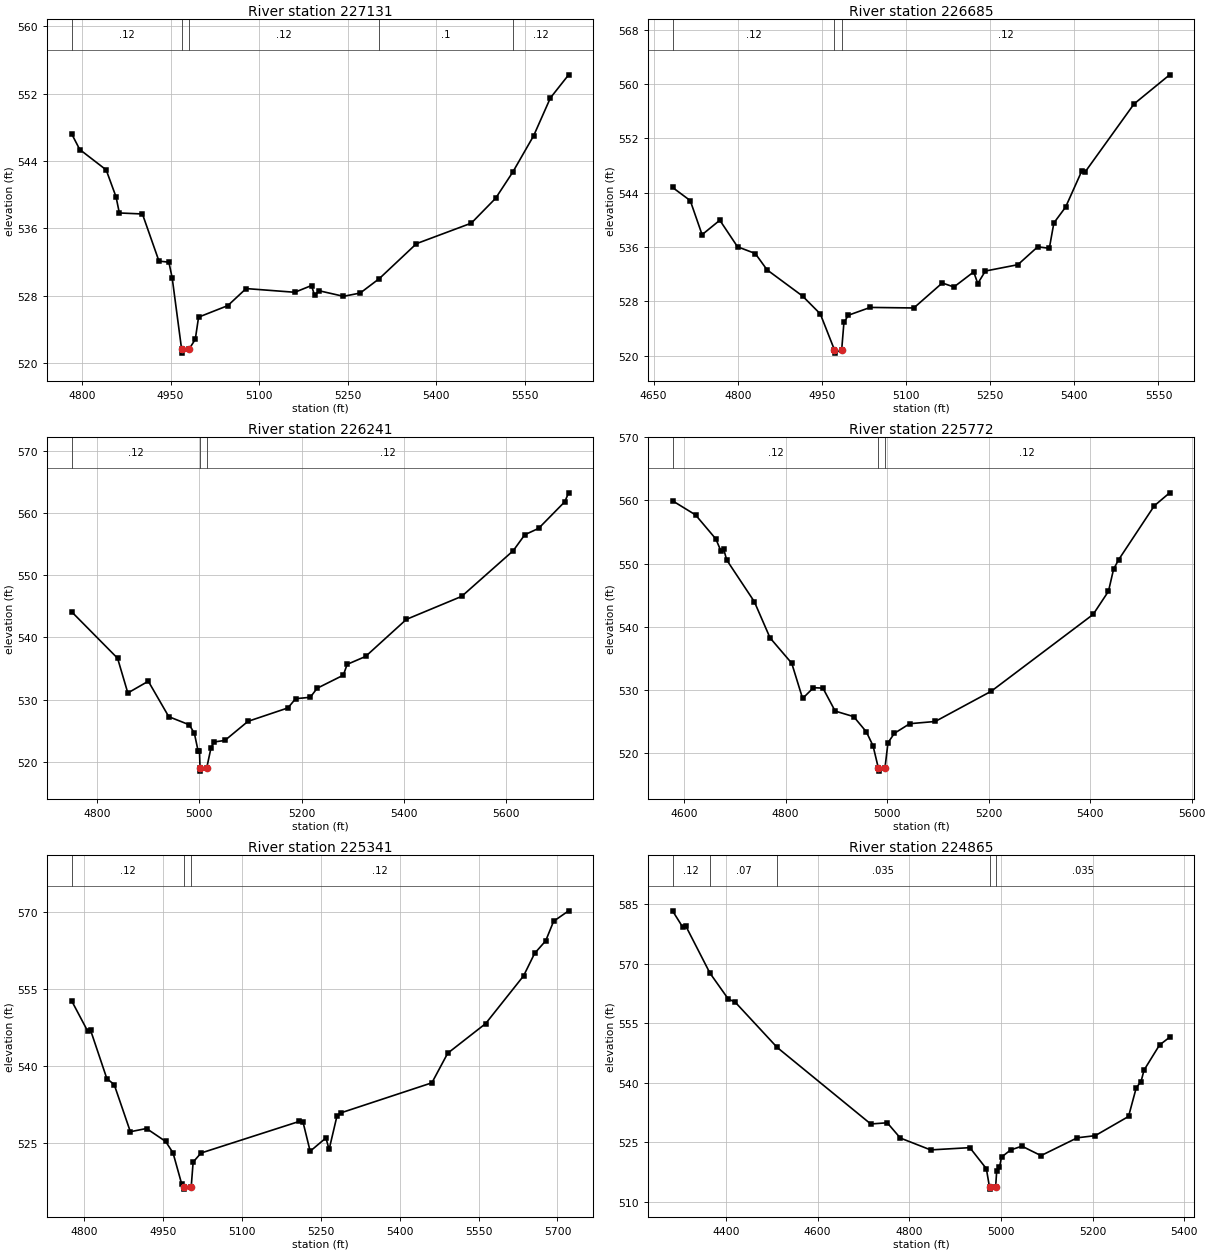
Type RM Length L Ch R = 1 ,227131  ,446,446,446
BEGIN DESCRIPTION:
SANDY FORK 196.0
END DESCRIPTION:
XS GIS Cut Line= 3
      2463024.98     13858574.96        2462925.       13858375.
      2462775.01     13857775.03
#Sta/Elev= 30
  4782.3  547.26  4796.2  545.37    4841  542.95  4857.7  539.75  4863.3  537.84
  4902.4  537.72  4930.4  532.13  4947.2     532  4952.8  530.14  4968.7  521.71
  4969.2  521.21  4981.6  521.71  4991.9  522.84  4997.5  525.48  5047.1  526.85
    5078  528.87  5160.5  528.43  5188.8  529.23    5194  528.05  5201.7  528.61
  5242.9  527.95  5271.3  528.34  5303.6  530.05  5366.6   534.2  5459.4  536.63
  5500.6  539.58  5529.7  542.69  5565.1  547.01  5593.4  551.49  5624.3  554.23
#Mann= 5 ,-1 , 0
  4782.3     .12       0  4968.7    .035       0  4981.6     .12       0
  5303.6      .1       0  5529.7     .12       0
Bank Sta=4968.7,4981.6
XS Rating Curve= 0 ,0
Exp/Cntr=0.3,0.1

Type RM Length L Ch R = 1 ,226685  ,444,444,444
BEGIN DESCRIPTION:
SANDY FORK 195.0
END DESCRIPTION:
XS GIS Cut Line= 3
      2463274.98     13858324.95        2463175.       13858025.
      2462724.97     13857674.98
#Sta/Elev= 30
  4683.6  544.76  4715.2  542.82  4736.3   537.8  4767.9  539.93  4799.5  536.02
  4831.1  535.03  4852.2  532.62  4915.5  528.76  4947.1  526.13  4972.2  520.86
  4972.7  520.36  4985.2  520.86  4989.2  524.87  4997.1  525.94    5036  527.09
  5113.8  527.01  5164.5  530.69  5185.3   530.1  5220.6  532.32  5227.8  530.61
  5241.4  532.45  5299.3  533.38  5334.6  536.01  5355.4   535.8  5363.5  539.53
  5384.4  541.86  5413.3  547.19  5419.7  547.09  5506.5  557.06  5569.9  561.34
#Mann= 3 ,-1 , 0
  4683.6     .12       0  4972.2    .035       0  4985.2     .12       0
Bank Sta=4972.2,4985.2
XS Rating Curve= 0 ,0
Exp/Cntr=0.3,0.1

Type RM Length L Ch R = 1 ,226241  ,469,469,469
BEGIN DESCRIPTION:
SANDY FORK 194.0
END DESCRIPTION:
XS GIS Cut Line= 3
        2463525.     13858225.05        2463525.       13857975.
      2463124.98     13857374.97
#Sta/Elev= 30
  4750.4  544.15  4840.4  536.66  4860.4  531.08  4900.4  532.97  4940.4  527.27
  4980.4  525.97  4990.4  524.61  4997.9  521.69  5000.4  521.69  5001.5  519.02
    5002  518.52  5014.5  519.02    5023   522.3    5029  523.21    5050  523.45
  5095.1  526.52  5173.2  528.68  5188.2  530.16  5216.8  530.39  5230.3  531.84
  5281.4  533.94  5288.9  535.68  5324.9  536.95  5404.6  542.91  5512.7  546.61
  5613.4  553.95  5635.9  556.51    5663  557.54    5714  561.81  5721.6  563.25
#Mann= 3 ,-1 , 0
  4750.4     .12       0  5001.5    .035       0  5014.5     .12       0
Bank Sta=5001.5,5014.5
XS Rating Curve= 0 ,0
Exp/Cntr=0.3,0.1

Type RM Length L Ch R = 1 ,225772  ,431,431,431
BEGIN DESCRIPTION:
SANDY FORK 193.0
END DESCRIPTION:
XS GIS Cut Line= 3
        2464075.     13858174.99        2463925.       13857775.
        2463875.     13857224.96
#Sta/Elev= 30
  4577.1  559.95  4622.5  557.71  4662.5   553.9  4672.3  552.03  4677.7  552.34
  4683.9  550.57  4738.2  543.99  4769.3  538.24    4812  534.23  4833.4  528.65
  4854.8  530.36  4873.5  530.29  4897.5  526.66    4934  525.78  4958.9  523.38
  4972.2  521.16  4982.6  517.65  4983.1  517.15  4995.7  517.65  5001.6  521.64
  5014.3  523.14  5044.5  524.66  5094.7  525.01  5205.1   529.8  5405.9  541.96
  5436.1  545.63  5446.1  549.11  5456.1  550.62  5526.4  559.16  5556.6  561.21
#Mann= 3 ,-1 , 0
  4577.1     .12       0  4982.6    .035       0  4995.7     .12       0
Bank Sta=4982.6,4995.7
XS Rating Curve= 0 ,0
Exp/Cntr=0.3,0.1

Type RM Length L Ch R = 1 ,225341  ,476,476,476
BEGIN DESCRIPTION:
SANDY FORK 192.0
END DESCRIPTION:
XS GIS Cut Line= 3
        2464425.     13857974.99        2464325.       13857775.
      2463925.01     13857175.01
#Sta/Elev= 30
  4776.5  552.78  4807.2  546.82  4812.8  546.97  4843.6  537.55  4857.6  536.38
  4888.3  527.17    4919   527.8  4955.4  525.27  4969.4  523.04  4986.1  516.87
  4990.7  516.46  4991.2  515.96    5004  516.46  5007.6  521.24  5022.6  523.01
  5208.9  529.17  5216.4  529.06    5230  523.36    5260  525.96    5266   523.7
    5281  530.26  5288.5  530.86  5461.3  536.72  5491.4   542.5  5563.5  548.29
  5635.6  557.61  5656.6  562.01  5677.6  564.45  5692.7  568.28  5721.2  570.31
#Mann= 3 ,-1 , 0
  4776.5     .12       0  4990.7    .035       0    5004     .12       0
Bank Sta=4990.7,5004
XS Rating Curve= 0 ,0
Exp/Cntr=0.3,0.1

Type RM Length L Ch R = 1 ,224865  ,448,448,448
BEGIN DESCRIPTION:
SANDY FORK 191.0
END DESCRIPTION:
XS GIS Cut Line= 3
        2465125.       13858175.        2464725.       13857575.
        2464625.     13857225.01
#Sta/Elev= 30
  4283.2  583.33  4305.7  579.17  4311.7   579.6  4364.9  567.62  4404.9  561.09
  4419.9  560.31  4511.7  548.87  4715.9  529.58  4751.9  529.88  4780.5  526.03
  4846.6  523.04  4932.2  523.61  4968.2  518.31  4975.1  513.65  4975.6  513.15
  4988.5  513.65  4990.8  517.78  4996.8  518.62  5001.3  521.22  5021.2  523.03
  5045.9  523.98  5087.5   521.6  5166.8   526.1  5205.8  526.63  5278.6  531.48
  5295.5  538.75  5305.9  540.28  5312.4  543.16  5346.2  549.49  5368.3  551.45
#Mann= 5 ,-1 , 0
  4283.2     .12       0  4364.9     .07       0  4511.7    .035       0
  4975.1    .035       0  4988.5    .035       0
Bank Sta=4975.1,4988.5
XS Rating Curve= 0 ,0
Exp/Cntr=0.3,0.1