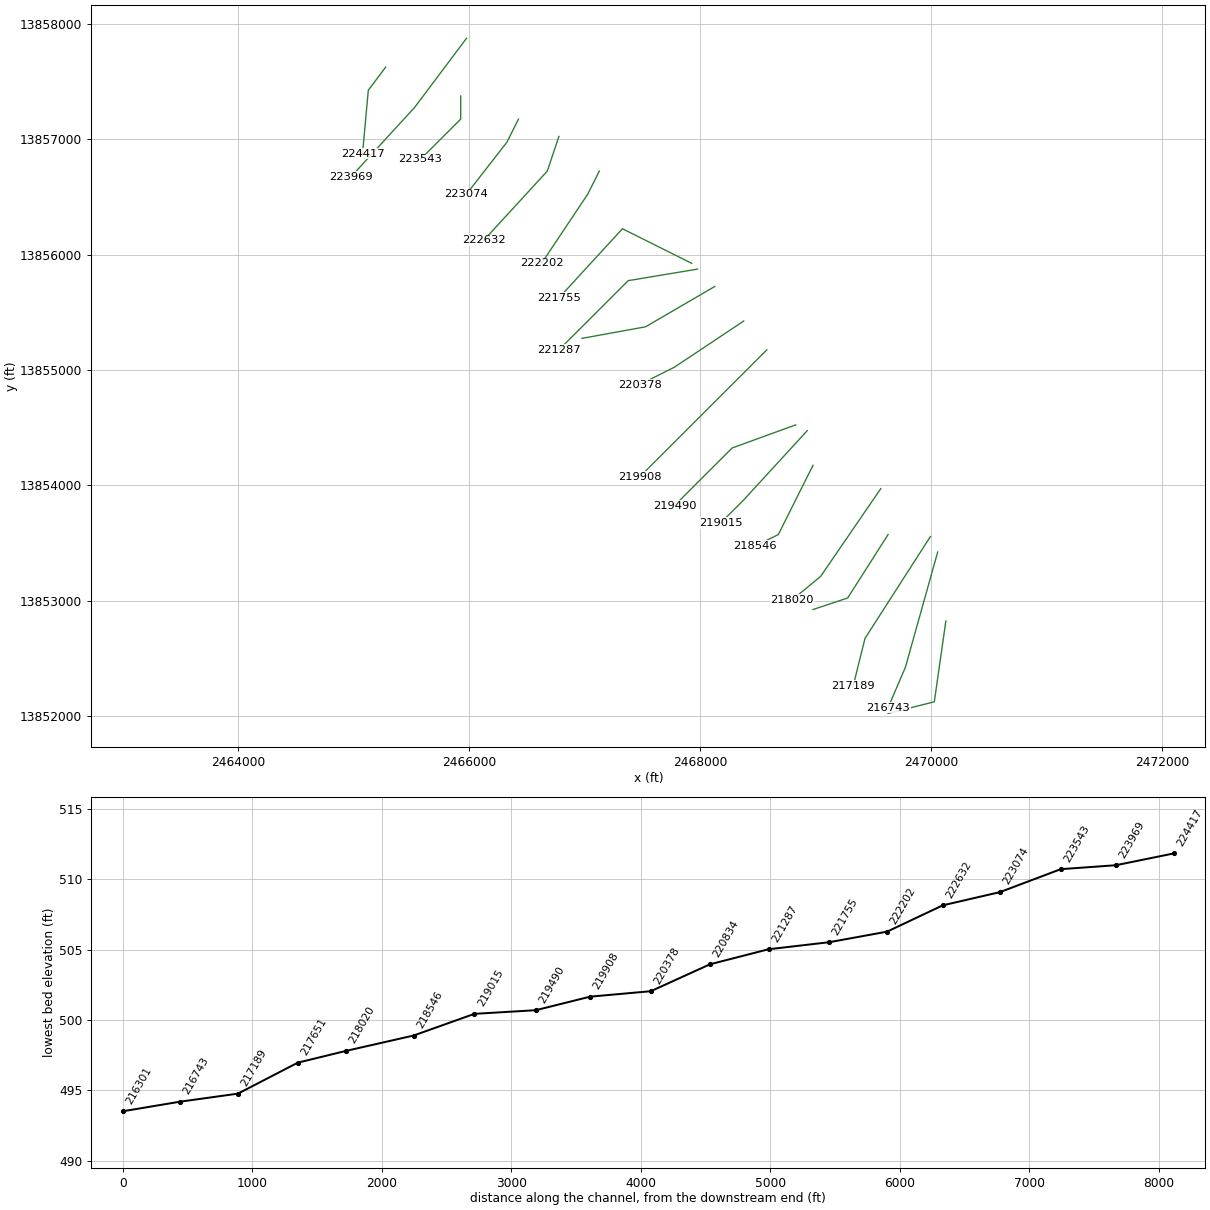
HEC-RAS study SANDY FORK.prj: SANDY FORK Base Level Engineering

--- SANDY FORK.g01 (geometry) --- (continued)

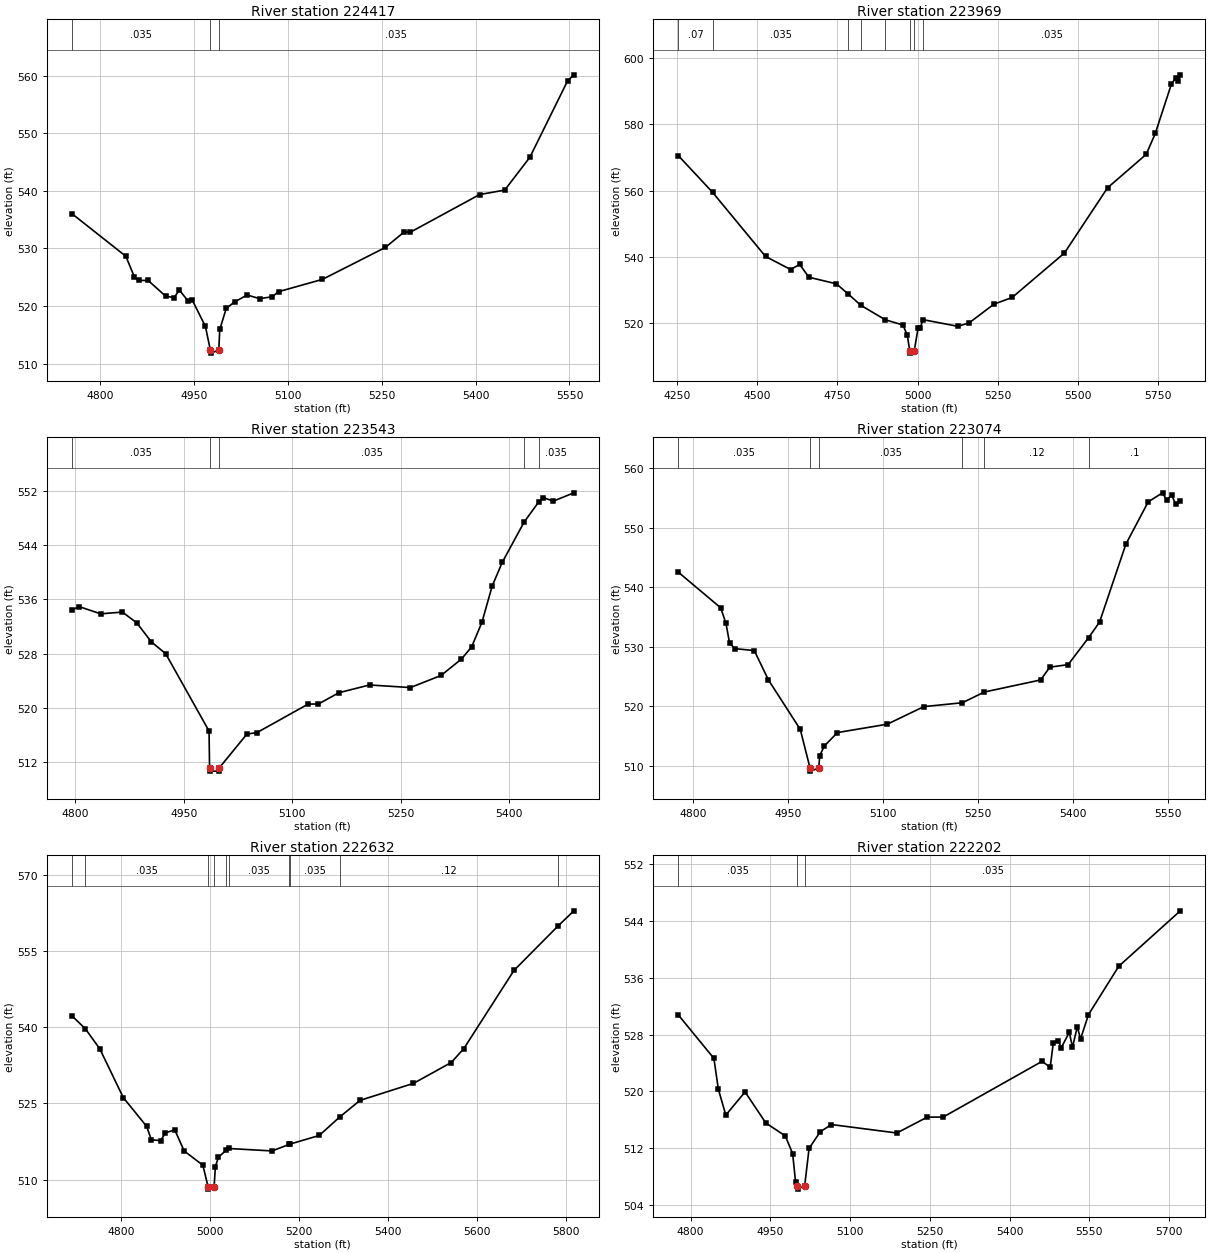
Type RM Length L Ch R = 1 ,224417  ,448,448,448
BEGIN DESCRIPTION:
SANDY FORK 190.0
END DESCRIPTION:
XS GIS Cut Line= 3
      2465275.02     13857625.02        2465125.       13857425.
        2465075.       13856875.
#Sta/Elev= 30
  4754.7  536.07  4841.2  528.64  4854.7  525.07    4862  524.45  4876.6  524.46
  4904.7  521.72  4918.3  521.48  4926.6  522.77  4941.2  520.81  4947.4  521.01
  4968.3  516.46  4976.2  512.33  4976.7  511.83  4989.6  512.33  4991.2  515.94
  5001.6  519.61  5014.8  520.71  5034.9  521.93  5054.9  521.29    5075  521.62
  5085.1   522.5  5155.3  524.64  5255.8  530.18  5285.9  532.88  5295.9  532.84
  5406.4  539.37  5446.5  540.14  5486.7  545.84    5547  559.11    5557  560.16
#Mann= 3 ,-1 , 0
  4754.7    .035       0  4976.2    .035       0  4989.6    .035       0
Bank Sta=4976.2,4989.6
XS Rating Curve= 0 ,0
Exp/Cntr=0.3,0.1

Type RM Length L Ch R = 1 ,223969  ,426,426,426
BEGIN DESCRIPTION:
SANDY FORK 189.0
END DESCRIPTION:
XS GIS Cut Line= 3
        2465975.       13857875.        2465525.       13857275.
      2464975.02     13856675.03
#Sta/Elev= 30
  4254.3  570.61  4361.2  559.51  4526.2  540.16  4604.3  536.22  4632.4  537.75
  4661.6  533.88    4747   531.9  4784.1  528.79  4823.1  525.42  4899.1  521.05
  4954.3  519.48  4967.8  516.38  4975.7  511.49  4976.2  510.99  4989.2  511.49
  5001.2  518.46  5007.7  518.46  5016.6  521.09  5124.8  519.09    5160  520.08
  5237.7  525.77  5294.4  527.78  5457.2  541.19  5591.6  560.87  5711.9  570.96
  5740.2  577.26  5790.2  592.11  5804.4  594.04  5811.1   593.1  5818.2  594.96
#Mann= 8 ,-1 , 0
  4254.3     .07       0  4361.2    .035       0  4784.1     .12       0
  4823.1    .035       0  4899.1     .12       0  4975.7     .05       0
  4989.2     .12       0  5016.6    .035       0
Bank Sta=4975.7,4989.2
XS Rating Curve= 0 ,0
Exp/Cntr=0.3,0.1

Type RM Length L Ch R = 1 ,223543  ,469,469,469
BEGIN DESCRIPTION:
SANDY FORK 188.0
END DESCRIPTION:
XS GIS Cut Line= 3
        2465925.     13857374.96        2465925.       13857175.
      2465575.02     13856825.02
#Sta/Elev= 30
    4795  534.41    4805  534.93    4835  533.86    4865  534.12    4885  532.53
    4905  529.75    4925  527.99    4985  516.61  4985.7  511.21  4986.2  510.71
  4998.8  510.71  4999.3  511.21  5037.4  516.16  5051.5  516.39  5122.2  520.58
  5136.4  520.59  5164.7  522.25  5207.1  523.39  5263.7  523.01  5306.1  524.79
  5334.4  527.21  5348.5  529.01  5362.7  532.62  5376.8  537.93  5390.9  541.46
  5421.1  547.37  5441.5  550.36  5447.5  550.96  5461.6  550.45  5489.9  551.67
#Mann= 5 ,-1 , 0
    4795    .035       0  4985.7    .035       0  4999.3    .035       0
  5421.1     .12       0  5441.5    .035       0
Bank Sta=4985.7,4999.3
XS Rating Curve= 0 ,0
Exp/Cntr=0.3,0.1

Type RM Length L Ch R = 1 ,223074  ,442,442,442
BEGIN DESCRIPTION:
SANDY FORK 187.0
END DESCRIPTION:
XS GIS Cut Line= 3
        2466425.       13857175.        2466325.       13856975.
      2465974.99     13856524.99
#Sta/Elev= 30
  4776.4  542.52  4843.5  536.52  4851.9  533.89  4857.5  530.63  4865.8  529.66
  4896.6  529.34  4918.9  524.42  4969.3  516.09  4984.8  509.58  4985.3  509.08
  4998.5  509.58    5000  511.63  5007.2  513.28  5028.1  515.56  5106.8  516.96
  5164.7  519.92  5225.6  520.57  5260.3  522.37  5349.3   524.4  5363.8  526.55
  5392.7  526.97  5425.1   531.5  5442.5  534.14  5484.1  547.23  5519.4  554.33
    5542  555.84  5548.4  554.62  5556.5  555.42  5562.9  553.91  5570.1  554.42
#Mann= 6 ,-1 , 0
  4776.4    .035       0  4984.8    .035       0  4998.5    .035       0
  5225.6      .1       0  5260.3     .12       0  5425.1      .1       0
Bank Sta=4984.8,4998.5
XS Rating Curve= 0 ,0
Exp/Cntr=0.3,0.1

Type RM Length L Ch R = 1 ,222632  ,430,430,430
BEGIN DESCRIPTION:
SANDY FORK 186.0
END DESCRIPTION:
XS GIS Cut Line= 3
      2466774.99     13857024.96        2466675.       13856725.
      2466125.02     13856125.02
#Sta/Elev= 30
  4688.6  542.25  4719.2  539.67  4751.8  535.71  4804.5  526.15  4857.2  520.47
  4867.8  517.82  4888.8   517.7  4899.4  519.22  4920.5  519.79  4941.5  515.65
  4983.7  512.84  4995.3  508.64  4995.8  508.14    5009  508.64  5011.9  512.57
  5018.7  514.43  5036.7  515.82  5042.1  516.13  5139.5  515.65  5178.1  516.94
  5179.1  516.98  5245.6  518.69  5291.6  522.32  5337.4  525.59  5457.7  528.94
  5542.8  533.04  5571.1  535.78    5684  551.16  5782.8  559.86  5818.7  562.87
#Mann= 10 ,-1 , 0
  4688.6     .07       0  4719.2    .035       0  4995.3    .035       0
    5009    .035       0  5036.7     .12       0  5042.1    .035       0
  5178.1      .1       0  5179.1    .035       0  5291.6     .12       0
  5782.8    .035       0
Bank Sta=4995.3,5009
XS Rating Curve= 0 ,0
Exp/Cntr=0.3,0.1

Type RM Length L Ch R = 1 ,222202  ,447,447,447
BEGIN DESCRIPTION:
SANDY FORK 185.0
END DESCRIPTION:
XS GIS Cut Line= 3
      2467125.02     13856725.03        2467025.       13856525.
      2466624.97     13855924.96
#Sta/Elev= 30
  4776.6  530.77  4843.7  524.65  4852.1  520.31  4866.1  516.68  4902.4  519.93
  4941.5  515.56  4977.9  513.76  4991.9  511.27  4997.4  507.27  5000.9  506.77
  5001.4  506.27  5014.6  506.77  5022.8  511.99  5043.8  514.33  5064.8  515.35
    5188  514.16  5245.1  516.39  5275.2   516.4  5461.5  524.24  5476.5  523.38
  5482.5  526.88  5491.5  527.13  5497.5  526.16  5512.5  528.32  5518.5  526.21
  5527.6  529.11  5533.6  527.36  5548.6   530.8  5605.7  537.61  5721.4  545.39
#Mann= 3 ,-1 , 0
  4776.6    .035       0  5000.9    .035       0  5014.6    .035       0
Bank Sta=5000.9,5014.6
XS Rating Curve= 0 ,0
Exp/Cntr=0.3,0.1

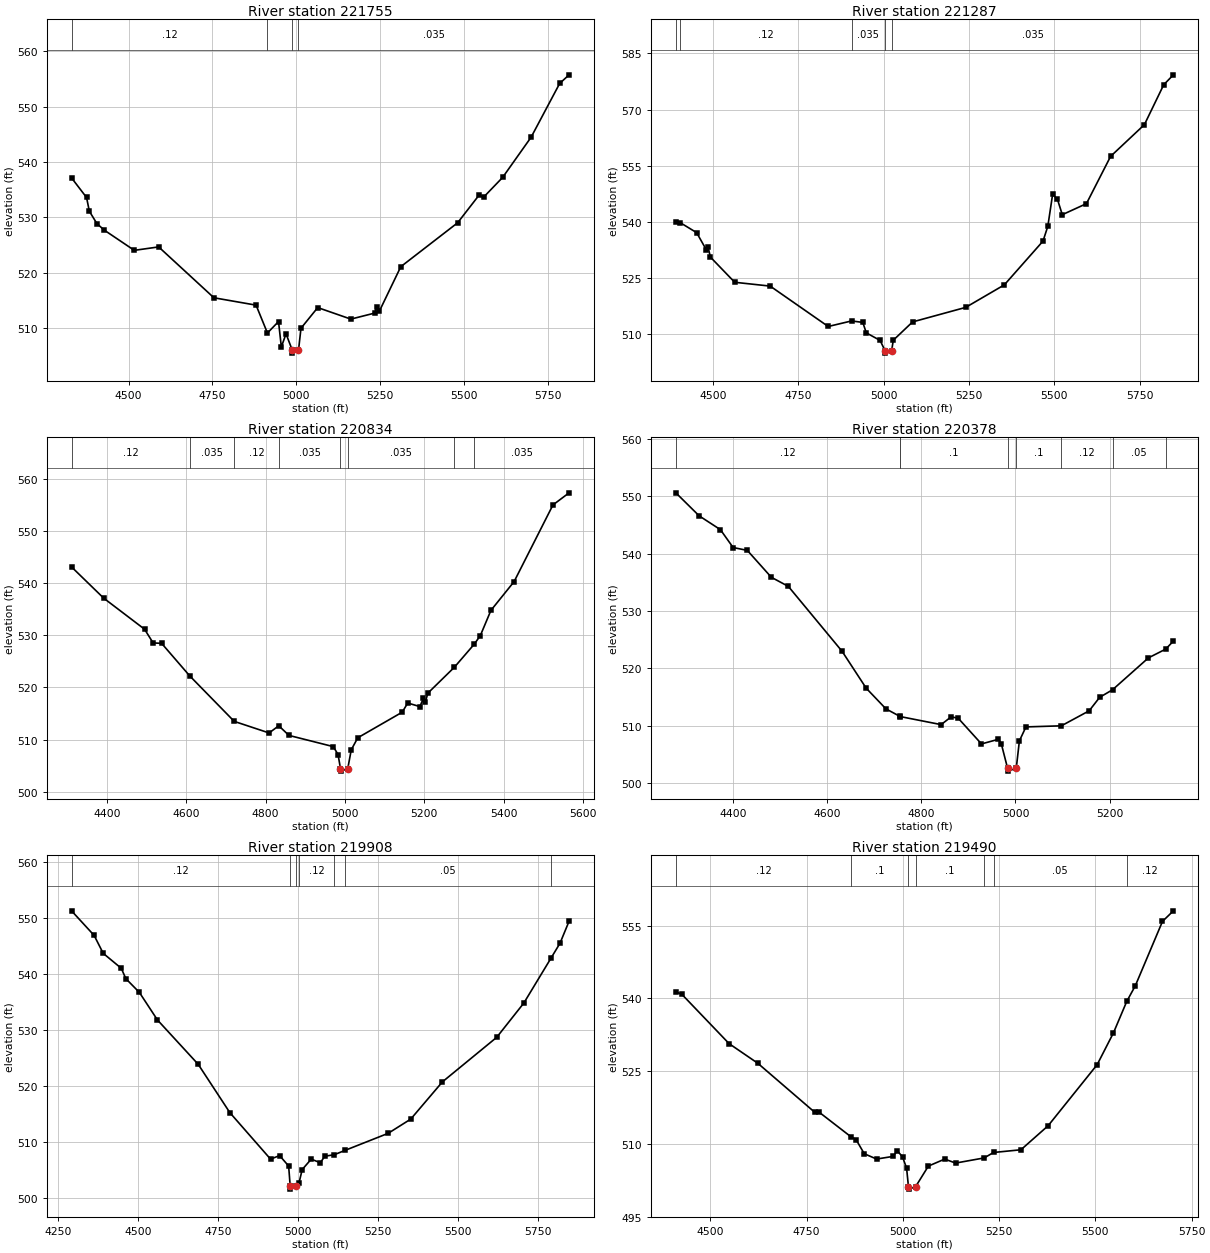
Type RM Length L Ch R = 1 ,221755  ,468,468,468
BEGIN DESCRIPTION:
SANDY FORK 184.0
END DESCRIPTION:
XS GIS Cut Line= 3
      2467925.03     13855924.98        2467325.       13856225.
        2466775.       13855625.
#Sta/Elev= 30
  4329.5  537.15  4374.3  533.61  4382.6  531.14    4405  528.91  4427.4  527.71
  4516.8  524.07  4589.5  524.69  4754.4  515.51  4880.2  514.18  4914.1  509.15
  4947.2  511.22  4955.6  506.63  4969.6  509.01  4988.4  506.02  4988.9  505.52
  5006.8  506.02  5014.2  510.01  5064.2  513.74  5163.1  511.66  5233.7  512.74
  5241.1  513.91  5247.9  513.06  5312.1  521.12  5481.6  529.04  5545.1  533.99
  5559.3  533.67  5616.1  537.24  5701.1   544.5  5786.2  554.19  5814.3  555.75
#Mann= 4 ,-1 , 0
  4329.5     .12       0  4914.1    .035       0  4988.4    .035       0
  5006.8    .035       0
Bank Sta=4988.4,5006.8
XS Rating Curve= 0 ,0
Exp/Cntr=0.3,0.1

Type RM Length L Ch R = 1 ,221287  ,453,453,453
BEGIN DESCRIPTION:
SANDY FORK 183.0
END DESCRIPTION:
XS GIS Cut Line= 3
      2467974.99       13855875.        2467375.       13855775.
        2466775.       13855175.
#Sta/Elev= 30
  4391.6  540.14  4404.1  539.86  4452.4  537.18  4480.3  532.67  4485.4  533.42
    4493  530.63  4563.9  523.93  4667.8  522.91  4837.7  512.13    4906  513.61
    4939  513.22  4949.2  510.43  4989.7  508.41  5004.8  505.52  5005.3  505.02
  5023.2  505.52  5028.2  508.46  5084.7  513.35  5240.3  517.23  5353.4  523.24
  5466.6  534.92  5480.7  538.86  5494.8  547.41    5509  546.04  5523.1  541.97
  5593.8  544.92  5664.5  557.53  5763.5     566  5820.1  576.66  5848.4   579.3
#Mann= 5 ,-1 , 0
  4391.6    .035       0  4404.1     .12       0    4906    .035       0
  5004.8    .035       0  5023.2    .035       0
Bank Sta=5004.8,5023.2
XS Rating Curve= 0 ,0
Exp/Cntr=0.3,0.1

Type RM Length L Ch R = 1 ,220834  ,456,456,456
BEGIN DESCRIPTION:
SANDY FORK 182.0
END DESCRIPTION:
XS GIS Cut Line= 3
        2468125.       13855725.        2467525.       13855375.
      2466975.04     13855275.01
#Sta/Elev= 30
  4311.3  543.11  4392.3  537.12  4495.3  531.16  4516.8  528.54  4538.3  528.45
    4609  522.22  4721.2  513.49  4809.1  511.27  4833.4  512.65  4859.1   510.8
  4970.8  508.65  4982.8  507.13  4988.9  504.45  4989.4  503.95  5007.3  504.45
  5016.1  508.05  5032.6  510.35  5144.4  515.25  5158.4  517.01  5188.9  516.33
  5197.8  517.89  5202.8  517.24  5209.2  518.91  5276.1  523.89  5325.7  528.27
  5341.3  529.94    5368  534.78  5426.5  540.31  5524.3     555  5564.9  557.32
#Mann= 8 ,-1 , 0
  4311.3     .12       0    4609    .035       0  4721.2     .12       0
  4833.4    .035       0  4988.9    .035       0  5007.3    .035       0
  5276.1      .1       0  5325.7    .035       0
Bank Sta=4988.9,5007.3
XS Rating Curve= 0 ,0
Exp/Cntr=0.3,0.1

Type RM Length L Ch R = 1 ,220378  ,470,470,470
BEGIN DESCRIPTION:
SANDY FORK 181.0
END DESCRIPTION:
XS GIS Cut Line= 3
      2468374.96     13855424.97        2467775.       13855025.
      2467474.98     13854874.99
#Sta/Elev= 30
  4278.9  550.63  4328.4  546.61  4373.5   544.2  4400.5  541.08  4430.6  540.58
  4481.7  535.88  4517.7   534.3  4631.9  522.96    4683  516.53    4725  512.91
  4754.4  511.61  4755.7  511.56  4842.2  510.16  4863.3  511.51  4878.3  511.29
  4927.9  506.79  4963.9   507.6  4969.9  506.84  4983.3  502.54  4983.8  502.04
  5001.7  502.54  5008.4  507.33  5022.3  509.76  5097.5  509.95  5156.5  512.57
  5178.9  514.93  5206.1  516.24  5282.3  521.81  5319.2  523.35  5335.4  524.75
#Mann= 8 ,-1 , 0
  4278.9     .12       0  4754.4     .07       0  4755.7      .1       0
  4983.3     .05       0  5001.7      .1       0  5097.5     .12       0
  5206.1     .05       0  5319.2    .035       0
Bank Sta=4983.3,5001.7
XS Rating Curve= 0 ,0
Exp/Cntr=0.3,0.1

Type RM Length L Ch R = 1 ,219908  ,418,418,418
BEGIN DESCRIPTION:
SANDY FORK 180.0
END DESCRIPTION:
XS GIS Cut Line= 3
      2468574.99     13855174.99        2468075.       13854675.
      2467475.01     13854075.01
#Sta/Elev= 30
  4292.9  551.28  4363.6  546.89  4391.9   543.7  4448.4  541.03  4462.6  539.19
    4505  536.73  4561.6  531.81  4688.9  523.91  4787.9  515.29  4915.1     507
  4943.4  507.63  4971.7  505.77  4976.6  502.15  4977.1  501.65  4995.1  502.15
  5004.3   502.8  5014.1  505.15  5042.4     507  5070.7  506.35  5084.8  507.52
  5114.1  507.78  5147.5  508.55  5282.8   511.6  5353.5  514.14  5452.5  520.78
  5622.2  528.72  5707.1  534.84  5791.3  542.78  5820.2  545.51  5848.5  549.43
#Mann= 7 ,-1 , 0
  4292.9     .12       0  4976.6     .05       0  4995.1     .12       0
  5004.3     .12       0  5114.1     .07       0  5147.5     .05       0
  5791.3     .12       0
Bank Sta=4976.6,4995.1
XS Rating Curve= 0 ,0
Exp/Cntr=0.3,0.1

Type RM Length L Ch R = 1 ,219490  ,475,475,475
BEGIN DESCRIPTION:
SANDY FORK 179.0
END DESCRIPTION:
XS GIS Cut Line= 3
      2468824.96     13854524.99        2468275.       13854325.
        2467775.       13853825.
#Sta/Elev= 30
  4410.3  541.33  4425.6  540.86  4548.6  530.67  4623.1  526.63  4771.4   516.5
  4782.7  516.53  4865.7  511.44  4878.4  510.89  4899.7  507.98  4931.7  506.89
  4974.2  507.43  4985.5  508.59    4999  507.35  5009.6  505.01  5014.5  501.19
    5015  500.69    5033  501.19  5066.2  505.44  5108.6  506.88  5136.9  506.06
  5211.1  507.12  5235.4  508.24  5306.6   508.8  5377.3  513.76  5504.6  526.34
    5547  532.91  5581.6   539.4  5603.6  542.58  5674.3  555.87  5702.6  558.04
#Mann= 7 ,-1 , 0
  4410.3     .12       0  4865.7      .1       0  5014.5     .05       0
    5033      .1       0  5211.1     .07       0  5235.4     .05       0
  5581.6     .12       0
Bank Sta=5014.5,5033
XS Rating Curve= 0 ,0
Exp/Cntr=0.3,0.1

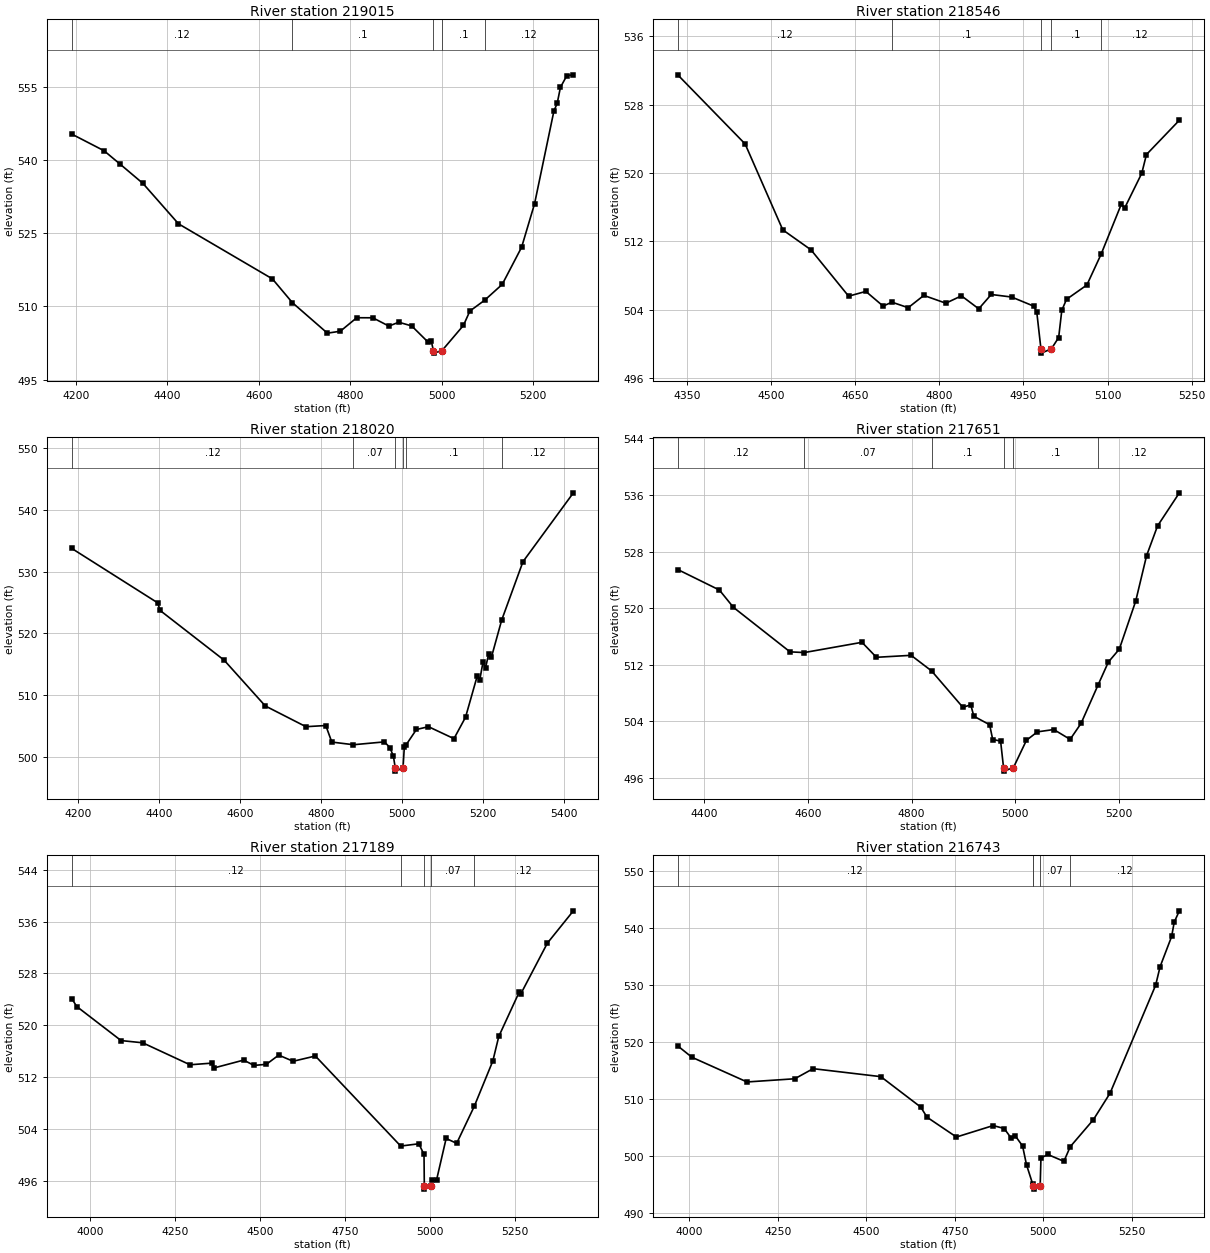
Type RM Length L Ch R = 1 ,219015  ,469,469,469
BEGIN DESCRIPTION:
SANDY FORK 178.0
END DESCRIPTION:
XS GIS Cut Line= 3
      2468924.99     13854474.99        2468375.       13853875.
      2468174.98     13853674.98
#Sta/Elev= 30
  4191.2   545.3  4261.8  541.89  4297.6  539.09  4346.9  535.19  4424.6  526.92
  4629.9  515.64  4673.6  510.77  4750.2  504.52  4778.5  504.92  4814.3  507.68
  4849.4  507.67  4884.6  505.97  4906.2  506.76  4934.5     506  4969.7  502.74
  4977.1  502.98    4982  500.93  4982.5  500.43  5000.6  500.93  5047.6  506.11
  5061.7  509.05  5093.9  511.26  5132.4  514.51  5174.8  522.12  5203.1  531.02
  5245.5  550.06  5252.6  551.59  5259.7  554.88  5273.8  557.29    5288  557.44
#Mann= 5 ,-1 , 0
  4191.2     .12       0  4673.6      .1       0    4982     .05       0
  5000.6      .1       0  5093.9     .12       0
Bank Sta=4982,5000.6
XS Rating Curve= 0 ,0
Exp/Cntr=0.3,0.1

Type RM Length L Ch R = 1 ,218546  ,526,526,526
BEGIN DESCRIPTION:
SANDY FORK 177.0
END DESCRIPTION:
XS GIS Cut Line= 3
      2468975.01     13854175.02        2468675.       13853575.
      2468475.04     13853475.02
#Sta/Elev= 30
  4333.6  531.49  4453.8  523.39  4520.9  513.33  4571.2  510.99  4638.3  505.56
    4669  506.12  4699.8   504.4  4715.5  504.86  4744.5  504.21  4772.4  505.65
  4811.6  504.74  4839.5   505.6  4870.3  504.08  4892.6  505.76    4929  505.46
  4968.1   504.4  4973.7  503.74  4981.2  499.39  4981.7  498.89  4999.8  499.39
  5012.8  500.72  5018.4   503.9  5026.8  505.19  5063.1  506.87  5088.3  510.45
  5124.6  516.35  5130.2  515.85    5161  519.96  5169.3  522.15    5228  526.17
#Mann= 5 ,-1 , 0
  4333.6     .12       0  4715.5      .1       0  4981.2     .05       0
  4999.8      .1       0  5088.3     .12       0
Bank Sta=4981.2,4999.8
XS Rating Curve= 0 ,0
Exp/Cntr=0.3,0.1

Type RM Length L Ch R = 1 ,218020  ,369,369,369
BEGIN DESCRIPTION:
E20718
END DESCRIPTION:
XS GIS Cut Line= 3
      2469561.79     13853972.63      2469040.93     13853212.46
       2468795.6     13853009.18
#Sta/Elev= 30
  4183.4  533.73  4395.8  524.95  4401.8  523.72  4560.2  515.69  4661.8  508.31
  4762.4  504.96  4811.4  505.15  4826.3  502.48  4879.9  502.05  4956.4  502.51
  4969.8   501.6  4978.6  500.19  4983.2  498.29  4983.7  497.79  5002.3  498.29
  5005.6  501.69  5010.5  502.08  5035.5  504.51  5065.3  504.96  5128.3  503.03
  5156.9  506.49  5185.6  513.09  5192.1  512.53  5199.9  515.32  5206.4  514.51
  5214.2  516.69  5220.7  516.13  5246.3  522.17  5298.9  531.59  5423.5   542.7
#Mann= 6 ,-1 , 0
  4183.4     .12       0  4879.9     .07       0  4983.2     .05       0
  5002.3     .07       0  5010.5      .1       0  5246.3     .12       0
Bank Sta=4983.2,5002.3
XS Rating Curve= 0 ,0
Exp/Cntr=0.3,0.1

Type RM Length L Ch R = 1 ,217651  ,462,462,462
BEGIN DESCRIPTION:
SANDY FORK 176.0
END DESCRIPTION:
XS GIS Cut Line= 3
      2469624.98     13853574.98        2469275.       13853025.
      2468975.02     13852925.01
#Sta/Elev= 30
  4348.8  525.46  4429.2  522.56  4456.3  520.11  4565.5  513.82    4593  513.72
  4704.4  515.17  4732.3  513.05  4799.2  513.33  4838.8  511.12  4899.1  505.98
  4914.3  506.33  4920.3  504.72  4950.7  503.52  4956.7  501.43  4971.9  501.21
  4977.6  497.46  4978.1  496.96  4996.7  497.46  5021.8  501.32  5042.9  502.51
  5074.5  502.84  5106.1  501.45  5127.2  503.71  5159.6  509.07  5179.9  512.38
    5201   514.2  5232.6  520.98  5253.7  527.43  5274.8  531.62  5316.9   536.3
#Mann= 6 ,-1 , 0
  4348.8     .12       0    4593     .07       0  4838.8      .1       0
  4977.6     .05       0  4996.7      .1       0  5159.6     .12       0
Bank Sta=4977.6,4996.7
XS Rating Curve= 0 ,0
Exp/Cntr=0.3,0.1

Type RM Length L Ch R = 1 ,217189  ,446,446,446
BEGIN DESCRIPTION:
SANDY FORK 175.0
END DESCRIPTION:
XS GIS Cut Line= 3
      2469991.18     13853557.36        2469425.       13852675.
      2469322.49     13852262.23
#Sta/Elev= 30
  3947.1  524.13  3961.8  522.91    4092  517.66  4155.4  517.32  4294.5  513.93
  4358.2  514.18  4365.8  513.45  4452.1  514.65  4482.5  513.83  4518.8     514
  4555.1  515.42  4597.4  514.47  4662.8  515.28  4913.5   501.4  4966.8  501.75
    4982   500.1  4982.9  495.26  4983.4  494.76  5002.2  495.26  5005.8  496.13
  5018.7  496.14    5047  502.57  5077.9  501.82  5129.4   507.5  5184.2  514.52
  5201.6  518.29  5261.7  525.14  5266.9  524.91  5344.4  532.68  5420.8  537.66
#Mann= 5 ,-1 , 0
  3947.1     .12       0  4913.5     .07       0  4982.9     .05       0
  5002.2     .07       0  5129.4     .12       0
Bank Sta=4982.9,5002.2
XS Rating Curve= 0 ,0
Exp/Cntr=0.3,0.1

Type RM Length L Ch R = 1 ,216743  ,442,442,442
BEGIN DESCRIPTION:
SANDY FORK 174.0
END DESCRIPTION:
XS GIS Cut Line= 3
      2470054.53     13853423.59        2469775.       13852425.
      2469624.98     13852074.96
#Sta/Elev= 30
    3967  519.29  4007.1   517.3  4162.8  512.97  4297.8  513.53  4349.7   515.3
  4541.1   513.9  4653.8  508.57  4671.7  506.79  4754.7  503.32  4858.6  505.33
  4889.7  504.81  4908.3  503.23  4920.9  503.54  4941.7  501.75  4952.8  498.45
  4969.9  495.15  4972.1  494.69  4972.6  494.19  4991.4  494.69  4993.6  499.65
    5013  500.26  5058.4  499.06  5076.5  501.63  5141.8  506.36  5188.9     511
  5317.7  529.91  5330.4  533.18    5363  538.47  5370.3  540.98  5384.8  542.96
#Mann= 5 ,-1 , 0
    3967     .12       0  4969.9     .07       0  4972.1     .05       0
  4991.4     .07       0  5076.5     .12       0
Bank Sta=4972.1,4991.4
XS Rating Curve= 0 ,0
Exp/Cntr=0.3,0.1

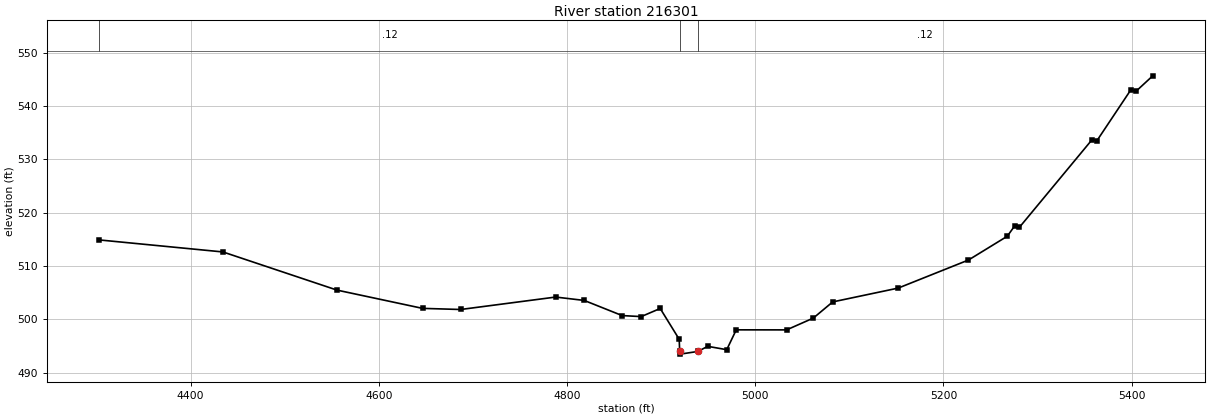
Type RM Length L Ch R = 1 ,216301  ,469,469,469
BEGIN DESCRIPTION:
SANDY FORK 173.0
END DESCRIPTION:
XS GIS Cut Line= 3
        2470125.     13852825.02        2470025.       13852125.
      2469625.04     13852025.01
#Sta/Elev= 30
    4303   514.9  4434.3  512.65  4555.6   505.5  4646.5  502.08  4686.9  501.87
  4787.9   504.2  4818.2  503.57  4858.6  500.73  4878.8  500.54    4899  502.06
  4919.2  496.29  4919.7  494.01  4920.2  493.51    4939  494.01  4949.5  494.97
  4969.7  494.34  4979.8  498.06  5033.3  498.05  5061.7  500.26  5082.3  503.29
  5151.9  505.88  5226.6  511.14  5267.8  515.59  5275.6  517.51  5280.7  517.26
    5358   533.7  5363.2  533.52  5399.2  543.04  5404.4  542.71  5422.4  545.64
#Mann= 3 ,-1 , 0
    4303     .12       0  4919.7     .05       0    4939     .12       0
Bank Sta=4919.7,4939
XS Rating Curve= 0 ,0
Exp/Cntr=0.3,0.1