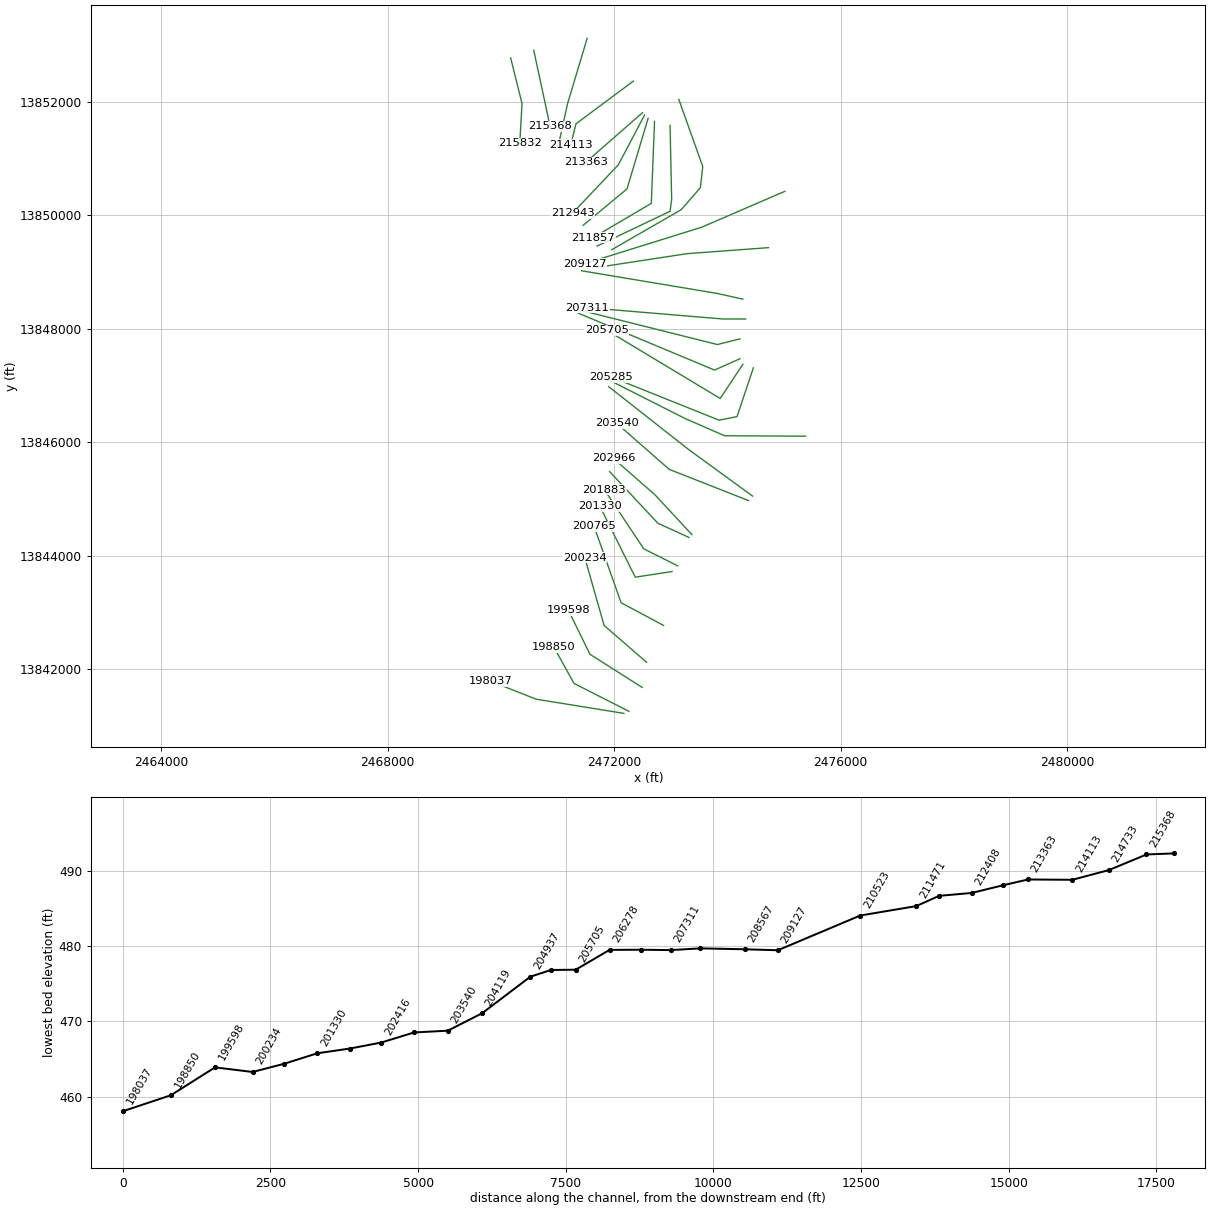
HEC-RAS study SANDY FORK.prj: SANDY FORK Base Level Engineering

--- SANDY FORK.g01 (geometry) --- (continued)

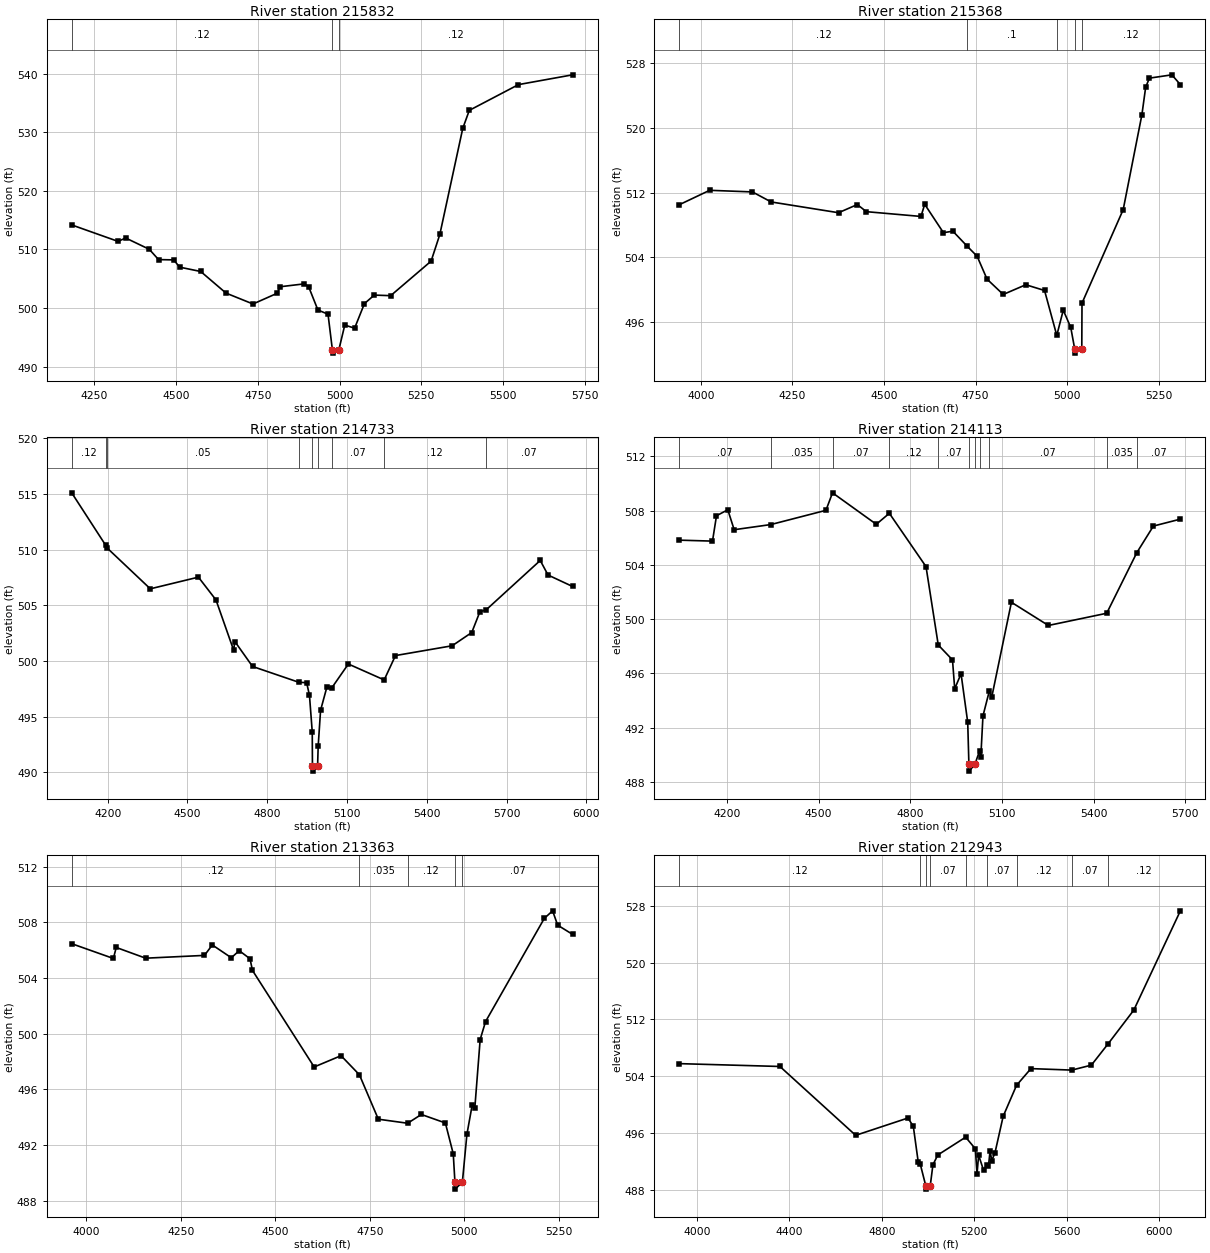
Type RM Length L Ch R = 1 ,215832  ,464,464,464
BEGIN DESCRIPTION:
SANDY FORK 172.0
END DESCRIPTION:
XS GIS Cut Line= 3
        2470175.     13852775.01        2470375.       13851975.
       2470336.1      13851269.8
#Sta/Elev= 30
  4181.3  514.19    4323  511.38  4346.2  511.96  4418.4  510.03  4446.7  508.27
  4493.1  508.22  4511.2  506.98  4575.6  506.24  4652.9  502.55  4735.4  500.69
  4810.1  502.54  4817.8  503.63  4892.5  504.13  4905.4  503.65  4933.8  499.66
  4964.7  498.95  4978.2   492.8  4978.7   492.3  4997.5   492.8  5015.9  497.09
    5046  496.56    5076  500.76  5106.1  502.21  5156.2  502.11  5279.8  508.01
  5306.4  512.56  5376.5  530.67  5396.5  533.75  5546.8  538.15  5712.2  539.82
#Mann= 3 ,-1 , 0
  4181.3     .12       0  4978.2     .05       0  4997.5     .12       0
Bank Sta=4978.2,4997.5
XS Rating Curve= 0 ,0
Exp/Cntr=0.3,0.1

Type RM Length L Ch R = 1 ,215368  ,635,635,635
BEGIN DESCRIPTION:
E20717
END DESCRIPTION:
XS GIS Cut Line= 2
      2470582.47     13852909.75      2470871.07     13851572.34
#Sta/Elev= 30
  3941.4  510.51  4023.8  512.28  4140.6  512.08  4191.8  510.84  4375.9  509.51
  4427.1  510.52  4451.9  509.64    4601  509.05  4611.2  510.55  4662.4  507.04
  4688.1  507.23  4727.7  505.35  4754.4  504.13  4781.5   501.3  4825.7  499.41
  4887.4  500.61  4938.6   499.9    4972  494.35  4989.7  497.47  5010.2  495.33
    5021  492.66  5021.5  492.16  5040.3  492.66  5040.9  498.34  5153.4  509.89
  5204.6  521.64  5214.8  525.02    5225  526.14  5286.4  526.55  5309.6  525.34
#Mann= 5 ,-1 , 0
  3941.4     .12       0  4727.7      .1       0    4972     .12       0
    5021     .05       0  5040.3     .12       0
Bank Sta=5021,5040.3
XS Rating Curve= 0 ,0
Exp/Cntr=0.3,0.1

Type RM Length L Ch R = 1 ,214733  ,620,620,620
BEGIN DESCRIPTION:
E20716
END DESCRIPTION:
XS GIS Cut Line= 3
      2471525.69     13853120.98      2471180.77      13851973.6
      2471032.94     13851304.85
#Sta/Elev= 30
  4064.7  515.11  4192.8  510.38  4196.5  510.18  4360.2  506.48    4541  507.53
  4607.1  505.48  4673.2  500.98  4678.4  501.73  4744.5   499.5  4918.3  498.08
  4947.9  498.04  4958.5  496.91    4969  493.61  4969.7  490.59  4970.2  490.09
  4989.1  490.59  4991.3  492.34  5000.3  495.56  5024.4  497.68  5041.4  497.54
  5104.7  499.72  5239.4  498.29  5281.9  500.48  5494.9  501.36  5568.6  502.55
  5599.3  504.42  5622.3  504.58  5826.1  509.03  5855.4  507.72  5947.7  506.69
#Mann= 9 ,-1 , 0
  4064.7     .12       0  4192.8     .07       0  4196.5     .05       0
  4918.3     .12       0  4969.7     .05       0  4989.1     .12       0
  5041.4     .07       0  5239.4     .12       0  5622.3     .07       0
Bank Sta=4969.7,4989.1
XS Rating Curve= 0 ,0
Exp/Cntr=0.3,0.1

Type RM Length L Ch R = 1 ,214113  ,750,750,750
BEGIN DESCRIPTION:
E20715
END DESCRIPTION:
XS GIS Cut Line= 3
      2472342.19     13852367.77      2471328.59     13851614.61
      2471237.27     13851249.34
#Sta/Elev= 30
  4044.5  505.83  4152.5  505.76  4165.6  507.63  4202.6  508.07  4223.4   506.6
  4343.3  506.98  4523.8  508.03  4545.3  509.32  4688.6     507  4731.3  507.81
  4851.3  503.88  4891.4   498.1    4938     497  4945.2  494.87    4966  495.98
  4987.8   492.4  4991.7   489.3  4992.2   488.8  5011.3   489.3  5026.4  490.28
  5030.7  489.87  5037.7  492.87  5058.9  494.74  5066.2  494.23  5130.8  501.25
  5251.8  499.54  5442.7  500.44  5541.3  504.91  5595.5  506.87  5683.8  507.38
#Mann= 11 ,-1 , 0
  4044.5     .07       0  4343.3    .035       0  4545.3     .07       0
  4731.3     .12       0  4891.4     .07       0  4991.7     .05       0
  5011.3     .07       0  5026.4     .12       0  5058.9     .07       0
  5442.7    .035       0  5541.3     .07       0
Bank Sta=4991.7,5011.3
XS Rating Curve= 0 ,0
Exp/Cntr=0.3,0.1

Type RM Length L Ch R = 1 ,213363  ,420,420,420
BEGIN DESCRIPTION:
E20714
END DESCRIPTION:
XS GIS Cut Line= 2
       2472504.1     13851811.71      2471505.24     13850939.46
#Sta/Elev= 30
  3960.9  506.46  4071.2   505.4  4078.8  506.19  4156.7  505.42  4312.3  505.62
  4333.2  506.37  4383.5  505.45  4404.4  505.96  4432.9  505.38  4439.5  504.54
  4602.8  497.61    4674  498.42  4722.6  497.05  4772.7  493.86  4850.3  493.57
  4886.6   494.2  4950.2  493.59  4971.1  491.37  4975.5  489.34    4976  488.84
  4995.2  489.34  5007.2  492.77  5021.4  494.91  5028.1  494.64  5042.3  499.58
  5056.6  500.87  5212.2  508.28  5234.1  508.82  5247.5  507.79    5287  507.13
#Mann= 5 ,-1 , 0
  3960.9     .12       0  4722.6    .035       0  4850.3     .12       0
  4975.5     .05       0  4995.2     .07       0
Bank Sta=4975.5,4995.2
XS Rating Curve= 0 ,0
Exp/Cntr=0.3,0.1

Type RM Length L Ch R = 1 ,212943  ,535,535,535
BEGIN DESCRIPTION:
E20713
END DESCRIPTION:
XS GIS Cut Line= 3
      2472539.29     13851769.46      2472074.72      13850889.6
      2471266.27     13850038.97
#Sta/Elev= 30
  3924.2  505.76    4359  505.36  4686.9  495.66  4913.3   498.1  4936.5  496.93
  4957.5  491.96  4966.9  491.56  4990.2  488.58  4990.7  488.08  5009.9  488.58
  5021.4  491.51  5042.5  492.89  5163.1   495.4  5205.1  493.76  5212.3   490.2
  5219.2  492.86  5240.7  490.73  5253.8  491.47  5261.7  491.29    5269  493.52
  5275.9  492.09    5290  493.19  5325.6  498.35  5383.5  502.71  5445.7  505.06
  5622.6  504.85  5707.4  505.55  5779.5  508.54  5891.2  513.31  6092.7  527.29
#Mann= 9 ,-1 , 0
  3924.2     .12       0  4966.9     .07       0  4990.2     .05       0
  5009.9     .07       0  5163.1    .035       0  5253.8     .07       0
  5383.5     .12       0  5622.6     .07       0  5779.5     .12       0
Bank Sta=4990.2,5009.9
XS Rating Curve= 0 ,0
Exp/Cntr=0.3,0.1

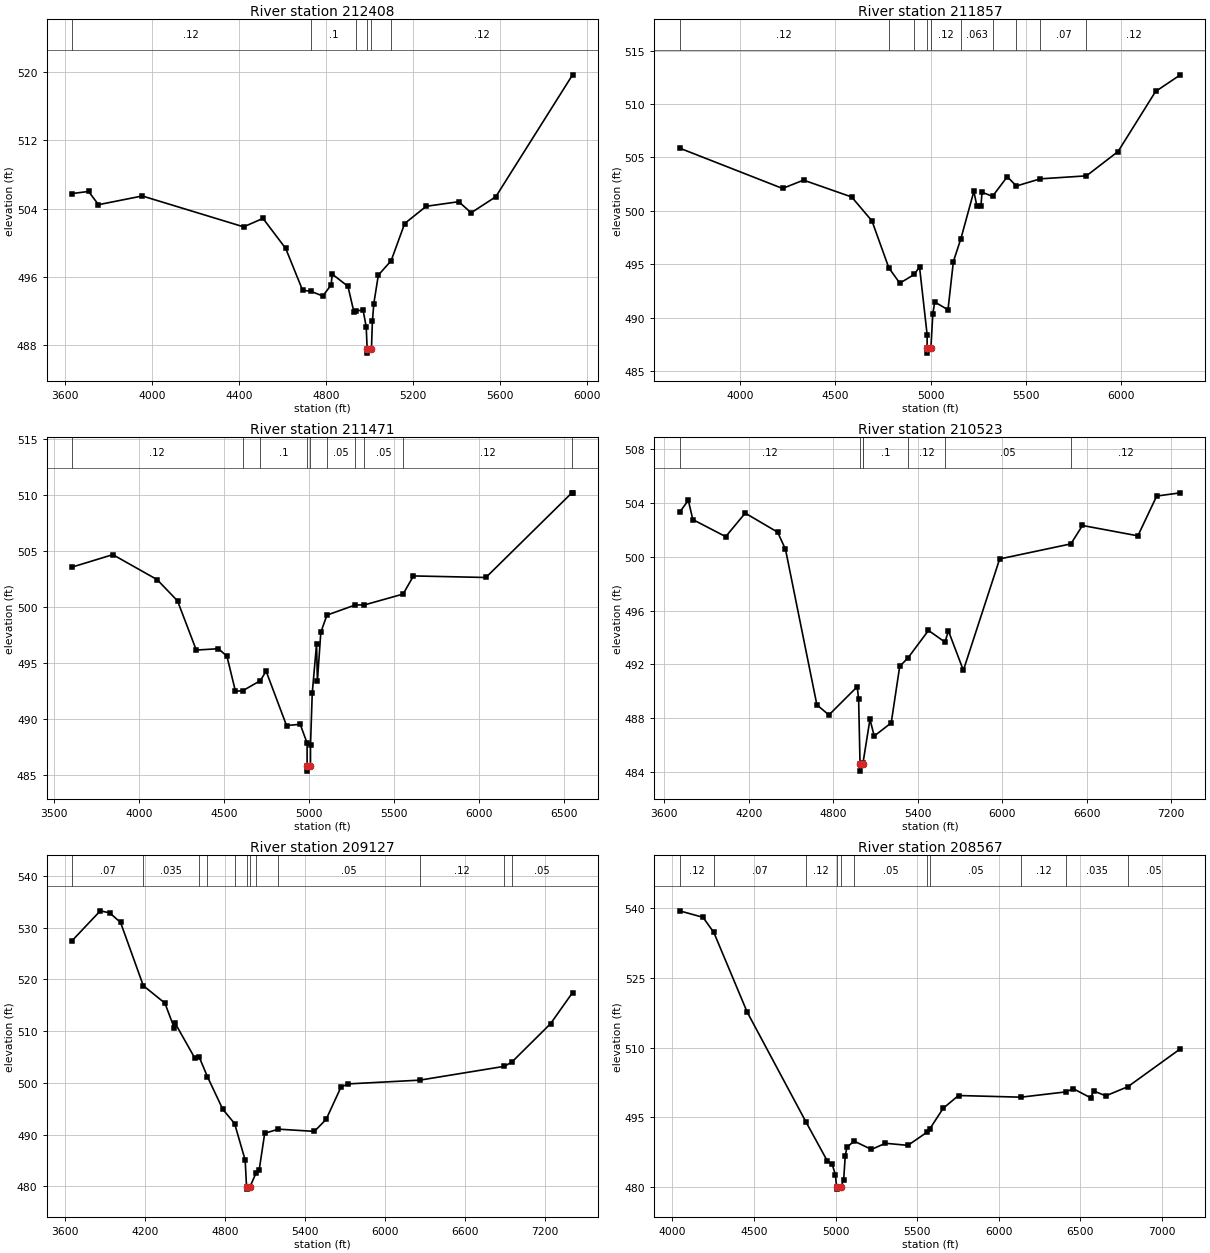
Type RM Length L Ch R = 1 ,212408  ,551,551,551
BEGIN DESCRIPTION:
E20712
END DESCRIPTION:
XS GIS Cut Line= 3
      2472602.64     13851713.15      2472229.58     13850467.26
      2471455.32     13849826.74
#Sta/Elev= 30
  3630.4  505.76    3708  506.01  3753.7  504.46  3955.3  505.48  4421.8  501.86
  4510.8  502.85  4615.3  499.33  4693.2  494.42  4730.1  494.31    4786  493.75
  4824.3  495.03  4829.5  496.32    4902  494.88  4928.8  491.93  4940.8  492.01
  4971.5  492.09  4985.9  490.16  4990.3  487.55  4990.8  487.05  5010.1  487.55
  5014.5  490.78    5021  492.87  5041.8   496.2  5100.6  497.88    5163  502.25
    5262  504.27  5411.8  504.81    5469  503.51  5582.4  505.39  5935.8  519.69
#Mann= 6 ,-1 , 0
  3630.4     .12       0  4730.1      .1       0  4940.8    .063       0
  4990.3    .063       0  5010.1    .063       0  5100.6     .12       0
Bank Sta=4990.3,5010.1
XS Rating Curve= 0 ,0
Exp/Cntr=0.3,0.1

Type RM Length L Ch R = 1 ,211857  ,386,386,386
BEGIN DESCRIPTION:
E20711
END DESCRIPTION:
XS GIS Cut Line= 3
      2472715.26     13851656.83      2472658.95     13850213.86
      2471632.55     13849609.26
#Sta/Elev= 30
  3679.4  505.87  4221.6  502.09    4332  502.87  4585.3  501.29    4692  499.05
  4780.8  494.65  4838.6  493.22  4914.7  494.04  4942.2  494.75  4982.2   488.4
  4982.3  487.17  4982.8  486.67  5002.2  487.17  5012.2  490.36  5022.2  491.46
    5092  490.73  5120.4  495.25  5160.1   497.4  5228.1  501.82  5243.8  500.45
  5265.3  500.44  5271.1  501.74  5326.3  501.35  5403.9  503.19  5451.9  502.32
  5577.3  502.99  5820.5  503.27  5986.9  505.55  6184.2  511.17  6314.7  512.73
#Mann= 10 ,-1 , 0
  3679.4     .12       0  4780.8     .07       0  4914.7     .12       0
  4982.3     .05       0  5002.2     .12       0  5160.1    .063       0
  5326.3     .07       0  5451.9     .12       0  5577.3     .07       0
  5820.5     .12       0
Bank Sta=4982.3,5002.2
XS Rating Curve= 0 ,0
Exp/Cntr=0.3,0.1

Type RM Length L Ch R = 1 ,211471  ,948,948,948
BEGIN DESCRIPTION:
E20710
END DESCRIPTION:
XS GIS Cut Line= 4
      2472989.78     13851586.46      2473017.94     13850284.25
      2472989.78     13850073.08      2471701.69     13849460.71
#Sta/Elev= 30
  3606.4  503.52  3847.9  504.64    4108  502.41    4228  500.51    4338  496.12
  4468.1  496.24  4518.1  495.57  4568.1  492.44  4611.3  492.49  4714.5  493.39
  4748.1  494.24  4868.2  489.38  4948.5  489.49  4988.9  487.82    4989  485.81
  4989.5  485.31  5008.9  485.81    5009  487.64  5019.1  492.26  5044.5  496.66
  5049.5  493.35  5069.6  497.71  5105.6  499.24  5272.2  500.15  5325.5  500.15
  5552.9  501.12  5613.6  502.74  6039.1   502.6  6544.1  510.16  6548.2  510.16
#Mann= 10 ,-1 , 0
  3606.4     .12       0  4611.3     .07       0  4714.5      .1       0
    4989     .05       0  5008.9      .1       0  5105.6     .05       0
  5272.2    .035       0  5325.5     .05       0  5552.9     .12       0
  6544.1    .035       0
Bank Sta=4989,5008.9
XS Rating Curve= 0 ,0
Exp/Cntr=0.3,0.1

Type RM Length L Ch R = 1 ,210523  ,1396,1396,1396
BEGIN DESCRIPTION:
E20709
END DESCRIPTION:
XS GIS Cut Line= 5
      2473144.64     13852043.98      2473566.98     13850861.44
      2473524.74     13850488.38      2473186.87     13850101.24
      2471962.11     13849397.35
#Sta/Elev= 30
  3707.4  503.32    3770  504.21  3801.9  502.78  4035.5  501.51  4174.1  503.26
  4404.5  501.84  4460.2  500.56  4683.2  488.99  4768.7  488.24  4969.6  490.34
  4979.6  489.41  4989.8  484.56  4990.3  484.06  5009.7  484.56  5010.1  484.63
  5060.2  487.92  5090.3  486.67  5211.1  487.65  5271.5  491.86  5329.9  492.48
  5475.8  494.53  5593.2  493.66  5617.3   494.5  5723.6  491.56  5981.4  499.85
  6487.2  500.97  6569.6  502.34  6963.1  501.57  7096.8  504.53    7265  504.77
#Mann= 7 ,-1 , 0
  3707.4     .12       0  4989.8     .05       0  5009.7     .12       0
  5010.1      .1       0  5329.9     .12       0  5593.2     .05       0
  6487.2     .12       0
Bank Sta=4989.8,5009.7
XS Rating Curve= 0 ,0
Exp/Cntr=0.3,0.1

Type RM Length L Ch R = 1 ,209127  ,560,560,560
BEGIN DESCRIPTION:
E20708
END DESCRIPTION:
XS GIS Cut Line= 3
      2475016.97     13850425.02      2473545.86     13849791.52
      2471483.46     13849150.98
#Sta/Elev= 30
  3647.6  527.38  3862.3  533.23  3932.8  532.83  4014.4  530.99  4185.2  518.77
  4347.5  515.39  4418.1  510.57  4423.5  511.55  4570.1  504.86    4604  505.03
  4666.8  501.18  4782.1  494.88  4870.8  492.12  4950.3  485.05  4960.4  479.95
  4960.9  479.45  4987.3  479.95    5033  482.64  5055.3  483.12  5096.9  490.23
  5199.5  491.04  5470.1  490.61  5558.5  492.94  5669.1  499.13  5721.3  499.78
  6261.5  500.51  6896.8  503.18  6954.1  504.03  7243.6  511.42  7408.9  517.43
#Mann= 12 ,-1 , 0
  3647.6     .07       0  4185.2    .035       0    4604     .07       0
  4666.8     .12       0  4870.8      .1       0  4960.4     .05       0
  4987.3      .1       0    5033     .07       0  5199.5     .05       0
  6261.5     .12       0  6896.8    .035       0  6954.1     .05       0
Bank Sta=4960.4,4987.3
XS Rating Curve= 0 ,0
Exp/Cntr=0.3,0.1

Type RM Length L Ch R = 1 ,208567  ,752,752,752
BEGIN DESCRIPTION:
E20707
END DESCRIPTION:
XS GIS Cut Line= 3
      2474728.42     13849432.54      2473292.46     13849326.95
      2471680.51     13849080.58
#Sta/Elev= 30
  4043.1  539.42  4186.9  538.03  4253.4  534.77  4457.6  517.67    4819  493.98
    4949  485.65    4979  484.93  4999.1  482.61  5005.7  480.08  5006.2  479.58
  5032.6  480.08  5049.2  481.49  5059.3  486.81  5069.3  488.57  5113.5  489.91
  5219.7  488.11    5305  489.44  5443.3  488.99  5558.4  491.77  5578.1  492.56
  5659.4  496.96  5753.5  499.71  6136.2  499.35  6414.3   500.5  6456.1  501.19
  6562.8  499.23    6583  500.67  6656.5  499.64  6792.2  501.61  7113.6  509.75
#Mann= 11 ,-1 , 0
  4043.1     .12       0  4253.4     .07       0    4819     .12       0
  5005.7     .05       0  5032.6     .12       0  5113.5     .05       0
  5558.4     .07       0  5578.1     .05       0  6136.2     .12       0
  6414.3    .035       0  6792.2     .05       0
Bank Sta=5005.7,5032.6
XS Rating Curve= 0 ,0
Exp/Cntr=0.3,0.1

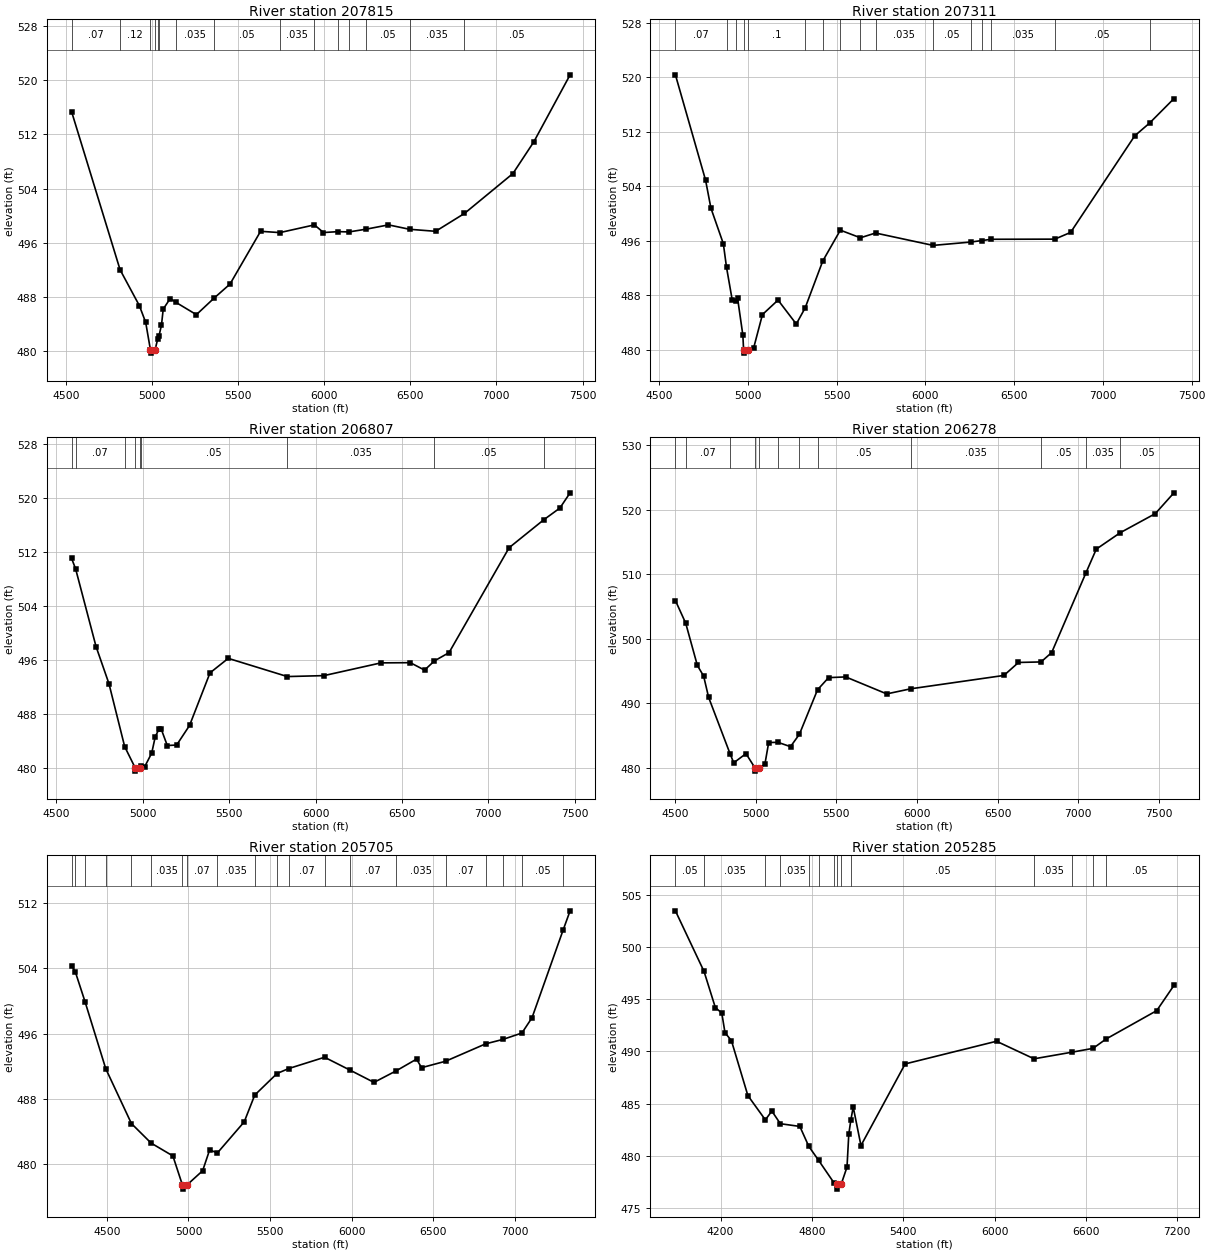
Type RM Length L Ch R = 1 ,207815  ,504,504,504
BEGIN DESCRIPTION:
SANDY FORK 166.0
END DESCRIPTION:
XS GIS Cut Line= 3
      2474274.96     13848525.01        2473825.       13848625.
      2471425.04     13849024.99
#Sta/Elev= 30
    4534  515.36  4815.5  492.01  4927.1  486.73  4964.2  484.24  4991.6   480.2
  4992.1   479.7  5018.5   480.2  5034.5  481.83  5041.1  482.22  5055.8  483.84
  5065.9   486.2  5106.4  487.76  5140.9  487.18  5258.5  485.38  5360.6  487.81
  5453.7   489.9  5631.1  497.69  5743.1   497.5  5943.8  498.64  5996.1  497.51
    6081  497.64  6144.5   497.6  6244.9  498.01  6373.7  498.64  6495.7  497.99
  6647.4  497.69  6814.8  500.33    7096  506.22  7217.7  510.92    7428   520.8
#Mann= 15 ,-1 , 0
    4534     .07       0  4815.5     .12       0  4991.6     .05       0
  5018.5     .12       0  5034.5      .1       0  5041.1     .07       0
  5140.9    .035       0  5360.6     .05       0  5743.1    .035       0
  5943.8     .05       0    6081    .035       0  6144.5     .07       0
  6244.9     .05       0  6495.7    .035       0  6814.8     .05       0
Bank Sta=4991.6,5018.5
XS Rating Curve= 0 ,0
Exp/Cntr=0.3,0.1

Type RM Length L Ch R = 1 ,207311  ,504,504,504
BEGIN DESCRIPTION:
SANDY FORK 165.0
END DESCRIPTION:
XS GIS Cut Line= 3
      2474324.96       13848175.        2473925.       13848175.
      2471524.98       13848375.
#Sta/Elev= 30
  4591.9  520.39  4761.9  504.89  4791.9  500.79  4861.9  495.56  4879.9  492.07
  4911.9  487.29  4931.1  487.19  4941.9  487.58  4971.9  482.11  4975.9  479.97
  4976.4  479.47  5002.8  479.97    5032  480.17  5082.2  485.14    5170  487.27
  5272.8  483.75  5322.8  486.12  5421.9  493.01    5521  497.55    5634  496.43
  5719.2  497.13  6043.5  495.31  6254.9   495.8    6320  496.03  6371.9  496.21
  6729.2  496.23  6818.2  497.22  7179.4  511.42  7263.2   513.3  7400.2  516.89
#Mann= 16 ,-1 , 0
  4591.9     .07       0  4879.9     .12       0  4931.1      .1       0
  4975.9     .05       0  5002.8      .1       0  5322.8     .12       0
  5421.9     .05       0    5521     .07       0    5634     .05       0
  5719.2    .035       0  6043.5     .05       0  6254.9    .035       0
    6320     .05       0  6371.9    .035       0  6729.2     .05       0
  7263.2     .07       0
Bank Sta=4975.9,5002.8
XS Rating Curve= 0 ,0
Exp/Cntr=0.3,0.1

Type RM Length L Ch R = 1 ,206807  ,529,529,529
BEGIN DESCRIPTION:
SANDY FORK 164.0
END DESCRIPTION:
XS GIS Cut Line= 3
      2474224.95     13847824.99        2473825.       13847725.
      2471425.02     13848324.99
#Sta/Elev= 30
  4587.7  511.08  4611.1  509.52  4729.4  497.99  4804.1  492.49    4895  483.16
  4955.6  480.02  4956.1  479.52  4982.5  480.02  4990.6  480.23  5010.3  480.15
  5051.5  482.19  5072.1  484.63  5092.7   485.7  5105.6  485.82  5141.7  483.32
  5195.8  483.39  5270.5  486.29  5389.1   494.1  5494.7  496.25  5836.8  493.55
  6048.8  493.69  6378.6  495.58  6548.7  495.61  6631.2  494.51  6688.7  495.88
  6772.9   497.1  7120.8  512.67  7321.2  516.81  7414.6  518.55  7473.8  520.81
#Mann= 9 ,-1 , 0
  4587.7     .05       0  4611.1     .07       0    4895      .1       0
  4955.6     .05       0  4982.5      .1       0  4990.6     .05       0
  5836.8    .035       0  6688.7     .05       0  7321.2     .07       0
Bank Sta=4955.6,4982.5
XS Rating Curve= 0 ,0
Exp/Cntr=0.3,0.1

Type RM Length L Ch R = 1 ,206278  ,573,573,573
BEGIN DESCRIPTION:
SANDY FORK 163.0
END DESCRIPTION:
XS GIS Cut Line= 3
      2474225.03     13847475.01        2473775.       13847275.
      2471374.98     13848275.01
#Sta/Elev= 30
  4501.6  505.92  4565.5  502.41  4637.7  495.87  4676.7  494.22  4707.5  490.93
  4840.5   482.2  4863.4  480.79  4939.4  482.21  4995.2     480  4995.7   479.5
  5022.2     480  5056.4  480.53  5080.2  483.93  5137.9  483.96  5215.6  483.29
  5270.8  485.21  5383.2   492.1  5451.8  493.98    5558  494.09  5812.5  491.46
  5961.2  492.25  6539.5  494.32  6629.9  496.33  6769.8  496.41  6835.7  497.86
  7046.8  510.12  7112.5  513.88  7261.5  516.43  7478.7  519.38  7594.1   522.6
#Mann= 12 ,-1 , 0
  4501.6     .05       0  4565.5     .07       0  4840.5      .1       0
  4995.2     .05       0  5022.2      .1       0  5137.9     .05       0
  5270.8     .07       0  5383.2     .05       0  5961.2    .035       0
  6769.8     .05       0  7046.8    .035       0  7261.5     .05       0
Bank Sta=4995.2,5022.2
XS Rating Curve= 0 ,0
Exp/Cntr=0.3,0.1

Type RM Length L Ch R = 1 ,205705  ,420,420,420
BEGIN DESCRIPTION:
SANDY FORK 162.0
END DESCRIPTION:
XS GIS Cut Line= 3
        2474275.       13847375.        2473875.       13846775.
      2471874.99       13847975.
#Sta/Elev= 30
  4284.1  504.34  4306.9  503.58  4366.1  499.93  4493.2  491.68  4650.6  484.93
  4771.2  482.53  4904.6  480.95  4963.1  477.37  4963.6  476.87  4990.2  477.37
  5086.8  479.13  5129.6  481.69  5177.2  481.32  5341.5  485.14  5405.9  488.43
  5542.3  491.08  5613.7  491.69  5833.7  493.08  5990.4  491.49  6136.4  489.99
  6273.1  491.42  6396.9  492.85    6428   491.8  6574.8  492.59  6820.4  494.73
  6925.5  495.27  7042.4  496.06  7104.4  497.94    7294  508.67  7337.6  511.08
#Mann= 20 ,-1 , 0
  4284.1     .05       0  4306.9     .07       0  4366.1     .05       0
  4493.2     .07       0  4650.6      .1       0  4771.2    .035       0
  4963.1     .05       0  4990.2     .07       0  5177.2    .035       0
  5405.9    .035       0  5542.3     .05       0  5613.7     .07       0
  5833.7     .05       0  5990.4     .07       0  6273.1    .035       0
  6574.8     .07       0  6820.4    .035       0  6925.5     .07       0
  7042.4     .05       0    7294    .035       0
Bank Sta=4963.1,4990.2
XS Rating Curve= 0 ,0
Exp/Cntr=0.3,0.1

Type RM Length L Ch R = 1 ,205285  ,348,348,348
BEGIN DESCRIPTION:
E20706
END DESCRIPTION:
XS GIS Cut Line= 4
      2474460.92     13847313.78      2474172.33     13846455.06
      2473855.58     13846391.71      2471955.03     13847151.92
#Sta/Elev= 30
  3903.1  503.46  4091.2  497.66  4165.6   494.2  4207.8  493.68  4228.9   491.8
  4271.1  491.04  4379.3  485.78  4494.1  483.46  4536.9   484.3  4592.6  483.09
  4720.8  482.83  4779.7  480.92  4844.3  479.58  4944.2  477.45  4966.1  477.33
  4966.6  476.83  4993.2  477.33  5030.7  478.94  5042.4  482.08  5055.6  483.41
  5071.4  484.69  5122.4     481  5412.7  488.81  6013.2  490.98  6259.9   489.3
  6511.3  489.94  6647.6   490.3  6732.7  491.19    7066  493.91    7179  496.32
#Mann= 14 ,-1 , 0
  3903.1     .05       0  4091.2    .035       0  4494.1     .07       0
  4592.6    .035       0  4779.7     .07       0  4844.3      .1       0
  4944.2     .07       0  4966.1     .05       0  4993.2     .07       0
  5055.6     .05       0  6259.9    .035       0  6511.3     .05       0
  6647.6    .035       0  6732.7     .05       0
Bank Sta=4966.1,4993.2
XS Rating Curve= 0 ,0
Exp/Cntr=0.3,0.1

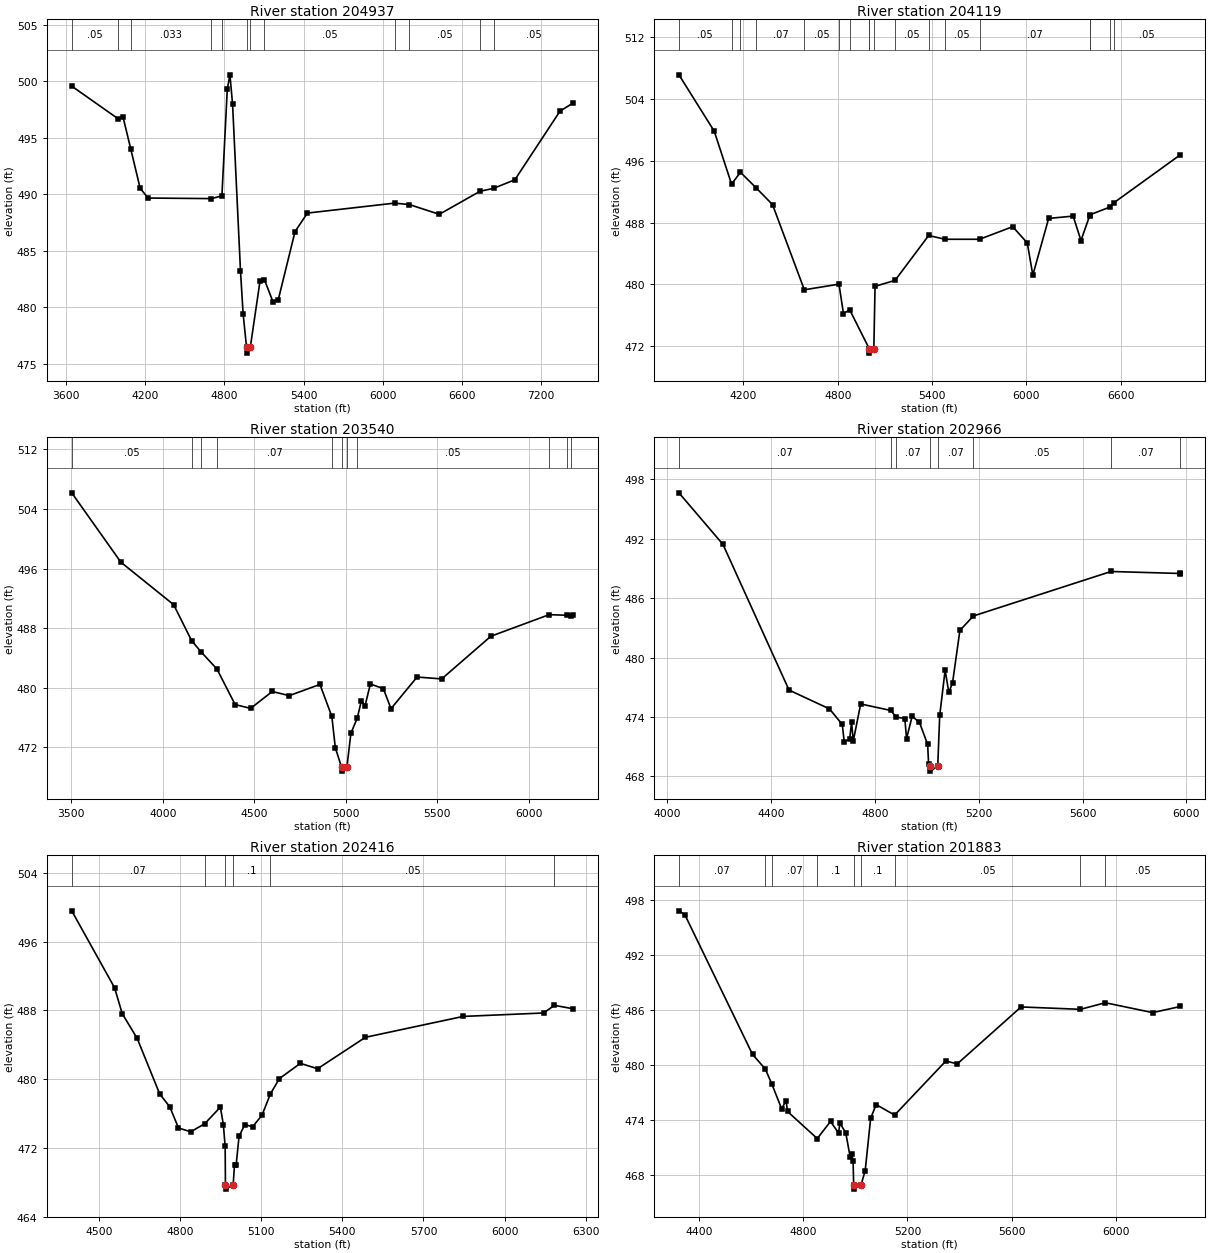
Type RM Length L Ch R = 1 ,204937  ,818,818,818
BEGIN DESCRIPTION:
E20705
END DESCRIPTION:
XS GIS Cut Line= 4
      2475383.01     13846110.15      2473954.12     13846117.19
      2473257.26     13846419.86      2471821.27      13847144.9
#Sta/Elev= 30
  3644.2  499.56  3993.2  496.69  4032.2  496.85  4091.8  493.97  4162.2  490.53
  4222.2  489.66  4702.6  489.61  4781.5  489.85  4822.2  499.29  4842.2  500.56
  4862.2  497.97  4922.2  483.21  4942.2   479.4  4968.2  476.44  4968.7  475.94
  4996.2  476.44  5070.2  482.32    5104  482.42  5170.3  480.42    5207   480.6
  5335.2  486.69    5429  488.33  6089.5  489.21  6201.8  489.08  6427.9  488.22
  6736.6  490.26  6839.8  490.52  7000.4  491.28    7342  497.35  7441.5  498.07
#Mann= 12 ,-1 , 0
  3644.2     .05       0  3993.2     .07       0  4091.8    .033       0
  4702.6     .12       0  4781.5      .1       0  4968.2     .05       0
  4996.2      .1       0    5104     .05       0  6089.5     .07       0
  6201.8     .05       0  6736.6    .035       0  6839.8     .05       0
Bank Sta=4968.2,4996.2
XS Rating Curve= 0 ,0
Exp/Cntr=0.3,0.1

Type RM Length L Ch R = 1 ,204119  ,579,579,579
BEGIN DESCRIPTION:
E20704
END DESCRIPTION:
XS GIS Cut Line= 3
      2474446.83     13845054.32      2473313.58     13845877.86
       2471905.8     13846982.96
#Sta/Elev= 30
  3789.2  507.12  4013.9  499.82  4123.9  492.98  4180.7   494.5  4282.6  492.44
  4384.8  490.32  4587.1  479.29  4807.5  480.02  4836.3   476.2  4875.5  476.71
  4999.9  471.67  5001.3  471.59  5001.8  471.09  5029.3  471.59  5037.2  479.74
  5164.5  480.51  5378.4  486.32    5482  485.83    5702  485.83  5912.9  487.46
  6005.8  485.36  6041.1  481.19  6141.8  488.53  6297.7  488.83  6347.5  485.67
    6403  488.89  6404.6     489  6531.5     490  6558.4  490.58  6979.8  496.77
#Mann= 18 ,-1 , 0
  3789.2     .05       0  4123.9     .07       0  4180.7     .05       0
  4282.6     .07       0  4587.1     .05       0  4807.5      .1       0
  4875.5     .07       0  4999.9     .05       0  5001.3     .05       0
  5029.3     .05       0  5164.5     .05       0  5378.4     .07       0
    5482     .05       0    5702     .07       0    6403     .05       0
  6404.6    .035       0  6531.5     .07       0  6558.4     .05       0
Bank Sta=5001.3,5029.3
XS Rating Curve= 0 ,0
Exp/Cntr=0.3,0.1

Type RM Length L Ch R = 1 ,203540  ,574,574,574
BEGIN DESCRIPTION:
SANDY FORK 159.0
END DESCRIPTION:
XS GIS Cut Line= 3
      2474375.04     13844974.99        2472975.       13845525.
      2472044.82     13846338.91
#Sta/Elev= 30
  3501.9  506.17  3770.5  496.85  4058.9  491.14    4157  486.31  4207.3  484.84
  4295.6  482.49  4394.9  477.72  4479.6  477.21  4597.8  479.48  4690.4  478.92
  4858.4  480.43  4923.4  476.12  4942.4  471.91    4977  469.28  4977.5  468.78
  5005.5  469.28  5027.5  473.87  5062.1  475.89  5084.4  478.19  5105.3  477.59
  5133.8  480.49  5204.9  479.86  5246.7  477.17  5389.1  481.42  5523.8  481.17
  5792.4   486.9  6110.9   489.8  6209.8  489.72  6230.3  489.65  6242.1  489.69
#Mann= 11 ,-1 , 0
  3501.9     .05       0    4157     .07       0  4207.3     .05       0
  4295.6     .07       0  4923.4     .12       0    4977     .05       0
  5005.5     .12       0  5062.1     .05       0  6110.9    .035       0
  6209.8     .05       0  6230.3     .07       0
Bank Sta=4977,5005.5
XS Rating Curve= 0 ,0
Exp/Cntr=0.3,0.1

Type RM Length L Ch R = 1 ,202966  ,550,550,550
BEGIN DESCRIPTION:
SANDY FORK 158.0
END DESCRIPTION:
XS GIS Cut Line= 3
      2473375.03     13844374.97        2472725.       13845075.
       2471989.5     13845718.56
#Sta/Elev= 30
  4044.2  496.63    4214  491.42  4468.6  476.72  4624.5  474.82  4673.8  473.25
  4681.2  471.52  4702.2  471.76  4709.5  473.45  4716.3   471.6  4744.7  475.32
  4861.1  474.66    4881     474  4914.7  473.85  4921.6  471.83  4943.1  474.08
  4971.4  473.45  5002.8  471.23  5006.6  469.22  5013.2  469.04  5013.7  468.54
  5041.7  469.04  5049.3  474.16  5070.2  478.73  5084.4  476.48  5098.7  477.44
  5127.1  482.74    5179   484.2  5709.7  488.69  5974.8  488.49  5976.8  488.46
#Mann= 8 ,-1 , 0
  4044.2     .07       0  4861.1      .1       0    4881     .07       0
  5013.2     .05       0  5041.7     .07       0    5179     .05       0
  5709.7     .07       0  5974.8     .05       0
Bank Sta=5013.2,5041.7
XS Rating Curve= 0 ,0
Exp/Cntr=0.3,0.1

Type RM Length L Ch R = 1 ,202416  ,533,533,533
BEGIN DESCRIPTION:
SANDY FORK 157.0
END DESCRIPTION:
XS GIS Cut Line= 3
        2473325.       13844325.        2472775.       13844575.
      2471922.18     13845486.63
#Sta/Elev= 30
  4400.4   499.6  4558.6  490.65  4587.1  487.62  4642.1  484.76  4725.5  478.28
  4762.9  476.78  4794.7  474.33  4839.8  473.88  4891.5  474.82  4949.6  476.75
  4960.6  474.71  4967.2  472.18  4968.3  467.71  4968.8  467.21  4996.8  467.71
  5001.8  470.07    5008  470.07  5018.5  473.35    5040  474.73  5068.3  474.46
  5103.5  475.82  5134.2  478.28  5167.5  480.07  5245.1  481.85  5308.6  481.22
  5485.5  484.88  5846.5  487.31  6143.5  487.71  6183.7   488.6  6252.9   488.2
#Mann= 6 ,-1 , 0
  4400.4     .07       0  4891.5      .1       0  4968.3     .05       0
  4996.8      .1       0  5134.2     .05       0  6183.7     .07       0
Bank Sta=4968.3,4996.8
XS Rating Curve= 0 ,0
Exp/Cntr=0.3,0.1

Type RM Length L Ch R = 1 ,201883  ,553,553,553
BEGIN DESCRIPTION:
SANDY FORK 156.0
END DESCRIPTION:
XS GIS Cut Line= 3
      2473125.02     13843824.99        2472525.       13844125.
      2471830.32     13845167.02
#Sta/Elev= 30
  4323.4  496.84  4345.8  496.43  4605.7  481.14  4654.5  479.55  4679.1  477.95
  4717.5  475.18  4734.3   476.1  4739.9   474.9  4853.9  471.94  4904.8  473.81
  4935.5  472.55  4941.1  473.64  4963.5  472.54  4980.3   469.9  4985.9   470.3
  4991.4  469.54  4993.5  466.91    4994  466.41  5022.1  466.91  5037.8  468.43
  5058.8  474.17  5079.9  475.65  5150.7  474.51  5347.3  480.42  5390.9   480.1
  5635.7  486.33  5863.4  486.07  5958.7  486.79  6140.5  485.71  6246.6  486.38
#Mann= 9 ,-1 , 0
  4323.4     .07       0  4654.5      .1       0  4679.1     .07       0
  4853.9      .1       0  4993.5     .05       0  5022.1      .1       0
  5150.7     .05       0  5863.4     .07       0  5958.7     .05       0
Bank Sta=4993.5,5022.1
XS Rating Curve= 0 ,0
Exp/Cntr=0.3,0.1

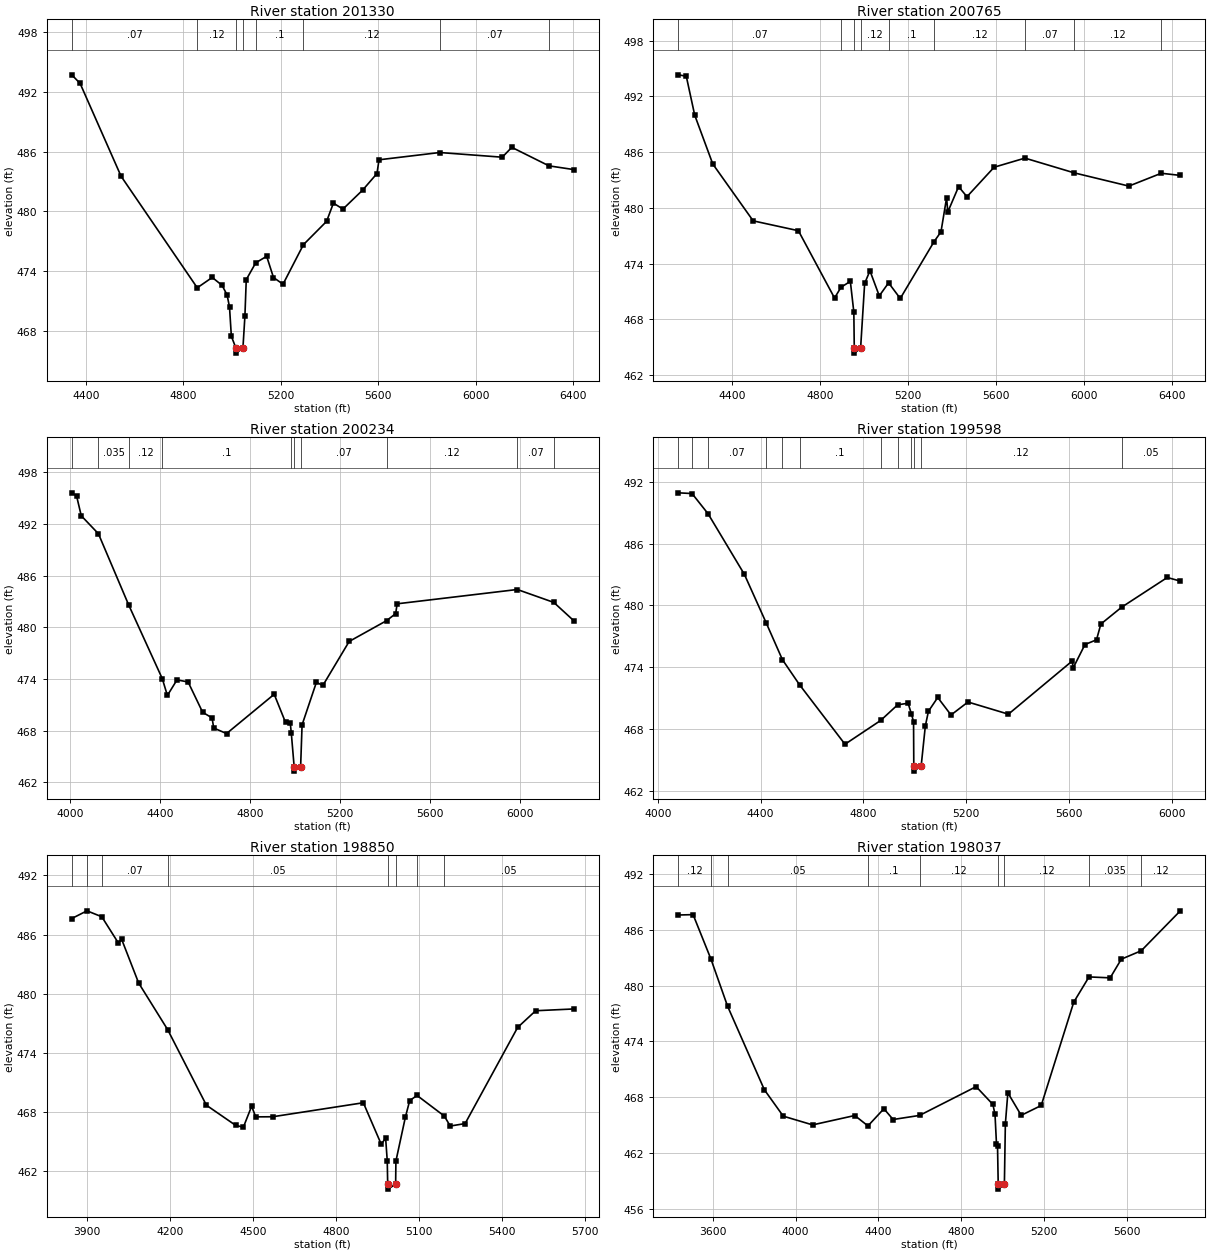
Type RM Length L Ch R = 1 ,201330  ,565,565,565
BEGIN DESCRIPTION:
SANDY FORK 155.0
END DESCRIPTION:
XS GIS Cut Line= 3
      2473025.04     13843725.01        2472375.       13843625.
      2471747.65     13844879.71
#Sta/Elev= 30
  4342.3  493.72  4376.5  492.86  4544.7  483.54  4857.5  472.34  4919.1  473.38
  4959.5  472.58  4979.8  471.63  4989.9  470.42  4997.5  467.47  5016.4  466.28
  5016.9  465.78    5045  466.28  5053.1  469.47  5058.7  473.16  5097.7  474.85
  5142.5   475.5  5170.5  473.37  5209.6   472.7  5293.4  476.67  5388.5  479.01
  5416.5  480.84  5455.6  480.24  5536.6  482.15  5595.3  483.81  5603.7  485.19
  5852.9  485.92  6109.6  485.45  6148.8  486.44  6301.6  484.58  6402.8  484.21
#Mann= 8 ,-1 , 0
  4342.3     .07       0  4857.5     .12       0  5016.4     .05       0
    5045     .12       0  5097.7      .1       0  5293.4     .12       0
  5852.9     .07       0  6301.6     .05       0
Bank Sta=5016.4,5045
XS Rating Curve= 0 ,0
Exp/Cntr=0.3,0.1

Type RM Length L Ch R = 1 ,200765  ,531,531,531
BEGIN DESCRIPTION:
SANDY FORK 154.0
END DESCRIPTION:
XS GIS Cut Line= 3
      2472874.98     13842775.01        2472125.       13843175.
      2471645.78     13844525.52
#Sta/Elev= 30
  4154.2  494.32  4189.9  494.17  4228.2  489.99  4310.4  484.73  4494.2  478.61
  4699.9  477.55  4864.3  470.31  4893.9  471.47  4936.2   472.1  4952.1  468.79
  4954.1  464.88  4954.6  464.38  4982.8  464.88  5001.3  471.88  5025.4  473.24
  5067.8  470.54  5110.2  471.94  5163.3  470.26  5316.9  476.37  5348.5  477.43
  5374.1   481.1  5379.4  479.56  5428.6  482.29  5466.7  481.21  5590.2  484.38
  5730.4  485.36    5955  483.77  6203.2  482.35  6350.5  483.73  6437.2   483.5
#Mann= 9 ,-1 , 0
  4154.2     .07       0  4893.9     .12       0  4954.1     .05       0
  4982.8     .12       0  5110.2      .1       0  5316.9     .12       0
  5730.4     .07       0    5955     .12       0  6350.5    .035       0
Bank Sta=4954.1,4982.8
XS Rating Curve= 0 ,0
Exp/Cntr=0.3,0.1

Type RM Length L Ch R = 1 ,200234  ,636,636,636
BEGIN DESCRIPTION:
SANDY FORK 153.0
END DESCRIPTION:
XS GIS Cut Line= 3
        2472575.       13842125.        2471825.       13842775.
      2471484.81     13843965.68
#Sta/Elev= 30
  4007.2   495.6  4028.6  495.24  4049.4  492.94  4125.7  490.85  4259.8  482.61
  4409.6  474.03  4432.2  472.08  4474.9  473.89  4524.3  473.65  4588.9  470.13
  4630.7  469.48  4638.3   468.3  4695.3  467.66    4907  472.22  4957.4  468.95
  4978.3   468.9  4983.1  467.68  4995.7   463.8  4996.2   463.3  5024.4   463.8
  5030.9  468.67  5094.6  473.61  5123.2  473.24  5240.2  478.35  5406.2  480.76
  5446.9  481.58  5453.4  482.72  5987.5  484.38  6149.8  482.88    6238  480.77
#Mann= 10 ,-1 , 0
  4007.2     .05       0  4125.7    .035       0  4259.8     .12       0
  4409.6      .1       0  4983.1     .07       0  4995.7     .05       0
  5024.4     .07       0  5406.2     .12       0  5987.5     .07       0
  6149.8    .035       0
Bank Sta=4995.7,5024.4
XS Rating Curve= 0 ,0
Exp/Cntr=0.3,0.1

Type RM Length L Ch R = 1 ,199598  ,748,748,748
BEGIN DESCRIPTION:
E20703
END DESCRIPTION:
XS GIS Cut Line= 3
      2472497.03     13841682.66      2471574.95     13842266.88
      2471195.13     13843040.59
#Sta/Elev= 30
  4080.5  490.93  4133.5  490.86  4195.8   488.9  4337.3  483.01  4422.9  478.26
  4485.3  474.73  4552.1  472.29  4728.8  466.52  4867.7  468.83  4933.8  470.35
  4974.5   470.5  4987.5  469.45  4995.7  468.71  4996.6  464.41  4997.1  463.91
  5025.3  464.41  5041.5  468.29  5053.6  469.72  5089.8  471.06  5141.5  469.36
  5207.5  470.62  5364.9  469.44  5612.2  474.58  5617.8  473.97  5662.8   476.2
  5707.8  476.66  5724.7  478.19  5805.3  479.82  5983.2  482.71    6034  482.36
#Mann= 12 ,-1 , 0
  4080.5     .05       0  4133.5    .035       0  4195.8     .07       0
  4422.9     .05       0  4485.3     .12       0  4552.1      .1       0
  4867.7     .12       0  4933.8      .1       0  4987.5     .12       0
  4996.6     .05       0  5025.3     .12       0  5805.3     .05       0
Bank Sta=4996.6,5025.3
XS Rating Curve= 0 ,0
Exp/Cntr=0.3,0.1

Type RM Length L Ch R = 1 ,198850  ,813,813,813
BEGIN DESCRIPTION:
E20702
END DESCRIPTION:
XS GIS Cut Line= 3
      2472264.78      13841260.3      2471293.39     13841753.03
      2470941.46     13842386.52
#Sta/Elev= 30
  3843.8  487.62  3898.8   488.4  3952.3   487.8  4011.8  485.16  4024.3   485.5
  4085.5  481.09  4190.5  476.36  4330.4  468.71  4436.1  466.67    4464  466.48
  4493.9  468.61  4508.5  467.53  4569.7  467.54  4897.6  468.96  4962.2  464.76
  4978.2  465.37    4984  463.08  4985.6  460.71  4986.1  460.21  5014.3  460.71
  5015.3  463.05  5049.7  467.52  5065.2  469.18  5091.7   469.7  5190.3  467.61
  5211.6   466.6  5265.4  466.85  5455.3  476.59  5520.5  478.28  5657.7  478.46
#Mann= 8 ,-1 , 0
  3843.8     .07       0  3898.8     .12       0  3952.3     .07       0
  4190.5     .05       0  4985.6     .05       0  5014.3     .05       0
  5091.7    .035       0  5190.3     .05       0
Bank Sta=4985.6,5014.3
XS Rating Curve= 0 ,0
Exp/Cntr=0.3,0.1

Type RM Length L Ch R = 1 ,198037  ,564,564,564
BEGIN DESCRIPTION:
SANDY FORK 152.0
END DESCRIPTION:
XS GIS Cut Line= 3
        2472175.       13841225.        2470625.       13841475.
      2469829.64     13841788.09
#Sta/Elev= 30
  3434.2  487.62  3505.1  487.66  3591.5  482.86  3671.7  477.79  3849.5  468.79
  3940.7  465.95  4082.5  465.01  4286.1  466.02  4349.9   464.9  4426.9  466.75
  4471.4  465.59  4599.1  466.03  4872.6  469.13  4953.6  467.21  4963.7  466.13
  4970.8  462.97  4975.9   462.7  4979.2  458.59  4979.7  458.09    5009  458.59
  5013.7  465.11  5025.7  468.47  5090.2  466.04    5187   467.1  5344.1  478.23
  5417.8  480.95  5520.1  480.85  5573.8  482.86  5670.2  483.77    5859  488.07
#Mann= 9 ,-1 , 0
  3434.2     .12       0  3591.5     .07       0  3671.7     .05       0
  4349.9      .1       0  4599.1     .12       0  4979.2     .05       0
    5009     .12       0  5417.8    .035       0  5670.2     .12       0
Bank Sta=4979.2,5009
XS Rating Curve= 0 ,0
Exp/Cntr=0.3,0.1