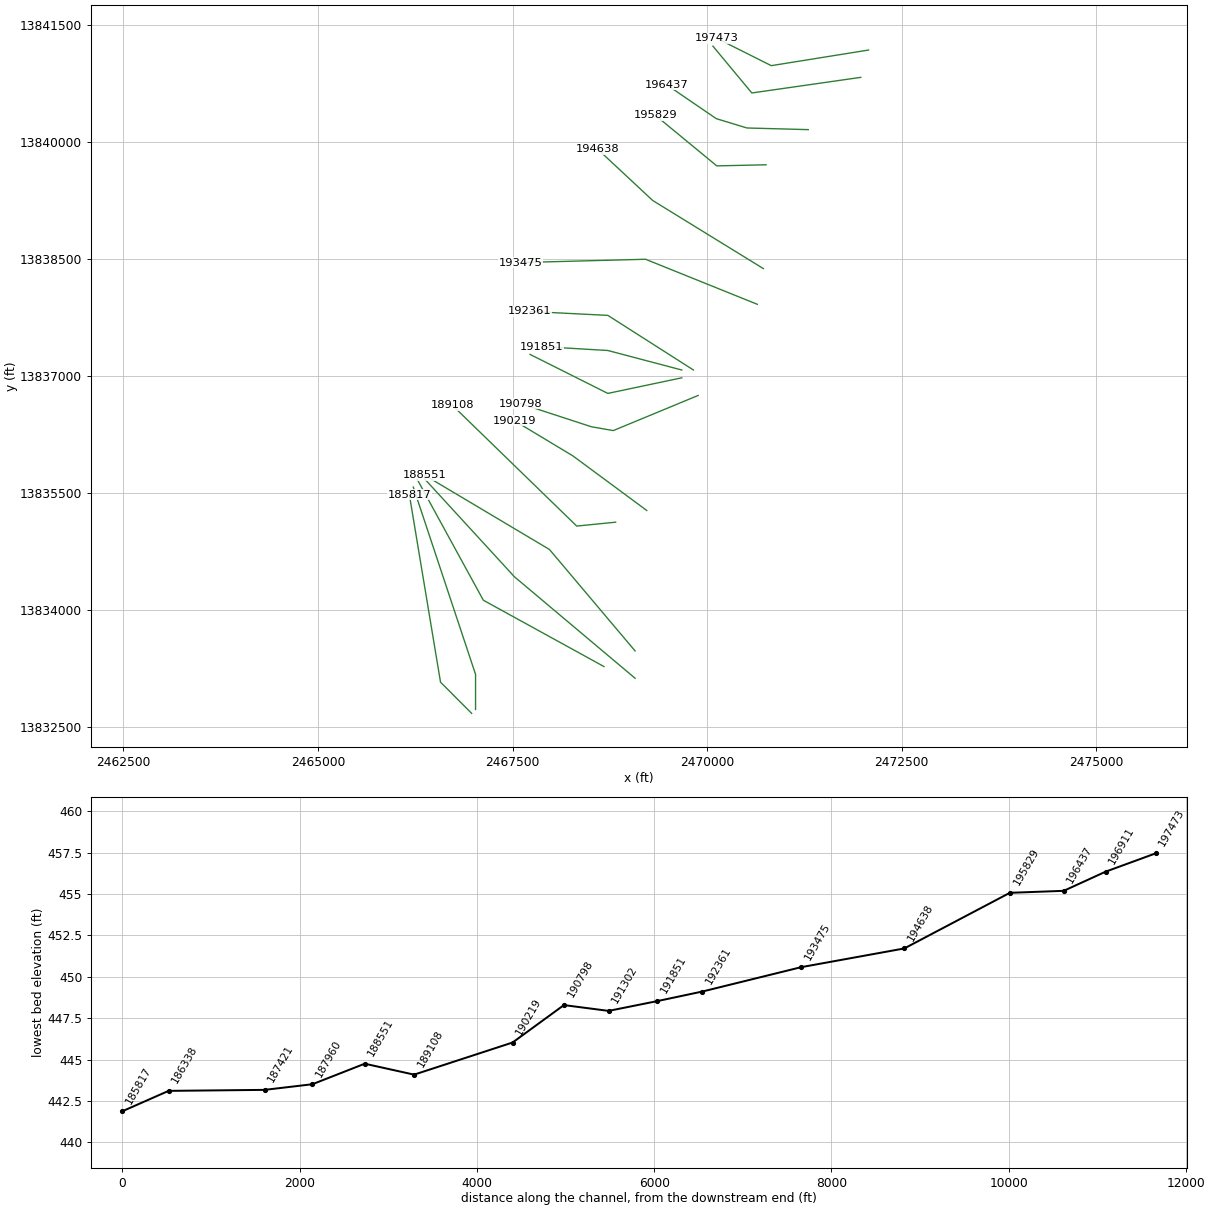
HEC-RAS study SANDY FORK.prj: SANDY FORK Base Level Engineering

--- SANDY FORK.g01 (geometry) --- (continued)

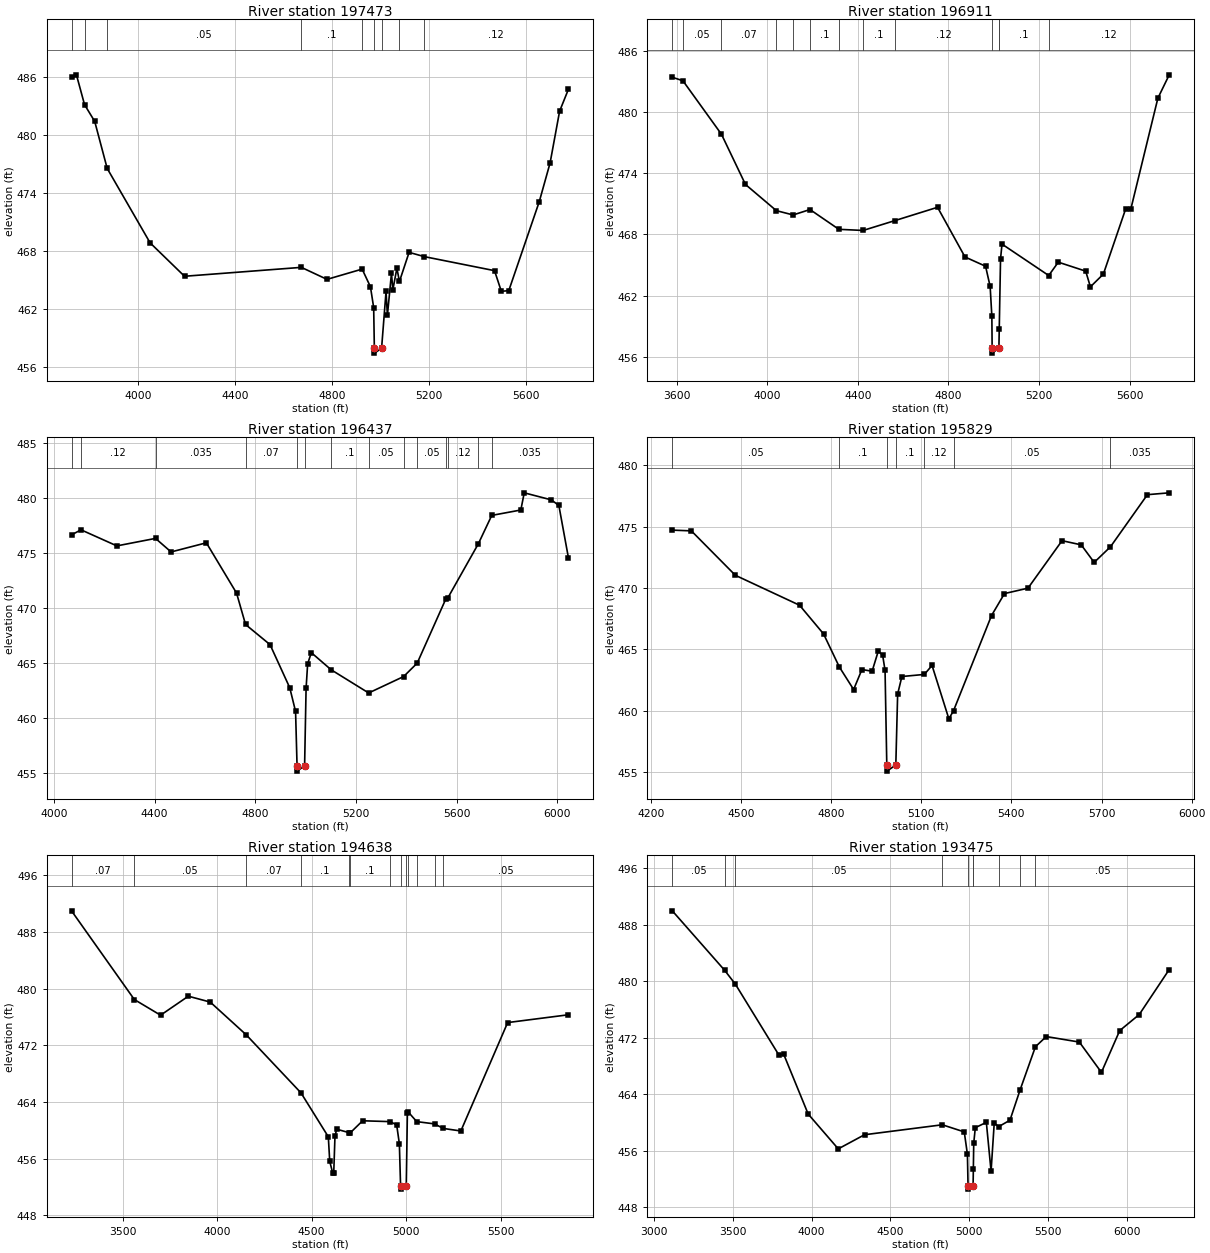
Type RM Length L Ch R = 1 ,197473  ,562,562,562
BEGIN DESCRIPTION:
SANDY FORK 151.0
END DESCRIPTION:
XS GIS Cut Line= 3
      2472075.05     13841175.01        2470825.       13840975.
      2470124.98     13841325.01
#Sta/Elev= 30
  3726.4  485.93  3746.7   486.2  3780.1  483.12    3822  481.39  3873.5  476.53
  4050.5  468.84  4192.3  465.39  4673.9  466.31  4779.7  465.07  4924.5  466.13
  4958.8   464.3  4972.1  462.16  4974.9  457.95  4975.4  457.45  5004.7  457.95
  5023.1  463.82  5028.7  461.35  5045.5  465.72    5051  463.97  5067.8  466.22
  5078.3  464.85  5118.1  467.86  5180.6  467.42  5470.3  465.97  5498.3  463.84
    5529   463.9  5654.8   473.1  5699.5  477.11  5738.6  482.44    5775  484.71
#Mann= 9 ,-1 , 0
  3726.4     .12       0  3780.1     .07       0  3873.5     .05       0
  4673.9      .1       0  4924.5     .12       0  4974.9     .05       0
  5004.7     .12       0  5078.3      .1       0  5180.6     .12       0
Bank Sta=4974.9,5004.7
XS Rating Curve= 0 ,0
Exp/Cntr=0.3,0.1

Type RM Length L Ch R = 1 ,196911  ,474,474,474
BEGIN DESCRIPTION:
SANDY FORK 150.0
END DESCRIPTION:
XS GIS Cut Line= 3
      2471974.96     13840824.99        2470575.       13840625.
        2470075.       13841225.
#Sta/Elev= 30
  3580.2   483.4    3627  483.06  3797.4  477.81  3903.4  472.89  4039.9  470.32
    4114   469.9  4188.4  470.43    4316  468.49  4423.1  468.38  4564.2  469.35
  4751.9  470.65  4873.2  465.78  4964.1  464.87  4984.3  462.89  4991.9  459.95
  4993.1  456.85  4993.6  456.35    5023  456.85  5024.5  458.67  5030.2  465.59
  5036.7  467.04  5243.1  463.96  5285.3  465.27  5406.4  464.39  5427.2  462.85
  5484.5   464.1  5583.4  470.52  5605.5  470.45  5725.3  481.35  5775.4  483.64
#Mann= 13 ,-1 , 0
  3580.2     .12       0    3627     .05       0  3797.4     .07       0
  4039.9      .1       0    4114     .07       0  4188.4      .1       0
    4316     .12       0  4423.1      .1       0  4564.2     .12       0
  4993.1     .05       0    5023     .12       0  5024.5      .1       0
  5243.1     .12       0
Bank Sta=4993.1,5023
XS Rating Curve= 0 ,0
Exp/Cntr=0.3,0.1

Type RM Length L Ch R = 1 ,196437  ,608,608,608
BEGIN DESCRIPTION:
E20701
END DESCRIPTION:
XS GIS Cut Line= 4
      2471300.48     13840155.19      2470512.07      13840176.3
      2470117.89     13840295.97      2469478.68     13840731.47
#Sta/Elev= 30
  4070.1  476.65  4107.9  477.11  4250.3  475.65  4403.8  476.33  4465.7   475.1
  4605.8  475.93  4725.8  471.36  4761.5  468.51  4858.8  466.68  4937.2  462.76
  4960.2  460.61  4966.1  455.69  4966.6  455.19  4996.1  455.69    5002  462.71
  5008.2  464.94  5022.9  465.95  5101.4   464.4  5250.6  462.29  5389.4  463.78
  5443.4     465  5557.1  470.83    5565  470.92  5686.5  475.85  5739.6  478.42
  5855.1  478.91  5868.6  480.47  5976.3  479.83  6006.2  479.32  6044.2  474.57
#Mann= 14 ,-1 , 0
  4070.1     .07       0  4107.9     .12       0  4403.8    .035       0
  4761.5     .07       0  4966.1     .05       0  4996.1     .07       0
  5101.4      .1       0  5250.6     .05       0  5389.4     .12       0
  5443.4     .05       0  5557.1    .035       0    5565     .12       0
  5686.5     .05       0  5739.6    .035       0
Bank Sta=4966.1,4996.1
XS Rating Curve= 0 ,0
Exp/Cntr=0.3,0.1

Type RM Length L Ch R = 1 ,195829  ,1191,1191,1191
BEGIN DESCRIPTION:
E20700
END DESCRIPTION:
XS GIS Cut Line= 3
      2470758.39     13839704.69      2470124.93     13839690.62
      2469336.53     13840338.23
#Sta/Elev= 30
  4271.4  474.71  4334.8  474.65  4481.2  471.03  4694.9  468.59  4774.9  466.25
  4827.3  463.56  4874.9  461.72  4902.5  463.35  4936.4  463.21  4957.2  464.87
  4971.6   464.5  4979.5  463.28  4985.3  455.57  4985.8  455.07  5015.3  455.57
  5021.4  461.35  5035.5  462.78  5110.1  462.95  5135.9  463.68  5191.9  459.33
  5207.5     460  5333.9  467.75    5377  469.54  5455.2  469.98  5568.6  473.85
  5632.4  473.51  5675.5  472.08  5729.7  473.35  5852.7   477.6  5925.3  477.75
#Mann= 7 ,-1 , 0
  4271.4     .05       0  4827.3      .1       0  4985.3     .05       0
  5015.3      .1       0  5110.1     .12       0  5207.5     .05       0
  5729.7    .035       0
Bank Sta=4985.3,5015.3
XS Rating Curve= 0 ,0
Exp/Cntr=0.3,0.1

Type RM Length L Ch R = 1 ,194638  ,1163,1163,1163
BEGIN DESCRIPTION:
SANDY FORK 149.0
END DESCRIPTION:
XS GIS Cut Line= 3
      2470723.23     13838374.34      2469301.37     13839247.16
       2468597.5     13839901.76
#Sta/Elev= 30
  3229.4  490.96  3561.8  478.45  3700.8  476.24  3847.6  478.92  3963.6  478.09
  4153.3  473.49  4443.6  465.29  4588.4  459.09  4595.8  455.63  4611.3  454.02
  4617.1  454.04  4623.6  459.16  4632.6  460.16    4699  459.67  4704.1  459.64
  4769.9  461.35  4916.1  461.23  4950.1  460.76  4964.3  458.13  4970.7  452.21
  4971.2  451.71  5000.9  452.21  5006.8  462.51  5012.4  462.55  5056.3  461.23
  5150.6  460.91  5196.5  460.27  5289.7  459.91  5537.4   475.2    5859   476.3
#Mann= 13 ,-1 , 0
  3229.4     .07       0  3561.8     .05       0  4153.3     .07       0
  4443.6      .1       0    4699     .12       0  4704.1      .1       0
  4916.1     .12       0  4970.7     .05       0  5000.9     .12       0
  5012.4      .1       0  5056.3     .05       0  5150.6     .07       0
  5196.5     .05       0
Bank Sta=4970.7,5000.9
XS Rating Curve= 0 ,0
Exp/Cntr=0.3,0.1

Type RM Length L Ch R = 1 ,193475  ,1114,1114,1114
BEGIN DESCRIPTION:
SANDY FORK 148.0
END DESCRIPTION:
XS GIS Cut Line= 3
      2470645.78     13837916.81      2469209.86     13838493.99
        2467605.     13838451.76
#Sta/Elev= 30
  3116.6  489.98  3448.7  481.56  3516.9  479.59  3793.3  469.55  3822.8  469.71
  3978.7  461.21  4169.6  456.28  4336.2  458.28  4829.9  459.69  4969.1  458.68
  4989.2   455.5  4993.1  451.08  4993.6  450.58  5025.2  451.08  5026.8  453.48
  5029.2  457.08  5039.2  459.28  5109.2  460.03  5139.2  453.11  5159.2  459.91
  5187.7  459.43  5259.2  460.34  5322.3  464.56  5420.7  470.74  5489.3  472.18
  5699.4   471.4  5839.4  467.11  5955.4  473.02  6079.5   475.3  6269.6  481.67
#Mann= 10 ,-1 , 0
  3116.6     .05       0  3448.7     .07       0  3516.9     .05       0
  4829.9      .1       0  4993.1     .05       0  5025.2      .1       0
  5026.8     .07       0  5187.7     .05       0  5322.3    .035       0
  5420.7     .05       0
Bank Sta=4993.1,5025.2
XS Rating Curve= 0 ,0
Exp/Cntr=0.3,0.1

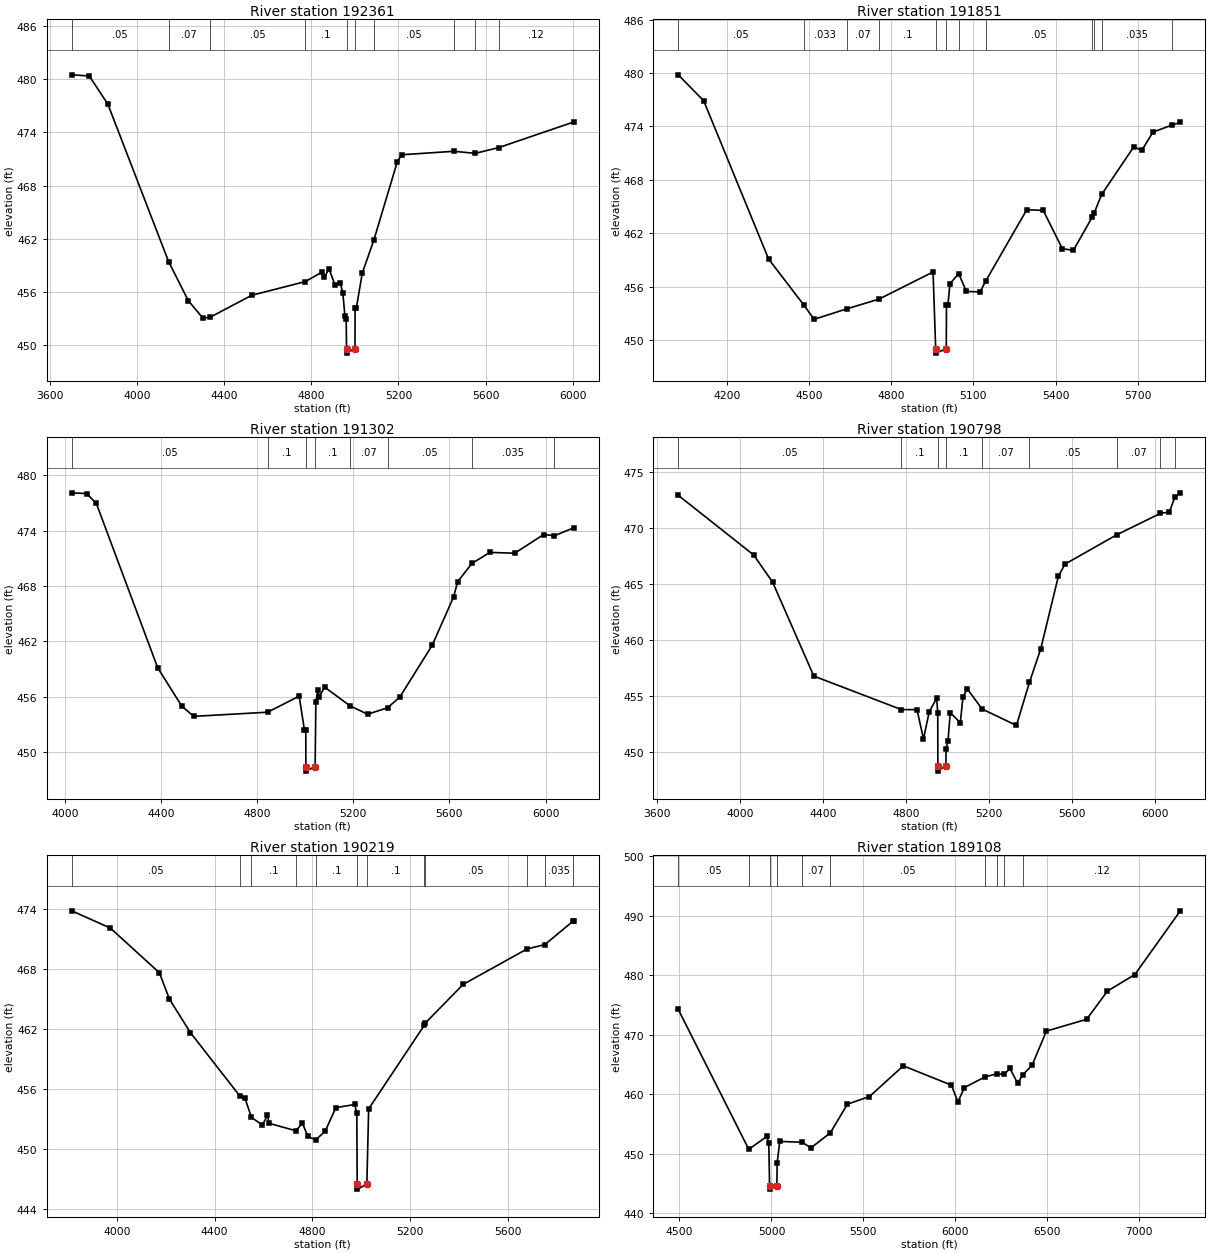
Type RM Length L Ch R = 1 ,192361  ,510,510,510
BEGIN DESCRIPTION:
SANDY FORK 147.0
END DESCRIPTION:
XS GIS Cut Line= 3
      2469824.97     13837075.02        2468725.       13837775.
      2467724.96       13837825.
#Sta/Elev= 30
    3700  480.48  3780.4  480.35  3865.9  477.16  4144.5  459.43  4235.1  455.02
  4301.9  453.06  4334.7  453.15  4526.3  455.63  4771.6  457.17  4850.6  458.26
  4859.9  457.65    4881  458.64    4909  456.74  4932.7  456.99  4944.5   455.9
  4953.9  453.35  4959.8  452.93  4961.6  449.61  4962.6  449.11  5000.2  449.61
  5000.8  454.16  5006.3  454.16  5033.8  458.14  5086.4  461.81    5194  470.63
  5214.1  471.47  5453.6  471.86  5552.3  471.63  5659.2  472.27  6005.1  475.17
#Mann= 10 ,-1 , 0
    3700     .05       0  4144.5     .07       0  4334.7     .05       0
  4771.6      .1       0  4961.6     .05       0  5000.2      .1       0
  5086.4     .05       0  5453.6     .07       0  5552.3    .035       0
  5659.2     .12       0
Bank Sta=4961.6,5000.2
XS Rating Curve= 0 ,0
Exp/Cntr=0.3,0.1

Type RM Length L Ch R = 1 ,191851  ,549,549,549
BEGIN DESCRIPTION:
SANDY FORK 146.0
END DESCRIPTION:
XS GIS Cut Line= 3
      2469675.03     13837074.99        2468725.       13837325.
      2467875.04       13837375.
#Sta/Elev= 30
  4021.8   479.8  4114.9  476.88  4351.7  459.11  4480.7  453.93  4518.2  452.33
    4637   453.5  4755.3   454.6  4952.5  457.65  4962.1  449.03  4963.1  448.53
  5000.7  449.03  5001.6  453.96  5006.7  453.96  5014.2  456.32    5046  457.46
  5074.3  455.46  5124.4  455.41  5144.8  456.63  5294.7  464.64  5354.8  464.57
  5424.9  460.26    5465  460.08  5533.7   463.8  5541.2  464.29  5568.6  466.37
  5685.3  471.69  5715.4  471.33  5755.5  473.36  5825.7  474.16  5855.6  474.45
#Mann= 12 ,-1 , 0
  4021.8     .05       0  4480.7    .033       0    4637     .07       0
  4755.3      .1       0  4962.1     .05       0  5000.7      .1       0
    5046     .07       0  5144.8     .05       0  5533.7    .035       0
  5541.2     .05       0  5568.6    .035       0  5825.7     .12       0
Bank Sta=4962.1,5000.7
XS Rating Curve= 0 ,0
Exp/Cntr=0.3,0.1

Type RM Length L Ch R = 1 ,191302  ,504,504,504
BEGIN DESCRIPTION:
SANDY FORK 145.0
END DESCRIPTION:
XS GIS Cut Line= 3
      2469674.97     13836974.99        2468725.       13836775.
      2467725.03     13837274.99
#Sta/Elev= 30
  4029.1  478.12  4090.4  478.04  4131.3  476.97  4386.7  459.14    4487  454.98
  4536.8  453.88  4843.9  454.33    4975  456.07  4997.3  452.37  5002.7  452.37
    5003  448.44    5004  447.94  5041.6  448.44  5044.6  455.42    5053  456.78
  5058.6     456    5081  457.05  5186.1  455.03  5259.8  454.11  5342.9  454.81
    5394  455.98  5528.2  461.57  5617.6  466.83  5634.4  468.48  5693.7  470.46
  5768.5  471.66    5872  471.57  5992.2   473.6  6037.4  473.47  6117.9  474.33
#Mann= 8 ,-1 , 0
  4029.1     .05       0  4843.9      .1       0    5003     .05       0
  5041.6      .1       0  5186.1     .07       0  5342.9     .05       0
  5693.7    .035       0  6037.4     .12       0
Bank Sta=5003,5041.6
XS Rating Curve= 0 ,0
Exp/Cntr=0.3,0.1

Type RM Length L Ch R = 1 ,190798  ,579,579,579
BEGIN DESCRIPTION:
E20699
END DESCRIPTION:
XS GIS Cut Line= 4
      2469885.62     13836749.04      2468794.56     13836298.54
      2468513.01     13836347.81      2467604.97     13836643.46
#Sta/Elev= 30
  3700.9  472.93  4064.6   467.6    4156  465.17  4354.8  456.78  4776.7  453.79
  4852.5  453.78  4883.6  451.15  4911.3   453.6  4947.3   454.8  4952.4  453.47
  4952.9  448.79  4953.9  448.29  4991.5  448.79  4992.5  450.31  5001.7  450.99
  5012.8  453.52  5061.2  452.61  5073.8  454.89  5094.1  455.66    5166  453.84
  5331.9  452.37  5394.7  456.23    5449  459.21    5534  465.69  5565.9  466.78
  5814.4  469.39  6025.5  471.31  6069.5  471.44  6096.4   472.8  6122.1  473.15
#Mann= 9 ,-1 , 0
  3700.9     .05       0  4776.7      .1       0  4952.9     .05       0
  4991.5      .1       0    5166     .07       0  5394.7     .05       0
  5814.4     .07       0  6025.5    .035       0  6096.4     .12       0
Bank Sta=4952.9,4991.5
XS Rating Curve= 0 ,0
Exp/Cntr=0.3,0.1

Type RM Length L Ch R = 1 ,190219  ,1111,1111,1111
BEGIN DESCRIPTION:
SANDY FORK 144.0
END DESCRIPTION:
XS GIS Cut Line= 3
      2469224.99       13835275.        2468275.       13835975.
      2467524.98     13836425.01
#Sta/Elev= 30
  3815.3  473.84    3973  472.12  4173.5  467.66  4215.2  465.01  4300.8  461.67
  4504.2   455.3  4523.3  455.17  4550.8   453.2  4595.4  452.43  4616.3  453.41
  4622.7  452.61  4732.5  451.86  4759.3  452.62  4781.3   451.3  4813.7  450.95
  4852.3  451.82    4896  454.17  4973.4  454.49  4981.8  453.61  4983.4  446.53
  4984.4  446.03  5022.9  446.53  5030.3  454.05  5258.5  462.42  5262.7  462.64
  5417.1  466.49  5678.5  470.03    5751  470.46  5867.9  472.83    5870  472.83
#Mann= 12 ,-1 , 0
  3815.3     .05       0  4504.2     .07       0  4550.8      .1       0
  4732.5     .05       0  4813.7      .1       0  4983.4     .05       0
  5022.9      .1       0  5258.5     .07       0  5262.7     .05       0
  5678.5     .07       0    5751    .035       0  5867.9     .12       0
Bank Sta=4983.4,5022.9
XS Rating Curve= 0 ,0
Exp/Cntr=0.3,0.1

Type RM Length L Ch R = 1 ,189108  ,557,557,557
BEGIN DESCRIPTION:
SANDY FORK 143.0
END DESCRIPTION:
XS GIS Cut Line= 3
      2468824.98       13835125.        2468325.       13835075.
      2466725.03     13836624.97
#Sta/Elev= 30
  4493.2  474.27  4876.6  450.78  4975.6  452.94  4985.6  451.78  4989.9  444.59
  4990.9  444.09  5029.6  444.59    5031  448.45  5045.2   452.1  5167.6  451.96
    5215  451.02  5320.2  453.54    5413  458.35  5533.2  459.64  5717.1  464.79
  5978.7  461.55    6014  458.71  6049.4  461.14  6160.4  462.92  6224.5  463.45
  6266.6  463.41  6296.9  464.35  6339.3  461.85  6365.6  463.26    6417  464.87
    6495  470.62  6714.1  472.61  6827.3  477.35  6975.8  480.11  7223.3  490.82
#Mann= 10 ,-1 , 0
  4493.2     .05       0  4876.6      .1       0  4989.9     .05       0
  5029.6      .1       0  5167.6     .07       0  5320.2     .05       0
  6160.4     .07       0  6224.5     .12       0  6266.6    .035       0
  6365.6     .12       0
Bank Sta=4989.9,5029.6
XS Rating Curve= 0 ,0
Exp/Cntr=0.3,0.1

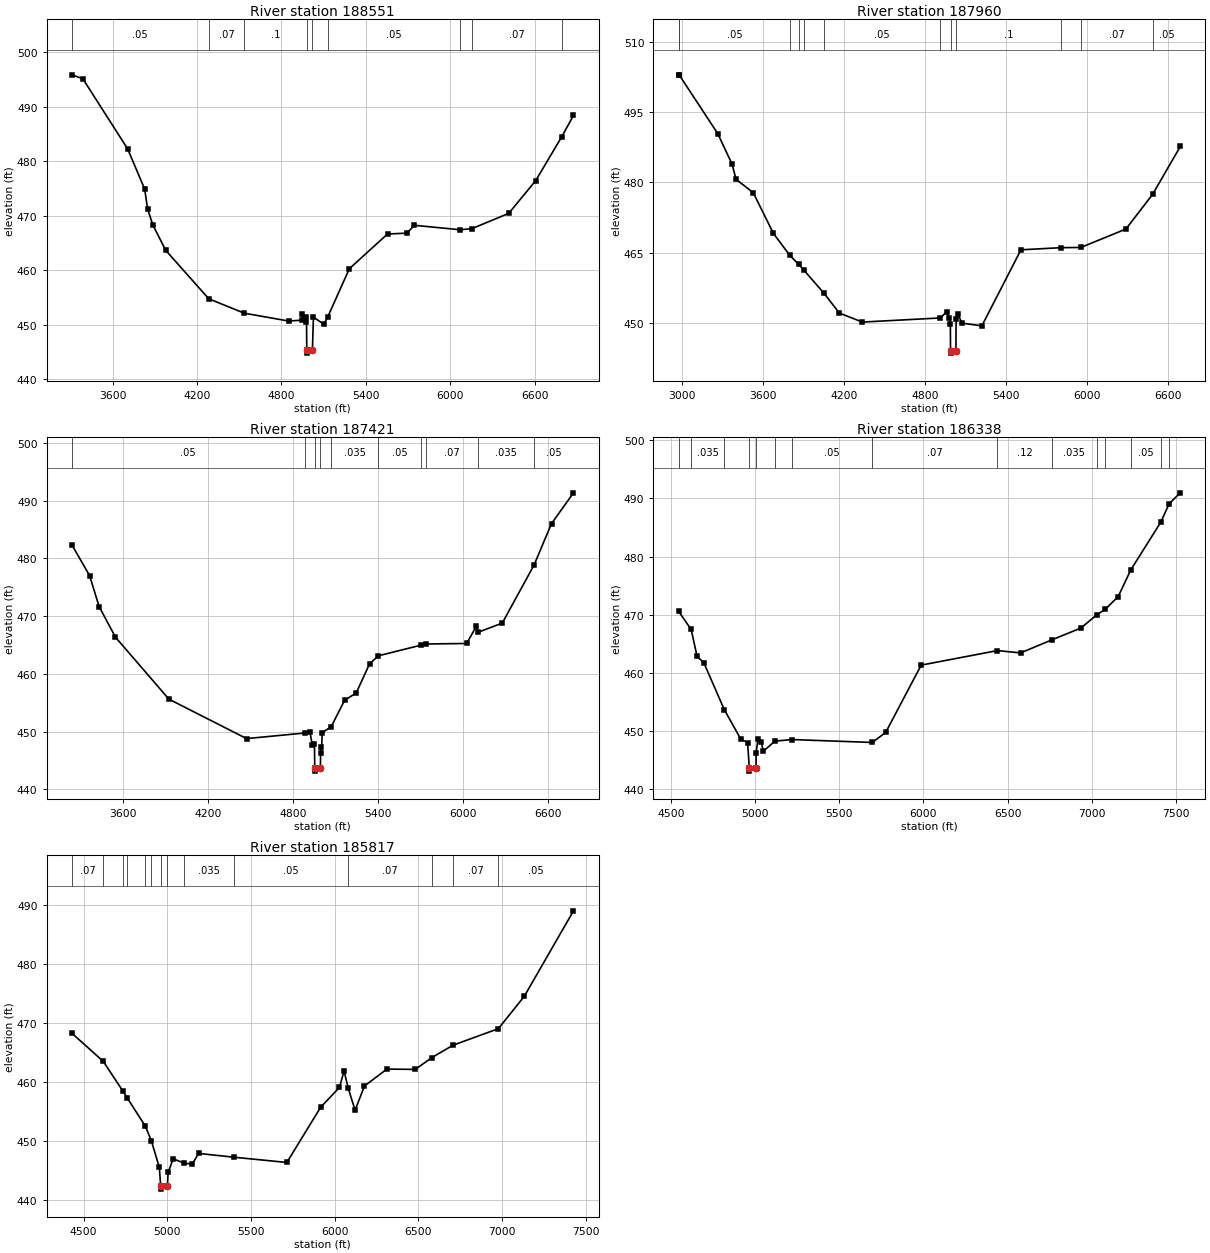
Type RM Length L Ch R = 1 ,188551  ,591,591,591
BEGIN DESCRIPTION:
SANDY FORK 142.0
END DESCRIPTION:
XS GIS Cut Line= 3
      2469075.03     13833474.97        2467975.       13834775.
      2466374.97     13835725.02
#Sta/Elev= 30
  3310.5  495.87  3389.1  495.15  3707.7  482.26  3828.6  474.87  3849.4  471.21
  3885.7  468.34    3978  463.63  4283.4  454.74  4535.1  452.09  4850.3  450.65
  4942.6   450.8  4949.2  451.97  4971.2  450.38  4977.8  451.32  4979.8  445.25
  4980.8  444.75  5019.8  445.25  5027.1  451.38  5101.2  450.03  5127.6  451.34
  5282.3  460.26  5553.2  466.63  5691.5  466.79  5744.2  468.23  6070.8  467.41
  6153.6  467.62  6414.4  470.43  6605.4  476.42  6791.6  484.53  6874.3  488.42
#Mann= 9 ,-1 , 0
  3310.5     .05       0  4283.4     .07       0  4535.1      .1       0
  4979.8     .05       0  5019.8      .1       0  5127.6     .05       0
  6070.8    .035       0  6153.6     .07       0  6791.6     .05       0
Bank Sta=4979.8,5019.8
XS Rating Curve= 0 ,0
Exp/Cntr=0.3,0.1

Type RM Length L Ch R = 1 ,187960  ,539,539,539
BEGIN DESCRIPTION:
SANDY FORK 141.0
END DESCRIPTION:
XS GIS Cut Line= 3
      2469075.02     13833124.99        2467525.       13834425.
      2466375.03     13835674.97
#Sta/Elev= 30
  2972.3  503.01  2976.9  502.99  3263.1  490.43  3369.8  483.86  3398.4  480.67
  3525.9  477.82  3675.5  469.12  3797.3   464.4  3862.9  462.49  3903.3   461.2
  4051.3  456.29  4164.7  452.08  4335.1  450.15  4913.8  451.03  4959.5  452.32
  4981.6  451.04  4988.2  449.69  4989.2  444.01  4990.2  443.51  5029.2  444.01
  5030.8  450.79  5044.9  451.88  5073.3  449.92  5221.9  449.35  5511.7   465.6
  5806.7  466.05  5956.8  466.11  6290.3  470.04  6488.7  477.48  6693.8   487.7
#Mann= 12 ,-1 , 0
  2972.3     .07       0  2976.9     .05       0  3797.3    .035       0
  3862.9     .05       0  3903.3    .035       0  4051.3     .05       0
  4913.8      .1       0  4989.2     .05       0  5029.2      .1       0
  5806.7    .035       0  5956.8     .07       0  6488.7     .05       0
Bank Sta=4989.2,5029.2
XS Rating Curve= 0 ,0
Exp/Cntr=0.3,0.1

Type RM Length L Ch R = 1 ,187421  ,1083,1083,1083
BEGIN DESCRIPTION:
SANDY FORK 140.0
END DESCRIPTION:
XS GIS Cut Line= 3
      2468675.02     13833274.99        2467125.       13834125.
      2466274.98     13835675.04
#Sta/Elev= 30
  3242.1  482.36  3367.6  477.02    3435  471.64  3550.1  466.35  3926.4  455.63
  4473.9   448.8  4882.5  449.76  4920.3  449.98  4936.4  447.76  4952.5   447.8
  4954.3  443.67  4955.3  443.17  4994.3  443.67  4996.1  447.31  5001.8  446.32
    5007  449.83  5070.1  450.85  5164.9  455.44  5246.4  456.68  5340.6  461.74
  5403.2  463.13  5699.9  464.95  5737.1  465.17  6024.9  465.26  6093.4  468.26
  6105.6   467.2  6275.8  468.79  6499.8  478.84  6622.7     486  6777.7  491.33
#Mann= 10 ,-1 , 0
  3242.1     .05       0  4882.5     .07       0  4954.3     .05       0
  4994.3     .07       0  5070.1    .035       0  5403.2     .05       0
  5699.9    .035       0  5737.1     .07       0  6105.6    .035       0
  6499.8     .05       0
Bank Sta=4954.3,4994.3
XS Rating Curve= 0 ,0
Exp/Cntr=0.3,0.1

Type RM Length L Ch R = 1 ,186338  ,521,521,521
BEGIN DESCRIPTION:
SANDY FORK 139.0
END DESCRIPTION:
XS GIS Cut Line= 3
        2467025.       13832725.        2467025.       13833175.
      2466225.01     13835574.98
#Sta/Elev= 30
  4546.2   470.6  4620.9  467.47  4656.2  462.83  4696.2  461.75  4817.7  453.68
  4916.2  448.58  4956.2  448.03  4966.1  443.61  4967.1  443.11  5006.3  443.61
  5006.7  446.27  5017.3  448.57  5038.4  448.04  5048.9  446.51    5118  448.27
  5220.7  448.54  5696.9  448.04  5776.2  449.77    5987  461.34  6439.8  463.84
  6577.3  463.44  6761.9  465.67  6935.7  467.72  7028.7  469.96  7081.5  470.97
  7157.1  473.14  7231.7  477.71  7410.9  485.97  7459.9  489.11    7526  490.97
#Mann= 15 ,-1 , 0
  4546.2     .07       0  4620.9    .035       0  4817.7      .1       0
  4966.1     .05       0  5006.3      .1       0    5118    .035       0
  5220.7     .05       0  5696.9     .07       0  6439.8     .12       0
  6761.9    .035       0  7028.7     .05       0  7081.5    .035       0
  7231.7     .05       0  7410.9    .035       0  7459.9     .05       0
Bank Sta=4966.1,5006.3
XS Rating Curve= 0 ,0
Exp/Cntr=0.3,0.1

Type RM Length L Ch R = 1 ,185817  ,538,538,538
BEGIN DESCRIPTION:
SANDY FORK 138.0
END DESCRIPTION:
XS GIS Cut Line= 3
      2466975.01     13832674.99        2466575.       13833075.
        2466175.       13835475.
#Sta/Elev= 30
  4429.3  468.28  4617.8  463.49  4734.1  458.51  4761.2   457.3  4869.4  452.51
  4904.6   450.1  4952.6  445.58  4960.8  442.38  4961.8  441.88    5001  442.38
  5005.1   444.7  5035.5  447.01  5101.4  446.27  5149.6  446.12  5187.6  447.92
  5399.2  447.28  5714.8  446.39  5917.5  455.76  6029.1  459.08  6056.9  461.89
  6081.8  458.93  6122.8  455.24  6178.6  459.33  6312.9  462.19  6482.7  462.14
  6581.8  464.14  6707.9  466.23    6979  469.03  7134.1  474.51  7428.1  488.97
#Mann= 14 ,-1 , 0
  4429.3     .07       0  4617.8     .12       0  4734.1     .07       0
  4761.2     .12       0  4869.4     .07       0  4904.6      .1       0
  4960.8     .05       0    5001      .1       0  5101.4    .035       0
  5399.2     .05       0  6081.8     .07       0  6581.8     .12       0
  6707.9     .07       0    6979     .05       0
Bank Sta=4960.8,5001
XS Rating Curve= 0 ,0
Exp/Cntr=0.3,0.1