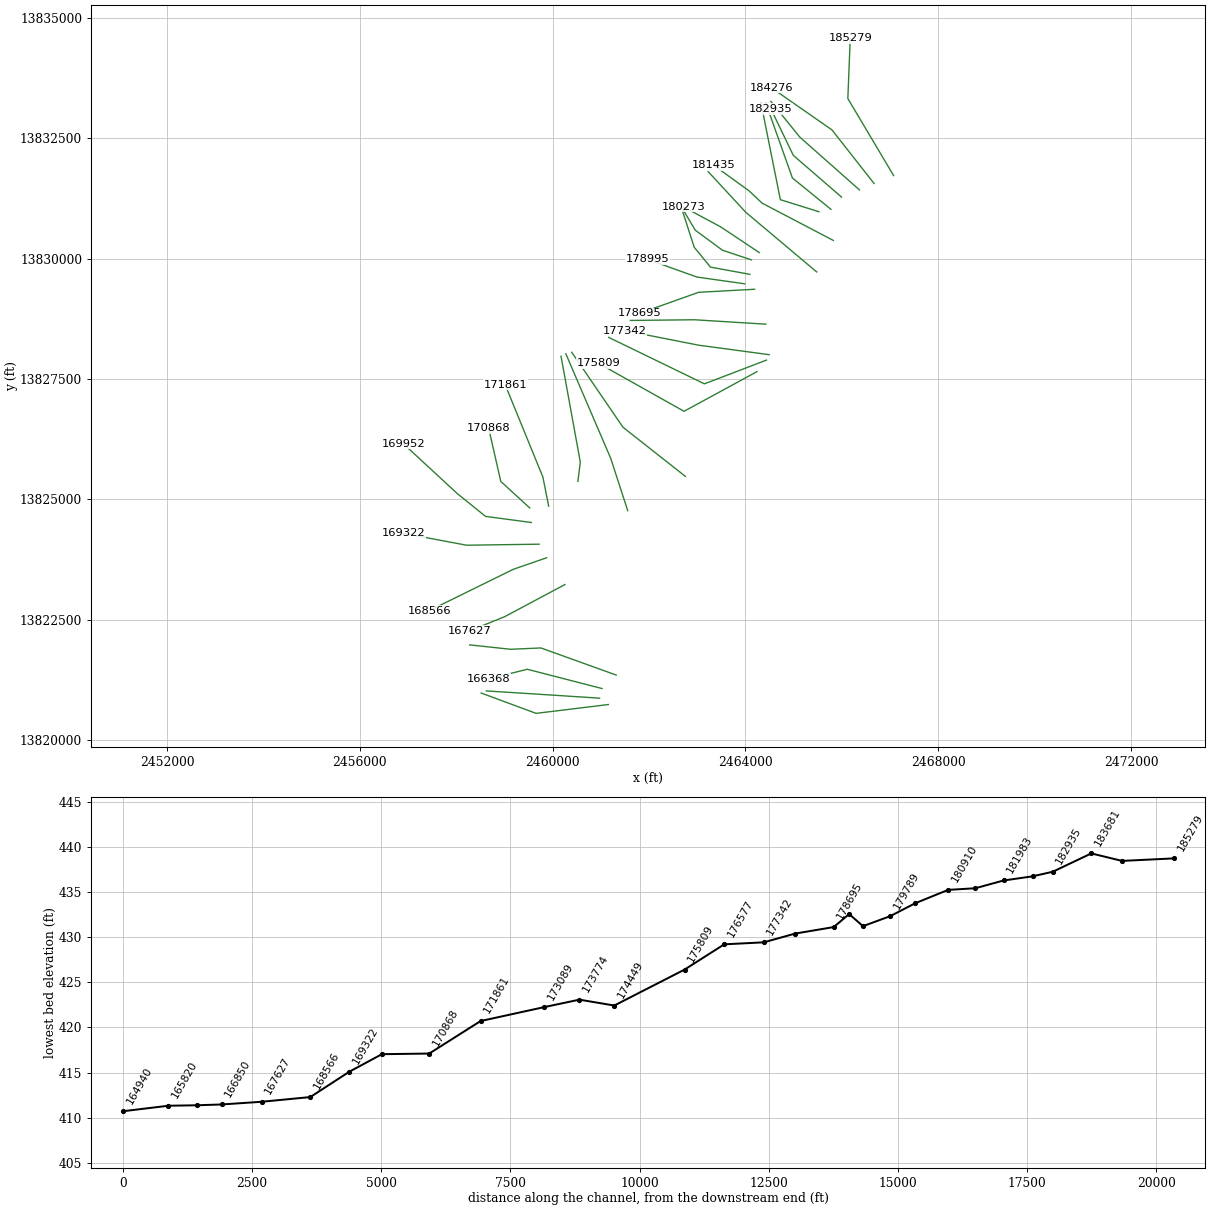
HEC-RAS study SANDY FORK.prj: SANDY FORK Base Level Engineering

--- SANDY FORK.g01 (geometry) --- (continued)

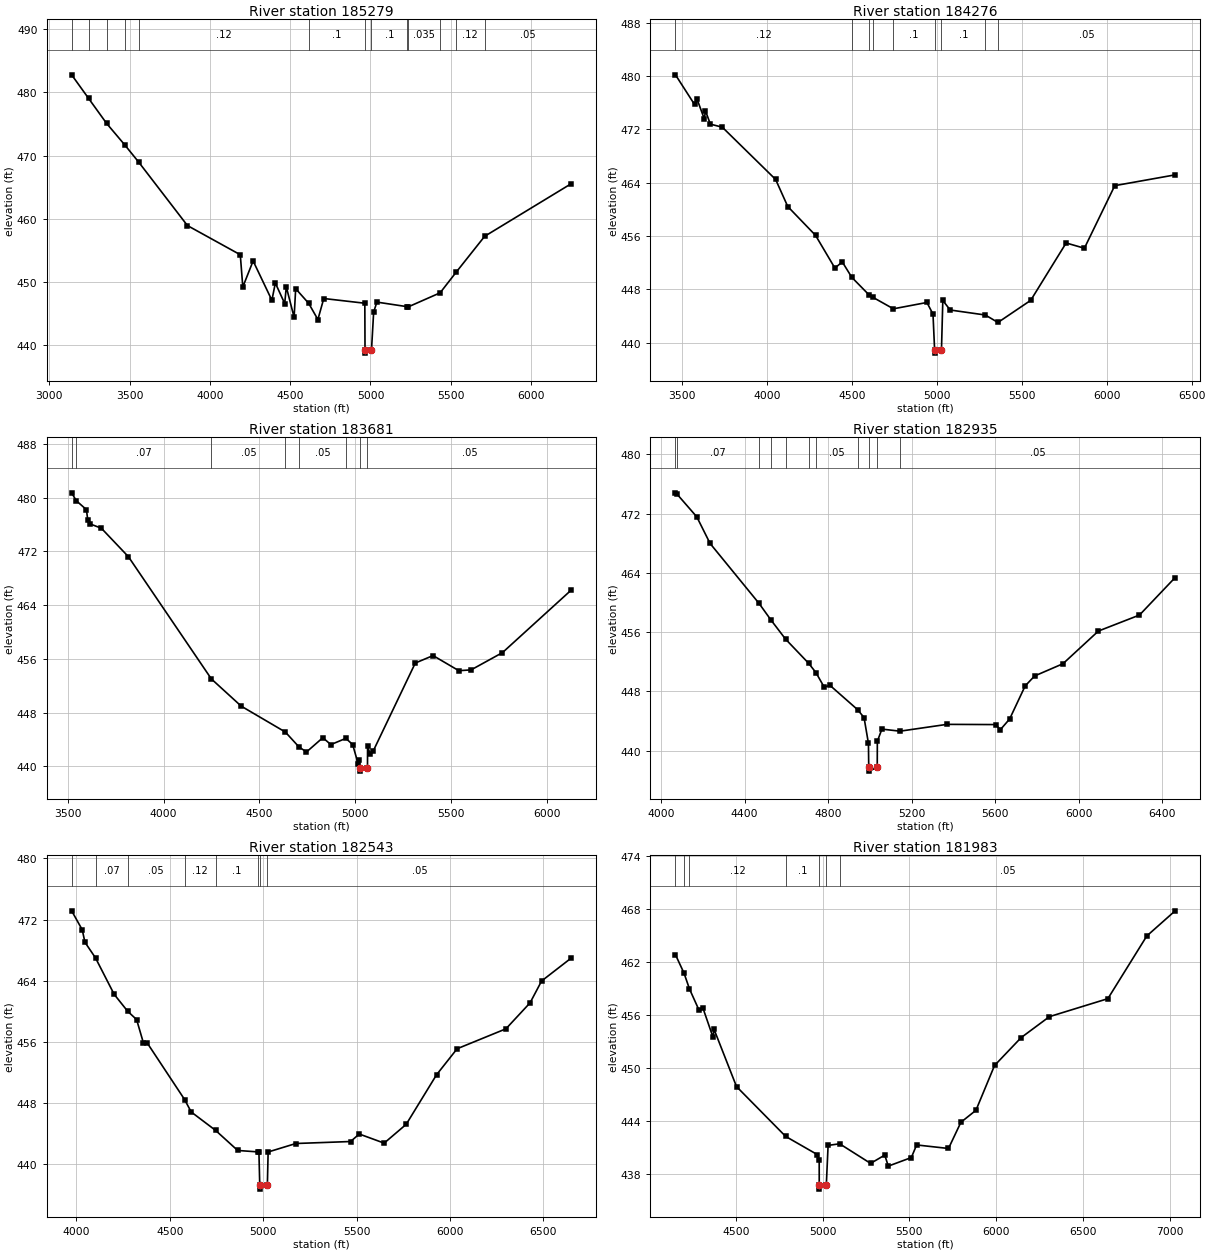
Type RM Length L Ch R = 1 ,185279  ,1003,1003,1003
BEGIN DESCRIPTION:
SANDY FORK 137.0
END DESCRIPTION:
XS GIS Cut Line= 3
      2467075.02     13831724.97        2466125.       13833325.
        2466175.     13834574.98
#Sta/Elev= 30
  3139.1  482.79  3244.5  479.06    3357  475.09  3469.6   471.7  3555.6     469
  3860.2  458.92  4189.3   454.3    4205  449.19  4269.2  453.32  4386.1  447.09
  4407.6  449.82    4466  446.57  4475.8  449.22  4524.5  444.39  4534.3  448.92
  4614.9  446.62  4672.6  444.04  4709.2  447.37  4964.9  446.62  4966.1  439.22
  4967.1  438.72  5006.4  439.22  5019.9  445.22  5039.9   446.8    5230  446.07
  5236.6  446.06  5433.8  448.27  5532.3  451.49  5711.2  457.22  6250.9  465.56
#Mann= 13 ,-1 , 0
  3139.1    .035       0  3244.5     .07       0    3357     .12       0
  3469.6     .07       0  3555.6     .12       0  4614.9      .1       0
  4966.1     .05       0  5006.4      .1       0    5230     .05       0
  5236.6    .035       0  5433.8     .05       0  5532.3     .12       0
  5711.2     .05       0
Bank Sta=4966.1,5006.4
XS Rating Curve= 0 ,0
Exp/Cntr=0.3,0.1

Type RM Length L Ch R = 1 ,184276  ,595,595,595
BEGIN DESCRIPTION:
SANDY FORK 136.0
END DESCRIPTION:
XS GIS Cut Line= 3
      2466668.81      13831561.3      2465795.97     13832673.48
      2464543.01     13833546.33
#Sta/Elev= 30
  3462.1   480.2  3574.2  475.75  3588.7  476.58    3632  473.57  3638.4  474.82
  3667.3   472.8  3737.8  472.34  4051.5   464.5  4122.9  460.44  4286.5  456.11
  4400.4   451.2  4443.7  452.13  4499.9  449.81    4602  447.16  4622.3  446.84
  4744.6  445.09  4941.9  446.04  4977.7  444.29  4987.2  438.94  4988.2  438.44
  5027.6  438.94  5035.5  446.34  5078.9  444.91  5285.7  444.16    5360  443.04
  5552.8  446.36  5761.3  454.97  5868.7  454.18  6047.5  463.57  6402.9  465.19
#Mann= 9 ,-1 , 0
  3462.1     .12       0  4499.9     .07       0    4602     .12       0
  4622.3     .07       0  4744.6      .1       0  4987.2     .05       0
  5027.6      .1       0  5285.7     .12       0    5360     .05       0
Bank Sta=4987.2,5027.6
XS Rating Curve= 0 ,0
Exp/Cntr=0.3,0.1

Type RM Length L Ch R = 1 ,183681  ,746,746,746
BEGIN DESCRIPTION:
E20698
END DESCRIPTION:
XS GIS Cut Line= 3
       2466366.1      13831427.6      2465127.27     13832525.66
      2464529.48      13833264.1
#Sta/Elev= 30
    3521  480.72    3545  479.55    3598  478.22  3604.7  476.74  3618.9  476.07
  3675.8  475.45  3817.1   471.2  4249.6     453  4405.1  448.95  4635.4  445.09
  4705.8  442.89  4745.5  442.12  4830.8  444.25  4872.6  443.22  4950.8  444.15
  4986.3  443.23  5014.8  440.38  5021.5  440.88  5022.9  439.77  5023.9  439.27
  5063.6  439.77  5064.1  442.95  5078.3  441.75  5092.6  442.21  5312.9  455.37
  5405.6  456.48  5539.9  454.23  5603.9  454.35  5767.4  456.92  6126.5  466.25
#Mann= 8 ,-1 , 0
    3521     .12       0    3545     .07       0  4249.6     .05       0
  4635.4      .1       0  4705.8     .05       0  4950.8      .1       0
  5022.9     .05       0  5063.6     .05       0
Bank Sta=5022.9,5063.6
XS Rating Curve= 0 ,0
Exp/Cntr=0.3,0.1

Type RM Length L Ch R = 1 ,182935  ,392,392,392
BEGIN DESCRIPTION:
E20697
END DESCRIPTION:
XS GIS Cut Line= 3
      2465993.08     13831279.74      2464993.53     13832145.56
      2464529.48      13833108.8
#Sta/Elev= 30
  4069.5  474.79    4077  474.61  4171.5  471.55  4235.1  467.96  4469.5  459.87
  4527.6  457.59  4596.4  455.05  4706.9  451.79  4741.9  450.53  4781.3  448.57
  4808.7  448.82  4941.3  445.53  4972.1  444.46  4993.1  440.98  4994.5  437.74
  4995.5  437.24  5035.2  437.74  5035.7  441.27  5057.6  442.91  5144.1  442.63
  5369.1  443.55    5602  443.52  5624.4  442.83  5668.8  444.27  5743.3  448.74
  5788.5  450.08  5924.1  451.73  6093.7  456.14  6290.4   458.3  6461.1  463.36
#Mann= 11 ,-1 , 0
  4069.5     .12       0    4077     .07       0  4469.5     .05       0
  4527.6     .07       0  4596.4     .05       0  4706.9     .07       0
  4741.9     .05       0  4941.3      .1       0  4994.5     .05       0
  5035.2      .1       0  5144.1     .05       0
Bank Sta=4994.5,5035.2
XS Rating Curve= 0 ,0
Exp/Cntr=0.3,0.1

Type RM Length L Ch R = 1 ,182543  ,560,560,560
BEGIN DESCRIPTION:
SANDY FORK 135.0
END DESCRIPTION:
XS GIS Cut Line= 3
      2465774.97     13831025.02        2464975.       13831675.
      2464425.01     13833224.97
#Sta/Elev= 30
  3974.2  473.15  4030.9  470.67  4045.3  469.04  4101.9  466.99  4201.9  462.22
  4274.4     460    4322  458.92  4358.5  455.86  4379.3  455.84  4579.1  448.45
  4614.2  446.83  4745.2  444.41  4863.2  441.79  4973.1   441.6  4976.9  441.57
  4981.4  437.23  4982.4  436.73  5022.1  437.23  5026.2  441.59  5174.7   442.7
  5467.5  442.96  5514.3  443.94  5647.4  442.75  5765.5  445.21  5928.1   451.7
  6038.1   455.1  6299.5  457.71  6428.7  461.11  6490.5  463.97  6649.6  466.98
#Mann= 8 ,-1 , 0
  3974.2     .12       0  4101.9     .07       0  4274.4     .05       0
  4579.1     .12       0  4745.2      .1       0  4973.1     .05       0
  4981.4     .05       0  5022.1     .05       0
Bank Sta=4981.4,5022.1
XS Rating Curve= 0 ,0
Exp/Cntr=0.3,0.1

Type RM Length L Ch R = 1 ,181983  ,548,548,548
BEGIN DESCRIPTION:
SANDY FORK 134.0
END DESCRIPTION:
XS GIS Cut Line= 3
      2465525.04     13830974.99        2464725.       13831225.
        2464325.       13833225.
#Sta/Elev= 30
  4152.6  462.85  4201.9  460.76  4233.3  458.97  4288.8  456.54  4309.8  456.86
    4369  453.48  4374.2  454.42  4504.1   447.9    4787  442.25  4969.3  440.19
  4980.3  439.53  4980.6  436.77  4981.6  436.27  5021.4  436.77  5031.6  441.23
  5098.1  441.41  5276.3  439.19  5357.9  440.13  5378.3  438.88  5510.9  439.85
  5541.5  441.28    5725  440.88  5796.4  443.85  5883.1  445.21  5990.2  450.29
  6143.2  453.45  6306.3  455.83  6642.9  457.87  6867.2  464.98  7030.4  467.83
#Mann= 7 ,-1 , 0
  4152.6     .12       0  4201.9     .07       0  4233.3     .12       0
    4787      .1       0  4980.6     .05       0  5021.4      .1       0
  5098.1     .05       0
Bank Sta=4980.6,5021.4
XS Rating Curve= 0 ,0
Exp/Cntr=0.3,0.1

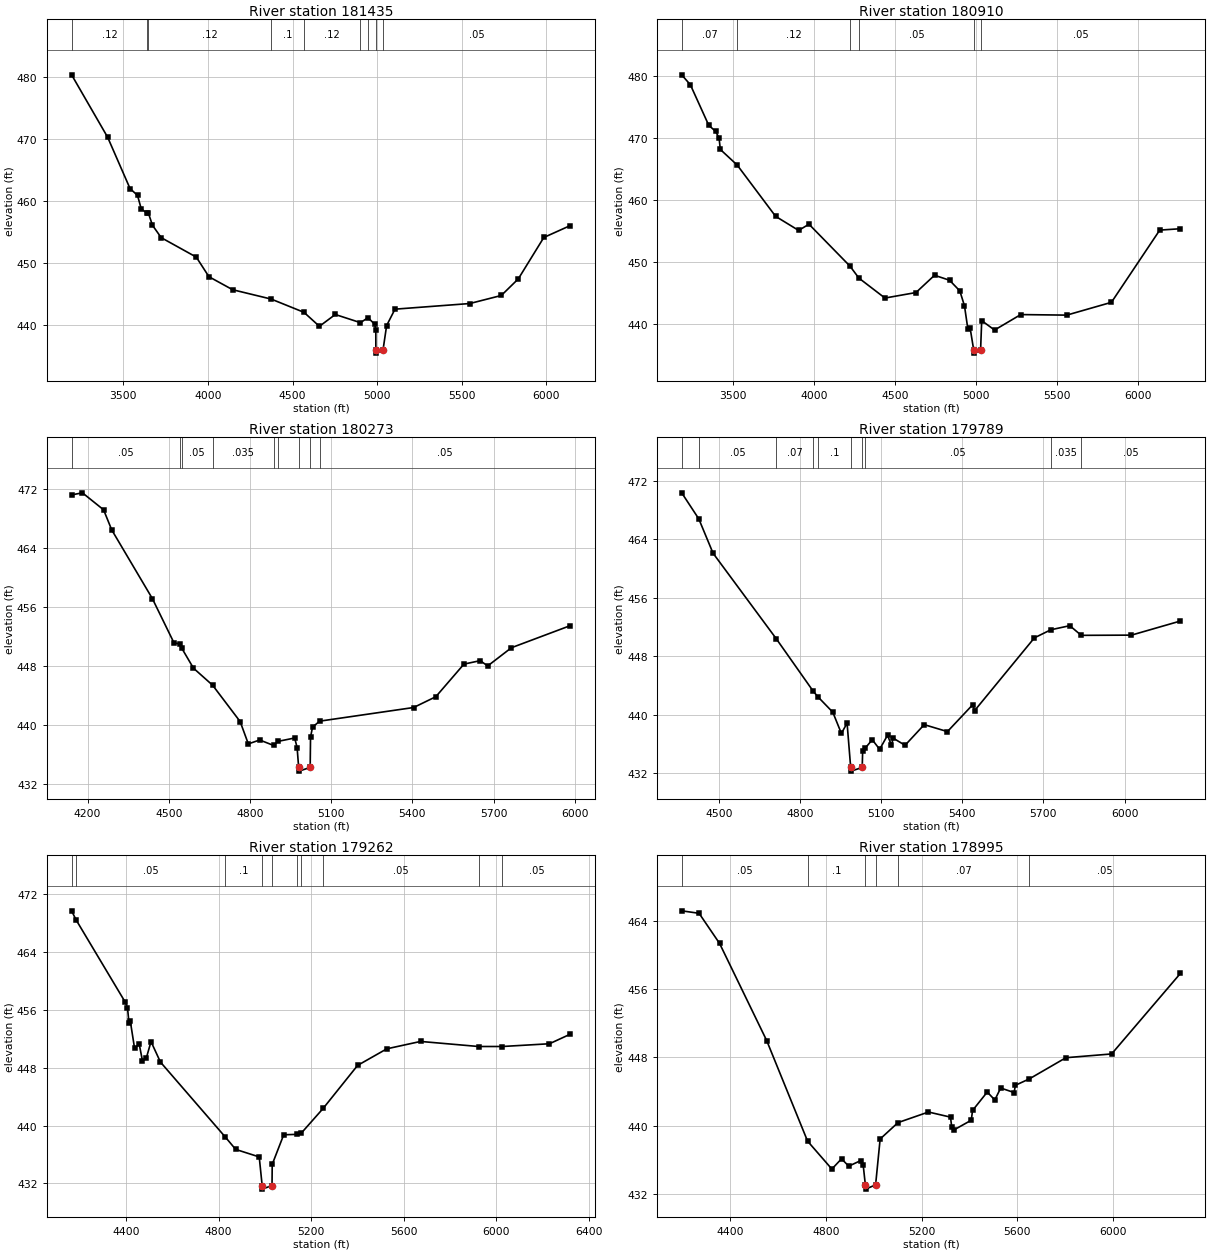
Type RM Length L Ch R = 1 ,181435  ,525,525,525
BEGIN DESCRIPTION:
E20696
END DESCRIPTION:
XS GIS Cut Line= 4
      2465824.15     13830378.76      2464345.94     13831153.06
      2464078.46     13831406.47      2463340.63     13831940.51
#Sta/Elev= 30
  3193.9  480.36  3406.9  470.28  3539.3  461.99  3583.4  460.89  3605.5   458.7
  3641.8  457.99  3647.7  458.03  3671.7  456.07  3723.5  454.06  3930.8  450.92
  4005.7  447.75  4145.8  445.65  4373.5  444.14  4567.4     442  4658.5  439.74
  4752.4  441.65  4901.3  440.33  4945.7  441.14    4985  440.08  4991.9  439.21
  4992.2  435.91  4993.2  435.41  5034.5  435.91  5055.8  439.86  5105.2  442.51
  5547.1  443.42  5733.5  444.72    5834   447.4  5984.9  454.09  6141.9  456.02
#Mann= 9 ,-1 , 0
  3193.9     .12       0  3641.8      .1       0  3647.7     .12       0
  4373.5      .1       0  4567.4     .12       0  4901.3      .1       0
  4945.7     .05       0  4992.2     .05       0  5034.5     .05       0
Bank Sta=4992.2,5034.5
XS Rating Curve= 0 ,0
Exp/Cntr=0.3,0.1

Type RM Length L Ch R = 1 ,180910  ,637,637,637
BEGIN DESCRIPTION:
E20695
END DESCRIPTION:
XS GIS Cut Line= 3
      2465479.23     13829724.14      2464008.07     13830963.01
      2463226.77     13831807.66
#Sta/Elev= 30
  3186.3   480.2  3239.8  478.59  3352.9  472.05  3395.8  471.05  3416.7  469.96
  3424.4  468.14  3528.3  465.62  3765.2  457.33  3906.9  455.06  3970.7  456.06
  4223.6  449.28  4278.5  447.35  4438.9  444.13  4630.1  445.02  4744.4  447.81
  4836.8  447.01  4900.5  445.28  4929.1  442.86  4949.9  439.12  4964.2  439.23
  4985.9  435.73  4986.9  435.23  5028.3  435.73  5035.2  440.48  5114.4  438.96
  5275.8  441.46  5559.2  441.37  5834.7  443.44  6132.4  455.11  6260.2  455.33
#Mann= 6 ,-1 , 0
  3186.3     .07       0  3528.3     .12       0  4223.6      .1       0
  4278.5     .05       0  4985.9     .05       0  5028.3     .05       0
Bank Sta=4985.9,5028.3
XS Rating Curve= 0 ,0
Exp/Cntr=0.3,0.1

Type RM Length L Ch R = 1 ,180273  ,484,484,484
BEGIN DESCRIPTION:
E20694
END DESCRIPTION:
XS GIS Cut Line= 3
      2464289.65     13830125.36      2463487.19     13830660.34
      2462712.88     13831075.65
#Sta/Elev= 30
  4140.9  471.18  4180.9  471.46  4259.1  469.16  4289.1  466.44  4439.3  457.13
  4519.1  451.14  4541.3  450.97  4547.1  450.46  4591.2   447.7    4662  445.39
  4763.8  440.46  4793.9  437.44  4835.9  437.97  4887.3  437.23  4903.4  437.78
  4965.1  438.24  4974.2  436.95  4979.9  434.25  4980.9  433.75  5022.5  434.25
  5023.8  438.36  5031.2  439.71  5057.4  440.52  5404.7  442.37  5486.7  443.83
  5590.7  448.25  5650.8  448.72  5678.4     448  5766.1  450.47    5984  453.47
#Mann= 9 ,-1 , 0
  4140.9     .05       0  4541.3    .035       0  4547.1     .05       0
    4662    .035       0  4887.3     .05       0  4903.4    .035       0
  4979.9    .035       0  5022.5    .035       0  5057.4     .05       0
Bank Sta=4979.9,5022.5
XS Rating Curve= 0 ,0
Exp/Cntr=0.3,0.1

Type RM Length L Ch R = 1 ,179789  ,527,527,527
BEGIN DESCRIPTION:
SANDY FORK 131.0
END DESCRIPTION:
XS GIS Cut Line= 4
      2464124.98     13829975.01        2463525.       13830175.
      2462959.73     13830591.21       2462699.6      13831029.3
#Sta/Elev= 30
  4362.9  470.34  4426.1  466.78  4478.8  462.09  4712.2  450.42  4849.6  443.21
  4867.8  442.42  4921.5  440.37  4953.2  437.47  4974.3  438.88  4987.6  432.82
  4988.6  432.32  5030.2  432.82  5031.9  435.06    5041  435.45  5067.4  436.61
  5094.7   435.3  5123.8  437.22  5138.4  435.85  5144.6  436.83  5188.6  435.85
  5259.5  438.67  5345.2  437.72  5439.2  441.41  5445.4  440.57  5666.8  450.53
  5727.5  451.63  5797.6  452.19    5840  450.87  6025.6   450.9  6206.8  452.83
#Mann= 10 ,-1 , 0
  4362.9    .035       0  4426.1     .05       0  4712.2     .07       0
  4849.6     .05       0  4867.8      .1       0  4987.6     .05       0
  5030.2      .1       0    5041     .05       0  5727.5    .035       0
    5840     .05       0
Bank Sta=4987.6,5030.2
XS Rating Curve= 0 ,0
Exp/Cntr=0.3,0.1

Type RM Length L Ch R = 1 ,179262  ,267,267,267
BEGIN DESCRIPTION:
SANDY FORK 130.0
END DESCRIPTION:
XS GIS Cut Line= 4
      2464092.58     13829674.87        2463275.       13829825.
      2462938.05     13830237.65      2462694.48     13830991.07
#Sta/Elev= 30
  4164.5  469.67  4183.3  468.45  4395.9  457.07    4406   456.3  4412.7   454.1
  4417.8  454.51  4436.6  450.68  4456.9  451.22  4470.9  448.92  4487.4  449.32
  4507.7   451.6  4548.4  448.77  4828.8  438.41  4873.7   436.7  4975.4  435.66
  4988.1  431.71  4989.1  431.21  5030.7  431.71  5031.6  434.63  5081.2  438.72
  5140.3  438.78  5158.1  438.98  5251.6  442.36  5400.7  448.31  5526.9   450.6
  5672.8  451.62  5923.5  450.92    6026  450.92  6229.8   451.3  6320.3  452.63
#Mann= 10 ,-1 , 0
  4164.5    .035       0  4183.3     .05       0  4828.8      .1       0
  4988.1     .05       0  5030.7      .1       0  5140.3     .05       0
  5158.1     .07       0  5251.6     .05       0  5923.5    .035       0
    6026     .05       0
Bank Sta=4988.1,5030.7
XS Rating Curve= 0 ,0
Exp/Cntr=0.3,0.1

Type RM Length L Ch R = 1 ,178995  ,300,300,300
BEGIN DESCRIPTION:
E20693
END DESCRIPTION:
XS GIS Cut Line= 3
      2463986.96     13829477.79      2462994.46     13829618.57
      2461973.84     13829984.58
#Sta/Elev= 30
  4196.2  465.14  4268.9  464.85  4354.5  461.33  4551.7  449.95  4722.8  438.17
  4824.4   434.9  4864.8   436.1  4895.1  435.24  4945.6   435.9  4955.7  435.32
  4964.5  433.05  4965.5  432.55  5007.4  433.05  5026.4  438.42  5101.1  440.34
  5228.6  441.58  5320.8  440.98  5326.1  439.77  5336.2   439.5  5407.7  440.62
    5413  441.76  5474.5  443.92  5506.1  442.99  5530.7  444.39  5586.9  443.86
  5592.2  444.71  5650.6  445.46  5803.6  447.94  5994.8  448.38  6282.9  457.82
#Mann= 6 ,-1 , 0
  4196.2     .05       0  4722.8      .1       0  4964.5     .05       0
  5007.4      .1       0  5101.1     .07       0  5650.6     .05       0
Bank Sta=4964.5,5007.4
XS Rating Curve= 0 ,0
Exp/Cntr=0.3,0.1

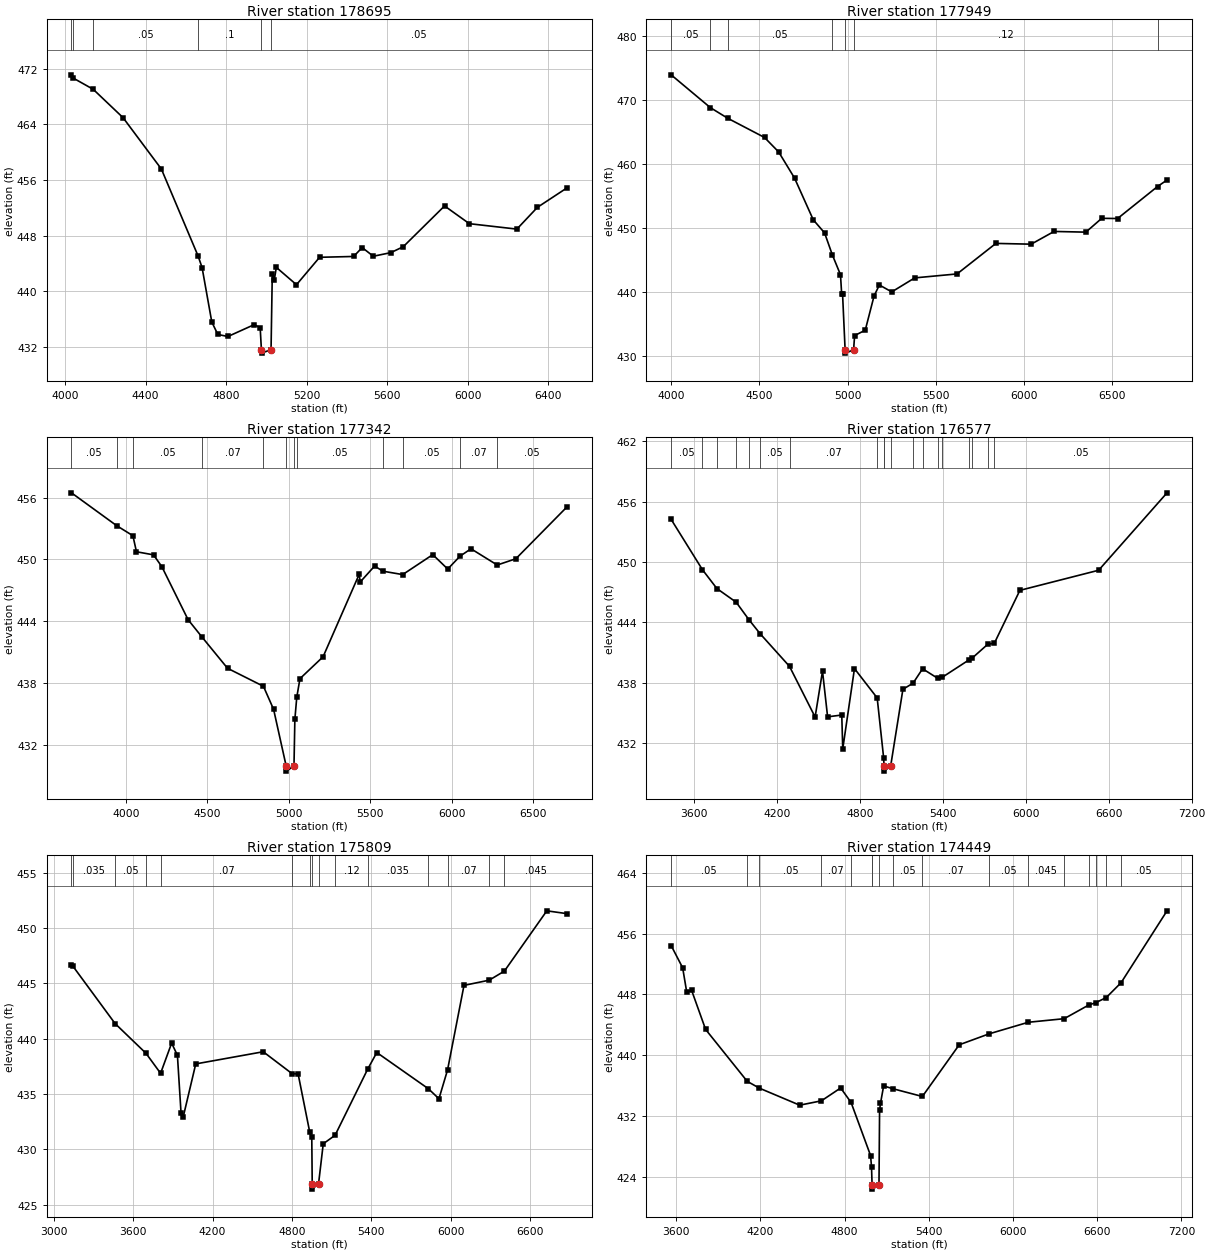
Type RM Length L Ch R = 1 ,178695  ,746,746,746
BEGIN DESCRIPTION:
E20692
END DESCRIPTION:
XS GIS Cut Line= 3
      2464191.04     13829365.16      2463029.66     13829301.82
      2461804.89     13828865.41
#Sta/Elev= 30
  4032.2   471.1  4041.7  470.62  4140.2  469.02  4288.6  464.94  4478.9  457.56
  4660.6  445.11    4681  443.41  4729.3  435.58  4759.3  433.79  4809.4   433.5
  4939.6   435.2  4969.6  434.78  4975.7  431.61  4976.7  431.11  5023.6  431.61
  5029.7  442.42  5039.7  441.64  5049.9  443.43  5149.9  440.94  5264.8  444.88
  5433.8     445  5476.3  446.28  5531.5  445.03  5618.7  445.55  5680.3   446.4
  5885.5  452.26  6008.7  449.71  6244.7  448.93  6346.8  452.06  6495.5  454.89
#Mann= 6 ,-1 , 0
  4032.2     .12       0  4041.7    .035       0  4140.2     .05       0
  4660.6      .1       0  4975.7     .05       0  5023.6     .05       0
Bank Sta=4975.7,5023.6
XS Rating Curve= 0 ,0
Exp/Cntr=0.3,0.1

Type RM Length L Ch R = 1 ,177949  ,607,607,607
BEGIN DESCRIPTION:
E20691
END DESCRIPTION:
XS GIS Cut Line= 3
      2464423.38     13828640.15      2462945.19     13828731.66
      2461614.79     13828717.58
#Sta/Elev= 30
  3999.9  473.89  4221.9  468.77  4320.8   467.1  4529.3   464.1  4609.4  461.84
  4699.6  457.75  4805.7  451.23  4869.9  449.18    4914  445.74  4960.1  442.64
  4966.8   439.6  4971.8  439.65  4986.3  430.89  4987.3  430.39  5034.2  430.89
  5040.3  433.14  5100.4  433.97  5150.5  439.33  5180.5  441.04  5250.7  439.96
  5380.9  442.15  5621.1  442.77  5841.1  447.54  6041.1  447.42  6171.1  449.41
  6351.2   449.3  6441.2  451.46  6531.2  451.43  6757.5  456.43  6811.4  457.45
#Mann= 7 ,-1 , 0
  3999.9     .05       0  4221.9    .035       0  4320.8     .05       0
    4914     .12       0  4986.3     .05       0  5034.2     .12       0
  6757.5     .07       0
Bank Sta=4986.3,5034.2
XS Rating Curve= 0 ,0
Exp/Cntr=0.3,0.1

Type RM Length L Ch R = 1 ,177342  ,765,765,765
BEGIN DESCRIPTION:
E20690
END DESCRIPTION:
XS GIS Cut Line= 3
      2464493.73     13828006.65      2463029.66     13828203.74
      2461495.21     13828506.41
#Sta/Elev= 30
  3667.4  456.48  3944.4  453.29  4044.2  452.31    4066  450.75  4170.6  450.45
  4221.7   449.3  4382.5  444.15  4466.3  442.49  4624.7  439.42  4844.7  437.67
  4907.2  435.42  4984.1  429.92  4985.1  429.42  5032.1  429.92  5037.5  434.45
  5049.1  436.59  5068.7  438.41  5210.6  440.54  5432.6  448.58  5437.7   447.8
  5526.6  449.36  5577.6  448.86  5698.7  448.53  5883.3  450.47    5975  449.07
  6050.5  450.32  6117.7  451.04  6278.6  449.46  6392.9  450.07  6708.7  455.15
#Mann= 12 ,-1 , 0
  3667.4     .05       0  3944.4    .035       0  4044.2     .05       0
  4466.3     .07       0  4844.7      .1       0  4984.1     .05       0
  5032.1      .1       0  5049.1     .05       0  5577.6     .07       0
  5698.7     .05       0  6050.5     .07       0  6278.6     .05       0
Bank Sta=4984.1,5032.1
XS Rating Curve= 0 ,0
Exp/Cntr=0.3,0.1

Type RM Length L Ch R = 1 ,176577  ,768,768,768
BEGIN DESCRIPTION:
E20689
END DESCRIPTION:
XS GIS Cut Line= 3
      2464437.43     13827894.02      2463149.32      13827401.3
       2461164.3     13828365.65
#Sta/Elev= 30
  3435.4  454.24    3662  449.23  3766.3  447.36  3905.8     446  3998.6  444.25
  4079.3  442.86  4291.4  439.62  4476.5  434.58  4530.1  439.14  4566.9   434.6
  4669.3  434.78  4676.4  431.41  4761.2   439.4  4925.4  436.48  4972.3   430.5
  4974.7   429.7  4975.7   429.2  5022.8   429.7  5111.5  437.34    5185  437.95
  5253.6  439.38  5364.7  438.42  5397.7  438.55  5586.8  440.24  5610.4  440.42
  5724.4  441.81  5773.1  441.93  5957.3  447.18  6526.9  449.18  7021.4  456.88
#Mann= 19 ,-1 , 0
  3435.4     .05       0    3662    .035       0  3766.3     .07       0
  3905.8     .05       0  3998.6     .07       0  4079.3     .05       0
  4291.4     .07       0  4925.4     .12       0  4972.3     .07       0
  4974.7     .05       0  5022.8     .07       0    5185    .035       0
  5253.6     .07       0  5364.7    .035       0  5397.7     .05       0
  5586.8    .035       0  5610.4     .05       0  5724.4     .07       0
  5773.1     .05       0
Bank Sta=4974.7,5022.8
XS Rating Curve= 0 ,0
Exp/Cntr=0.3,0.1

Type RM Length L Ch R = 1 ,175809  ,1360,1360,1360
BEGIN DESCRIPTION:
E20688
END DESCRIPTION:
XS GIS Cut Line= 3
      2464240.36      13827654.7      2462726.98     13826831.14
      2460960.22     13827823.63
#Sta/Elev= 30
  3132.7  446.66    3144  446.55  3462.4  441.37  3696.2  438.68  3806.6  436.87
  3890.1   439.6  3933.8   438.5  3961.3  433.26  3977.5  432.92  4072.4  437.72
  4582.5  438.82  4800.6  436.84  4846.5  436.81  4934.8  431.52  4949.7  431.08
    4953   426.9    4954   426.4  5001.1   426.9  5036.4   430.5    5126  431.27
  5372.5  437.25  5441.3  438.75  5831.8  435.47  5911.2  434.57  5976.3  437.18
  6100.6  444.82  6291.1  445.29    6406  446.11  6726.8  451.56  6882.1   451.3
#Mann= 15 ,-1 , 0
  3132.7     .05       0    3144    .035       0  3462.4     .05       0
  3696.2    .035       0  3806.6     .07       0  4800.6    .035       0
  4934.8      .1       0    4953     .05       0  5001.1      .1       0
    5126     .12       0  5372.5    .035       0  5831.8     .05       0
  5976.3     .07       0  6291.1     .05       0    6406    .045       0
Bank Sta=4953,5001.1
XS Rating Curve= 0 ,0
Exp/Cntr=0.3,0.1

Type RM Length L Ch R = 1 ,174449  ,675,675,675
BEGIN DESCRIPTION:
E20687
END DESCRIPTION:
XS GIS Cut Line= 3
       2462755.1     13825479.69      2461459.97     13826500.31
      2460397.08     13828055.92
#Sta/Elev= 30
  3564.4  454.42  3646.5   451.5  3675.4  448.31  3710.6  448.52    3810   443.4
  4106.6  436.58  4193.6  435.68  4480.3  433.45    4635  434.02  4772.2  435.71
  4846.3  433.81  4985.4  426.83    4992  425.34  4996.2  422.92  4997.2  422.42
  5045.2  422.92  5049.5  432.79  5055.9  433.68  5078.4  435.98  5146.3   435.6
  5354.3  434.59  5616.8  441.38  5829.7  442.82  6108.9  444.34  6364.6  444.81
    6541  446.62    6588   446.9  6663.9  447.58  6770.2  449.54  7097.4  458.98
#Mann= 17 ,-1 , 0
  3564.4     .05       0  4106.6     .07       0  4193.6     .05       0
    4635     .07       0  4846.3      .1       0    4992     .07       0
  4996.2     .05       0  5045.2     .07       0  5146.3     .05       0
  5354.3     .07       0  5829.7     .05       0  6108.9    .045       0
  6364.6     .07       0    6541    .045       0    6588     .05       0
  6663.9     .12       0  6770.2     .05       0
Bank Sta=4996.2,5045.2
XS Rating Curve= 0 ,0
Exp/Cntr=0.3,0.1

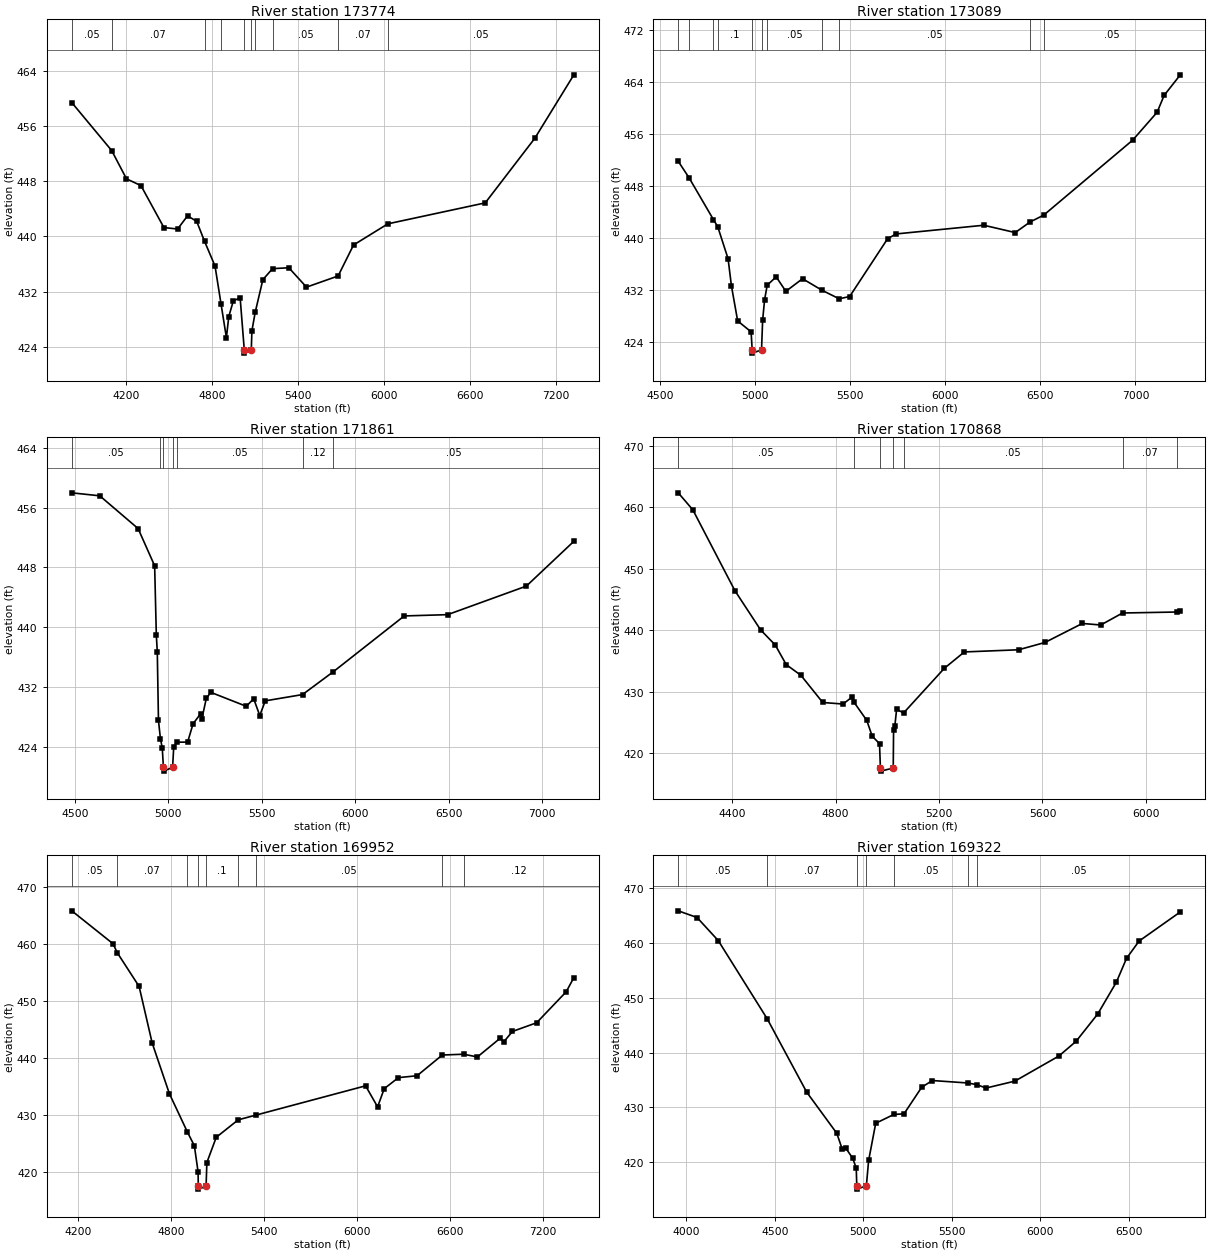
Type RM Length L Ch R = 1 ,173774  ,685,685,685
BEGIN DESCRIPTION:
SANDY FORK 129.0
END DESCRIPTION:
XS GIS Cut Line= 3
      2461558.51     13824768.74      2461206.57     13825852.73
        2460275.     13828025.01
#Sta/Elev= 30
  3819.4  459.41  4097.8  452.45  4201.2  448.35  4302.3  447.36  4462.2  441.28
    4558  441.07  4627.2  442.98  4691.1  442.18  4745.6   439.3    4819   435.7
    4861  430.19  4898.4  425.31  4914.9  428.37  4946.8  430.65  4994.2   431.1
    5023  423.57    5024  423.07    5072  423.57  5076.5  426.33  5099.2  428.98
  5152.7  433.72  5220.2  435.32    5334  435.45  5457.2  432.64  5677.8  434.26
  5785.4  438.75  6024.8  441.82  6704.5  444.86  7050.7  454.24  7322.7  463.43
#Mann= 10 ,-1 , 0
  3819.4     .05       0  4097.8     .07       0  4745.6     .12       0
    4861      .1       0    5023     .05       0    5072      .1       0
  5099.2     .07       0  5220.2     .05       0  5677.8     .07       0
  6024.8     .05       0
Bank Sta=5023,5072
XS Rating Curve= 0 ,0
Exp/Cntr=0.3,0.1

Type RM Length L Ch R = 1 ,173089  ,1228,1228,1228
BEGIN DESCRIPTION:
SANDY FORK 128.0
END DESCRIPTION:
XS GIS Cut Line= 3
        2460525.       13825375.        2460575.       13825775.
        2460175.     13827975.02
#Sta/Elev= 30
  4596.5  451.79  4653.7  449.24  4781.5  442.81  4804.3   441.7  4858.5  436.78
  4876.2  432.58  4908.9   427.2  4979.5  425.52  4985.2  422.74  4986.2  422.24
  5034.3  422.74  5040.3  427.36  5050.4  430.46  5064.2  432.71  5111.4  433.99
  5162.2  431.76  5249.9   433.7  5354.4  431.89  5442.7  430.61  5497.6  430.96
  5697.1  439.86  5741.6   440.6  6202.8  441.94  6367.9  440.81  6445.9  442.44
  6517.3  443.49  6985.4  455.05  7113.7  459.34  7150.6  461.94  7235.7  465.11
#Mann= 11 ,-1 , 0
  4596.5     .07       0  4653.7      .1       0  4781.5     .07       0
  4804.3      .1       0  4985.2     .05       0  5034.3      .1       0
  5064.2     .05       0  5354.4    .035       0  5442.7     .05       0
  6445.9     .07       0  6517.3     .05       0
Bank Sta=4985.2,5034.3
XS Rating Curve= 0 ,0
Exp/Cntr=0.3,0.1

Type RM Length L Ch R = 1 ,171861  ,993,993,993
BEGIN DESCRIPTION:
SANDY FORK 127.0
END DESCRIPTION:
XS GIS Cut Line= 3
      2459918.44     13824860.22      2459798.77     13825465.58
      2459017.47     13827380.12
#Sta/Elev= 30
    4484     458  4633.7   457.6  4838.7  453.21  4927.2  448.22  4936.2   438.9
  4941.3  436.71  4947.6  427.49    4958  425.07    4968   423.8    4974   421.2
    4975   420.7  5023.2   421.2  5029.1  423.88  5045.6  424.58  5103.5  424.59
  5132.9  427.06  5173.9  428.41  5179.3  427.66  5203.4  430.45  5227.4  431.26
  5417.3  429.39  5456.9   430.4  5489.3  428.15  5518.8  430.12  5717.9  430.96
  5883.1  434.03  6261.9   441.5  6493.7  441.67    6915   445.5  7168.9   451.5
#Mann= 7 ,-1 , 0
    4484     .05       0    4958      .1       0    4974     .05       0
  5023.2      .1       0  5045.6     .05       0  5717.9     .12       0
  5883.1     .05       0
Bank Sta=4974,5023.2
XS Rating Curve= 0 ,0
Exp/Cntr=0.3,0.1

Type RM Length L Ch R = 1 ,170868  ,916,916,916
BEGIN DESCRIPTION:
SANDY FORK 126.0
END DESCRIPTION:
XS GIS Cut Line= 3
      2459524.99     13824825.01        2458925.       13825375.
      2458674.99     13826475.02
#Sta/Elev= 30
  4191.2  462.35  4247.6  459.59  4410.4  446.44  4509.7  440.07  4566.4  437.61
  4608.9  434.42  4665.7  432.68  4750.2  428.26  4828.5  428.01  4863.6  429.14
  4870.3  428.35  4920.3  425.36  4941.3   422.8  4969.7  421.56  4973.2   417.6
  4974.2   417.1  5022.8   417.6  5024.1  423.72  5029.2   424.5  5035.9  427.17
  5062.7  426.55  5220.5  433.82  5297.9  436.48  5507.6  436.83  5609.7  438.02
  5754.3  441.11  5825.5  440.86  5909.7  442.81  6119.1  442.97  6133.2  443.17
#Mann= 7 ,-1 , 0
  4191.2     .05       0  4870.3      .1       0  4973.2     .05       0
  5022.8      .1       0  5062.7     .05       0  5909.7     .07       0
  6119.1     .12       0
Bank Sta=4973.2,5022.8
XS Rating Curve= 0 ,0
Exp/Cntr=0.3,0.1

Type RM Length L Ch R = 1 ,169952  ,630,630,630
BEGIN DESCRIPTION:
E20686
END DESCRIPTION:
XS GIS Cut Line= 4
      2459559.46     13824522.36      2458609.19     13824649.06
      2458024.96     13825120.67      2456900.69     13826160.62
#Sta/Elev= 30
  4158.6   465.9  4425.4  460.11  4451.7  458.57  4593.3  452.62  4677.6  442.69
  4788.6   433.8  4904.7  427.08    4950  424.64  4974.1  420.03  4975.3  417.53
  4976.3  417.03  5025.6  417.53  5030.7   421.7  5091.2  426.13  5233.1   429.2
  5344.7  430.01  6055.3  435.17  6132.9  431.47  6175.5  434.67  6267.3  436.61
  6387.5  436.94  6550.4  440.58  6688.1  440.72    6777  440.24  6925.6  443.56
  6946.6  442.87  7003.3  444.72  7159.2  446.24  7350.3  451.69  7399.6  454.17
#Mann= 9 ,-1 , 0
  4158.6     .05       0  4451.7     .07       0  4904.7      .1       0
  4975.3     .05       0  5025.6      .1       0  5233.1     .07       0
  5344.7     .05       0  6550.4     .07       0  6688.1     .12       0
Bank Sta=4975.3,5025.6
XS Rating Curve= 0 ,0
Exp/Cntr=0.3,0.1

Type RM Length L Ch R = 1 ,169322  ,756,756,756
BEGIN DESCRIPTION:
E20685
END DESCRIPTION:
XS GIS Cut Line= 3
      2459721.38     13824071.87      2458215.01     13824050.75
       2456905.8     13824297.11
#Sta/Elev= 30
  3953.8  465.88  4060.2  464.66  4180.2  460.44  4457.1  446.16  4680.3  432.78
  4850.3  425.28  4880.3  422.45  4900.3  422.61  4940.3  420.72  4960.3  418.92
  4963.2  415.69  4964.3  415.09  5017.4  415.69  5030.3  420.32  5070.3  427.11
    5173  428.72  5230.3  428.83  5330.3  433.68  5390.3  434.91  5591.3  434.46
  5641.1  434.16  5694.4  433.54  5857.2   434.8  6105.8  439.38  6203.1  442.06
  6325.9  447.07  6430.8  452.85  6488.4   457.2  6559.3  460.36  6792.5  465.68
#Mann= 7 ,-1 , 0
  3953.8     .05       0  4457.1     .07       0  4963.2     .05       0
  5017.4     .07       0    5173     .05       0  5591.3      .1       0
  5641.1     .05       0
Bank Sta=4963.2,5017.4
XS Rating Curve= 0 ,0
Exp/Cntr=0.3,0.1

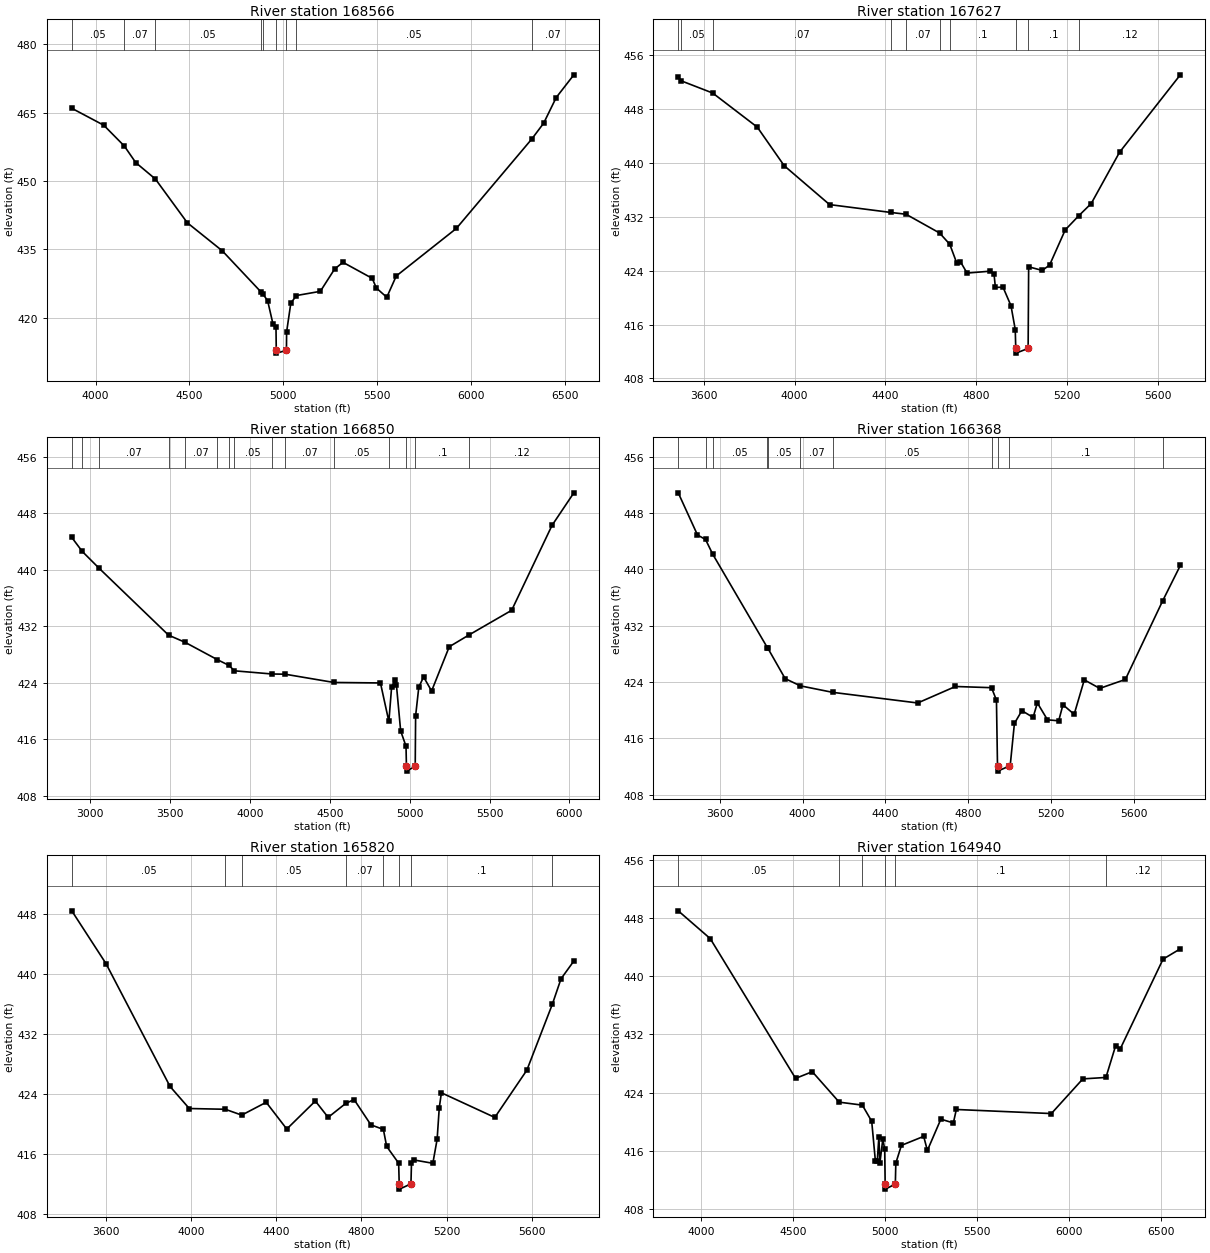
Type RM Length L Ch R = 1 ,168566  ,939,939,939
BEGIN DESCRIPTION:
SANDY FORK 125.0
END DESCRIPTION:
XS GIS Cut Line= 3
      2459876.23     13823790.32      2459186.38     13823550.99
      2457440.75     13822692.25
#Sta/Elev= 30
  3872.7  465.93  4043.4  462.21  4152.7  457.66  4213.6  454.03  4318.3  450.43
  4488.5  440.84    4675  434.69  4879.6  425.75    4893  425.14  4916.5  423.76
  4944.6  418.72    4961  417.96  4962.5  412.88  4963.6  412.28  5016.7  412.88
  5017.6  416.93  5040.1  423.24  5070.1   424.9  5197.4  425.82  5273.1  430.69
  5317.7  432.18  5473.7  428.67    5496  426.54  5551.4  424.52  5601.9  429.18
  5922.1   439.6  6324.8  459.23  6387.5  462.67  6454.4  468.29  6548.3  473.26
#Mann= 9 ,-1 , 0
  3872.7     .05       0  4152.7     .07       0  4318.3     .05       0
  4879.6     .12       0    4893      .1       0  4962.5     .05       0
  5016.7      .1       0  5070.1     .05       0  6324.8     .07       0
Bank Sta=4962.5,5016.7
XS Rating Curve= 0 ,0
Exp/Cntr=0.3,0.1

Type RM Length L Ch R = 1 ,167627  ,777,777,777
BEGIN DESCRIPTION:
SANDY FORK 124.0
END DESCRIPTION:
XS GIS Cut Line= 3
      2460256.28     13823234.22      2459003.37     13822565.53
      2458271.49     13822269.96
#Sta/Elev= 30
  3488.3  452.68  3499.1  452.16  3639.9  450.32  3836.3  445.26  3954.5  439.55
  4154.3  433.78  4425.3  432.61  4490.8  432.35  4638.4  429.57  4683.2   427.9
  4713.9  425.12    4730  425.32  4759.3  423.63  4861.7  423.91    4878  423.49
    4884   421.5  4917.5  421.54  4952.6  418.79  4971.4  415.26  4973.6  412.46
  4974.8  411.76  5028.1  412.46  5030.4  424.56  5090.1  424.02  5122.4  424.81
  5191.4  430.03  5251.5  432.15  5305.8  433.94  5430.2  441.53  5697.8  453.02
#Mann= 10 ,-1 , 0
  3488.3     .07       0  3499.1     .05       0  3639.9     .07       0
  4425.3     .05       0  4490.8     .07       0  4638.4     .12       0
  4683.2      .1       0  4973.6     .05       0  5028.1      .1       0
  5251.5     .12       0
Bank Sta=4973.6,5028.1
XS Rating Curve= 0 ,0
Exp/Cntr=0.3,0.1

Type RM Length L Ch R = 1 ,166850  ,482,482,482
BEGIN DESCRIPTION:
E20684
END DESCRIPTION:
XS GIS Cut Line= 4
      2461319.22     13821354.82      2459756.54     13821917.95
      2459130.07     13821889.79      2458279.22     13821981.21
#Sta/Elev= 30
  2884.1  444.56  2950.2  442.57    3056  440.18  3490.2  430.72  3593.3  429.71
  3796.5  427.24  3868.5  426.44  3902.3  425.67  4137.5  425.22  4219.7  425.19
  4525.2  424.02    4817  423.95  4869.7  418.49    4887   423.4  4907.1  424.36
  4917.1  423.65  4943.5  417.16  4977.1  414.98  4979.7  412.16  4980.9  411.46
  5034.7  412.16  5037.2  419.29  5057.2  423.37  5087.2   424.8  5137.3  422.81
  5247.8  429.08  5374.5  430.79  5638.6  434.24  5891.4  446.27    6028  450.88
#Mann= 15 ,-1 , 0
  2884.1     .05       0  2950.2    .035       0    3056     .07       0
  3490.2     .05       0  3593.3     .07       0  3796.5     .05       0
  3868.5     .07       0  3902.3     .05       0  4137.5     .12       0
  4219.7     .07       0  4525.2     .05       0  4869.7      .1       0
  4979.7     .05       0  5034.7      .1       0  5374.5     .12       0
Bank Sta=4979.7,5034.7
XS Rating Curve= 0 ,0
Exp/Cntr=0.3,0.1

Type RM Length L Ch R = 1 ,166368  ,548,548,548
BEGIN DESCRIPTION:
SANDY FORK 123.0
END DESCRIPTION:
XS GIS Cut Line= 3
      2461025.02     13821074.99        2459475.       13821475.
      2458675.02     13821275.01
#Sta/Elev= 30
  3399.2  450.86  3492.2  444.88  3531.1  444.24  3565.6  442.16  3829.6   428.9
  3831.7  428.83  3915.6   424.5  3989.1  423.47    4145  422.55  4555.9  421.04
  4738.3  423.38  4912.6  423.21  4936.4  421.44  4941.5  412.07  4942.7  411.37
  4996.6  412.07  5002.6  412.09  5023.2  418.14  5059.3  419.95  5113.4  418.99
    5134  421.05    5183  418.65  5237.1  418.51  5257.7  420.79  5311.8  419.43
  5360.8  424.32  5435.5  423.11  5559.2  424.38  5738.8   435.5  5824.6  440.55
#Mann= 11 ,-1 , 0
  3399.2     .05       0  3531.1     .07       0  3565.6     .05       0
  3829.6     .07       0  3831.7     .05       0  3989.1     .07       0
    4145     .05       0  4912.6      .1       0  4941.5     .05       0
  4996.6      .1       0  5738.8     .12       0
Bank Sta=4941.5,4996.6
XS Rating Curve= 0 ,0
Exp/Cntr=0.3,0.1

Type RM Length L Ch R = 1 ,165820  ,880,880,880
BEGIN DESCRIPTION:
SANDY FORK 122.0
END DESCRIPTION:
XS GIS Cut Line= 3
      2460975.05       13820875.        2459425.       13820975.
      2458625.03       13821025.
#Sta/Elev= 30
  3441.8  448.47  3602.2  441.43  3902.8  425.02    3993  422.08  4161.7  421.98
  4238.9   421.2  4353.7  422.91  4450.2  419.34  4584.2  423.08  4644.3   420.9
  4726.6  422.76  4765.8  423.28  4844.8   419.9  4903.3  419.29  4918.7  417.02
    4975  414.78  4977.5  412.02  4978.7  411.32  5032.6  412.02  5035.1  414.81
  5045.2  415.22  5135.3  414.77  5155.4  417.98  5165.4  422.18  5175.4  424.18
  5425.9  420.89  5576.2   427.2  5695.6  435.99  5736.5   439.4  5796.6  441.77
#Mann= 8 ,-1 , 0
  3441.8     .05       0  4161.7     .12       0  4238.9     .05       0
  4726.6     .07       0  4903.3      .1       0  4977.5     .05       0
  5032.6      .1       0  5695.6     .12       0
Bank Sta=4977.5,5032.6
XS Rating Curve= 0 ,0
Exp/Cntr=0.3,0.1

Type RM Length L Ch R = 1 ,164940  ,808,808,808
BEGIN DESCRIPTION:
E20683
END DESCRIPTION:
XS GIS Cut Line= 3
      2461157.34     13820742.45        2459658.     13820559.43
      2458518.88     13820981.32
#Sta/Elev= 30
  3878.1  449.01  4051.7  445.19  4515.1  425.95  4605.8  426.87  4751.7  422.68
  4877.3  422.27  4928.2  420.05  4948.3  414.56  4958.4  414.55  4967.3  417.95
  4972.4  414.27  4988.6  417.59  4998.7  416.22  5001.3  411.41  5002.5  410.71
  5056.5  411.41  5059.1  414.29  5089.4  416.73  5210.3  417.97  5230.4  416.03
  5303.6  420.34  5371.4  419.82  5387.6  421.67  5903.4  421.11  6074.2  425.88
  6199.6  426.08  6252.1  430.44  6276.9  429.99  6509.6  442.36  6603.3  443.78
#Mann= 6 ,-1 , 0
  3878.1     .05       0  4751.7     .12       0  4877.3      .1       0
  5001.3     .05       0  5056.5      .1       0  6199.6     .12       0
Bank Sta=5001.3,5056.5
XS Rating Curve= 0 ,0
Exp/Cntr=0.3,0.1