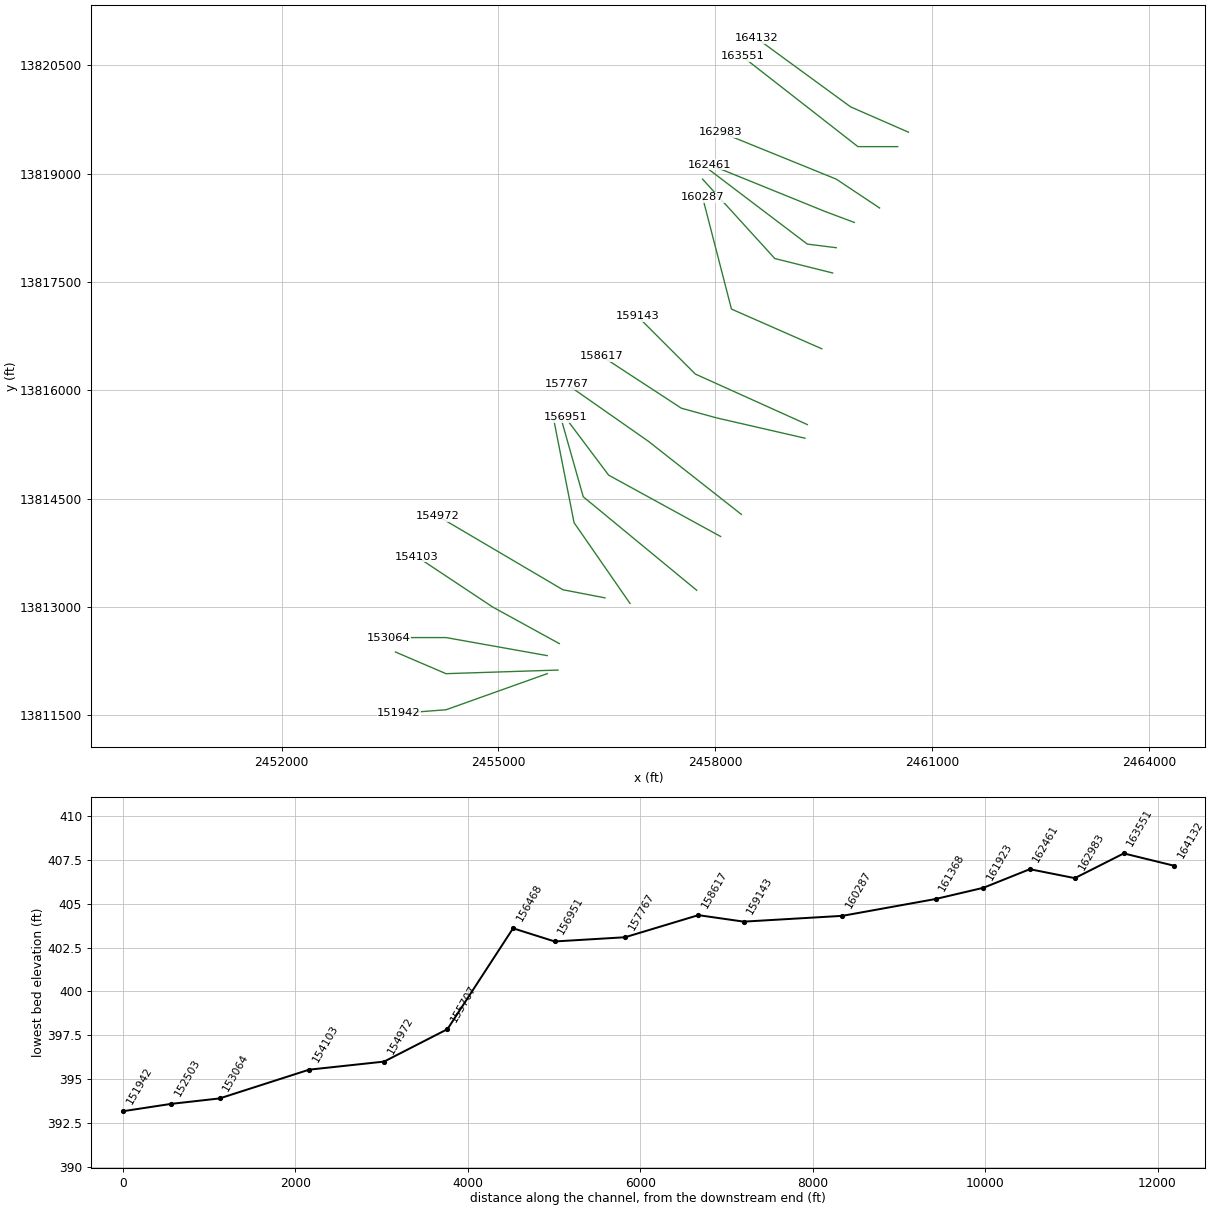
HEC-RAS study SANDY FORK.prj: SANDY FORK Base Level Engineering

--- SANDY FORK.g01 (geometry) --- (continued)

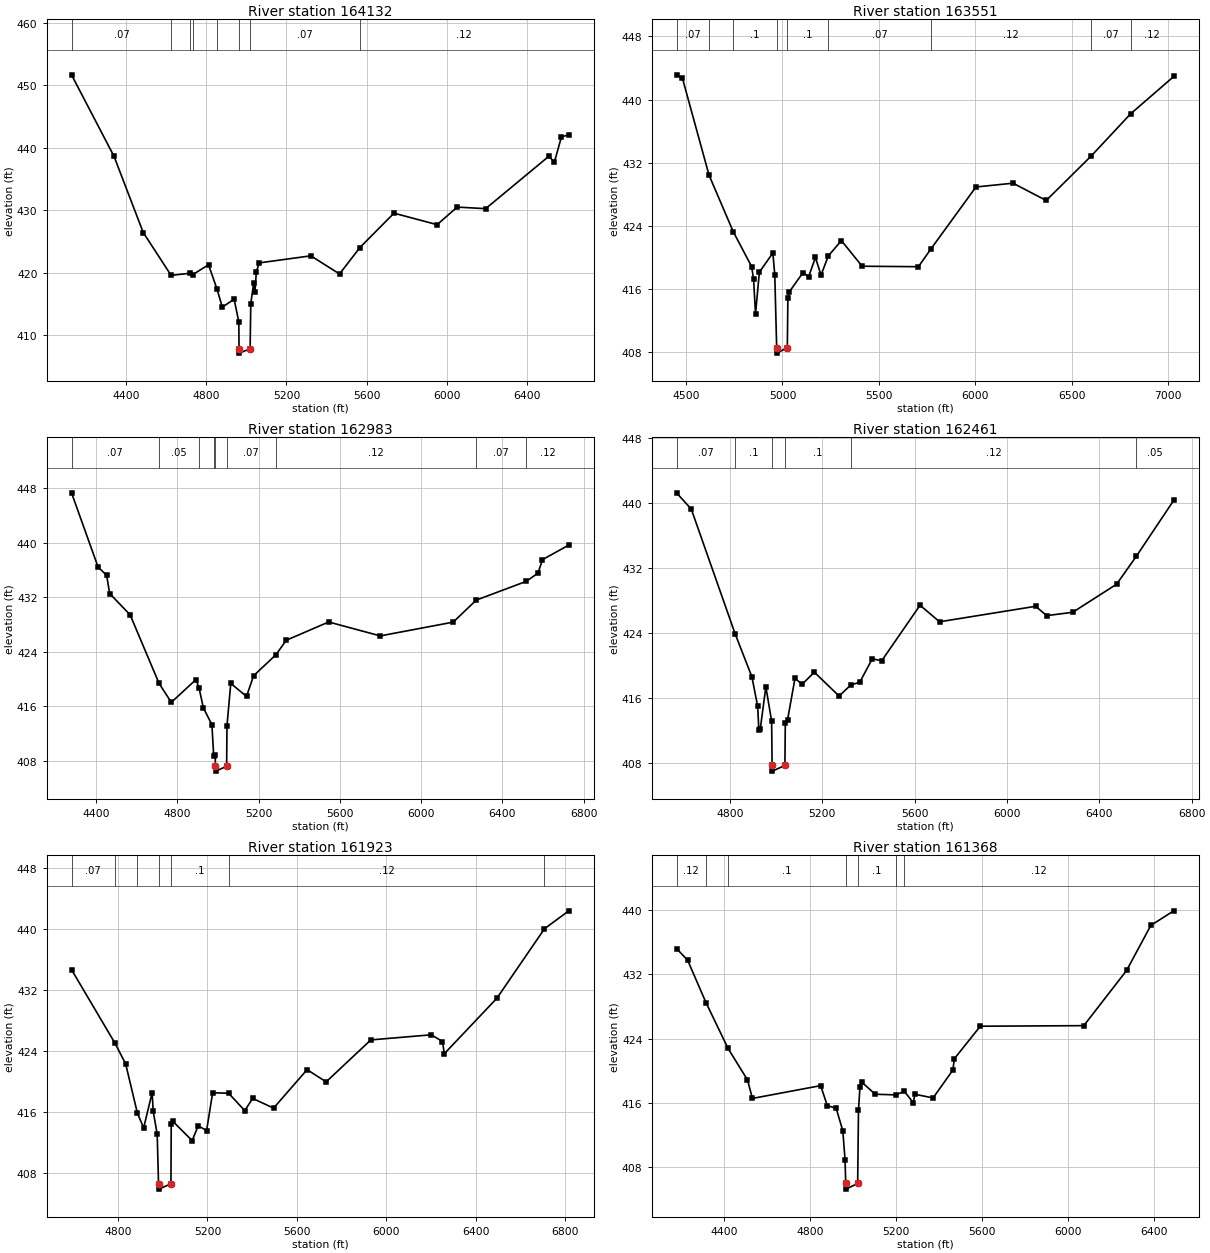
Type RM Length L Ch R = 1 ,164132  ,581,581,581
BEGIN DESCRIPTION:
SANDY FORK 121.0
END DESCRIPTION:
XS GIS Cut Line= 3
      2460674.96     13819575.02        2459875.       13819925.
        2458575.       13820875.
#Sta/Elev= 30
  4126.7  451.65  4339.1  438.61  4484.9  426.44  4624.1   419.6  4716.8  419.93
    4733  419.73  4810.8   421.3  4852.5  417.47  4879.8  414.52  4938.7  415.79
  4962.1  412.16  4963.3  407.87  4964.5  407.17  5018.6  407.87  5021.9  415.04
  5036.5  418.45  5042.7  416.92  5049.4  420.09  5063.6  421.59  5321.9  422.72
  5465.1  419.82  5566.7  424.04    5737  429.54  5952.4   427.7  6052.6  430.51
  6194.9  430.26  6510.7  438.64  6537.8  437.68  6573.3  441.72    6610  442.08
#Mann= 8 ,-1 , 0
  4126.7     .07       0  4624.1      .1       0  4716.8     .12       0
    4733      .1       0  4852.5     .07       0  4963.3     .05       0
  5018.6     .07       0  5566.7     .12       0
Bank Sta=4963.3,5018.6
XS Rating Curve= 0 ,0
Exp/Cntr=0.3,0.1

Type RM Length L Ch R = 1 ,163551  ,568,568,568
BEGIN DESCRIPTION:
SANDY FORK 120.0
END DESCRIPTION:
XS GIS Cut Line= 3
      2460524.99       13819375.        2459975.       13819375.
      2458374.99     13820625.01
#Sta/Elev= 30
  4450.1  443.13  4480.1  442.77  4618.9  430.42  4744.5  423.26  4840.1  418.83
  4850.1  417.23  4860.1  412.83  4880.1  418.13  4950.1  420.56  4960.1  417.79
  4969.9  408.57  4971.1  407.87  5025.2  408.57  5028.1  414.82  5036.3  415.66
  5106.8  418.08  5135.7  417.54    5171  419.99    5200  417.76  5238.1  420.19
  5305.8  422.13  5413.4  418.88  5705.5  418.82  5771.5  421.11    6004  428.92
  6196.6   429.4  6368.5  427.21  6602.3  432.85  6806.3  438.18  7030.5  442.92
#Mann= 9 ,-1 , 0
  4450.1     .07       0  4618.9     .12       0  4744.5      .1       0
  4969.9     .05       0  5025.2      .1       0  5238.1     .07       0
  5771.5     .12       0  6602.3     .07       0  6806.3     .12       0
Bank Sta=4969.9,5025.2
XS Rating Curve= 0 ,0
Exp/Cntr=0.3,0.1

Type RM Length L Ch R = 1 ,162983  ,522,522,522
BEGIN DESCRIPTION:
SANDY FORK 119.0
END DESCRIPTION:
XS GIS Cut Line= 3
      2460275.02     13818524.99        2459675.       13818925.
      2458075.03     13819574.99
#Sta/Elev= 30
  4278.6  447.29  4409.3   436.4  4451.4  435.19  4466.4  432.52  4567.1  429.39
  4709.5  419.33  4769.9  416.55  4891.6   419.9  4906.7  418.62  4927.6  415.75
  4969.7  413.28  4978.7  408.63  4986.2   408.8  4986.8  407.16    4988  406.46
  5042.2  407.16  5043.9  413.13  5062.6  419.33  5140.1  417.42  5175.1  420.46
  5285.1  423.54  5335.8  425.66  5544.6  428.34  5798.5   426.3  6157.8  428.32
    6271  431.55  6517.2   434.3  6575.4  435.52  6597.2  437.49  6726.7  439.62
#Mann= 9 ,-1 , 0
  4278.6     .07       0  4709.5     .05       0  4906.7      .1       0
  4978.7     .07       0  4986.8     .05       0  5042.2     .07       0
  5285.1     .12       0    6271     .07       0  6517.2     .12       0
Bank Sta=4986.8,5042.2
XS Rating Curve= 0 ,0
Exp/Cntr=0.3,0.1

Type RM Length L Ch R = 1 ,162461  ,538,538,538
BEGIN DESCRIPTION:
SANDY FORK 118.0
END DESCRIPTION:
XS GIS Cut Line= 3
      2459924.99       13818325.        2459525.       13818475.
      2457924.99     13819125.01
#Sta/Elev= 30
  4568.3  441.26  4632.4  439.25  4822.4  423.88  4894.9  418.59  4919.8  414.98
  4925.2  412.05  4931.4   412.2  4955.4  417.37  4980.4  413.12  4982.5  407.67
  4983.7  406.97  5037.9  407.67  5039.7  412.92  5049.5  413.32  5081.8  418.42
  5111.9  417.66  5165.5  419.16  5272.6  416.22  5323.3  417.58  5362.5  417.93
  5416.4  420.81  5457.3  420.57  5623.4  427.41  5707.9  425.37  6124.1  427.28
    6172  426.13  6284.7  426.54  6474.9     430  6560.4  433.44  6722.5  440.34
#Mann= 6 ,-1 , 0
  4568.3     .07       0  4822.4      .1       0  4982.5     .05       0
  5037.9      .1       0  5323.3     .12       0  6560.4     .05       0
Bank Sta=4982.5,5037.9
XS Rating Curve= 0 ,0
Exp/Cntr=0.3,0.1

Type RM Length L Ch R = 1 ,161923  ,555,555,555
BEGIN DESCRIPTION:
SANDY FORK 117.0
END DESCRIPTION:
XS GIS Cut Line= 3
        2459675.       13817975.        2459275.       13818025.
      2457825.03     13819124.98
#Sta/Elev= 30
  4592.5  434.68  4787.1  425.02  4834.4  422.34  4886.8  415.89    4915  413.94
  4952.8  418.56  4957.8   416.1  4975.5   413.1  4981.5  406.61  4982.7  405.91
  5036.9  406.61  5038.3  414.42  5045.8  414.79  5131.8  412.27  5158.9  414.22
  5196.3  413.58  5223.4  418.54  5294.8  418.48  5366.9   416.2  5402.3   417.8
  5495.8  416.53  5645.6  421.57  5730.9  419.97  5930.6  425.47    6201  426.14
  6250.9  425.26  6259.2  423.66  6494.3  430.94    6707  440.04  6815.6  442.39
#Mann= 7 ,-1 , 0
  4592.5     .07       0  4787.1     .12       0  4886.8      .1       0
  4981.5     .05       0  5036.9      .1       0  5294.8     .12       0
    6707     .05       0
Bank Sta=4981.5,5036.9
XS Rating Curve= 0 ,0
Exp/Cntr=0.3,0.1

Type RM Length L Ch R = 1 ,161368  ,1081,1081,1081
BEGIN DESCRIPTION:
SANDY FORK 116.0
END DESCRIPTION:
XS GIS Cut Line= 3
      2459624.96     13817625.01        2458825.       13817825.
      2457824.99     13818925.01
#Sta/Elev= 30
  4179.4  435.19  4230.9  433.75  4316.9  428.44  4419.2  422.76  4509.2  418.86
  4532.4  416.55  4849.4  418.14  4880.3  415.65  4921.5  415.33  4952.4  412.52
  4962.7  408.95    4966  405.97  4967.2  405.27  5021.4  405.97  5025.3  415.06
    5032  417.96  5039.5   418.6    5103  417.07  5197.7  416.99  5238.4  417.43
    5280  416.01  5287.4  417.07  5371.9  416.61  5463.8  420.07  5471.2   421.5
  5591.5  425.53  6072.6   425.6  6271.3  432.46  6384.2  438.07  6490.6  439.88
#Mann= 7 ,-1 , 0
  4179.4     .12       0  4316.9     .07       0  4419.2      .1       0
    4966     .05       0  5021.4      .1       0  5197.7    .035       0
  5238.4     .12       0
Bank Sta=4966,5021.4
XS Rating Curve= 0 ,0
Exp/Cntr=0.3,0.1

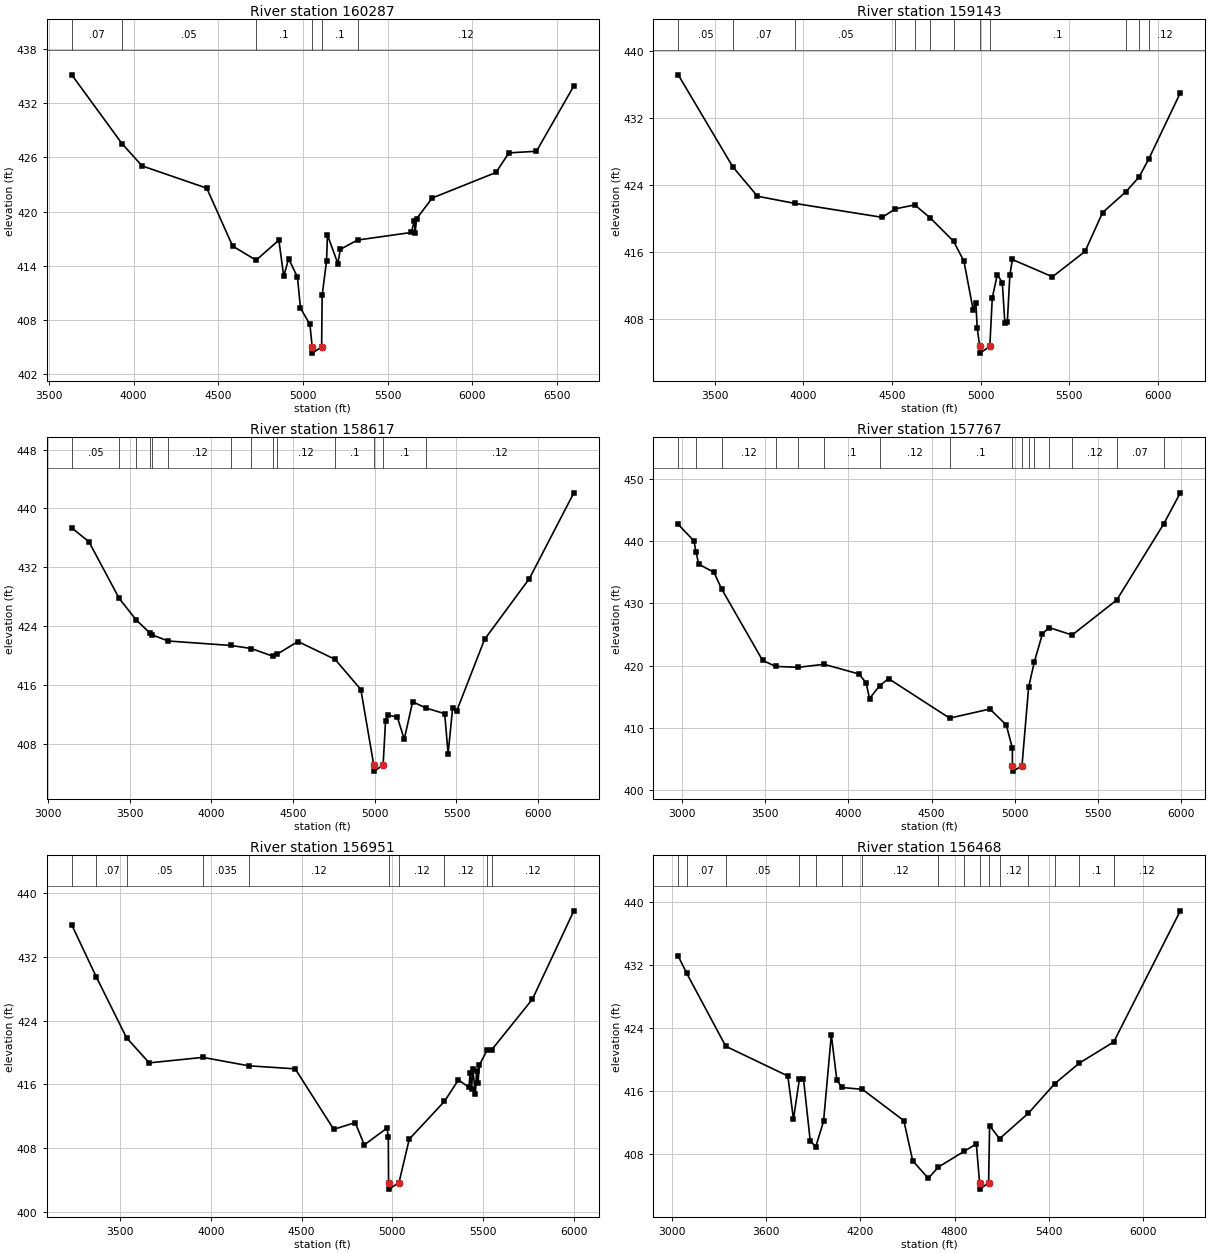
Type RM Length L Ch R = 1 ,160287  ,1144,1144,1144
BEGIN DESCRIPTION:
SANDY FORK 115.0
END DESCRIPTION:
XS GIS Cut Line= 3
      2459475.01     13816574.99        2458225.       13817125.
      2457825.01     13818674.96
#Sta/Elev= 30
  3634.2  435.15  3930.7  427.53  4049.4  425.06  4431.8  422.59  4584.7  416.17
  4723.4  414.61  4857.8  416.83  4886.6  412.81  4915.4  414.78  4967.6  412.73
  4985.5  409.29  5041.2  407.49  5054.6  405.01  5055.8  404.31  5110.4  405.01
  5113.5   410.7  5139.6  414.54  5144.8  417.41  5206.4  414.23  5220.9  415.81
  5322.4  416.84  5640.2  417.68  5657.9  418.94  5663.1  417.63  5671.2   419.2
  5764.1   421.5  6140.7  424.33  6216.9   426.5  6379.6  426.68  6600.6  433.92
#Mann= 6 ,-1 , 0
  3634.2     .07       0  3930.7     .05       0  4723.4      .1       0
  5054.6     .05       0  5110.4      .1       0  5322.4     .12       0
Bank Sta=5054.6,5110.4
XS Rating Curve= 0 ,0
Exp/Cntr=0.3,0.1

Type RM Length L Ch R = 1 ,159143  ,526,526,526
BEGIN DESCRIPTION:
SANDY FORK 114.0
END DESCRIPTION:
XS GIS Cut Line= 3
      2459275.03     13815524.99        2457725.       13816225.
      2456925.02     13817024.98
#Sta/Elev= 30
  3294.7  437.12  3601.9  426.18  3741.7  422.66  3955.1   421.8  4445.1  420.15
  4519.2  421.16  4628.7  421.63  4714.2  420.12  4847.7   417.3  4906.3  414.93
    4958  409.16  4973.5  409.99  4981.2  406.96  4995.2  404.78  4996.5  403.98
  5052.2  404.78  5066.2  410.57  5094.5  413.33  5122.7  412.39  5136.9  407.61
    5151  407.65  5165.2  413.25  5179.3  415.13  5405.6  413.07  5589.4  416.09
  5688.4  420.72  5819.6  423.19  5894.1  424.95  5949.1  427.11  6126.8  434.97
#Mann= 12 ,-1 , 0
  3294.7     .05       0  3601.9     .07       0  3955.1     .05       0
  4519.2    .035       0  4628.7     .05       0  4714.2    .035       0
  4847.7      .1       0  4995.2     .05       0  5052.2      .1       0
  5819.6     .12       0  5894.1      .1       0  5949.1     .12       0
Bank Sta=4995.2,5052.2
XS Rating Curve= 0 ,0
Exp/Cntr=0.3,0.1

Type RM Length L Ch R = 1 ,158617  ,850,850,850
BEGIN DESCRIPTION:
E20682
END DESCRIPTION:
XS GIS Cut Line= 4
      2459242.71     13815336.52      2458017.92     13815618.08
      2457532.23     13815751.82      2456434.13     13816469.81
#Sta/Elev= 30
  3145.8  437.36  3250.9  435.48  3436.2  427.78  3540.7  424.85  3621.7  423.15
  3634.2  422.87    3736  422.01  4121.1   421.4  4244.7  420.99  4376.9  419.94
  4403.8  420.24    4530  421.94  4757.6  419.51  4914.9  415.42    4994  405.15
  4995.3  404.35    5051  405.15  5065.9  411.11    5081  411.98  5138.3  411.66
  5180.4  408.68  5231.7  413.76  5314.8   412.9  5427.8  412.15  5448.9  406.73
  5476.5   412.9  5500.2  412.45    5672  422.23  5946.5  430.49  6218.3  442.12
#Mann= 14 ,-1 , 0
  3145.8     .05       0  3436.2     .12       0  3540.7     .05       0
  3621.7     .07       0  3634.2     .05       0    3736     .12       0
  4121.1     .07       0  4244.7     .12       0  4376.9    .035       0
  4403.8     .12       0  4757.6      .1       0    4994     .05       0
    5051      .1       0  5314.8     .12       0
Bank Sta=4994,5051
XS Rating Curve= 0 ,0
Exp/Cntr=0.3,0.1

Type RM Length L Ch R = 1 ,157767  ,816,816,816
BEGIN DESCRIPTION:
SANDY FORK 113.0
END DESCRIPTION:
XS GIS Cut Line= 3
      2458362.83     13814280.68       2457074.7     13815294.29
      2455949.25      13816082.1
#Sta/Elev= 30
  2980.1  442.66  3074.4  440.02  3086.4  438.27  3103.3  436.28  3194.6  434.98
    3240  432.33  3486.5  420.84  3565.1  419.89  3700.7  419.74  3854.3  420.23
  4063.9  418.68  4107.2  417.26    4128  414.73  4188.9  416.79  4241.9  417.93
  4608.5  411.59  4850.3  413.05  4948.8  410.49    4985  406.79  4985.6  403.89
    4987  403.09  5042.7  403.89  5082.8  416.55  5116.9  420.61  5165.9  425.12
  5205.5  426.12  5343.7  424.92  5611.6  430.54  5893.6  442.75    5993  447.73
#Mann= 16 ,-1 , 0
  2980.1     .07       0  3086.4    .035       0    3240     .12       0
  3565.1      .1       0  3700.7     .12       0  3854.3      .1       0
  4188.9     .12       0  4608.5      .1       0  4985.6     .05       0
  5042.7      .1       0  5082.8     .07       0  5116.9     .12       0
  5205.5     .07       0  5343.7     .12       0  5611.6     .07       0
  5893.6     .12       0
Bank Sta=4985.6,5042.7
XS Rating Curve= 0 ,0
Exp/Cntr=0.3,0.1

Type RM Length L Ch R = 1 ,156951  ,483,483,483
BEGIN DESCRIPTION:
SANDY FORK 112.0
END DESCRIPTION:
XS GIS Cut Line= 3
      2458075.01     13813974.99        2456525.       13814825.
      2455924.99     13815625.02
#Sta/Elev= 30
  3232.7  436.04  3367.5  429.53  3534.7  421.86  3659.7  418.71  3955.5   419.4
  4208.7  418.34  4464.4  417.96  4676.8  410.36  4795.2  411.21  4845.5  408.41
  4970.6  410.52  4977.7  409.42  4979.1  403.65  4980.5  402.85  5036.4  403.65
  5093.2  409.13  5287.4  413.88    5364  416.57  5422.4  415.64  5428.6  417.43
  5436.9  415.45  5443.2  417.97  5457.8  414.78    5464  417.66  5472.4  416.17
  5478.6  418.39  5523.1  420.34  5548.8  420.38  5772.4  426.72  6000.5  437.81
#Mann= 10 ,-1 , 0
  3232.7     .12       0  3367.5     .07       0  3534.7     .05       0
  3955.5    .035       0  4208.7     .12       0  4979.1     .05       0
  5036.4     .12       0  5287.4     .12       0  5523.1      .1       0
  5548.8     .12       0
Bank Sta=4979.1,5036.4
XS Rating Curve= 0 ,0
Exp/Cntr=0.3,0.1

Type RM Length L Ch R = 1 ,156468  ,761,761,761
BEGIN DESCRIPTION:
E20681
END DESCRIPTION:
XS GIS Cut Line= 3
      2457743.38     13813230.48      2456173.71     13814525.63
      2455856.95     13815644.85
#Sta/Elev= 30
  3039.3  433.18  3093.7  430.99    3342  421.74  3737.3  417.97  3773.4  412.49
  3810.9  417.55  3837.2   417.6  3879.9  409.76  3914.8  408.95  3964.9   412.2
  4014.4  423.18  4049.5  417.45  4081.5  416.51  4212.3  416.27  4476.3   412.3
  4532.9   407.2  4631.9  404.97    4697  406.41  4860.4   408.4  4938.1  409.34
    4959   404.4  4960.3   403.6  5016.3   404.4  5022.8  411.67    5086     410
  5270.3  413.25  5437.6  416.99  5594.7  419.61  5813.3  422.29  6237.5  438.94
#Mann= 16 ,-1 , 0
  3039.3     .05       0  3093.7     .07       0    3342     .05       0
  3810.9     .12       0  3914.8     .05       0  4081.5     .12       0
  4212.3     .12       0    4697    .063       0  4860.4      .1       0
    4959     .05       0  5016.3      .1       0    5086     .12       0
  5270.3      .1       0  5437.6     .12       0  5594.7      .1       0
  5813.3     .12       0
Bank Sta=4959,5016.3
XS Rating Curve= 0 ,0
Exp/Cntr=0.3,0.1

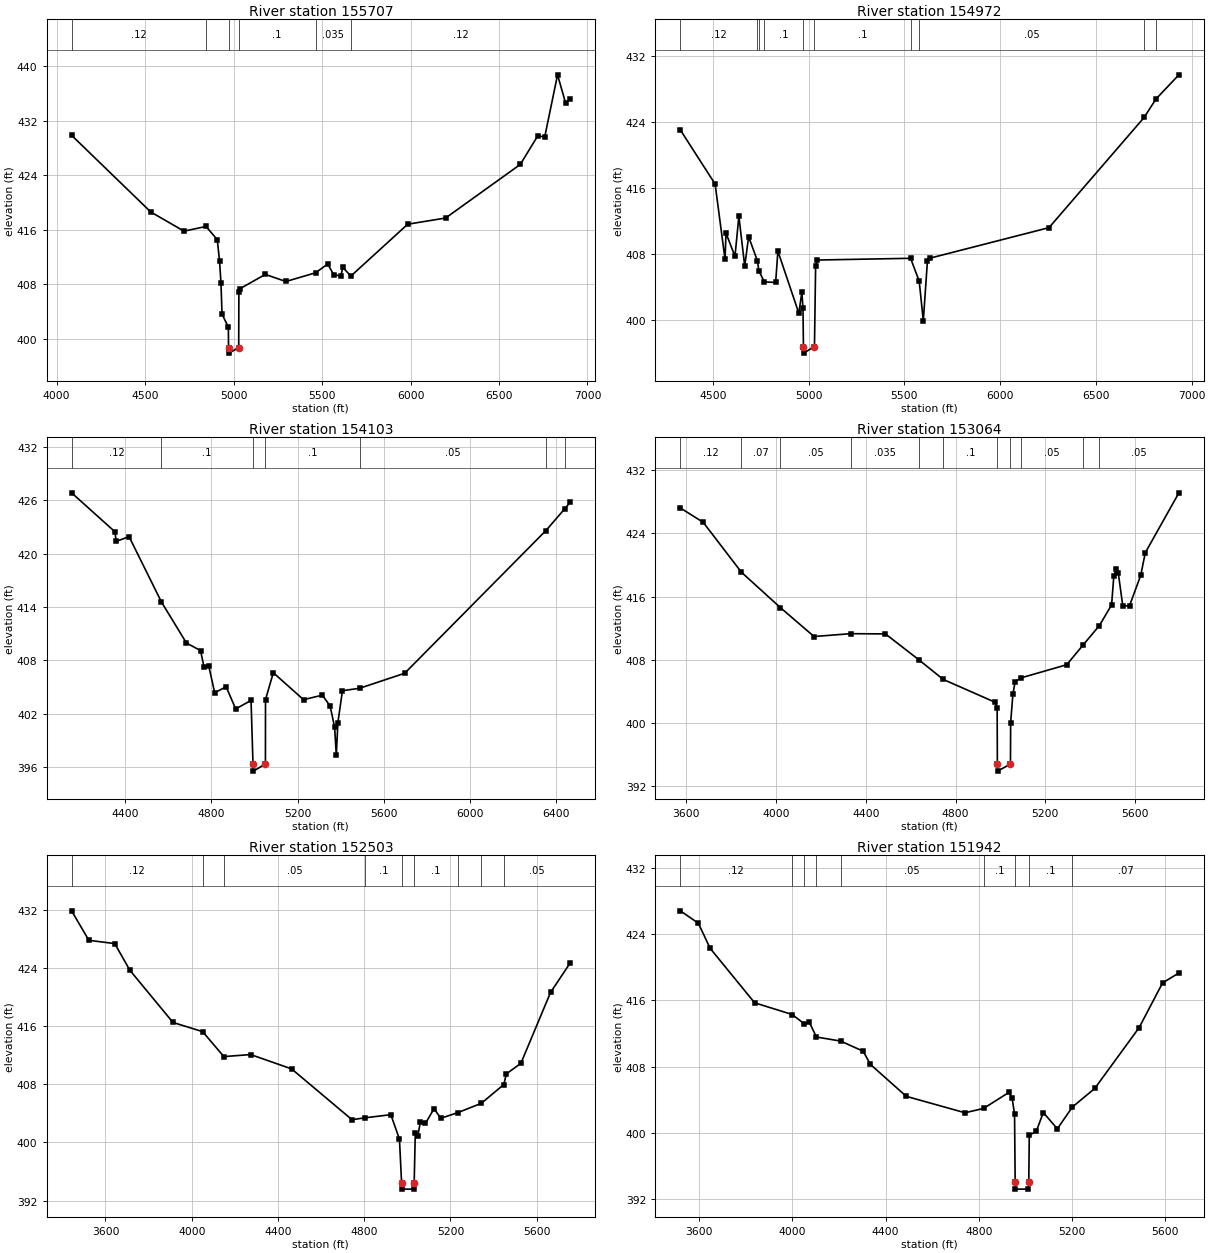
Type RM Length L Ch R = 1 ,155707  ,735,735,735
BEGIN DESCRIPTION:
E20680
END DESCRIPTION:
XS GIS Cut Line= 3
       2456821.3     13813047.44      2456047.01     13814166.65
      2455765.46     13815595.53
#Sta/Elev= 30
  4084.5  429.87  4531.9   418.6  4719.7  415.78  4844.2  416.47  4907.6  414.54
  4920.6  411.44  4928.6  408.19  4934.6  403.59  4970.5  401.67  4971.5  398.65
  4972.8  397.85  5028.9  398.65  5029.9  406.89    5036  407.32  5179.3  409.42
  5295.5  408.38  5463.4  409.66  5531.9  410.95  5566.1  409.36  5606.8   409.2
    5617  410.45  5662.9  409.18    5984   416.8    6198  417.71  6620.3  425.59
  6717.8  429.74  6758.6  429.67  6830.8  438.76    6877  434.55  6901.8  435.21
#Mann= 6 ,-1 , 0
  4084.5     .12       0  4844.2      .1       0  4971.5     .05       0
  5028.9      .1       0  5463.4    .035       0  5662.9     .12       0
Bank Sta=4971.5,5028.9
XS Rating Curve= 0 ,0
Exp/Cntr=0.3,0.1

Type RM Length L Ch R = 1 ,154972  ,869,869,869
BEGIN DESCRIPTION:
SANDY FORK 111.0
END DESCRIPTION:
XS GIS Cut Line= 3
      2456474.95     13813125.01      2455892.15      13813237.5
      2454160.53     13814258.17
#Sta/Elev= 30
    4330  423.01  4511.4  416.47  4563.2  407.35  4568.3  410.52  4615.1  407.72
  4635.5  412.57    4666  406.53  4686.4   410.1  4732.2  407.17  4740.2  405.95
  4768.7  404.62  4827.6  404.56  4839.2  408.35  4948.7  400.83  4964.4  403.39
  4970.2  401.49  4972.7   396.8    4974     396  5030.3   396.8  5036.3  406.52
  5044.4  407.27  5532.3  407.48  5577.4   404.7  5598.7   399.9  5620.1  407.11
  5635.8  407.51  6255.2  411.19    6752  424.53  6814.4  426.78  6933.6  429.69
#Mann= 10 ,-1 , 0
    4330     .12       0  4732.2      .1       0  4740.2     .12       0
  4768.7      .1       0  4972.7     .05       0  5030.3      .1       0
  5532.3      .1       0  5577.4     .05       0    6752    .035       0
  6814.4     .05       0
Bank Sta=4972.7,5030.3
XS Rating Curve= 0 ,0
Exp/Cntr=0.3,0.1

Type RM Length L Ch R = 1 ,154103  ,1039,1039,1039
BEGIN DESCRIPTION:
SANDY FORK 110.0
END DESCRIPTION:
XS GIS Cut Line= 3
      2455842.91     13812491.36      2454920.78     13812998.18
      2453872.01     13813695.01
#Sta/Elev= 30
  4152.1  426.82  4353.2  422.44  4358.9  421.36  4418.5   421.9  4568.7  414.55
  4684.7  409.94  4750.1  409.09  4765.9  407.25    4788  407.37  4815.5  404.35
  4868.6  405.02    4913  402.53  4984.1  403.49  4993.2  396.34  4994.5  395.54
  5050.8  396.34  5051.2  403.58  5087.3   406.6  5227.5  403.57  5314.7  404.08
  5350.8  402.86  5371.8  400.45  5379.4   397.3  5386.8     401  5407.9  404.58
  5487.1  404.85  5696.5  406.54  6351.3  422.58  6439.5  425.05  6463.5  425.75
#Mann= 7 ,-1 , 0
  4152.1     .12       0  4568.7      .1       0  4993.2     .05       0
  5050.8      .1       0  5487.1     .05       0  6351.3    .035       0
  6439.5     .05       0
Bank Sta=4993.2,5050.8
XS Rating Curve= 0 ,0
Exp/Cntr=0.3,0.1

Type RM Length L Ch R = 1 ,153064  ,561,561,561
BEGIN DESCRIPTION:
SANDY FORK 109.0
END DESCRIPTION:
XS GIS Cut Line= 3
        2455675.       13812325.        2454275.       13812575.
      2453475.05       13812575.
#Sta/Elev= 30
  3573.2  427.21  3674.8   425.4  3845.6  419.07  4018.6  414.61    4169  410.94
  4332.1   411.3  4487.4  411.27    4635  408.02  4744.7  405.51    4975  402.63
  4985.2  401.93  4986.1   394.8  4987.5   393.9  5044.5   394.8  5045.3  400.03
  5055.3  403.62  5065.3  405.24  5090.9   405.7  5295.3  407.37  5368.9  409.89
    5441  412.33  5495.3  414.95  5505.3  418.64  5515.3  419.45  5525.3  418.95
  5545.3  414.79  5575.3  414.84  5625.3   418.7  5645.3  421.54  5795.3  429.13
#Mann= 11 ,-1 , 0
  3573.2     .12       0  3845.6     .07       0  4018.6     .05       0
  4332.1    .035       0    4635     .05       0  4744.7      .1       0
  4986.1     .05       0  5044.5      .1       0  5090.9     .05       0
  5368.9     .07       0    5441     .05       0
Bank Sta=4986.1,5044.5
XS Rating Curve= 0 ,0
Exp/Cntr=0.3,0.1

Type RM Length L Ch R = 1 ,152503  ,561,561,561
BEGIN DESCRIPTION:
SANDY FORK 108.0
END DESCRIPTION:
XS GIS Cut Line= 3
      2455825.02       13812125.        2454275.       13812075.
      2453575.01       13812375.
#Sta/Elev= 30
  3442.8  431.83  3522.9  427.78  3642.9  427.33    3713  423.67  3913.1  416.49
  4050.6  415.23  4149.1   411.8  4273.3  412.08  4463.4  410.11  4743.5  403.13
  4803.7  403.39  4923.6  403.82  4963.6  400.46  4973.4  394.49  4974.8  393.59
  5030.5  393.59  5031.9  394.49  5037.1  401.36    5048  400.84  5060.7  402.79
  5084.3  402.63  5124.2  404.65    5155  403.32    5234   404.1  5343.3  405.38
  5447.5  407.96  5459.6  409.43  5526.7  410.87  5664.5  420.62  5755.2  424.65
#Mann= 9 ,-1 , 0
  3442.8     .12       0  4050.6     .07       0  4149.1     .05       0
  4803.7      .1       0  4973.4     .05       0  5031.9      .1       0
    5234     .05       0  5343.3     .07       0  5447.5     .05       0
Bank Sta=4973.4,5031.9
XS Rating Curve= 0 ,0
Exp/Cntr=0.3,0.1

Type RM Length L Ch R = 1 ,151942  ,534,534,534
BEGIN DESCRIPTION:
SANDY FORK 107.0
END DESCRIPTION:
XS GIS Cut Line= 3
      2455674.99     13812074.99        2454275.       13811575.
      2453625.01       13811525.
#Sta/Elev= 30
  3519.6  426.85  3596.6  425.35    3647  422.32  3838.1  415.72  3999.5   414.3
  4051.5  413.16  4073.3  413.34  4103.1  411.58  4206.6  411.09  4303.8  409.86
  4334.6  408.27  4488.5   404.4  4740.7  402.41  4820.3  402.94  4929.2  404.88
  4942.5  404.23  4953.1  402.24  4955.7  394.07  4957.1  393.17  5012.8  393.17
  5014.2  394.07  5016.2  399.69  5046.3  400.16  5076.4  402.44  5136.6  400.47
  5201.3  403.11    5297  405.35  5487.6  412.72  5587.9  418.12  5658.1  419.33
#Mann= 9 ,-1 , 0
  3519.6     .12       0  3999.5     .07       0  4051.5     .12       0
  4103.1    .035       0  4206.6     .05       0  4820.3      .1       0
  4955.7     .05       0  5014.2      .1       0  5201.3     .07       0
Bank Sta=4955.7,5014.2
XS Rating Curve= 0 ,0
Exp/Cntr=0.3,0.1