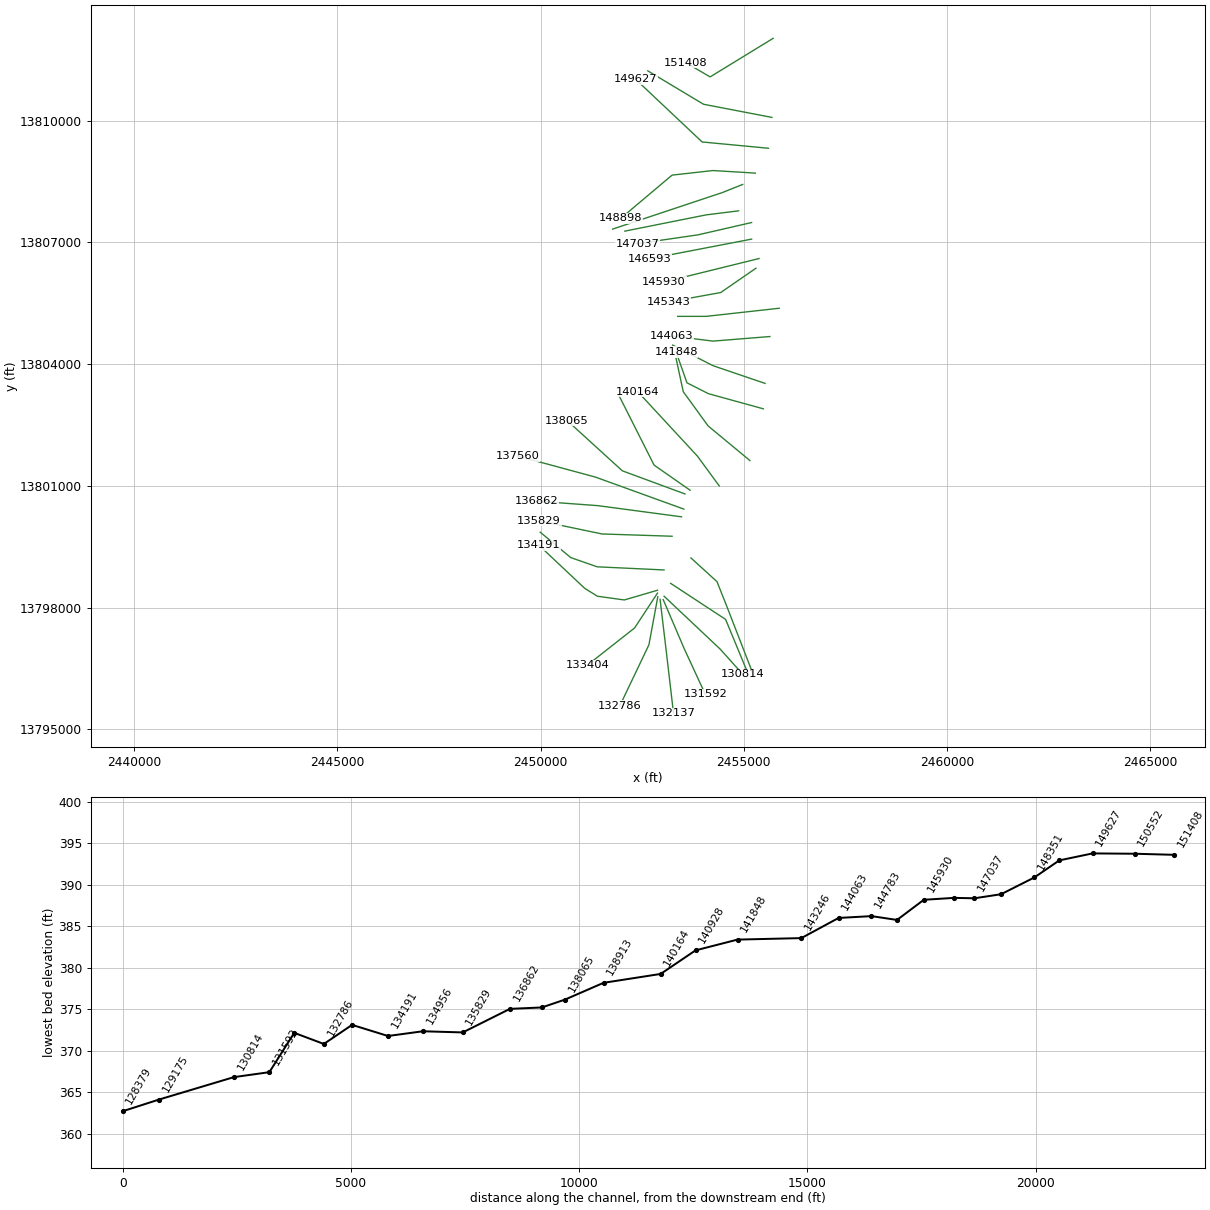
HEC-RAS study SANDY FORK.prj: SANDY FORK Base Level Engineering

--- SANDY FORK.g01 (geometry) --- (continued)

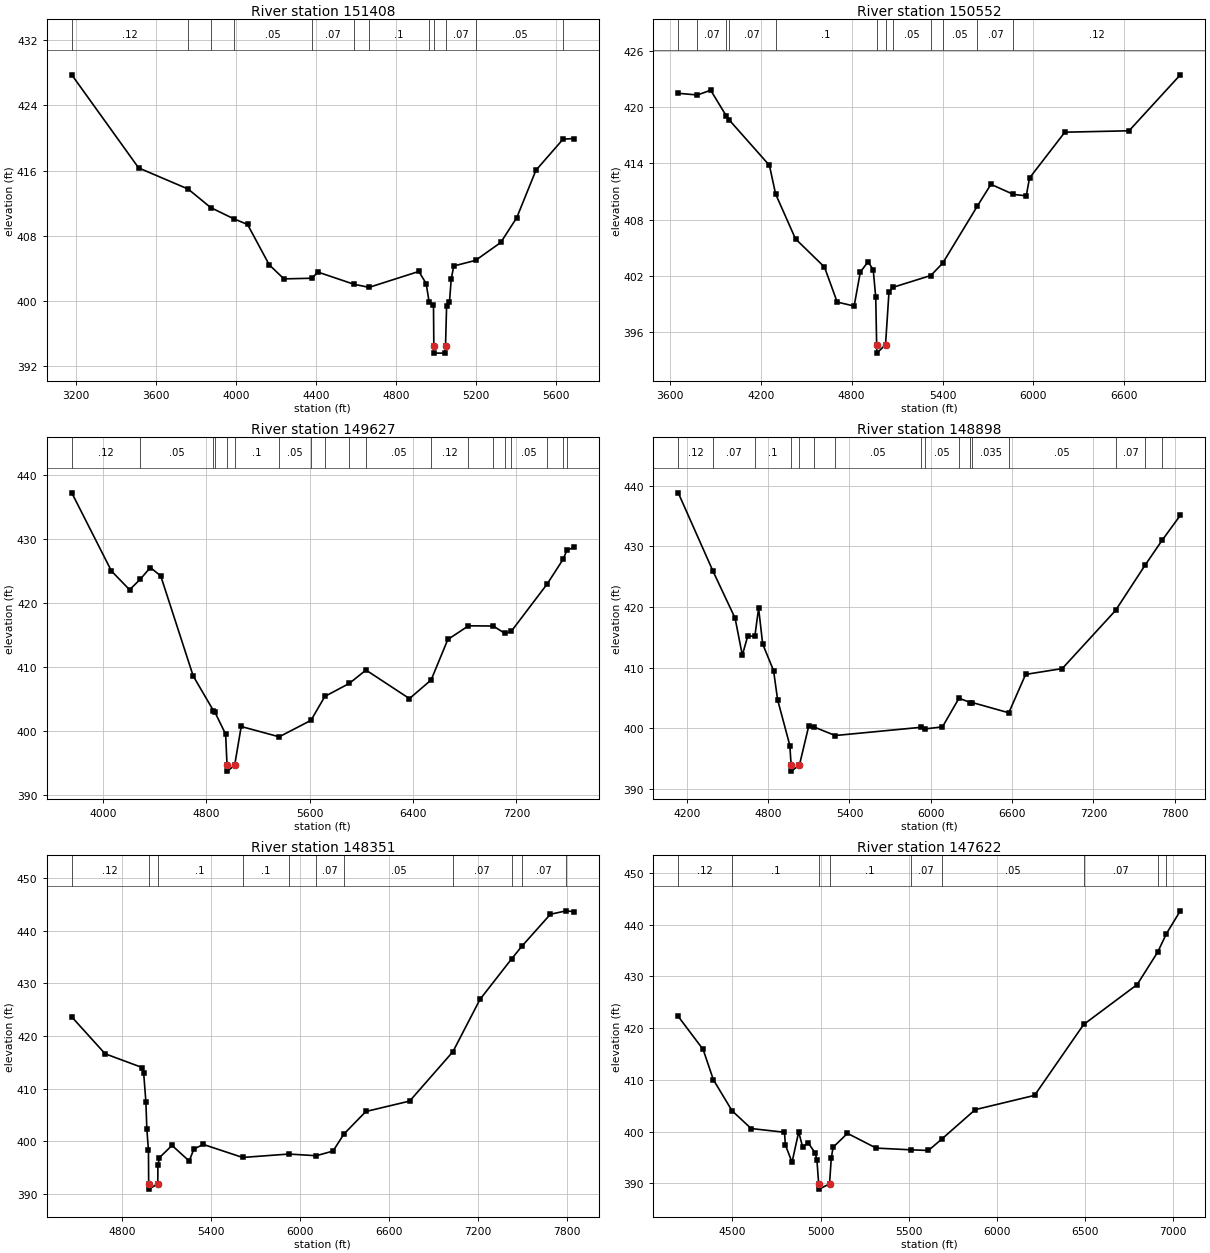
Type RM Length L Ch R = 1 ,151408  ,856,856,856
BEGIN DESCRIPTION:
SANDY FORK 106.0
END DESCRIPTION:
XS GIS Cut Line= 3
      2455724.99     13812024.99        2454175.       13811075.
      2453574.98     13811425.01
#Sta/Elev= 30
  3177.8  427.73  3512.4  416.32  3760.1  413.73  3873.6  411.45  3987.2   410.1
  4057.4  409.39  4166.1  404.44  4239.6  402.72  4381.4   402.8  4407.8  403.57
    4590  402.06  4665.4  401.68  4914.6  403.63  4951.3  402.15  4966.4  399.85
    4988  399.54  4989.7  394.52  4991.1  393.62  5046.8  393.62  5048.2  394.52
  5053.6  399.36  5068.1  399.92  5076.8  402.72  5089.6   404.3  5198.7  404.99
  5324.5  407.18  5404.7  410.22  5500.6  416.03  5636.7  419.85  5690.4  419.92
#Mann= 12 ,-1 , 0
  3177.8     .12       0  3760.1     .07       0  3873.6    .035       0
  3987.2     .05       0  4381.4     .07       0    4590     .12       0
  4665.4      .1       0  4966.4     .07       0  4989.7     .05       0
  5048.2     .07       0  5198.7     .05       0  5636.7     .07       0
Bank Sta=4989.7,5048.2
XS Rating Curve= 0 ,0
Exp/Cntr=0.3,0.1

Type RM Length L Ch R = 1 ,150552  ,925,925,925
BEGIN DESCRIPTION:
E20679
END DESCRIPTION:
XS GIS Cut Line= 3
      2455695.09       13810077.      2454012.75      13810400.8
      2452640.18     13811224.35
#Sta/Elev= 30
  3655.7  421.47  3782.8  421.29  3869.6   421.8  3972.1  419.08  3989.6  418.67
  4257.6  413.78  4298.3  410.73  4429.7  405.94    4621  402.93  4704.7   399.2
  4816.7  398.77  4857.5   402.4  4908.4  403.49  4942.7  402.65  4959.3   399.7
  4965.3  394.65  4966.7  393.75  5023.9  394.65  5046.5  400.22  5070.8  400.76
  5322.7  402.03  5401.4  403.35  5630.2  409.44  5719.6  411.76  5868.5  410.68
  5952.8  410.53  5974.2  412.43  6207.5  417.32  6631.2  417.47  6969.6  423.44
#Mann= 12 ,-1 , 0
  3655.7     .12       0  3782.8     .07       0  3972.1    .035       0
  3989.6     .07       0  4298.3      .1       0  4965.3     .05       0
  5023.9      .1       0  5070.8     .05       0  5322.7     .07       0
  5401.4     .05       0  5630.2     .07       0  5868.5     .12       0
Bank Sta=4965.3,5023.9
XS Rating Curve= 0 ,0
Exp/Cntr=0.3,0.1

Type RM Length L Ch R = 1 ,149627  ,729,729,729
BEGIN DESCRIPTION:
E20678
END DESCRIPTION:
XS GIS Cut Line= 3
      2455610.56     13809316.81      2453977.56     13809471.66
      2452344.53     13811013.18
#Sta/Elev= 30
  3758.9  437.19  4065.8     425  4206.5  422.07  4287.4  423.68  4367.2  425.54
  4447.5  424.23  4698.7  408.63  4855.4  403.22    4866  403.01  4949.8  399.56
  4960.6  394.69    4962  393.79  5019.4  394.69  5070.3  400.75  5364.3  399.14
  5610.3  401.71  5717.8  405.44    5907  407.47    6036  409.55  6372.5   405.1
  6540.5  408.01  6669.5  414.32  6829.5  416.45  7020.7  416.42  7109.3   415.3
  7159.9  415.57  7438.3  422.97  7561.3  426.81  7591.2  428.24  7644.9  428.67
#Mann= 19 ,-1 , 0
  3758.9     .12       0  4287.4     .05       0  4855.4     .12       0
    4866      .1       0  4960.6     .05       0  5019.4      .1       0
  5364.3     .05       0  5610.3     .07       0  5717.8     .05       0
    5907    .035       0    6036     .05       0  6540.5     .12       0
  6829.5     .07       0  7020.7     .05       0  7109.3     .12       0
  7159.9     .05       0  7438.3     .07       0  7561.3     .05       0
  7591.2     .07       0
Bank Sta=4960.6,5019.4
XS Rating Curve= 0 ,0
Exp/Cntr=0.3,0.1

Type RM Length L Ch R = 1 ,148898  ,547,547,547
BEGIN DESCRIPTION:
E20677
END DESCRIPTION:
XS GIS Cut Line= 4
      2455286.84     13808704.41      2454245.04     13808767.76
      2453238.46     13808655.14      2451979.25      13807592.9
#Sta/Elev= 30
  4136.8  438.84  4393.9  425.89  4556.4  418.16  4609.5  412.07  4649.6  415.23
    4702  415.19  4729.7  419.81  4759.8  413.91  4839.9  409.54    4870  404.72
  4960.2  397.17  4969.5  393.95    4971  392.95  5030.9  393.95  5100.4  400.47
    5137  400.24    5295  398.82  5924.9  400.17  5954.8   399.9  6086.2  400.25
    6208  404.97  6292.5  404.26  6307.5  404.25  6575.4  402.57  6699.6   408.9
  6969.8  409.86  7362.9  419.44  7583.6     427  7705.5  430.98  7840.8  435.13
#Mann= 16 ,-1 , 0
  4136.8     .12       0  4393.9     .07       0    4702      .1       0
  4969.5     .05       0  5030.9      .1       0    5137     .07       0
    5295     .05       0  5924.9     .12       0  5954.8     .05       0
    6208     .12       0  6292.5     .05       0  6307.5    .035       0
  6575.4     .05       0  7362.9     .07       0  7583.6     .12       0
  7705.5     .07       0
Bank Sta=4969.5,5030.9
XS Rating Curve= 0 ,0
Exp/Cntr=0.3,0.1

Type RM Length L Ch R = 1 ,148351  ,729,729,729
BEGIN DESCRIPTION:
SANDY FORK 103.0
END DESCRIPTION:
XS GIS Cut Line= 3
      2454975.02     13808425.01        2454475.       13808225.
      2451774.99       13807325.
#Sta/Elev= 30
  4461.9  423.63  4686.7  416.62  4937.2     414  4946.6  412.96  4961.4  407.54
  4968.1  402.24  4978.9  398.25  4980.3  391.89  4981.8  390.89  5041.7  391.89
  5042.6  395.47  5053.1  396.87  5137.5  399.21  5253.4  396.23    5285  398.51
  5348.3  399.39  5613.8  396.91  5925.1  397.56    6110  397.24  6223.2  398.13
  6296.7  401.37  6444.5  405.65  6739.7  407.63  7031.5  417.03    7214  426.97
    7427  434.67  7496.5  437.08  7688.4  443.15  7795.6   443.8  7846.5  443.63
#Mann= 11 ,-1 , 0
  4461.9     .12       0  4980.3     .05       0  5041.7      .1       0
  5613.8      .1       0  5925.1     .05       0    6110     .07       0
  6296.7     .05       0  7031.5     .07       0    7427     .12       0
  7496.5     .07       0  7795.6     .05       0
Bank Sta=4980.3,5041.7
XS Rating Curve= 0 ,0
Exp/Cntr=0.3,0.1

Type RM Length L Ch R = 1 ,147622  ,585,585,585
BEGIN DESCRIPTION:
SANDY FORK 102.0
END DESCRIPTION:
XS GIS Cut Line= 3
      2454875.03       13807775.        2454075.       13807675.
      2452074.97     13807274.99
#Sta/Elev= 30
  4193.3  422.25  4334.4  415.86  4392.4  410.02  4498.2  404.02  4606.5  400.58
  4795.5  399.86  4800.5  397.43  4838.3  394.06  4876.1  399.93  4898.8  396.97
    4929  397.88  4969.3  395.85  4979.4  394.52  4989.3  389.87  4990.8  388.87
  5050.7  389.87  5060.7  394.79  5070.9  396.95  5152.5  399.65  5315.7   396.8
  5510.5  396.47  5611.4  396.34  5688.3  398.58  5876.6  404.23  6213.1  406.99
  6491.3  420.69  6794.4   428.4  6911.1  434.69  6960.4  438.24  7039.2  442.66
#Mann= 9 ,-1 , 0
  4193.3     .12       0  4498.2      .1       0  4989.3     .05       0
  5050.7      .1       0  5510.5     .07       0  5688.3     .05       0
  6491.3     .07       0  6911.1     .12       0  6960.4     .07       0
Bank Sta=4989.3,5050.7
XS Rating Curve= 0 ,0
Exp/Cntr=0.3,0.1

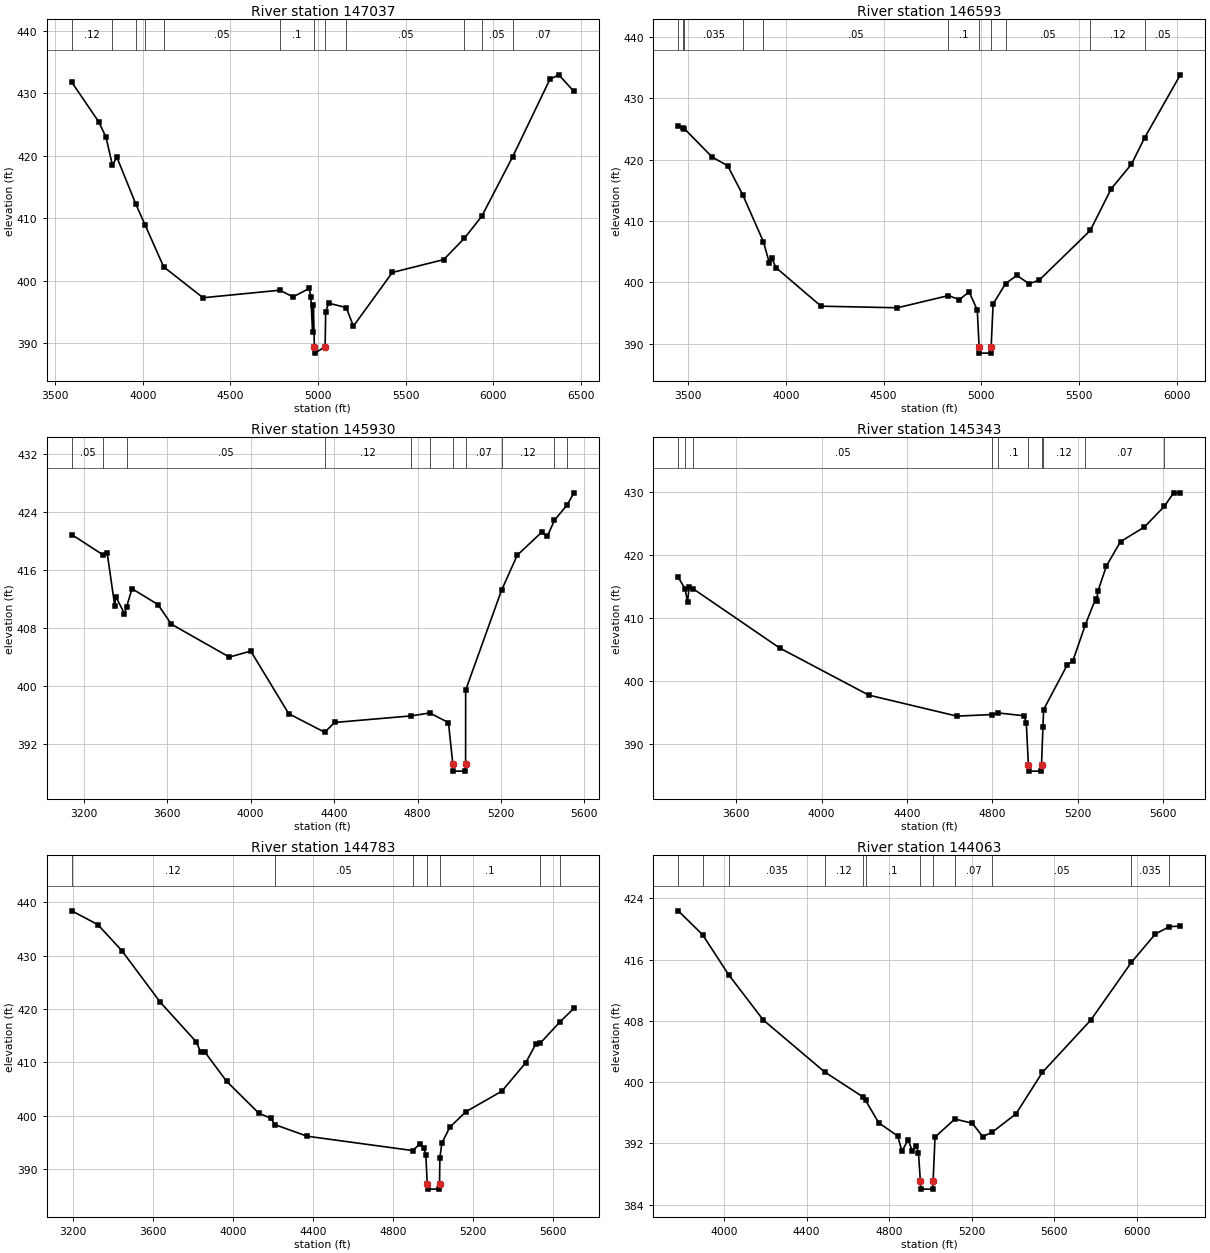
Type RM Length L Ch R = 1 ,147037  ,444,444,444
BEGIN DESCRIPTION:
E20676
END DESCRIPTION:
XS GIS Cut Line= 3
      2455195.28     13807486.67      2453879.01       13807184.
      2452379.83     13806965.81
#Sta/Elev= 30
  3594.8  431.78    3749  425.42    3790  422.99  3826.7  418.49  3852.2  419.77
    3961  412.21  4014.6  408.83  4119.3   402.2  4344.1  397.25  4783.3  398.46
  4857.2  397.38    4950  398.75  4959.6  397.33  4968.9  391.76    4974  396.07
  4979.4  389.38  4980.9  388.38  5040.8  389.38    5044  394.91  5060.6  396.39
  5161.4  395.67  5202.1  392.69  5424.4   401.3  5717.5  403.36  5835.9  406.79
    5935  410.31  6110.8  419.81  6323.8  432.25  6374.3  432.96  6460.4  430.31
#Mann= 12 ,-1 , 0
  3594.8     .12       0  3826.7     .07       0    3961     .05       0
  4014.6     .07       0  4119.3     .05       0  4783.3      .1       0
  4979.4     .05       0  5040.8      .1       0  5161.4     .05       0
  5835.9     .07       0    5935     .05       0  6110.8     .07       0
Bank Sta=4979.4,5040.8
XS Rating Curve= 0 ,0
Exp/Cntr=0.3,0.1

Type RM Length L Ch R = 1 ,146593  ,663,663,663
BEGIN DESCRIPTION:
E20675
END DESCRIPTION:
XS GIS Cut Line= 2
      2455195.28     13807078.41      2452675.36     13806592.73
#Sta/Elev= 30
  3450.4  425.56  3473.5  425.12    3482  425.04  3623.8  420.42  3703.2     419
  3781.2  414.18  3886.1  406.58  3915.8  403.17  3929.3  403.89  3949.7  402.39
  4180.3  396.09  4570.9  395.83  4831.5  397.82  4886.6  397.16  4937.6  398.41
  4978.9  395.46  4988.3  389.43  4989.8  388.43  5048.3  388.43  5049.8  389.43
  5059.8  396.45  5123.6  399.78  5181.3  401.11  5243.4  399.75  5295.2  400.33
  5556.6  408.45  5663.5  415.25  5767.2  419.26  5833.7  423.54  6016.7  433.84
#Mann= 11 ,-1 , 0
  3450.4    .035       0  3473.5     .05       0    3482    .035       0
  3781.2     .07       0  3886.1     .05       0  4831.5      .1       0
  4988.3     .05       0  5049.8      .1       0  5123.6     .05       0
  5556.6     .12       0  5833.7     .05       0
Bank Sta=4988.3,5049.8
XS Rating Curve= 0 ,0
Exp/Cntr=0.3,0.1

Type RM Length L Ch R = 1 ,145930  ,587,587,587
BEGIN DESCRIPTION:
E20674
END DESCRIPTION:
XS GIS Cut Line= 2
       2455378.3     13806599.76      2453041.42     13806022.58
#Sta/Elev= 30
  3142.3  420.82  3294.4  417.98  3311.9  418.32  3348.2  411.03  3353.3  412.26
  3394.8  409.93  3405.6  410.89  3431.1  413.36  3555.5  411.17  3619.5  408.47
  3897.6  403.93  4000.6  404.75  4182.4  396.12  4354.8  393.56  4402.4  394.91
  4767.2  395.81  4858.6  396.22  4948.3  394.89    4969   389.2  4970.5   388.2
    5029   388.2  5030.5   389.2  5030.7  399.37  5202.8  413.15  5277.9  417.97
  5394.9  421.14  5422.1  420.57  5455.9  422.77  5518.6  424.97  5549.4  426.58
#Mann= 11 ,-1 , 0
  3142.3     .05       0  3294.4     .07       0  3405.6     .05       0
  4354.8     .12       0  4767.2      .1       0  4858.6     .07       0
    4969     .05       0  5030.5     .07       0  5202.8     .12       0
  5455.9     .07       0  5518.6     .12       0
Bank Sta=4969,5030.5
XS Rating Curve= 0 ,0
Exp/Cntr=0.3,0.1

Type RM Length L Ch R = 1 ,145343  ,560,560,560
BEGIN DESCRIPTION:
E20673
END DESCRIPTION:
XS GIS Cut Line= 3
      2455300.89     13806360.45      2454435.09     13805762.13
      2453154.39     13805529.91
#Sta/Elev= 30
  3327.5  416.47  3359.3  414.63  3371.1   412.6  3379.1  414.95  3397.7  414.64
  3802.9  405.27  4220.6  397.81  4634.1  394.48  4799.8  394.73  4828.4  394.98
  4948.2  394.54  4959.3  393.46  4969.2  386.77  4970.7  385.77  5029.2  385.77
  5030.7  386.77  5037.4  392.69  5040.6  395.52  5152.4  402.65  5177.2  403.19
  5236.3  408.94  5284.1  413.05  5289.1  412.73  5294.7  414.22  5335.3  418.28
  5401.1  422.11    5513  424.42  5606.8  427.71  5650.4  429.84  5681.5  429.79
#Mann= 10 ,-1 , 0
  3327.5     .05       0  3359.3     .07       0  3397.7     .05       0
  4799.8     .12       0  4828.4      .1       0  4969.2     .05       0
  5030.7      .1       0  5037.4     .12       0  5236.3     .07       0
  5606.8     .05       0
Bank Sta=4969.2,5030.7
XS Rating Curve= 0 ,0
Exp/Cntr=0.3,0.1

Type RM Length L Ch R = 1 ,144783  ,720,720,720
BEGIN DESCRIPTION:
SANDY FORK 99.0
END DESCRIPTION:
XS GIS Cut Line= 3
      2455875.03       13805375.        2454075.       13805175.
      2453375.01       13805175.
#Sta/Elev= 30
  3193.7  438.41  3324.5  435.81  3445.3  430.89  3636.4  421.27  3817.5  413.79
  3837.7  411.95  3857.8  412.01  3968.5  406.43  4129.5  400.46  4189.8  399.52
  4208.3  398.34  4370.9  396.15  4898.7  393.46  4934.4  394.68  4954.5  393.96
  4964.6  392.59  4971.5  387.23    4973  386.23  5031.5  386.23    5033  387.23
  5034.8  392.14  5044.8  394.89  5084.8  397.85  5164.8  400.74  5344.8   404.6
  5464.8  409.96  5514.8  413.45  5535.7  413.56  5634.2  417.54  5704.8  420.12
#Mann= 7 ,-1 , 0
  3193.7     .12       0  4208.3     .05       0  4898.7      .1       0
  4971.5     .05       0    5033      .1       0  5535.7     .07       0
  5634.2     .05       0
Bank Sta=4971.5,5033
XS Rating Curve= 0 ,0
Exp/Cntr=0.3,0.1

Type RM Length L Ch R = 1 ,144063  ,817,817,817
BEGIN DESCRIPTION:
E20672
END DESCRIPTION:
XS GIS Cut Line= 3
      2455645.77     13804678.13      2454245.04     13804565.51
      2453224.42      13804692.2
#Sta/Elev= 30
  3777.9  422.37  3895.6  419.26  4021.8  414.04    4190  408.11  4487.1  401.33
  4675.4  398.02  4686.2  397.59  4749.8  394.67  4842.1  392.94  4862.2  390.95
  4892.3  392.46  4912.3     391  4932.4  391.61  4942.4  390.76  4951.7  387.01
  4953.2  386.01  5011.8  386.01  5013.3  387.01  5022.7  392.81  5118.7  395.17
  5203.3  394.62  5253.7  392.88    5298  393.41    5415  395.84  5542.6  401.25
  5777.7   408.1    5974  415.62  6090.1  419.33  6158.8  420.31  6211.6  420.37
#Mann= 12 ,-1 , 0
  3777.9     .07       0  3895.6     .12       0  4021.8    .035       0
  4487.1     .12       0  4675.4    .035       0  4686.2      .1       0
  4951.7     .05       0  5013.3      .1       0  5118.7     .07       0
    5298     .05       0    5974    .035       0  6158.8     .05       0
Bank Sta=4951.7,5013.3
XS Rating Curve= 0 ,0
Exp/Cntr=0.3,0.1

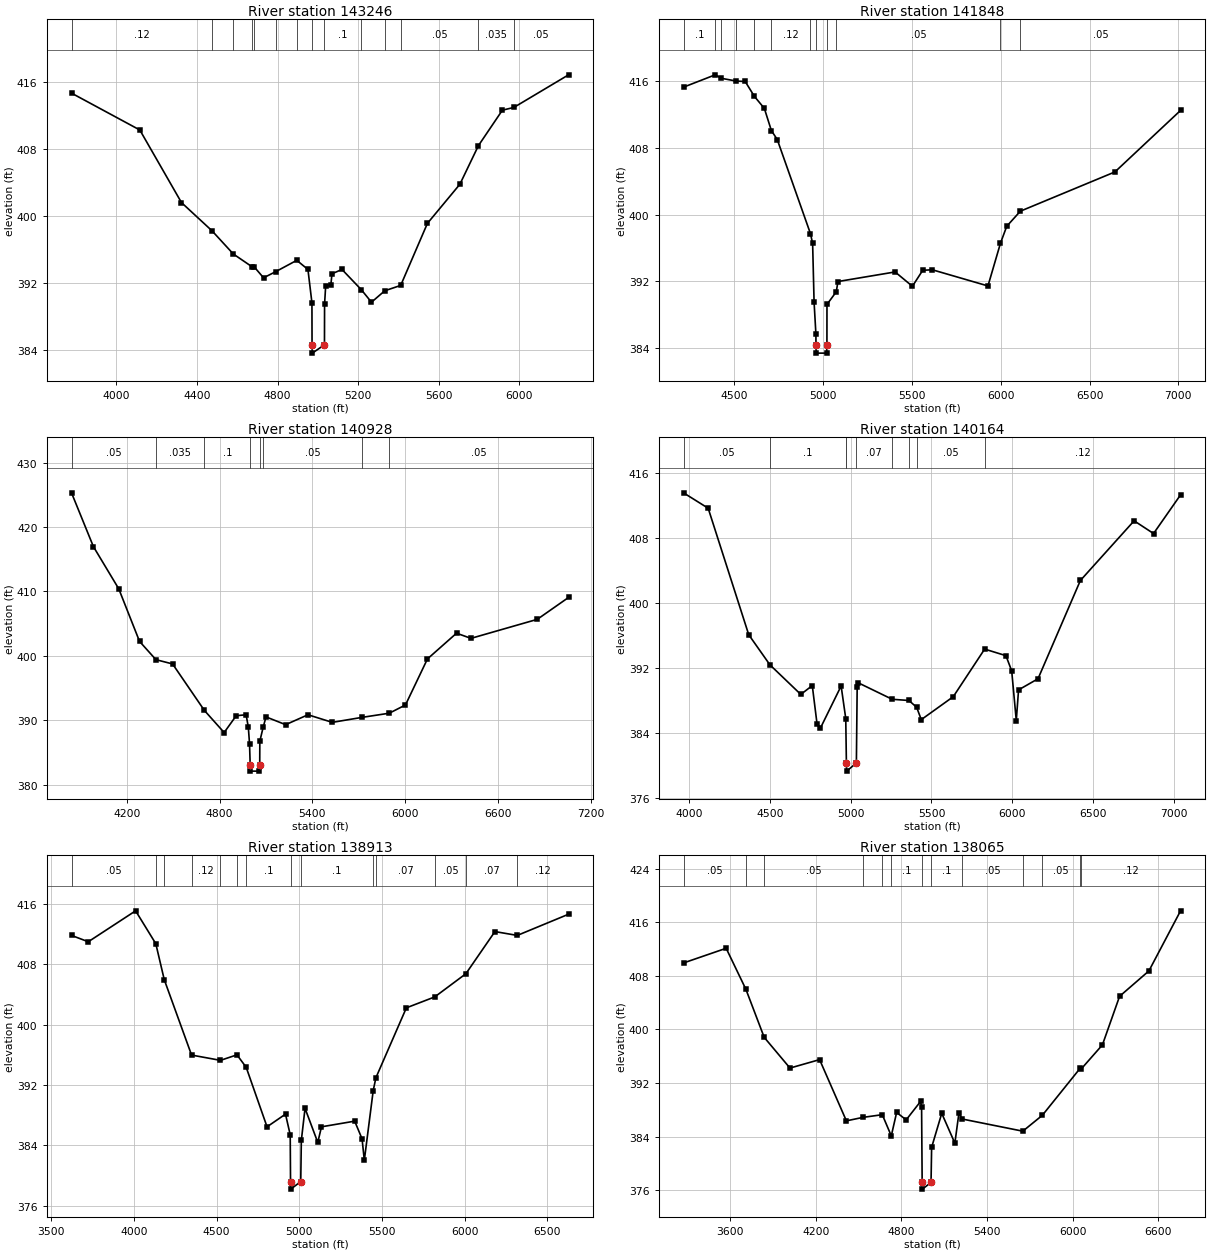
Type RM Length L Ch R = 1 ,143246  ,1398,1398,1398
BEGIN DESCRIPTION:
E20671
END DESCRIPTION:
XS GIS Cut Line= 3
      2455526.09     13803523.75      2454245.04     13803960.16
       2453252.5     13804466.98
#Sta/Elev= 30
  3776.9  414.68  4116.1  410.27  4322.8  401.59    4475   398.2  4580.1  395.44
    4672  393.93  4685.2  393.86  4730.4  392.59  4790.3  393.32  4895.3  394.68
  4950.7  393.59  4970.6  389.59  4971.1  384.58  4972.6  383.58  5032.8  384.58
  5033.3  389.43  5038.6  391.55  5064.7  391.78    5070  393.07  5119.7  393.59
    5216  391.16  5266.2  389.67  5332.2  391.04  5411.3  391.68  5543.9   399.1
  5705.1  403.78  5797.2   408.4  5916.1  412.64  5973.1  412.97  6244.7  416.87
#Mann= 14 ,-1 , 0
  3776.9     .12       0    4475    .035       0  4580.1     .07       0
    4672     .12       0  4685.2     .07       0  4790.3     .12       0
  4895.3      .1       0  4971.1     .05       0  5032.8      .1       0
    5216     .05       0  5332.2     .07       0  5411.3     .05       0
  5797.2    .035       0  5973.1     .05       0
Bank Sta=4971.1,5032.8
XS Rating Curve= 0 ,0
Exp/Cntr=0.3,0.1

Type RM Length L Ch R = 1 ,141848  ,920,920,920
BEGIN DESCRIPTION:
E20670
END DESCRIPTION:
XS GIS Cut Line= 4
      2455483.86     13802897.28      2454132.41     13803270.34
      2453604.49     13803537.82      2453337.01     13804298.02
#Sta/Elev= 30
  4213.2  415.31  4391.6  416.79  4426.9  416.37  4511.3  416.04  4560.6  415.99
  4612.2  414.21  4668.5  412.76  4707.9  410.11  4741.1  409.03  4928.1  397.74
  4940.4  396.56  4948.6  389.51  4958.9  385.68  4959.2   384.4  4960.7   383.4
  5019.4   383.4  5020.9   384.4  5021.2  389.24  5073.6  390.76    5083  391.99
    5405  393.14  5502.4  391.42  5560.6  393.34  5614.6   393.4    5928  391.46
  5998.5  396.59  6033.8  398.62  6110.5  400.43  6643.2  405.14  7012.9  412.52
#Mann= 12 ,-1 , 0
  4213.2      .1       0  4391.6     .12       0  4426.9     .07       0
  4511.3     .12       0  4612.2     .07       0  4707.9     .12       0
  4928.1      .1       0  4959.2     .05       0  5020.9      .1       0
  5073.6     .05       0  5998.5    .035       0  6110.5     .05       0
Bank Sta=4959.2,5020.9
XS Rating Curve= 0 ,0
Exp/Cntr=0.3,0.1

Type RM Length L Ch R = 1 ,140928  ,764,764,764
BEGIN DESCRIPTION:
E20669
END DESCRIPTION:
XS GIS Cut Line= 4
      2455153.09      13801623.2      2454125.37     13802474.93
      2453512.98     13803319.61        2453337.     13804136.17
#Sta/Elev= 30
  3842.8   425.3  3984.3  416.95  4148.4  410.39  4282.5  402.24  4388.6   399.4
  4496.1  398.74  4701.8  391.52  4829.5  388.09  4907.6   390.7  4971.4  390.85
  4985.8  388.95  4993.6  386.37  4997.9   383.1  4999.4   382.1  5058.1   382.1
  5059.6   383.1  5060.2  386.74  5081.5  388.88  5100.1  390.52  5227.1  389.31
  5371.6  390.85  5528.6  389.67  5722.4  390.45  5897.1  391.09  6001.8  392.37
    6144  399.52  6331.9  403.51  6425.4  402.71  6853.8  405.66  7056.2  409.06
#Mann= 8 ,-1 , 0
  3842.8     .05       0  4388.6    .035       0  4701.8      .1       0
  4997.9     .05       0  5059.6      .1       0  5081.5     .05       0
  5722.4    .035       0  5897.1     .05       0
Bank Sta=4997.9,5059.6
XS Rating Curve= 0 ,0
Exp/Cntr=0.3,0.1

Type RM Length L Ch R = 1 ,140164  ,1251,1251,1251
BEGIN DESCRIPTION:
SANDY FORK 96.0
END DESCRIPTION:
XS GIS Cut Line= 3
      2454399.88     13800996.77      2453857.89     13801735.84
      2452393.82     13803319.58
#Sta/Elev= 30
    3967  413.58  4119.4  411.68  4370.2  396.08  4501.2  392.37  4692.1  388.72
  4763.1  389.81  4792.4  385.11  4813.3  384.56  4941.5  389.76  4970.1  385.75
  4974.1  380.26  4975.6  379.26  5035.8  380.26  5040.7   389.6  5047.5  390.15
  5257.3  388.12  5360.9  387.97  5408.5  387.13  5437.1  385.61  5634.9  388.44
  5828.9  394.31  5960.4   393.5  5996.1  391.63  6024.5   385.5  6038.6  389.28
  6158.9  390.65  6420.8  402.77  6753.1  410.13  6873.3  408.56  7040.3  413.33
#Mann= 9 ,-1 , 0
    3967     .05       0  4501.2      .1       0  4970.1     .07       0
  4974.1     .05       0  5035.8     .07       0  5257.3      .1       0
  5360.9     .12       0  5408.5     .05       0  5828.9     .12       0
Bank Sta=4974.1,5035.8
XS Rating Curve= 0 ,0
Exp/Cntr=0.3,0.1

Type RM Length L Ch R = 1 ,138913  ,848,848,848
BEGIN DESCRIPTION:
SANDY FORK 95.0
END DESCRIPTION:
XS GIS Cut Line= 3
       2453681.9     13800891.18      2452795.01      13801510.6
      2451929.61     13803227.33
#Sta/Elev= 30
  3623.1  411.82  3724.4  410.98  4010.5  415.08  4132.6  410.72  4183.6  405.96
  4348.7  395.96  4523.5  395.26    4623  395.99  4678.9  394.34  4804.9  386.45
  4916.5  388.13    4945  385.39  4946.9  379.19  4948.4  378.19  5008.6  379.19
  5012.2  384.65  5034.6   388.9  5111.6  384.38  5133.9  386.45  5334.7   387.2
  5379.3  384.85  5392.9  382.01  5446.7  391.26  5462.9  392.95    5647  402.22
  5818.7  403.67  6006.7  406.74  6182.3  412.33  6317.5  411.82  6627.4  414.63
#Mann= 14 ,-1 , 0
  3623.1     .05       0  4132.6     .12       0  4183.6     .05       0
  4348.7     .12       0  4523.5      .1       0    4623     .12       0
  4678.9      .1       0  4946.9     .05       0  5008.6      .1       0
  5446.7     .12       0  5462.9     .07       0  5818.7     .05       0
  6006.7     .07       0  6317.5     .12       0
Bank Sta=4946.9,5008.6
XS Rating Curve= 0 ,0
Exp/Cntr=0.3,0.1

Type RM Length L Ch R = 1 ,138065  ,505,505,505
BEGIN DESCRIPTION:
E20668
END DESCRIPTION:
XS GIS Cut Line= 3
      2453555.19     13800799.67      2452013.69     13801369.82
      2450655.19     13802608.65
#Sta/Elev= 30
  3274.3  409.92    3573  412.11  3711.6  405.97  3839.3  398.82  4020.1  394.23
  4227.6  395.49  4415.3  386.35  4531.3  386.87  4666.8  387.27  4729.8  384.11
  4767.2   387.6  4834.2   386.5  4934.7  389.24  4942.1  388.42  4946.1  377.16
  4947.6  376.16  5008.3  377.16  5012.4  382.39  5083.3  387.47  5175.2  383.02
  5203.6  387.51  5227.5  386.62  5651.2  384.81  5788.1  387.18  6052.7  394.19
  6061.8  394.13  6208.9  397.69  6329.2  404.94  6534.6  408.73  6756.4   417.7
#Mann= 13 ,-1 , 0
  3274.3     .05       0  3711.6     .12       0  3839.3     .05       0
  4531.3     .12       0  4666.8     .05       0  4729.8      .1       0
  4946.1     .05       0  5008.3      .1       0  5227.5     .05       0
  5651.2    .035       0  5788.1     .05       0  6052.7     .07       0
  6061.8     .12       0
Bank Sta=4946.1,5008.3
XS Rating Curve= 0 ,0
Exp/Cntr=0.3,0.1

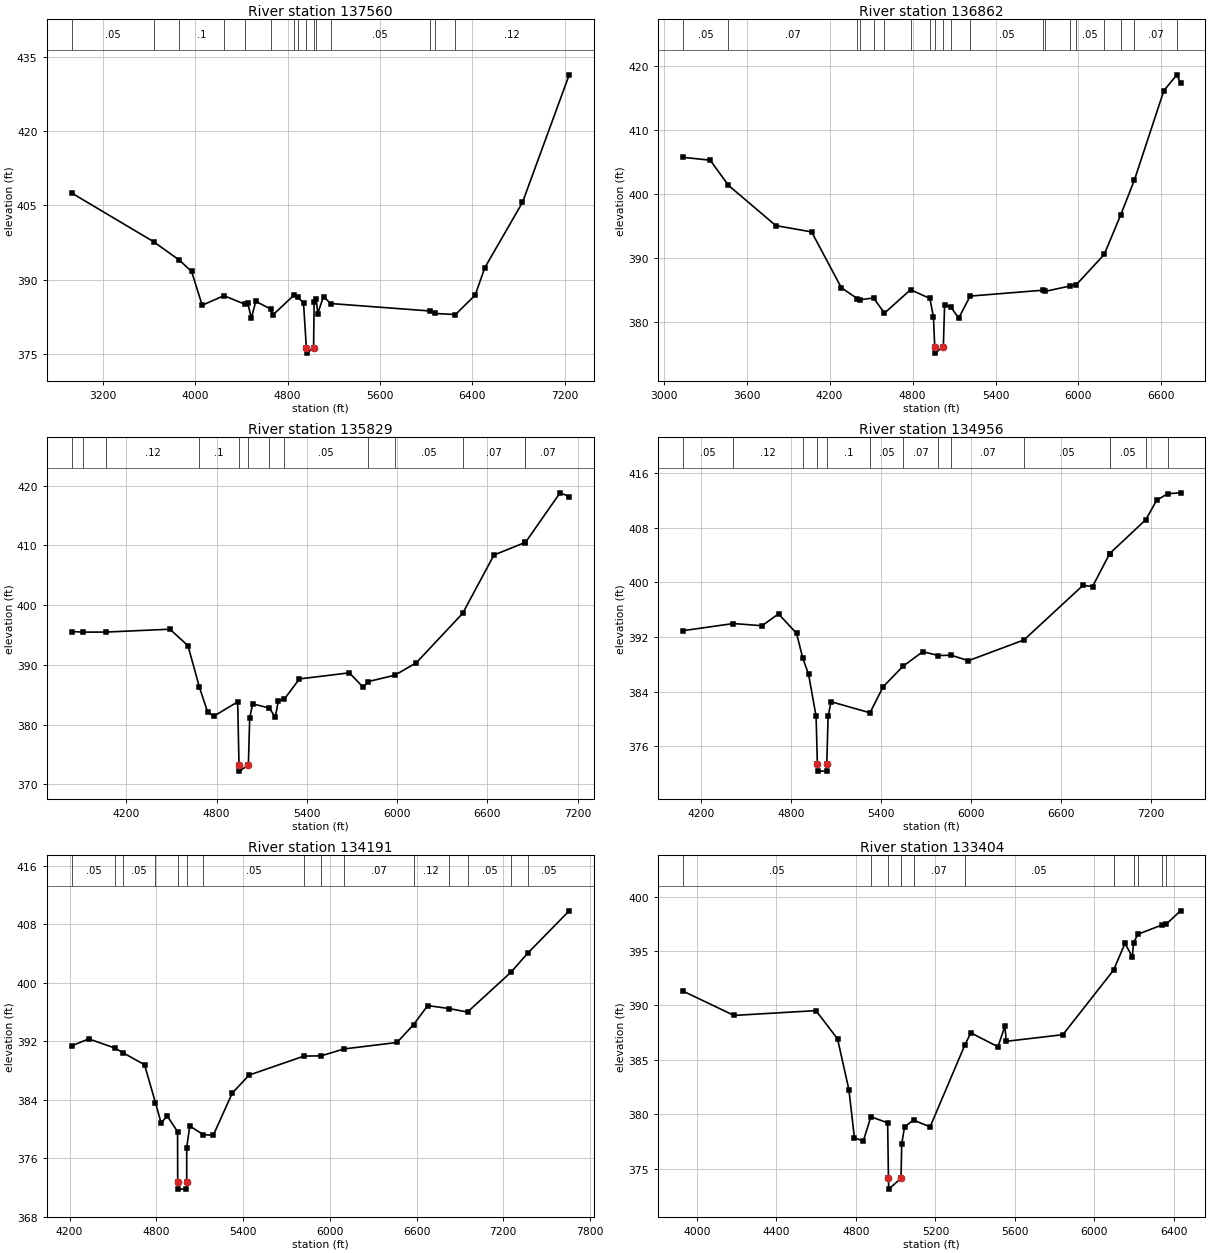
Type RM Length L Ch R = 1 ,137560  ,698,698,698
BEGIN DESCRIPTION:
E20667
END DESCRIPTION:
XS GIS Cut Line= 3
      2453527.03     13800426.61      2451352.02     13801214.96
      2449430.35     13801735.86
#Sta/Elev= 30
  2932.1  407.51  3643.9  397.65  3865.2  393.94  3970.2   391.7  4062.1  384.87
    4250   386.8    4433  385.06  4455.3   385.4  4487.2  382.25  4525.6  385.66
  4654.1  384.11  4673.4  382.92  4854.7  386.86  4888.4   386.5  4938.4  385.37
  4963.3  376.22  4964.8  375.22  5025.5  376.22  5030.3  385.57  5048.3  386.09
  5061.6   383.2  5111.5  386.63  5172.1  385.22  6029.9  383.72  6071.9  383.22
  6252.9     383  6423.6  386.93  6506.5  392.44  6832.4   405.6  7236.6  431.32
#Mann= 15 ,-1 , 0
  2932.1     .05       0  3643.9     .07       0  3865.2      .1       0
    4250     .07       0    4433     .12       0  4654.1      .1       0
  4854.7     .07       0  4888.4      .1       0  4963.3     .05       0
  5025.5      .1       0  5048.3    .035       0  5172.1     .05       0
  6029.9     .07       0  6071.9     .05       0  6252.9     .12       0
Bank Sta=4963.3,5025.5
XS Rating Curve= 0 ,0
Exp/Cntr=0.3,0.1

Type RM Length L Ch R = 1 ,136862  ,1033,1033,1033
BEGIN DESCRIPTION:
E20666
END DESCRIPTION:
XS GIS Cut Line= 3
      2453470.77     13800236.54      2451415.37     13800511.07
      2449894.98     13800623.69
#Sta/Elev= 30
  3139.6  405.74  3337.1  405.29  3469.2  401.35  3811.3  395.04  4070.3  394.05
  4285.5   385.3    4400  383.61  4418.7  383.42  4518.4  383.69  4597.3  381.32
  4785.6  384.99  4925.6  383.62  4951.3   380.7  4960.6  376.05  4962.1  375.05
  5022.8  376.05    5032  382.61  5075.6  382.32  5133.8  380.54  5216.7  383.99
  5741.7  384.91  5759.9  384.73    5942  385.59  5983.6  385.76  6185.7  390.51
  6305.4  396.71  6404.3  402.18  6617.5  416.21  6711.6  418.67  6737.8  417.42
#Mann= 20 ,-1 , 0
  3139.6     .05       0  3469.2     .07       0    4400      .1       0
  4418.7     .07       0  4518.4     .12       0  4597.3      .1       0
  4785.6     .07       0  4925.6      .1       0  4960.6     .05       0
  5022.8      .1       0  5075.6    .035       0  5216.7     .05       0
  5741.7     .07       0  5759.9     .05       0    5942     .07       0
  5983.6     .05       0  6185.7     .07       0  6305.4     .12       0
  6404.3     .07       0  6711.6     .07       0
Bank Sta=4960.6,5022.8
XS Rating Curve= 0 ,0
Exp/Cntr=0.3,0.1

Type RM Length L Ch R = 1 ,135829  ,873,873,873
BEGIN DESCRIPTION:
E20665
END DESCRIPTION:
XS GIS Cut Line= 3
      2453238.49      13799757.9      2451513.92     13799814.21
      2449965.39     13800137.99
#Sta/Elev= 30
  3835.9  395.57  3913.7  395.47  4065.3  395.48  4489.7  395.96  4609.8  393.19
  4686.2  386.21  4739.9  382.13  4779.9  381.39    4940   383.8  4948.8  373.21
  4950.3  372.21  5011.1  373.21    5020  381.18    5040  383.47  5150.3  382.76
  5190.1  381.23  5210.1  384.01    5249  384.22  5350.2  387.64  5682.6  388.66
  5774.8  386.21  5804.9  387.18  5984.5  388.26  6127.2  390.34  6435.5  398.62
  6643.2  408.37  6846.8  410.44  6852.7  410.48  7082.5  418.78  7143.4  418.16
#Mann= 13 ,-1 , 0
  3835.9     .07       0  3913.7     .05       0  4065.3     .12       0
  4686.2      .1       0  4948.8     .05       0  5011.1      .1       0
  5150.3     .07       0    5249     .05       0  5804.9    .035       0
  5984.5     .05       0  6435.5     .07       0  6846.8     .05       0
  6852.7     .07       0
Bank Sta=4948.8,5011.1
XS Rating Curve= 0 ,0
Exp/Cntr=0.3,0.1

Type RM Length L Ch R = 1 ,134956  ,765,765,765
BEGIN DESCRIPTION:
E20664
END DESCRIPTION:
XS GIS Cut Line= 4
      2453041.42      13798927.3      2451394.26     13799004.73
      2450744.17     13799231.87      2449992.94      13799857.9
#Sta/Elev= 30
  4079.8  392.91  4415.5  393.96  4606.8  393.64  4716.9  395.37  4837.1  392.53
    4878  388.93  4917.1  386.53  4967.2  380.39    4976  373.35  4977.5  372.35
  5036.9  372.35  5038.4  373.35  5047.3   380.4  5067.3  382.51  5326.5  380.89
  5413.9   384.7  5544.9  387.68    5678  389.84  5782.2  389.28  5867.1  389.32
  5982.1  388.52  6352.3  391.56  6745.4  399.55  6809.2  399.38  6922.9  404.18
  6923.1   404.2  7164.3  409.18  7236.1     412    7309  412.97  7395.3   413.1
#Mann= 14 ,-1 , 0
  4079.8     .05       0  4415.5     .12       0    4878      .1       0
    4976     .05       0  5038.4      .1       0  5326.5     .05       0
  5544.9     .07       0  5782.2     .05       0  5867.1     .07       0
  6352.3     .05       0  6922.9    .035       0  6923.1     .05       0
  7164.3     .07       0    7309     .12       0
Bank Sta=4976,5038.4
XS Rating Curve= 0 ,0
Exp/Cntr=0.3,0.1

Type RM Length L Ch R = 1 ,134191  ,787,787,787
BEGIN DESCRIPTION:
E20663
END DESCRIPTION:
XS GIS Cut Line= 5
      2452879.45     13798427.53      2452062.96     13798188.21
       2451401.3     13798279.72      2451089.14      13798473.2
      2449956.59      13799540.1
#Sta/Elev= 30
  4213.8  391.38  4333.1  392.33  4517.3  391.05  4567.1  390.46  4718.6   388.8
  4793.9  383.62  4833.3  380.82  4874.9   381.8  4947.1  379.64  4947.9  372.78
  4949.4  371.78  5008.8  371.78  5010.3  372.78  5010.4  377.47  5031.3  380.41
  5125.7  379.23  5193.8  379.14  5325.1  384.91  5441.9  387.38  5821.3  389.98
  5940.4  390.01  6096.2  390.95  6464.7  391.84  6579.1  394.28  6677.1  396.89
  6825.8  396.48  6952.4     396  7254.9  401.49  7369.6  404.07  7655.8  409.85
#Mann= 15 ,-1 , 0
  4213.8     .05       0  4517.3    .035       0  4567.1     .05       0
  4793.9      .1       0  4947.9     .05       0  5010.3      .1       0
  5125.7     .05       0  5821.3     .07       0  5940.4    .035       0
  6096.2     .07       0  6579.1     .12       0  6825.8     .07       0
  6952.4     .05       0  7254.9    .035       0  7369.6     .05       0
Bank Sta=4947.9,5010.3
XS Rating Curve= 0 ,0
Exp/Cntr=0.3,0.1

Type RM Length L Ch R = 1 ,133404  ,618,618,618
BEGIN DESCRIPTION:
E20662
END DESCRIPTION:
XS GIS Cut Line= 3
       2452879.5     13798357.18      2452316.36     13797498.39
       2451154.9      13796583.3
#Sta/Elev= 30
  3928.7  391.32  4185.8  389.08  4598.8  389.52  4707.3  386.93  4764.5  382.27
  4792.3  377.84  4836.9  377.53  4875.5  379.77  4959.7  379.21  4963.7  374.12
  4965.2  373.12    5027  374.12  5030.6   377.3  5045.1  378.85  5090.2  379.46
  5173.4  378.84  5348.3  386.36  5378.5  387.48  5514.9   386.2  5550.2   388.1
  5556.5   386.7    5842  387.31  6097.1  393.24  6154.6   395.7  6191.6  394.46
  6197.7  395.76  6219.7  396.54  6342.3   397.4  6362.7  397.47  6434.3  398.69
#Mann= 11 ,-1 , 0
  3928.7     .05       0  4875.5      .1       0  4963.7     .05       0
    5027      .1       0  5090.2     .07       0  5348.3     .05       0
  6097.1    .035       0  6197.7     .07       0  6219.7     .05       0
  6342.3     .07       0  6362.7    .035       0
Bank Sta=4963.7,5027
XS Rating Curve= 0 ,0
Exp/Cntr=0.3,0.1

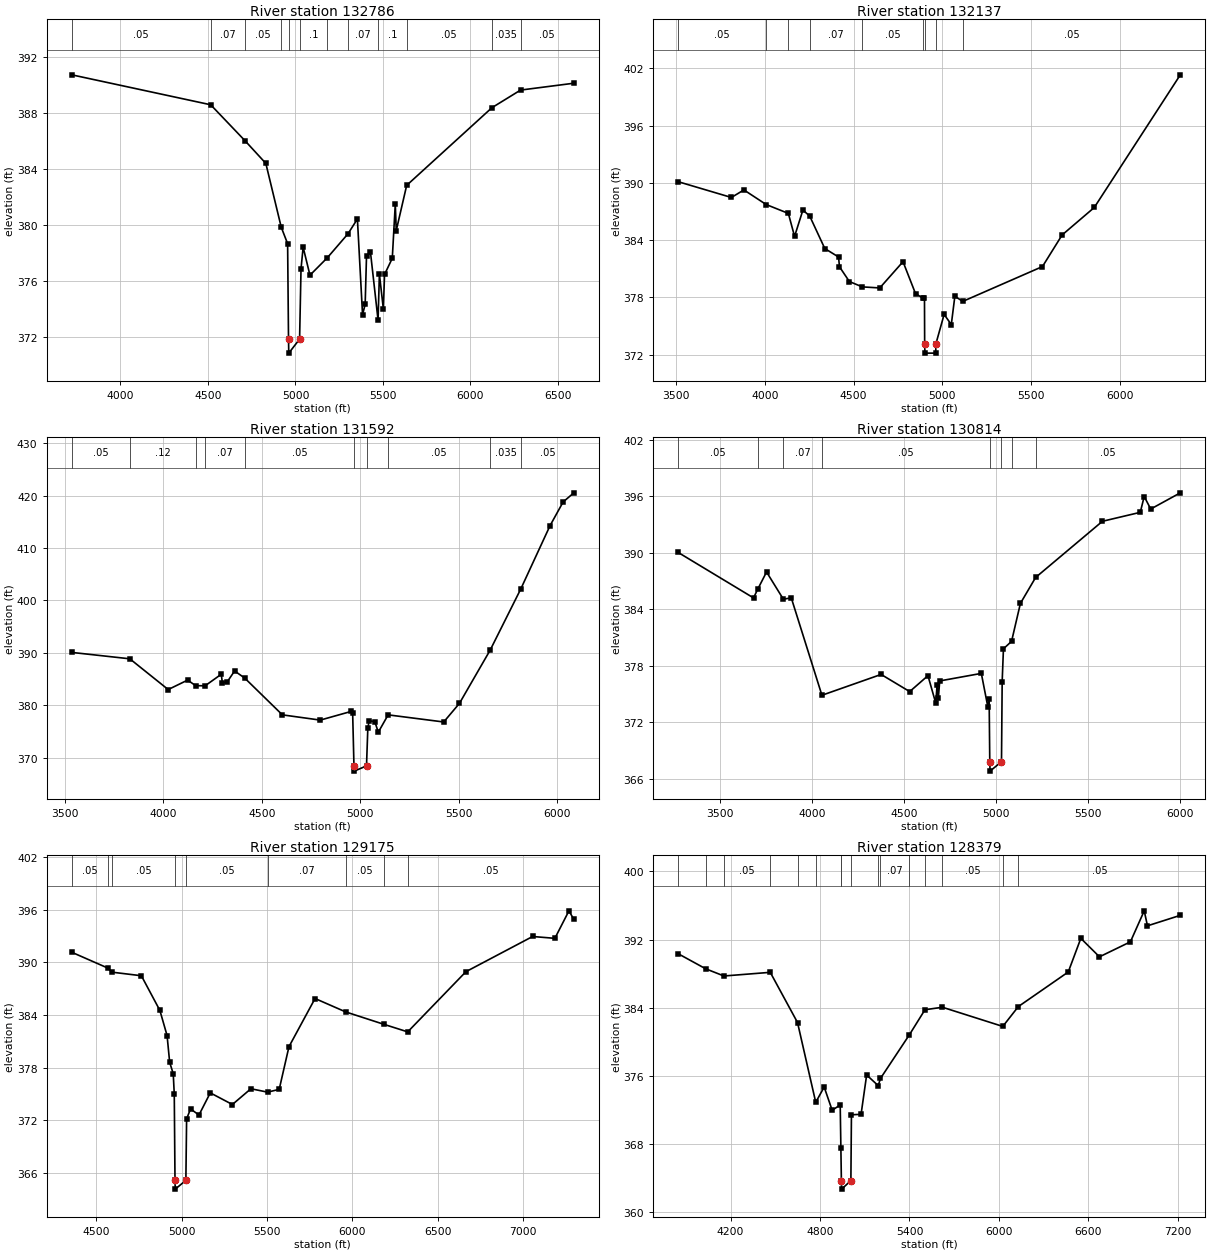
Type RM Length L Ch R = 1 ,132786  ,649,649,649
BEGIN DESCRIPTION:
E20661
END DESCRIPTION:
XS GIS Cut Line= 3
      2452886.52     13798265.64      2452668.31     13797083.09
      2451951.11     13795578.39
#Sta/Elev= 30
  3721.6  390.71  4515.5  388.57  4713.2  385.98  4830.7  384.38  4918.7  379.82
  4955.2  378.64  4960.3  371.82  4961.8  370.82  5023.6  371.82  5031.8  376.85
  5043.9  378.39  5082.8  376.39  5182.4  377.64  5300.3  379.35    5354  380.41
  5383.4  373.57  5398.3   374.3  5406.1  377.75  5428.8  378.02  5472.1  373.18
  5479.7  376.47  5502.4  373.97  5509.1  376.44  5553.4   377.6  5570.5  381.48
    5576  379.58  5635.6  382.81  6122.7  388.36  6286.5  389.62    6591  390.11
#Mann= 12 ,-1 , 0
  3721.6     .05       0  4515.5     .07       0  4713.2     .05       0
  4918.7      .1       0  4960.3     .05       0  5023.6      .1       0
  5182.4     .05       0  5300.3     .07       0  5472.1      .1       0
  5635.6     .05       0  6122.7    .035       0  6286.5     .05       0
Bank Sta=4960.3,5023.6
XS Rating Curve= 0 ,0
Exp/Cntr=0.3,0.1

Type RM Length L Ch R = 1 ,132137  ,545,545,545
BEGIN DESCRIPTION:
E20660
END DESCRIPTION:
XS GIS Cut Line= 3
      2452942.83     13798202.28      2453097.69     13796900.08
      2453273.66      13795393.7
#Sta/Elev= 30
  3511.9  390.12  3811.3  388.47  3881.8  389.26  4007.2  387.73  4132.2   386.8
  4167.1  384.39  4214.1  387.15  4252.5  386.52  4337.4  383.12    4415  382.23
    4420  381.21  4475.9  379.66  4548.8   379.1  4647.1  378.99    4778  381.74
  4848.5  378.39  4887.8  377.95  4898.9   377.9  4899.9  373.16  4901.4  372.16
  4962.1  372.16  4963.6  373.16  5009.6  376.22  5049.9  375.15    5070  378.12
  5114.6  377.58  5563.4  381.23  5674.1  384.54  5855.3  387.42  6339.9  401.32
#Mann= 9 ,-1 , 0
  3511.9     .05       0  4007.2     .12       0  4132.2     .05       0
  4252.5     .07       0  4548.8     .05       0  4887.8    .035       0
  4899.9    .035       0  4963.6    .035       0  5114.6     .05       0
Bank Sta=4899.9,4963.6
XS Rating Curve= 0 ,0
Exp/Cntr=0.3,0.1

Type RM Length L Ch R = 1 ,131592  ,778,778,778
BEGIN DESCRIPTION:
E20659
END DESCRIPTION:
XS GIS Cut Line= 3
      2453020.24     13798195.28      2453541.14     13796977.51
      2454054.98     13795865.37
#Sta/Elev= 30
  3535.1  390.08  3829.8  388.86  4024.8  382.99  4123.7   384.8    4164  383.73
  4212.3  383.71  4294.3  385.91  4299.7  384.29  4323.3  384.39    4362  386.54
  4413.4  385.18  4604.6  378.16  4797.1  377.16  4954.1  378.82  4961.5  378.45
  4968.1  368.42  4969.6  367.42  5031.8  368.42  5038.6  375.71  5045.9  377.06
  5074.3  376.82  5091.7  374.85  5141.6  378.16  5423.9   376.8  5503.7  380.35
  5660.1  390.54  5815.9  402.24  5963.9  414.28  6030.3   418.8  6084.7  420.54
#Mann= 10 ,-1 , 0
  3535.1     .05       0  3829.8     .12       0    4164    .035       0
  4212.3     .07       0  4413.4     .05       0  4968.1     .05       0
  5031.8     .05       0  5141.6     .05       0  5660.1    .035       0
  5815.9     .05       0
Bank Sta=4968.1,5031.8
XS Rating Curve= 0 ,0
Exp/Cntr=0.3,0.1

Type RM Length L Ch R = 1 ,130814  ,1639,1639,1639
BEGIN DESCRIPTION:
E20658
END DESCRIPTION:
XS GIS Cut Line= 3
      2453041.38     13798279.71      2454421.01     13796977.51
      2454976.25     13796359.01
#Sta/Elev= 30
  3274.5  390.02  3683.6   385.2  3706.6  386.13  3754.4  387.95  3845.8  385.06
  3888.7  385.21  4055.3  374.87    4377  377.08  4532.3  375.26  4631.5  376.95
  4673.9  374.03  4681.2  375.98  4688.1  374.61  4695.4  376.39  4921.5  377.19
  4957.1  373.62    4964  374.48  4967.4  367.82  4968.9  366.82  5031.1  367.82
  5034.8  376.33  5041.7   379.8  5085.8  380.59  5133.9  384.62  5216.6  387.37
  5579.6  393.33  5785.2  394.28  5806.6  395.96    5842  394.63  6002.8  396.35
#Mann= 8 ,-1 , 0
  3274.5     .05       0  3706.6    .035       0  3845.8     .07       0
  4055.3     .05       0  4967.4     .05       0  5031.1     .05       0
  5085.8    .035       0  5216.6     .05       0
Bank Sta=4967.4,5031.1
XS Rating Curve= 0 ,0
Exp/Cntr=0.3,0.1

Type RM Length L Ch R = 1 ,129175  ,796,796,796
BEGIN DESCRIPTION:
E20657
END DESCRIPTION:
XS GIS Cut Line= 3
      2453203.23     13798596.49      2454554.75     13797709.56
      2455061.54     13796484.82
#Sta/Elev= 30
  4355.2  391.16    4566  389.36  4589.6  388.89    4763  388.48  4871.5  384.52
  4913.7  381.65  4928.8   378.6  4949.8  377.29  4955.8  374.96  4960.1  365.12
  4961.6  364.12  5023.8  365.12  5028.1  372.13  5051.1  373.28  5100.5  372.58
  5166.8  375.11  5296.4  373.78  5404.9  375.58  5502.7  375.19  5570.7  375.51
  5627.9  380.38  5780.7  385.88  5960.3  384.35  6184.8  382.93  6323.7  382.07
  6664.7  388.94  7055.7  392.96    7186  392.75  7268.5  395.89  7297.2  394.91
#Mann= 9 ,-1 , 0
  4355.2     .05       0    4566     .07       0  4589.6     .05       0
  4960.1     .05       0  5023.8     .05       0  5502.7     .07       0
  5960.3     .05       0  6184.8    .035       0  6323.7     .05       0
Bank Sta=4960.1,5023.8
XS Rating Curve= 0 ,0
Exp/Cntr=0.3,0.1

Type RM Length L Ch R = 1 ,128379  ,621,621,621
BEGIN DESCRIPTION:
E20656
END DESCRIPTION:
XS GIS Cut Line= 4
      2453703.02     13799222.95      2454343.58      13798638.7
      2454575.87     13798054.47      2455251.39     13796309.36
#Sta/Elev= 30
  3849.2  390.34  4033.9  388.57  4155.9  387.73  4466.3  388.16  4649.1  382.27
  4771.3   372.9  4827.8   374.7  4881.6  371.96  4935.4   372.6  4939.9  367.54
  4943.3  363.71  4944.8  362.71    5007  363.71  5010.7  371.44  5075.3  371.49
  5112.7  376.11  5190.1  374.86  5205.6  375.71  5399.4  380.83  5503.8  383.77
  5621.1  384.06  6025.7  381.81    6130  384.14  6464.7   388.2  6549.1  392.15
    6674  389.98  6881.5  391.74  6974.2  395.38  6995.9  393.62  7216.2  394.85
#Mann= 16 ,-1 , 0
  3849.2     .05       0  4033.9     .07       0  4155.9     .05       0
  4466.3     .07       0  4649.1    .035       0  4771.3     .05       0
  4939.9      .1       0  4943.3     .05       0    5007      .1       0
  5190.1     .05       0  5205.6     .07       0  5399.4     .12       0
  5503.8     .07       0  5621.1     .05       0  6025.7    .035       0
    6130     .05       0
Bank Sta=4943.3,5007
XS Rating Curve= 0 ,0
Exp/Cntr=0.3,0.1