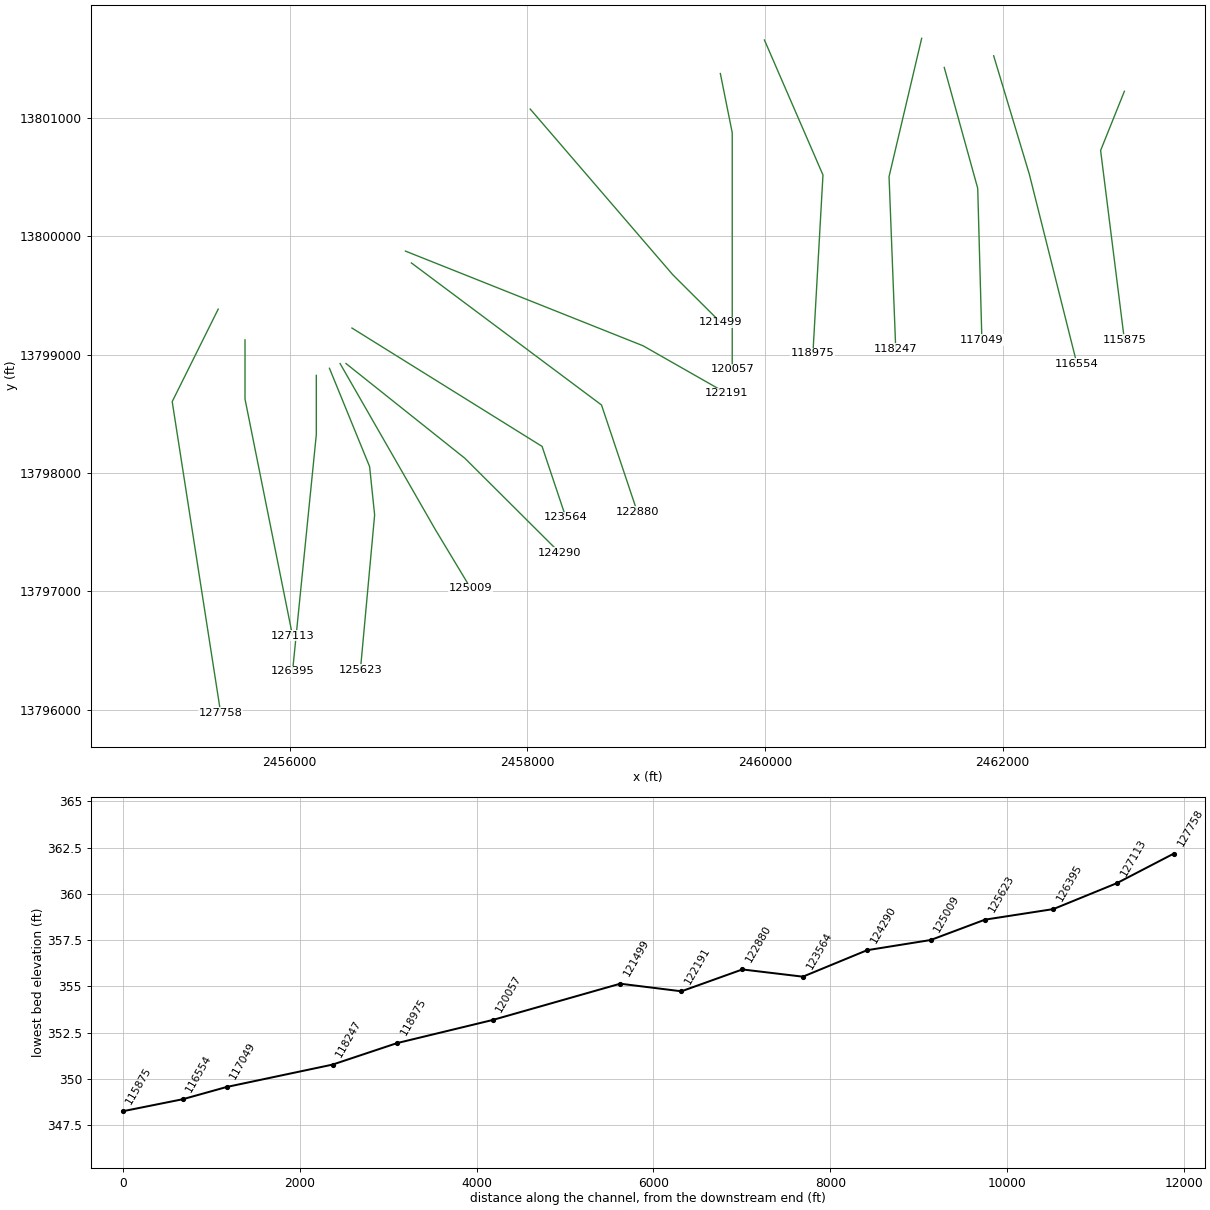
HEC-RAS study SANDY FORK.prj: SANDY FORK Base Level Engineering

--- SANDY FORK.g01 (geometry) --- (continued)

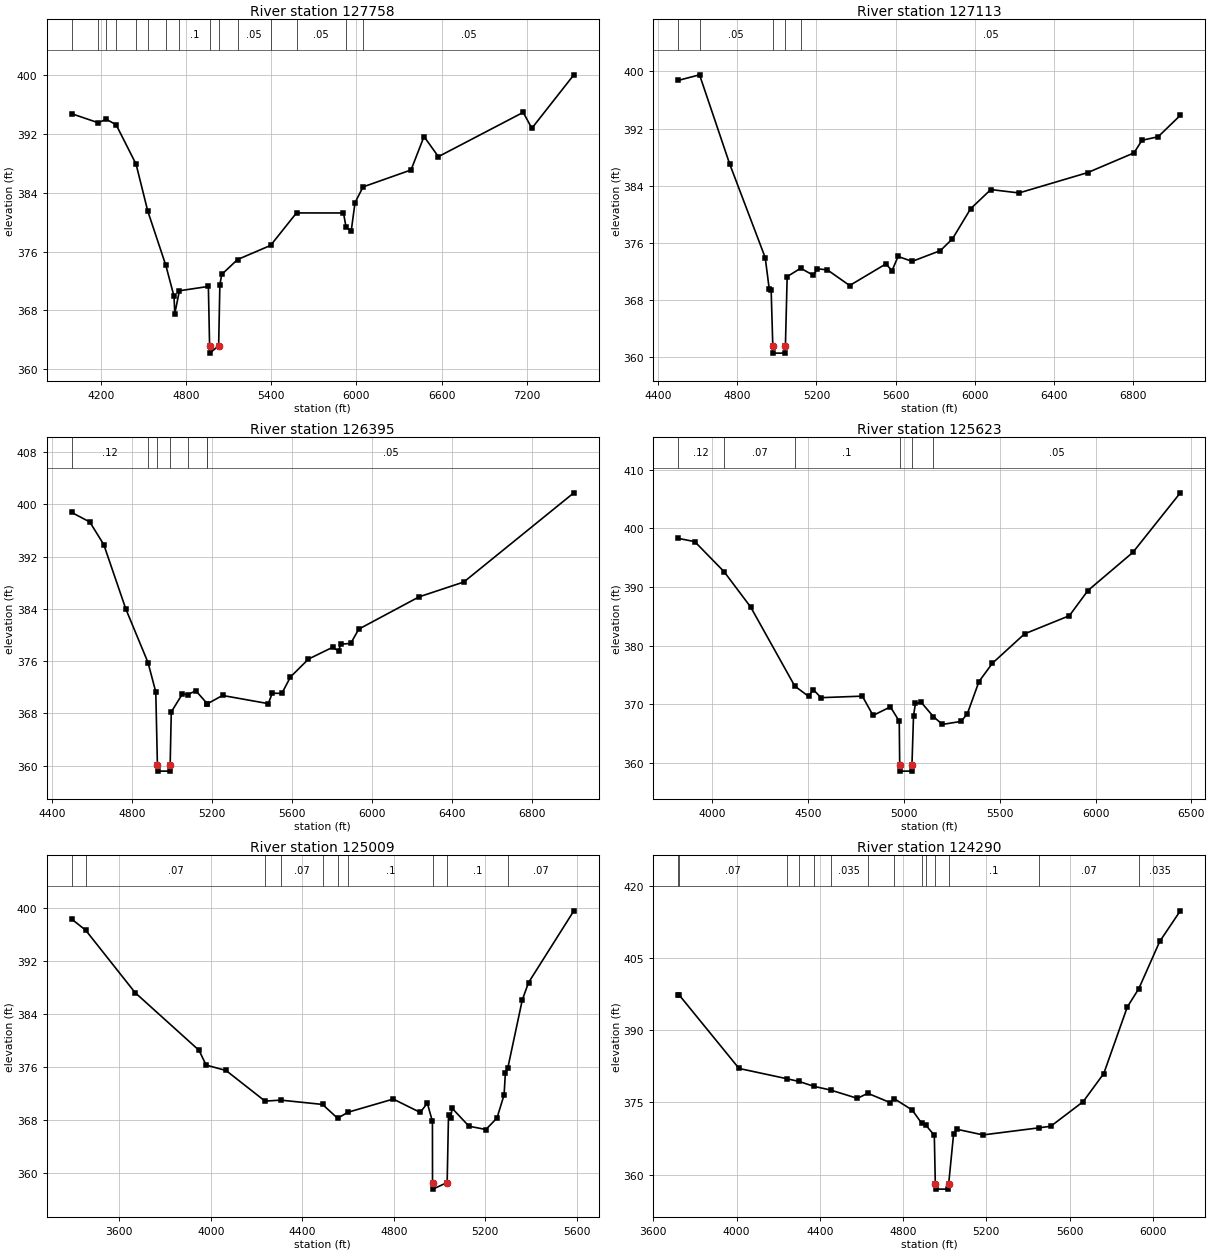
Type RM Length L Ch R = 1 ,127758  ,645,645,645
BEGIN DESCRIPTION:
E20655
END DESCRIPTION:
XS GIS Cut Line= 3
      2455399.44     13799384.86      2455012.28     13798603.51
      2455420.27     13795972.67
#Sta/Elev= 30
  3995.7  394.77  4181.2  393.55  4238.6  394.02  4307.8  393.28  4448.3  387.91
  4530.6  381.52    4658  374.12  4715.3  369.92    4721  367.57  4753.4  370.67
  4957.3  371.26  4965.9  363.18  4967.4  362.18  5029.6  363.18  5038.2  371.45
    5051  372.89  5162.6  374.92  5395.5  376.85  5577.7  381.27  5908.5  381.26
  5926.8  379.29  5963.1  378.84  5989.5  382.66    6046  384.81  6384.1  387.12
  6475.2  391.67  6576.4  388.93  7173.5  394.96  7234.2  392.79    7530  400.07
#Mann= 15 ,-1 , 0
  3995.7    .035       0  4181.2     .05       0  4238.6     .07       0
  4307.8     .05       0  4448.3     .07       0  4530.6     .05       0
    4658     .07       0  4753.4      .1       0  4965.9     .05       0
  5029.6      .1       0  5162.6     .05       0  5395.5     .07       0
  5577.7     .05       0  5926.8     .07       0    6046     .05       0
Bank Sta=4965.9,5029.6
XS Rating Curve= 0 ,0
Exp/Cntr=0.3,0.1

Type RM Length L Ch R = 1 ,127113  ,718,718,718
BEGIN DESCRIPTION:
SANDY FORK 90.0
END DESCRIPTION:
XS GIS Cut Line= 3
        2455625.     13799125.02        2455625.       13798625.
        2456025.     13796625.02
#Sta/Elev= 30
  4500.8  398.75  4608.6  399.53  4760.8  387.07  4940.8  373.94  4960.8  369.61
  4970.8  369.38  4979.1  361.58  4980.6  360.58  5041.4  360.58  5042.9  361.58
  5051.8  371.29  5120.2  372.46  5184.4  371.47  5204.8  372.39  5255.8  372.22
  5367.9  370.04  5551.5  373.07  5582.1  372.11  5612.7  374.11  5684.1  373.42
  5826.9  374.93    5888  376.58  5979.8  380.79  6081.8  383.47  6224.6     383
  6571.3  385.84  6805.9   388.6  6846.7  390.37  6928.2  390.86  7040.4  393.86
#Mann= 5 ,-1 , 0
  4500.8     .12       0  4608.6     .05       0  4979.1     .05       0
  5042.9     .05       0  5120.2     .05       0
Bank Sta=4979.1,5042.9
XS Rating Curve= 0 ,0
Exp/Cntr=0.3,0.1

Type RM Length L Ch R = 1 ,126395  ,772,772,772
BEGIN DESCRIPTION:
SANDY FORK 89.0
END DESCRIPTION:
XS GIS Cut Line= 3
        2456225.     13798825.02        2456225.       13798325.
        2456025.       13796325.
#Sta/Elev= 30
  4499.7  398.76  4589.7  397.31  4659.7  393.85  4769.7  384.01  4880.9  375.79
  4919.7  371.29  4927.8  360.18  4929.3  359.18  4990.1  359.18  4991.6  360.18
  4997.2  368.24  5052.5  370.98  5078.4  370.89  5120.3  371.47  5177.5  369.48
  5177.8  369.49  5253.5  370.76  5482.1  369.51  5502.2  371.11    5550  371.07
  5592.7  373.58  5683.1  376.33  5803.7  378.13  5833.9  377.56  5843.9  378.61
  5894.2  378.72  5934.4  380.91  6235.9  385.85  6459.5  388.12  7009.7  401.77
#Mann= 7 ,-1 , 0
  4499.7     .12       0  4880.9      .1       0  4927.8     .05       0
  4991.6      .1       0  5078.4     .05       0  5177.5     .07       0
  5177.8     .05       0
Bank Sta=4927.8,4991.6
XS Rating Curve= 0 ,0
Exp/Cntr=0.3,0.1

Type RM Length L Ch R = 1 ,125623  ,614,614,614
BEGIN DESCRIPTION:
E20654
END DESCRIPTION:
XS GIS Cut Line= 4
      2456335.59      13798885.1      2456673.48     13798054.47
      2456715.71     13797646.21      2456596.19     13796338.52
#Sta/Elev= 30
  3822.1  398.28  3908.3  397.72  4061.4   392.6    4200  386.58  4430.4   373.1
  4502.5  371.35  4526.6  372.51  4567.1  371.13  4782.9  371.39  4838.9   368.1
  4929.4  369.56  4975.6  367.11  4977.9  359.61  4979.4  358.61  5040.3  358.61
  5041.8  359.61    5050  368.03  5060.1  370.15  5090.3  370.33  5153.2  367.92
  5200.8  366.57    5299  367.09  5331.3  368.42  5391.6  373.87  5461.8     377
  5629.5     382  5863.5   385.1    5960  389.38  6194.9  395.89  6442.4  406.04
#Mann= 6 ,-1 , 0
  3822.1     .12       0  4061.4     .07       0  4430.4      .1       0
  4977.9     .05       0  5041.8      .1       0  5153.2     .05       0
Bank Sta=4977.9,5041.8
XS Rating Curve= 0 ,0
Exp/Cntr=0.3,0.1

Type RM Length L Ch R = 1 ,125009  ,719,719,719
BEGIN DESCRIPTION:
SANDY FORK 88.0
END DESCRIPTION:
XS GIS Cut Line= 3
      2456425.02     13798924.97        2457225.       13797525.
      2457524.99     13797025.01
#Sta/Elev= 30
  3391.7  398.31  3452.5  396.64  3668.8   387.2  3948.1  378.49  3979.1  376.26
  4066.2  375.44  4236.9  370.81  4305.6  370.96  4488.2  370.31  4554.1  368.22
  4599.7  369.13  4797.5  371.12  4915.6   369.1  4946.5  370.51  4968.8  367.74
  4969.2  358.51  4970.7  357.51  5033.2  358.51  5039.1  368.64  5048.8  368.21
  5054.7  369.74  5128.5  367.02  5202.4  366.52    5251  368.25  5282.1  371.75
  5287.9  375.13  5298.8  375.88  5361.8  386.11    5389  388.72  5587.2  399.57
#Mann= 10 ,-1 , 0
  3391.7     .12       0  3452.5     .07       0  4236.9      .1       0
  4305.6     .07       0  4488.2     .12       0  4554.1     .07       0
  4599.7      .1       0  4969.2     .05       0  5033.2      .1       0
  5298.8     .07       0
Bank Sta=4969.2,5033.2
XS Rating Curve= 0 ,0
Exp/Cntr=0.3,0.1

Type RM Length L Ch R = 1 ,124290  ,726,726,726
BEGIN DESCRIPTION:
SANDY FORK 87.0
END DESCRIPTION:
XS GIS Cut Line= 3
      2456475.03     13798924.97        2457475.       13798125.
      2458275.03     13797324.97
#Sta/Elev= 30
  3719.7  397.43  3723.1  397.41  4011.8  382.07  4243.1  379.92  4300.3  379.36
  4372.2  378.34  4452.4  377.57  4580.1  375.85  4630.4   376.9    4737  374.98
  4756.6   375.8  4844.2   373.4  4888.5   370.7  4908.7  370.31  4949.9  368.15
  4954.7  357.96  4956.2  356.96  5017.2  356.96  5018.7  357.96  5042.7  368.51
  5056.8  369.43  5184.1  368.24  5453.3  369.72  5509.4  370.04    5665  375.16
    5764  381.01  5877.1  394.87  5932.4  398.68  6032.7  408.49  6131.7  414.87
#Mann= 14 ,-1 , 0
  3719.7     .12       0  3723.1     .07       0  4243.1     .05       0
  4300.3     .07       0  4372.2     .05       0  4452.4    .035       0
  4630.4     .07       0  4756.6    .035       0  4888.5     .12       0
  4908.7      .1       0  4954.7     .05       0  5018.7      .1       0
  5453.3     .07       0  5932.4    .035       0
Bank Sta=4954.7,5018.7
XS Rating Curve= 0 ,0
Exp/Cntr=0.3,0.1

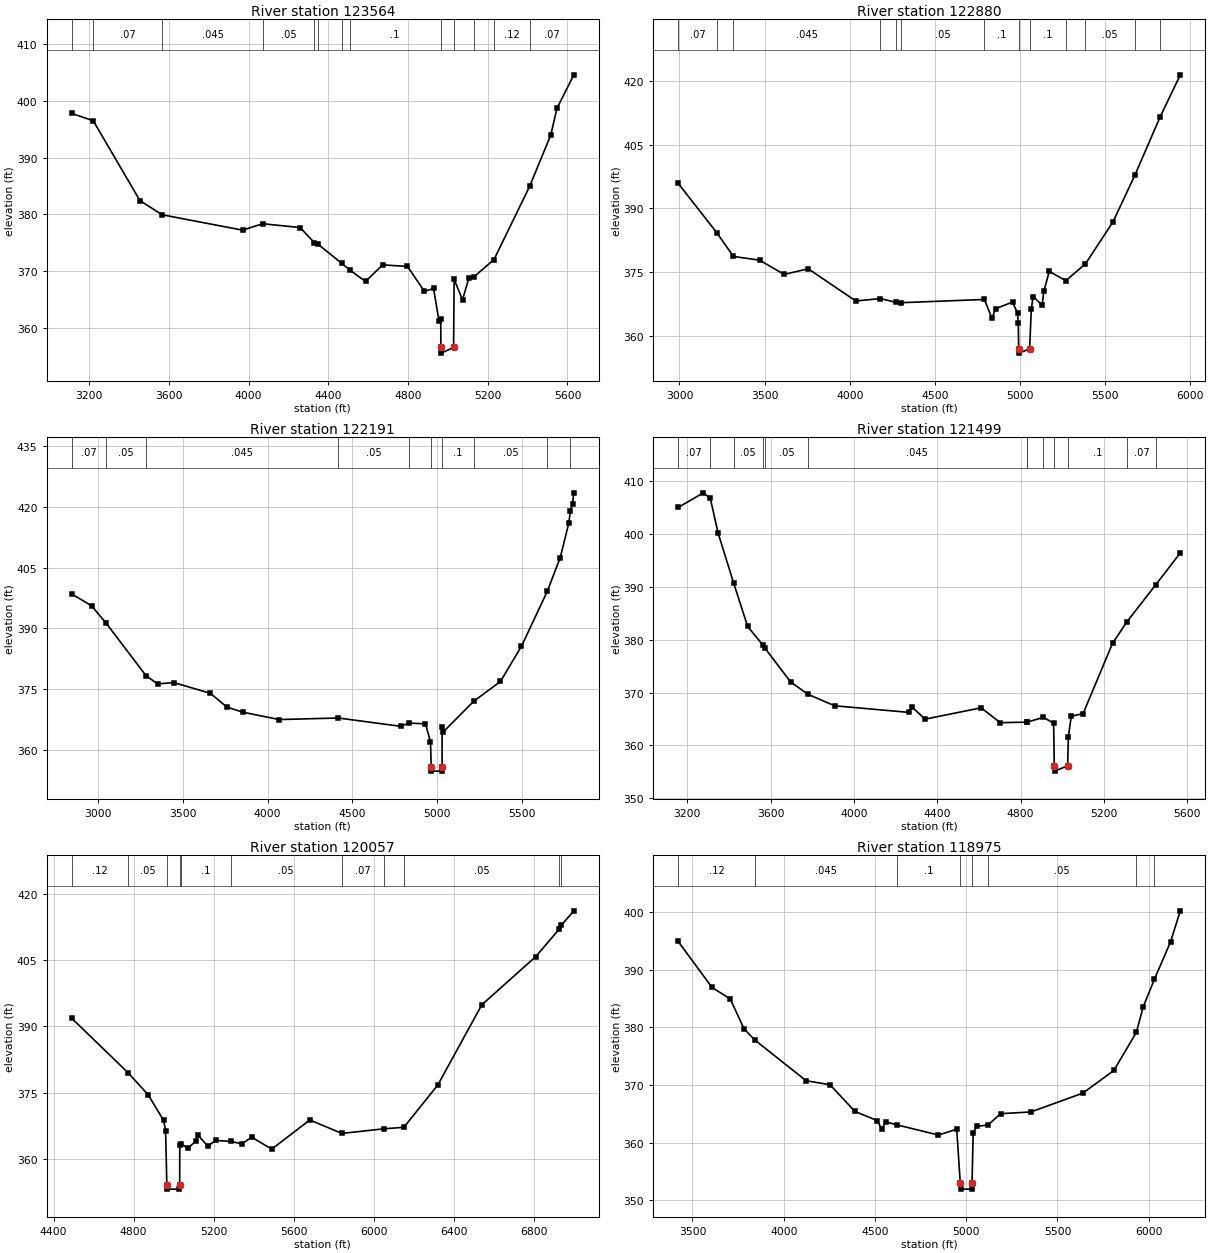
Type RM Length L Ch R = 1 ,123564  ,684,684,684
BEGIN DESCRIPTION:
SANDY FORK 86.0
END DESCRIPTION:
XS GIS Cut Line= 3
      2456524.97     13799225.02        2458125.       13798225.
        2458325.     13797624.99
#Sta/Elev= 30
  3112.7  397.78  3220.3   396.5  3454.7  382.42  3566.3  379.92  3969.5  377.21
  4071.1  378.34  4258.4  377.67  4329.3  375.03  4349.8  374.68  4468.1  371.34
  4506.9  370.21  4586.8  368.16  4672.3  371.09  4797.3  370.81  4882.2  366.42
  4928.2  366.93  4955.3  361.19  4964.2  361.51  4964.6  356.53  4966.1  355.53
  5028.6  356.53  5031.2  368.55  5073.3  364.93  5104.9  368.72  5131.6     369
  5231.4  372.03  5409.9  384.91    5516  393.96  5547.7  398.72    5632  404.59
#Mann= 13 ,-1 , 0
  3112.7     .12       0  3220.3     .07       0  3566.3    .045       0
  4071.1     .05       0  4329.3     .12       0  4349.8     .05       0
  4468.1     .07       0  4506.9      .1       0  4964.6     .05       0
  5028.6      .1       0  5131.6     .07       0  5231.4     .12       0
  5409.9     .07       0
Bank Sta=4964.6,5028.6
XS Rating Curve= 0 ,0
Exp/Cntr=0.3,0.1

Type RM Length L Ch R = 1 ,122880  ,689,689,689
BEGIN DESCRIPTION:
SANDY FORK 85.0
END DESCRIPTION:
XS GIS Cut Line= 3
      2457024.99     13799775.01        2458625.       13798575.
        2458925.     13797674.99
#Sta/Elev= 30
    2993  395.88  3218.8  384.31  3317.2  378.69  3471.1   377.8  3614.9  374.46
  3756.6  375.78  4035.7   368.2  4180.8  368.77  4272.4  367.86  4298.7  367.79
    4791  368.56  4835.7  364.09  4856.6  366.37  4956.6  367.95  4985.7  365.32
  4989.9  363.12  4992.6  356.92  4994.1  355.92  5056.6  356.92  5066.8  366.38
  5077.3  369.25    5130  367.22  5140.6  370.52  5172.2  375.18  5268.9  372.98
  5383.8   376.9  5546.4  386.84  5675.1  397.84  5823.3  411.56  5941.7  421.46
#Mann= 13 ,-1 , 0
    2993     .07       0  3218.8     .05       0  3317.2    .045       0
  4180.8     .05       0  4272.4    .045       0  4298.7     .05       0
    4791      .1       0  4992.6     .05       0  5056.6      .1       0
  5268.9     .07       0  5383.8     .05       0  5675.1     .07       0
  5823.3     .12       0
Bank Sta=4992.6,5056.6
XS Rating Curve= 0 ,0
Exp/Cntr=0.3,0.1

Type RM Length L Ch R = 1 ,122191  ,692,692,692
BEGIN DESCRIPTION:
SANDY FORK 84.0
END DESCRIPTION:
XS GIS Cut Line= 3
      2456974.96     13799875.02        2458975.       13799075.
      2459674.97     13798675.02
#Sta/Elev= 30
  2845.6  398.47  2962.8  395.54  3048.7  391.25    3284  378.27  3351.9  376.28
  3447.4   376.6  3662.8  373.95  3761.1  370.53    3854  369.29  4069.4  367.47
  4417.3  367.86  4784.3  365.81  4834.4   366.6  4931.1  366.42  4960.7  362.02
    4965  355.74  4966.5  354.74  5027.6  354.74  5029.1  355.74  5029.2  365.52
    5035  364.39  5215.1  371.98  5373.3  376.87  5497.1  385.57  5648.9  399.09
  5725.3  407.42  5776.4     416  5784.9  418.84    5798  420.78  5805.9  423.45
#Mann= 10 ,-1 , 0
  2845.6     .07       0  3048.7     .05       0    3284    .045       0
  4417.3     .05       0  4834.4      .1       0    4965     .05       0
  5029.1      .1       0  5215.1     .05       0  5648.9     .12       0
  5784.9     .05       0
Bank Sta=4965,5029.1
XS Rating Curve= 0 ,0
Exp/Cntr=0.3,0.1

Type RM Length L Ch R = 1 ,121499  ,1442,1442,1442
BEGIN DESCRIPTION:
SANDY FORK 83.0
END DESCRIPTION:
XS GIS Cut Line= 3
      2458025.01     13801074.99        2459225.       13799675.
      2459625.02     13799274.98
#Sta/Elev= 30
  3156.7     405  3276.9  407.77  3310.3  406.78  3348.2  400.14    3422  390.79
  3489.8   382.5  3563.4  378.96  3571.6  378.47  3696.1  372.01  3779.4  369.67
    3908   367.5    4263  366.26  4276.7  367.34  4341.5  364.98  4610.4  367.12
  4702.6  364.31  4828.6  364.41  4831.1  364.41  4909.6  365.32  4958.3   364.2
  4961.4  356.15  4962.9  355.15  5025.6  356.15  5028.9  361.61    5043  365.54
  5099.6  366.02    5241  379.31  5310.7  383.42  5449.1  390.42  5566.3  396.41
#Mann= 13 ,-1 , 0
  3156.7     .07       0  3310.3     .12       0    3422     .05       0
  3563.4     .07       0  3571.6     .05       0  3779.4    .045       0
  4828.6     .05       0  4831.1     .07       0  4909.6      .1       0
  4961.4     .05       0  5025.6      .1       0  5310.7     .07       0
  5449.1     .05       0
Bank Sta=4961.4,5025.6
XS Rating Curve= 0 ,0
Exp/Cntr=0.3,0.1

Type RM Length L Ch R = 1 ,120057  ,1082,1082,1082
BEGIN DESCRIPTION:
SANDY FORK 82.0
END DESCRIPTION:
XS GIS Cut Line= 3
        2459625.     13801375.02        2459725.       13800875.
        2459725.     13798875.02
#Sta/Elev= 30
  4490.6   391.8  4772.4  379.48    4873  374.49  4949.5  368.73  4959.7  366.39
  4965.8  354.19  4967.3  353.19  5028.6  353.19  5030.1  354.19  5030.5  363.18
  5037.6  363.43  5070.5  362.43  5110.5  364.03  5120.5  365.46  5170.5   362.9
  5210.5   364.2  5285.1  363.97  5340.5  363.44  5390.5  364.91  5490.5  362.23
  5680.5  368.82    5841  365.78  6052.5  366.83  6150.9  367.16  6320.5  376.74
  6540.5  394.86  6810.5  405.76  6928.1     412  6938.2  412.85  7000.5  416.09
#Mann= 11 ,-1 , 0
  4490.6     .12       0  4772.4     .05       0  4965.8     .05       0
  5030.1     .05       0  5037.6      .1       0  5285.1     .05       0
    5841     .07       0  6052.5      .1       0  6150.9     .05       0
  6928.1     .07       0  6938.2     .12       0
Bank Sta=4965.8,5030.1
XS Rating Curve= 0 ,0
Exp/Cntr=0.3,0.1

Type RM Length L Ch R = 1 ,118975  ,728,728,728
BEGIN DESCRIPTION:
E20653
END DESCRIPTION:
XS GIS Cut Line= 3
      2459995.85     13801658.46      2460488.59      13800518.1
      2460404.12     13799011.73
#Sta/Elev= 30
  3422.1  394.89  3607.3  386.92  3706.8  384.94  3782.7  379.73  3842.2  377.79
  4123.1  370.74  4253.8  370.05  4390.3  365.41  4513.2  363.82  4536.7  362.33
  4558.8   363.6  4622.8  363.07  4847.7  361.32  4947.9  362.34  4967.6  352.94
  4969.1  351.94  5030.4  351.94  5031.9  352.94    5038  361.69  5058.1  362.81
  5119.7  363.07  5188.3  365.03  5353.6  365.32    5639  368.59  5809.3  372.53
  5932.2  379.13  5969.5  383.53  6030.9  388.33  6119.7  394.83  6173.1  400.21
#Mann= 8 ,-1 , 0
  3422.1     .12       0  3842.2    .045       0  4622.8      .1       0
  4967.6     .05       0  5031.9      .1       0  5119.7     .05       0
  5932.2     .07       0  6030.9     .12       0
Bank Sta=4967.6,5031.9
XS Rating Curve= 0 ,0
Exp/Cntr=0.3,0.1

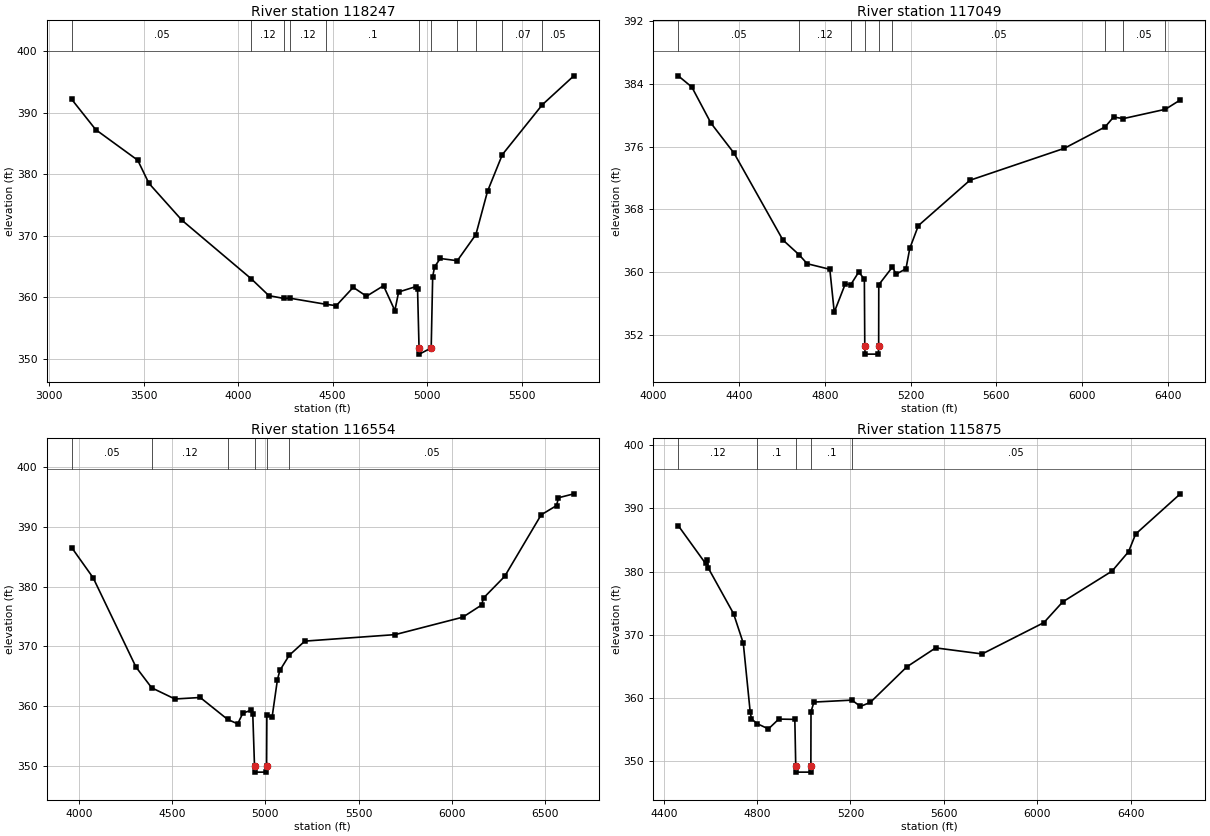
Type RM Length L Ch R = 1 ,118247  ,1198,1198,1198
BEGIN DESCRIPTION:
SANDY FORK 81.0
END DESCRIPTION:
XS GIS Cut Line= 3
      2461319.19     13801672.51      2461044.67     13800504.03
      2461100.92     13799048.51
#Sta/Elev= 30
  3119.8  392.19  3246.5  387.28  3468.8  382.31  3528.1  378.55  3702.8  372.55
  4069.5  363.03  4162.8  360.29  4242.6  359.83    4273  359.88  4463.2  358.89
  4519.3  358.66  4609.3  361.64  4679.4  360.19  4769.5   361.9  4829.5  357.86
  4849.5  360.88  4939.6  361.75  4949.6   361.4  4957.5  351.78    4959  350.78
  5021.8  351.78  5029.7  363.38  5039.7  364.97  5069.7  366.33    5160  365.97
  5258.4  370.23  5319.9  377.26  5398.3  383.22  5609.9  391.33  5776.7  396.03
#Mann= 11 ,-1 , 0
  3119.8     .05       0  4069.5     .12       0  4242.6     .07       0
    4273     .12       0  4463.2      .1       0  4957.5     .05       0
  5021.8      .1       0    5160     .05       0  5258.4     .12       0
  5398.3     .07       0  5609.9     .05       0
Bank Sta=4957.5,5021.8
XS Rating Curve= 0 ,0
Exp/Cntr=0.3,0.1

Type RM Length L Ch R = 1 ,117049  ,495,495,495
BEGIN DESCRIPTION:
E20652
END DESCRIPTION:
XS GIS Cut Line= 3
      2461509.24     13801426.15       2461790.8     13800405.48
        2461826.     13799124.36
#Sta/Elev= 30
    4117     385  4180.4  383.57  4269.5  378.98  4377.5  375.14  4604.6  364.11
  4680.4  362.22  4718.1  361.08  4823.6  360.37  4844.3  354.91  4896.2  358.55
    4920  358.36  4958.4  360.02  4984.6  359.12  4986.6  350.57  4988.1  349.57
  5049.8  349.57  5051.3  350.57  5051.8   358.4  5115.6  360.66  5132.4  359.75
  5178.5  360.43  5196.3  363.03  5236.3  365.93  5476.4   371.7  5916.6  375.77
  6106.6  378.49  6146.6  379.76    6191  379.55  6387.8  380.74  6457.4  381.93
#Mann= 9 ,-1 , 0
    4117     .05       0  4680.4     .12       0    4920      .1       0
  4986.6     .05       0  5051.3      .1       0  5115.6     .05       0
  6106.6     .07       0    6191     .05       0  6387.8      .1       0
Bank Sta=4986.6,5051.3
XS Rating Curve= 0 ,0
Exp/Cntr=0.3,0.1

Type RM Length L Ch R = 1 ,116554  ,679,679,679
BEGIN DESCRIPTION:
SANDY FORK 80.0
END DESCRIPTION:
XS GIS Cut Line= 3
        2461925.     13801524.99        2462225.       13800525.
      2462625.01     13798924.96
#Sta/Elev= 30
  3961.6  386.53  4076.4  381.48  4306.1  366.52  4390.4  363.04  4514.9  361.17
  4650.7  361.42  4797.4  357.75  4851.6     357  4879.5  358.81    4923  359.26
  4932.5  358.71  4941.9  349.91  4943.4  348.91  5005.2  348.91  5006.7  349.91
  5008.2  358.46  5036.5  358.19  5064.9  364.42  5077.8  365.95  5127.7  368.48
  5211.8  370.87  5696.2  371.96  6059.6  374.89  6160.1  376.92  6170.4   378.1
  6283.8  381.72  6479.6  392.04  6562.1  393.59  6572.4   394.9  6654.9  395.56
#Mann= 6 ,-1 , 0
  3961.6     .05       0  4390.4     .12       0  4797.4      .1       0
  4941.9     .05       0  5006.7      .1       0  5127.7     .05       0
Bank Sta=4941.9,5006.7
XS Rating Curve= 0 ,0
Exp/Cntr=0.3,0.1

Type RM Length L Ch R = 1 ,115875  ,707,707,707
BEGIN DESCRIPTION:
SANDY FORK 79.0
END DESCRIPTION:
XS GIS Cut Line= 3
      2463025.01     13801225.02        2462825.       13800725.
        2463025.     13799124.99
#Sta/Elev= 30
  4462.1  387.29  4579.2  381.29  4584.6  381.87  4591.4  380.53  4699.1  373.35
  4740.8  368.67  4770.4  357.78  4775.8   356.7  4799.3  355.95  4848.5   355.1
  4892.9  356.66  4961.6  356.61  4965.5  349.26    4967  348.26  5028.8  348.26
  5030.3  349.26  5030.9  357.82  5043.5  359.35  5206.3  359.66  5242.5  358.66
  5285.3  359.31  5441.5  364.93    5565  367.93    5764  366.97  6028.6  371.93
  6109.2  375.21  6320.8  380.09  6391.4  383.16  6421.6  385.95  6613.1  392.32
#Mann= 5 ,-1 , 0
  4462.1     .12       0  4799.3      .1       0  4965.5     .05       0
  5030.3      .1       0  5206.3     .05       0
Bank Sta=4965.5,5030.3
XS Rating Curve= 0 ,0
Exp/Cntr=0.3,0.1