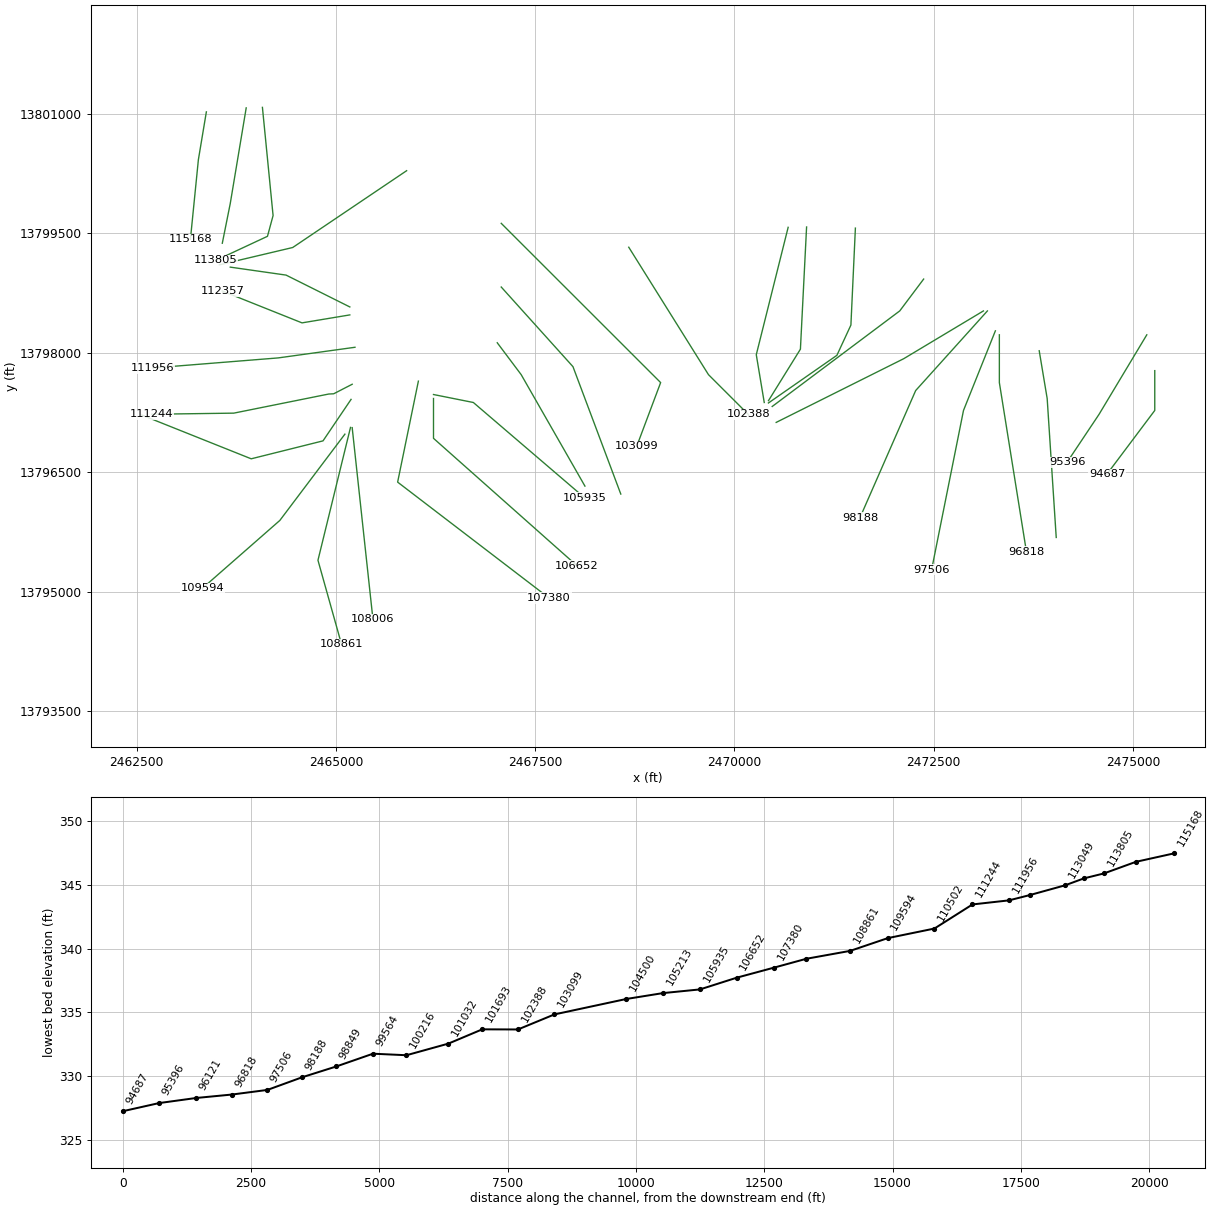
HEC-RAS study SANDY FORK.prj: SANDY FORK Base Level Engineering

--- SANDY FORK.g01 (geometry) --- (continued)

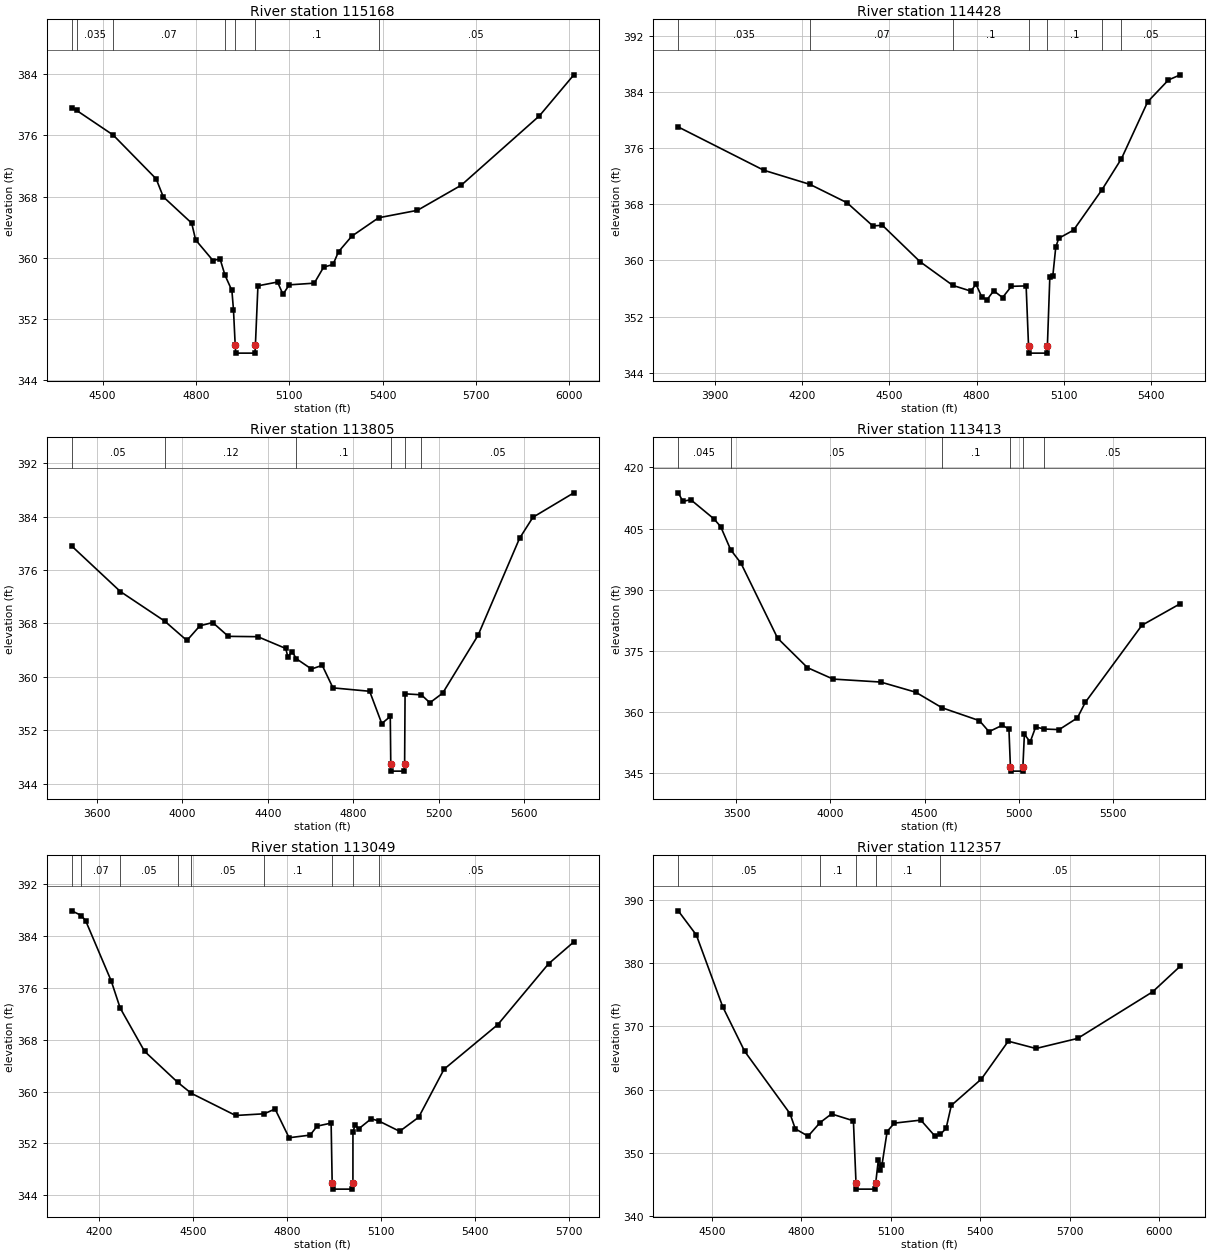
Type RM Length L Ch R = 1 ,115168  ,740,740,740
BEGIN DESCRIPTION:
SANDY FORK 78.0
END DESCRIPTION:
XS GIS Cut Line= 3
      2463375.01     13801025.04        2463275.       13800425.
        2463175.     13799425.01
#Sta/Elev= 30
    4401   379.6  4416.7  379.28  4534.3  376.05  4672.2  370.31    4695  367.96
  4786.3  364.51    4799  362.31  4854.7  359.61  4877.5  359.82  4893.5  357.67
  4915.5  355.68  4920.6  353.16  4926.2  348.47  4927.7  347.47  4989.5  347.47
    4991  348.47  4999.2  356.29  5062.1  356.79  5079.7  355.18  5099.8  356.42
  5180.2  356.64  5210.3  358.74  5240.5  359.09  5258.1  360.76  5300.8   362.8
  5386.8  365.21  5511.8  366.19  5652.5  369.48  5903.8  378.58  6014.3  383.95
#Mann= 7 ,-1 , 0
    4401     .12       0  4416.7    .035       0  4534.3     .07       0
  4893.5      .1       0  4926.2     .05       0    4991      .1       0
  5386.8     .05       0
Bank Sta=4926.2,4991
XS Rating Curve= 0 ,0
Exp/Cntr=0.3,0.1

Type RM Length L Ch R = 1 ,114428  ,623,623,623
BEGIN DESCRIPTION:
SANDY FORK 77.0
END DESCRIPTION:
XS GIS Cut Line= 3
      2463875.01     13801075.04        2463675.       13799875.
        2463575.       13799375.
#Sta/Elev= 30
  3774.1  379.01  4068.1  372.85  4227.2  370.83  4354.5  368.22  4443.2  364.92
  4476.2  365.01  4605.5  359.83  4718.4  356.45  4780.3  355.64  4798.1  356.62
  4818.4  354.76  4836.1  354.42  4858.9  355.69  4889.3  354.72  4919.7  356.32
  4970.4  356.38  4978.7  347.81  4980.2  346.81    5042  346.81  5043.5  347.81
  5051.9  357.63  5062.1  357.77  5072.3  361.89  5082.5  363.16  5133.5  364.32
  5231.4  370.08  5298.3   374.5  5388.4  382.59  5459.8   385.7  5500.6  386.43
#Mann= 7 ,-1 , 0
  3774.1    .035       0  4227.2     .07       0  4718.4      .1       0
  4978.7     .05       0  5043.5      .1       0  5231.4     .07       0
  5298.3     .05       0
Bank Sta=4978.7,5043.5
XS Rating Curve= 0 ,0
Exp/Cntr=0.3,0.1

Type RM Length L Ch R = 1 ,113805  ,392,392,392
BEGIN DESCRIPTION:
E20650
END DESCRIPTION:
XS GIS Cut Line= 4
      2464078.46     13801081.22       2464212.2      13799722.7
      2464141.81     13799462.26      2463494.68     13799159.79
#Sta/Elev= 30
    3482  379.58  3709.3  372.78  3916.3  368.36  4020.8  365.45  4081.1  367.64
  4141.4  368.14  4214.5  366.07  4352.4  366.02    4483  364.26  4493.1     363
  4513.2   363.8  4532.4  362.73  4603.6  361.18  4653.9  361.73  4704.1  358.36
  4875.8  357.85  4932.5  353.02  4972.3  354.08  4974.6   346.9  4976.1   345.9
  5037.9   345.9  5039.4   346.9  5041.5  357.47  5117.8  357.32  5157.5  356.13
  5217.4  357.57  5382.9  366.22    5577  380.73  5639.7  383.89  5831.2  387.55
#Mann= 6 ,-1 , 0
    3482     .05       0  3916.3     .12       0  4532.4      .1       0
  4974.6     .05       0  5039.4      .1       0  5117.8     .05       0
Bank Sta=4974.6,5039.4
XS Rating Curve= 0 ,0
Exp/Cntr=0.3,0.1

Type RM Length L Ch R = 1 ,113413  ,364,364,364
BEGIN DESCRIPTION:
E20651
END DESCRIPTION:
XS GIS Cut Line= 3
      2465887.51     13800285.85      2464458.57     13799321.48
       2463538.2     13799103.69
#Sta/Elev= 30
  3190.5  413.78  3215.2  411.69  3257.2  412.09  3380.1   407.4  3416.1   405.5
    3469  399.84    3524  396.52  3718.8  378.13  3877.7  370.89  4013.9  368.09
  4267.2  367.36  4453.3  364.87  4593.3  361.05    4792  357.89  4842.9  355.19
  4913.6  356.76  4948.9  355.83  4956.9  346.51  4958.4  345.51  5021.6  345.51
  5023.1  346.51  5031.1  354.55  5061.9  352.67  5091.1  356.34  5137.5  355.83
  5216.1   355.7  5312.7  358.56    5355  362.38    5656  381.29  5860.2  386.59
#Mann= 6 ,-1 , 0
  3190.5    .045       0    3469     .05       0  4593.3      .1       0
  4956.9     .05       0  5023.1      .1       0  5137.5     .05       0
Bank Sta=4956.9,5023.1
XS Rating Curve= 0 ,0
Exp/Cntr=0.3,0.1

Type RM Length L Ch R = 1 ,113049  ,692,692,692
BEGIN DESCRIPTION:
SANDY FORK 76.0
END DESCRIPTION:
XS GIS Cut Line= 3
      2465174.99       13798575.        2464375.       13798975.
      2463675.03       13799075.
#Sta/Elev= 30
  4112.7  387.82  4143.2   387.1  4157.4  386.25  4238.5  377.03    4267  372.86
  4344.7   366.2  4450.7  361.41  4493.8  359.73  4635.4  356.31  4726.4  356.57
  4761.2  357.31  4805.9  352.88    4873  353.29  4895.3  354.67    4940  355.14
  4943.3  345.97  4944.8  344.97    5008  344.97  5009.5  345.97  5009.6  353.83
  5017.2  354.91  5027.3  354.23  5067.7   355.8  5091.3  355.48  5158.6  353.87
  5219.3  356.04  5300.1  363.43  5471.8  370.31  5633.4  379.66  5714.2  383.04
#Mann= 9 ,-1 , 0
  4112.7     .05       0  4143.2     .07       0    4267     .05       0
  4450.7     .07       0  4493.8     .05       0  4726.4      .1       0
  4943.3     .05       0  5009.5      .1       0  5091.3     .05       0
Bank Sta=4943.3,5009.5
XS Rating Curve= 0 ,0
Exp/Cntr=0.3,0.1

Type RM Length L Ch R = 1 ,112357  ,401,401,401
BEGIN DESCRIPTION:
SANDY FORK 75.0
END DESCRIPTION:
XS GIS Cut Line= 3
      2465175.01       13798475.        2464575.       13798375.
      2463575.02     13798774.99
#Sta/Elev= 30
  4386.3  388.35  4447.1  384.51  4535.8  373.11  4609.3  366.06  4761.4  356.18
  4779.2  353.77  4822.2   352.6  4862.5  354.76  4900.8  356.13  4974.3  355.04
    4983   345.2  4984.5   344.2  5047.7   344.2  5049.2   345.2  5057.9  348.79
  5063.2  347.29    5070  347.97  5087.5  353.34  5111.7  354.67  5200.6  355.15
    5249  352.56  5265.9  352.88  5285.4  353.84  5302.9  357.48  5403.9  361.67
  5494.1  367.67    5587  366.51    5727  368.11  5978.7   375.5  6071.6  379.58
#Mann= 5 ,-1 , 0
  4386.3     .05       0  4862.5      .1       0    4983     .05       0
  5049.2      .1       0  5265.9     .05       0
Bank Sta=4983,5049.2
XS Rating Curve= 0 ,0
Exp/Cntr=0.3,0.1

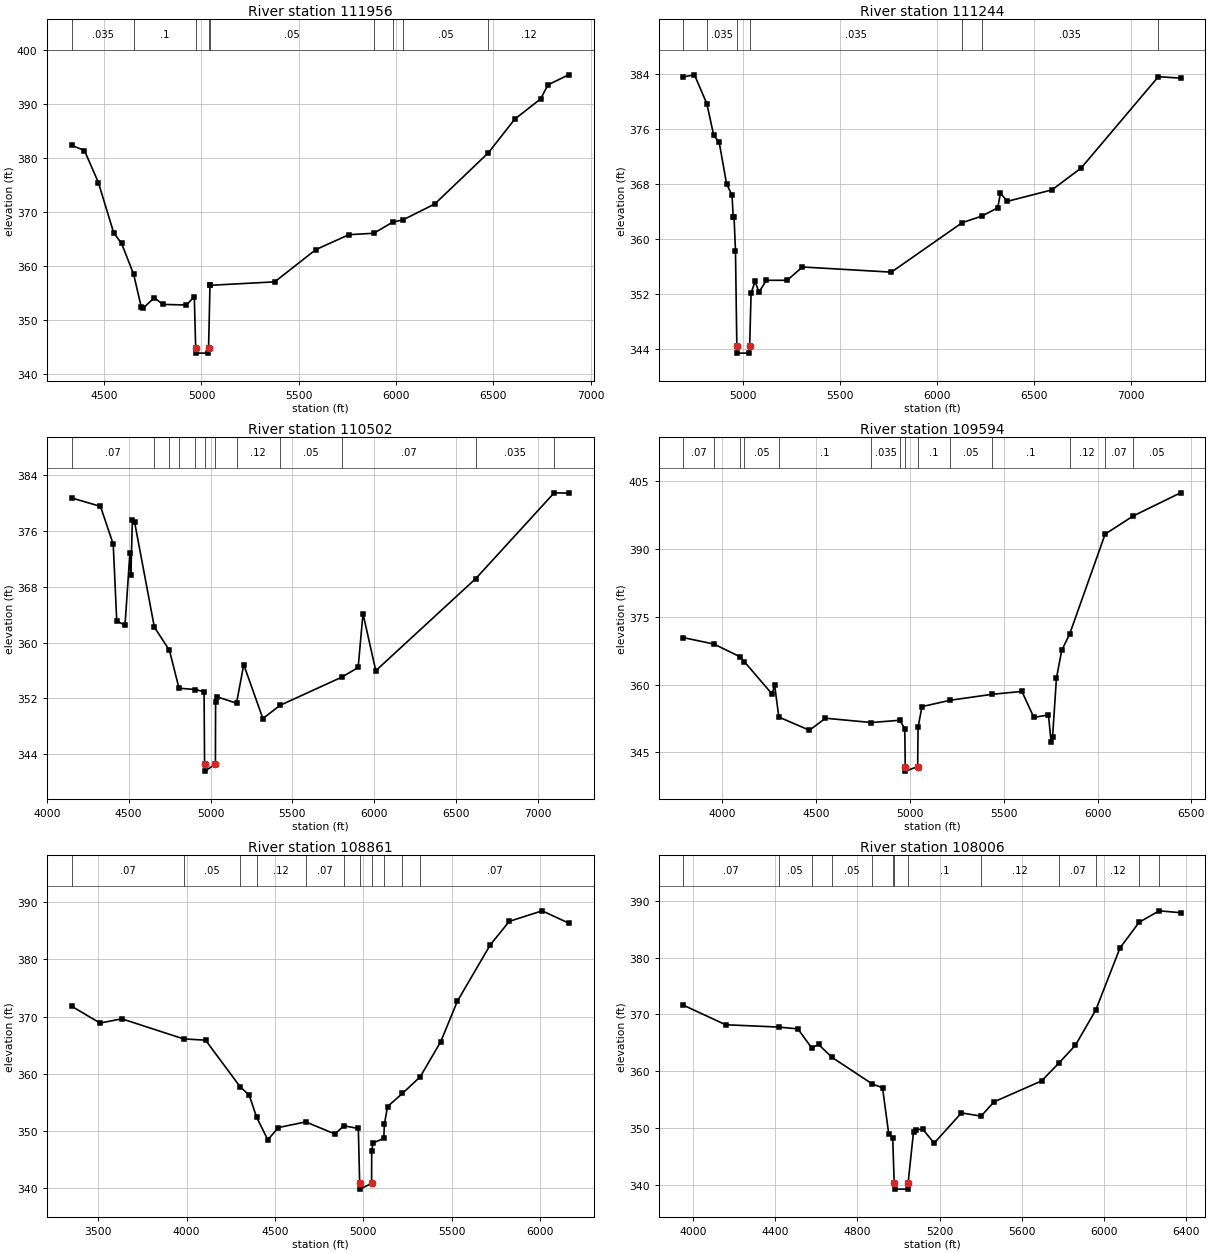
Type RM Length L Ch R = 1 ,111956  ,712,712,712
BEGIN DESCRIPTION:
E20649
END DESCRIPTION:
XS GIS Cut Line= 3
      2465239.88     13798068.55      2464275.55     13797934.81
      2462699.39     13797808.15
#Sta/Elev= 30
  4332.2  382.35  4398.6  381.37  4470.3  375.43  4549.1  366.09  4589.5  364.14
  4651.6   358.4  4690.6  352.32  4700.6  352.13  4757.2  354.07  4801.5  352.83
  4922.7  352.71  4963.1  354.29  4970.3  344.79  4971.8  343.79    5035  343.79
  5036.5  344.79  5043.8  356.35  5044.5  356.37  5376.5  357.01  5587.2  362.98
  5757.8  365.76  5885.7  366.02  5981.8  368.07  6036.4  368.52  6199.2  371.46
  6474.7  380.96  6609.9  387.18  6742.5  390.93  6781.1  393.56    6887  395.41
#Mann= 9 ,-1 , 0
  4332.2    .035       0  4651.6      .1       0  4970.3     .05       0
  5036.5      .1       0  5044.5     .05       0  5885.7    .035       0
  5981.8     .12       0  6036.4     .05       0  6474.7     .12       0
Bank Sta=4970.3,5036.5
XS Rating Curve= 0 ,0
Exp/Cntr=0.3,0.1

Type RM Length L Ch R = 1 ,111244  ,742,742,742
BEGIN DESCRIPTION:
E20648
END DESCRIPTION:
XS GIS Cut Line= 5
      2465204.71     13797603.98      2464972.41     13797484.31
      2464909.93     13797481.25      2463718.98      13797241.3
      2462691.22     13797227.42
#Sta/Elev= 30
  4691.2  383.52  4748.2  383.82  4812.4   379.6  4847.7  375.03  4875.5  374.07
  4914.2  367.98    4942  366.39  4948.2   363.2  4952.5   363.2  4959.9  358.31
  4966.9  344.47  4968.4  343.47  5031.6  343.47  5033.1  344.47  5040.5  352.17
  5060.9  353.87  5081.3  352.32  5119.8  354.03  5226.6  354.03  5305.7  355.96
  5764.8  355.21  6130.6  362.39  6230.5  363.32  6313.9  364.54  6327.7  366.64
  6363.9  365.48    6594  367.14    6744  370.29  7143.2  383.55  7257.8  383.34
#Mann= 7 ,-1 , 0
  4691.2     .07       0  4812.4    .035       0  4966.9    .035       0
  5033.1    .035       0  6130.6     .07       0  6230.5    .035       0
  7143.2     .05       0
Bank Sta=4966.9,5033.1
XS Rating Curve= 0 ,0
Exp/Cntr=0.3,0.1

Type RM Length L Ch R = 1 ,110502  ,908,908,908
BEGIN DESCRIPTION:
E20647
END DESCRIPTION:
XS GIS Cut Line= 4
       2465190.6     13797413.89      2464838.67     13796893.04
      2463937.68     13796667.79      2462565.13     13797216.81
#Sta/Elev= 30
  4151.3  380.73    4328  379.52  4405.9   374.1  4427.5  363.08  4477.9   362.5
  4507.8  372.85  4513.8  369.66  4522.8  377.53  4536.2  377.29  4657.2  362.21
  4749.3  358.89  4807.5  353.46  4908.3  353.27  4960.7  352.95  4963.7  342.58
  4965.2  341.58  5029.9  342.58  5031.1  351.42    5038  352.25  5158.8  351.31
  5202.9  356.85  5319.7  349.11    5424     351  5801.9  355.05  5901.5  356.43
  5931.1  364.15  6009.2  355.97  6619.8  369.17  7098.7  381.46  7186.9  381.42
#Mann= 12 ,-1 , 0
  4151.3     .07       0  4657.2      .1       0  4749.3     .07       0
  4807.5    .035       0  4908.3      .1       0  4963.7     .05       0
  5029.9      .1       0  5158.8     .12       0    5424     .05       0
  5801.9     .07       0  6619.8    .035       0  7098.7     .05       0
Bank Sta=4963.7,5029.9
XS Rating Curve= 0 ,0
Exp/Cntr=0.3,0.1

Type RM Length L Ch R = 1 ,109594  ,733,733,733
BEGIN DESCRIPTION:
SANDY FORK 74.0
END DESCRIPTION:
XS GIS Cut Line= 3
      2465113.17     13796977.48      2464296.67     13795893.51
      2463325.27     13795041.78
#Sta/Elev= 30
  3793.4  370.38  3955.2  368.97    4097  366.11  4118.7  365.02    4265  357.93
  4279.6  359.79  4301.8   352.8  4464.9  349.88  4550.3  352.54  4794.8  351.59
  4946.4  352.09  4972.9  350.19  4975.2  341.83  4976.7  340.83  5041.5  341.83
  5043.7  350.55  5064.5  355.11  5215.6  356.53  5437.4  357.83    5597  358.48
  5660.5  352.72  5738.4  353.28  5752.6   347.3  5760.2  348.34  5781.1  361.44
  5809.5   367.6  5850.9  371.11  6040.5   393.3  6190.3  397.32  6442.4  402.44
#Mann= 14 ,-1 , 0
  3793.4     .07       0  3955.2      .1       0    4097     .07       0
  4118.7     .05       0  4301.8      .1       0  4794.8    .035       0
  4946.4      .1       0  4975.2     .05       0  5041.5      .1       0
  5215.6     .05       0  5437.4      .1       0  5850.9     .12       0
  6040.5     .07       0  6190.3     .05       0
Bank Sta=4975.2,5041.5
XS Rating Curve= 0 ,0
Exp/Cntr=0.3,0.1

Type RM Length L Ch R = 1 ,108861  ,855,855,855
BEGIN DESCRIPTION:
E20646
END DESCRIPTION:
XS GIS Cut Line= 3
      2465183.57     13797061.94      2464775.32     13795393.74
      2465070.96     13794337.88
#Sta/Elev= 30
  3348.9  371.81  3510.5  368.86    3634   369.6  3983.2  366.09  4107.6  365.87
  4304.3  357.68  4354.7  356.26  4396.9  352.37  4460.2  348.45  4519.4  350.59
  4674.5  351.58    4840  349.47  4890.3   350.9  4972.4  350.43  4979.8  340.83
  4981.3  339.83  5047.3  340.83  5048.1  346.47  5054.7   347.9  5116.3  348.69
  5120.2  351.26  5137.7  354.27  5221.6  356.55    5323  359.48  5438.9  365.61
  5533.1  372.69  5719.3  382.54  5826.9  386.64    6013  388.48  6162.8  386.33
#Mann= 11 ,-1 , 0
  3348.9     .07       0  3983.2     .05       0  4304.3     .07       0
  4396.9     .12       0  4674.5     .07       0  4890.3      .1       0
  4979.8     .05       0  5047.3      .1       0  5120.2     .07       0
  5221.6     .12       0    5323     .07       0
Bank Sta=4979.8,5047.3
XS Rating Curve= 0 ,0
Exp/Cntr=0.3,0.1

Type RM Length L Ch R = 1 ,108006  ,626,626,626
BEGIN DESCRIPTION:
E20645
END DESCRIPTION:
XS GIS Cut Line= 2
      2465204.69      13797059.2      2465465.14     13794651.85
#Sta/Elev= 30
  3952.5  371.61  4157.9  368.17  4417.1  367.76  4509.9  367.44  4577.2  364.09
  4610.5   364.7  4675.8  362.43  4873.2  357.72  4922.3  357.08  4952.5  348.93
  4971.9  348.21  4979.1  340.21  4980.6  339.21  5045.1  339.21  5046.6  340.21
  5073.2  349.29  5083.3  349.68    5118  349.77  5173.8  347.31  5306.5  352.64
  5402.4  352.07  5465.5  354.59  5696.8  358.27  5781.9  361.44    5862  364.57
  5961.3  370.79    6079  381.71  6172.3  386.22  6269.4  388.24  6373.9  387.91
#Mann= 13 ,-1 , 0
  3952.5     .07       0  4417.1     .05       0  4577.2     .07       0
  4675.8     .05       0  4873.2     .07       0  4971.9      .1       0
  4979.1     .05       0  5046.6      .1       0  5402.4     .12       0
  5781.9     .07       0  5961.3     .12       0  6172.3     .07       0
  6269.4     .05       0
Bank Sta=4979.1,5046.6
XS Rating Curve= 0 ,0
Exp/Cntr=0.3,0.1

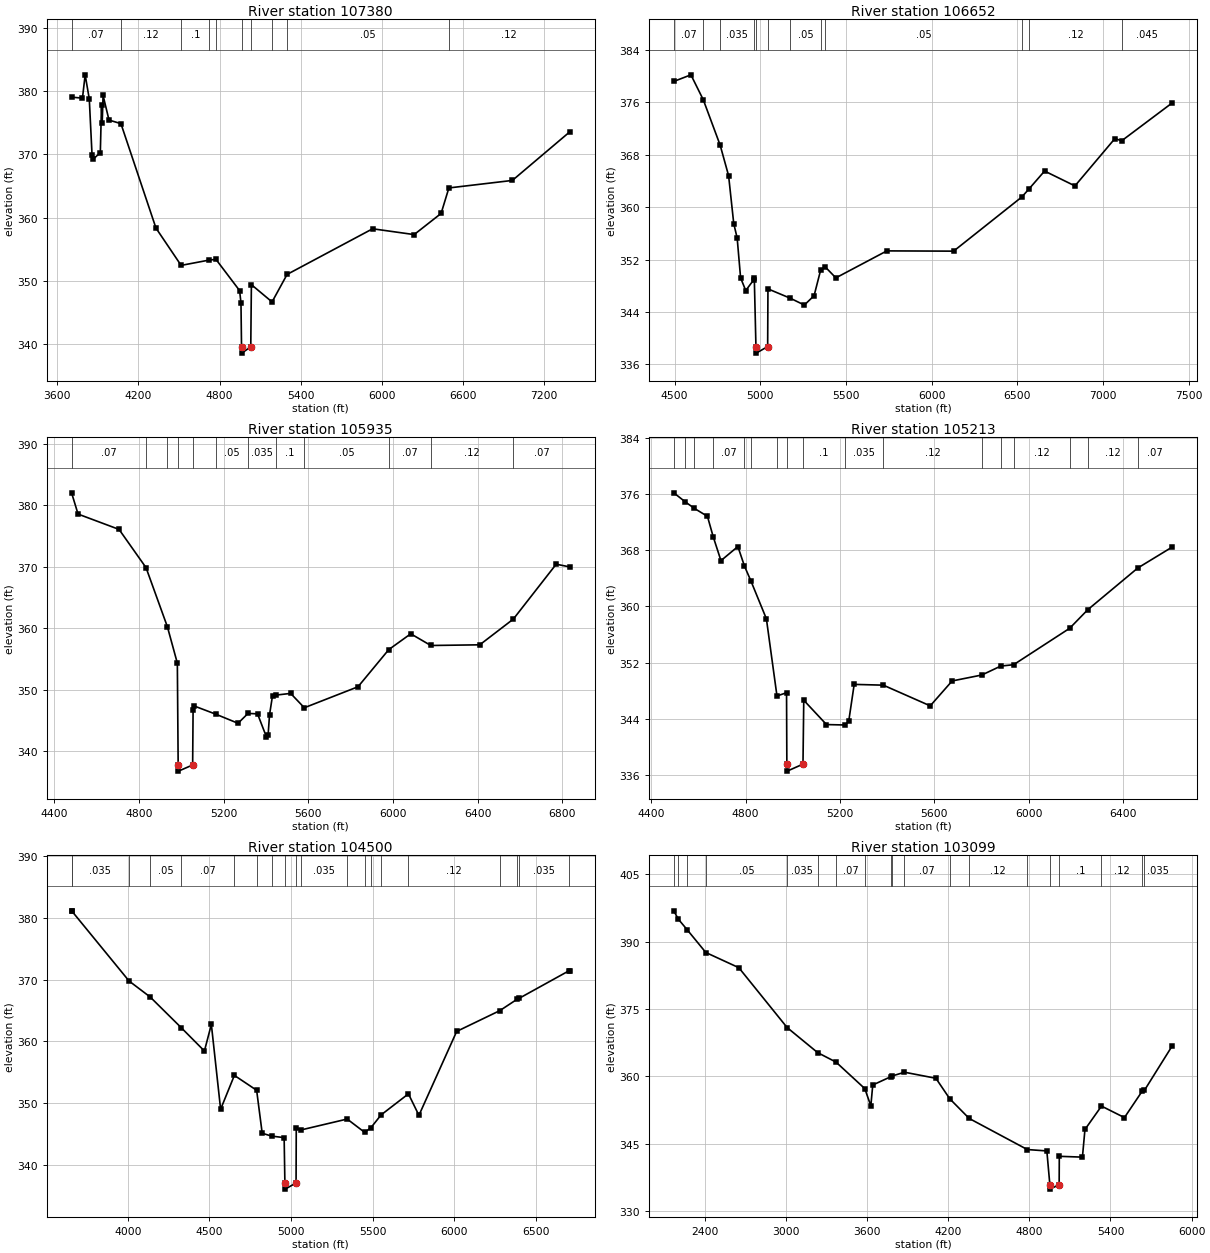
Type RM Length L Ch R = 1 ,107380  ,728,728,728
BEGIN DESCRIPTION:
SANDY FORK 71.0
END DESCRIPTION:
XS GIS Cut Line= 3
       2466035.3     13797643.41        2465775.       13796375.
      2467674.91     13794919.67
#Sta/Elev= 30
  3704.9  379.07  3785.5  378.92  3805.4  382.61    3836  378.79  3856.4  369.92
  3866.6  369.28  3917.7  370.29  3926.5  377.83  3931.6  374.98  3938.1  379.34
    3982  375.44  4070.2  374.88  4329.6  358.33  4515.9  352.42  4725.6  353.27
  4773.9  353.37  4948.7  348.43  4958.9  346.48    4963  339.52  4964.5  338.52
  5031.4  339.52    5036  349.37    5189  346.63  5300.3  350.99  5933.5  358.22
  6240.9   357.3  6440.4  360.65    6498  364.69    6968  365.88    7393  373.58
#Mann= 10 ,-1 , 0
  3704.9     .07       0  4070.2     .12       0  4515.9      .1       0
  4725.6     .12       0  4773.9      .1       0    4963     .05       0
  5031.4      .1       0    5189     .12       0  5300.3     .05       0
    6498     .12       0
Bank Sta=4963,5031.4
XS Rating Curve= 0 ,0
Exp/Cntr=0.3,0.1

Type RM Length L Ch R = 1 ,106652  ,717,717,717
BEGIN DESCRIPTION:
SANDY FORK 70.0
END DESCRIPTION:
XS GIS Cut Line= 3
        2466225.     13797424.98        2466225.       13796925.
        2468025.       13795325.
#Sta/Elev= 30
  4495.1  379.21  4595.1  380.22  4667.5   376.4  4765.9  369.47  4815.1  364.82
  4845.1  357.51  4865.1   355.3  4885.1  349.22  4915.1  347.29  4962.7  348.95
  4965.1  349.14  4974.7  338.73  4976.2  337.73  5043.1  338.73  5044.8  347.54
  5176.2   346.1  5257.2  345.07  5314.1   346.5  5352.2  350.39  5378.5  350.91
  5441.2  349.22  5738.9  353.34  6128.6   353.3  6526.8  361.57  6569.1  362.81
  6659.6  365.53  6836.9  363.26  7070.2  370.49  7109.8  370.15  7403.4  375.91
#Mann= 12 ,-1 , 0
  4495.1     .07       0  4667.5     .12       0  4765.9    .035       0
  4962.7      .1       0  4974.7     .05       0  5043.1      .1       0
  5176.2     .05       0  5352.2    .035       0  5378.5     .05       0
  6526.8     .07       0  6569.1     .12       0  7109.8    .045       0
Bank Sta=4974.7,5043.1
XS Rating Curve= 0 ,0
Exp/Cntr=0.3,0.1

Type RM Length L Ch R = 1 ,105935  ,722,722,722
BEGIN DESCRIPTION:
SANDY FORK 69.0
END DESCRIPTION:
XS GIS Cut Line= 3
      2466225.04     13797474.99        2466725.       13797375.
      2468125.03     13796174.98
#Sta/Elev= 30
  4482.1     382  4512.7  378.55  4706.4  376.06  4833.9  369.85  4934.9  360.24
  4981.8  354.34  4985.7  337.81  4987.2  336.81  5054.1  337.81  5056.2  346.77
  5062.8  347.37  5163.9  346.05  5268.5  344.58  5315.7  346.18  5360.7  346.11
    5403  342.34  5410.7   342.7  5417.3  345.94  5431.5  349.08  5448.7  349.16
  5517.1  349.43  5581.7   347.1  5835.4  350.51  5980.6  356.54  6084.6  359.11
  6179.5  357.21  6410.6  357.32  6569.3   361.5  6771.7  370.41  6835.9  369.97
#Mann= 12 ,-1 , 0
  4482.1     .07       0  4833.9     .12       0  4934.9      .1       0
  4985.7     .05       0  5054.1      .1       0  5163.9     .05       0
  5315.7    .035       0  5448.7      .1       0  5581.7     .05       0
  5980.6     .07       0  6179.5     .12       0  6569.3     .07       0
Bank Sta=4985.7,5054.1
XS Rating Curve= 0 ,0
Exp/Cntr=0.3,0.1

Type RM Length L Ch R = 1 ,105213  ,713,713,713
BEGIN DESCRIPTION:
SANDY FORK 68.0
END DESCRIPTION:
XS GIS Cut Line= 3
      2467025.03     13798124.96        2467325.       13797725.
        2468125.     13796325.01
#Sta/Elev= 30
  4495.7  376.21  4544.8  374.91  4583.5  373.98  4638.4  372.86  4662.7  369.96
  4695.7  366.54  4767.5  368.55  4795.3  365.77  4822.1  363.69  4888.4  358.24
  4933.2  347.24  4973.8   347.7  4975.1  337.52  4976.6  336.52  5043.5  337.52
  5046.8  346.63  5143.2  343.16  5222.6   343.1  5237.5  343.65  5260.6  348.89
  5384.2  348.78    5583  345.83  5675.9  349.38  5801.9  350.23  5881.9   351.5
  5936.7   351.7  6174.2  356.89    6251  359.54  6463.1  365.49  6608.1  368.46
#Mann= 17 ,-1 , 0
  4495.7     .05       0  4544.8     .07       0  4583.5     .05       0
  4662.7     .07       0  4795.3      .1       0  4822.1     .07       0
  4933.2      .1       0  4975.1     .05       0  5043.5      .1       0
  5222.6    .035       0  5384.2     .12       0  5801.9     .05       0
  5881.9     .07       0  5936.7     .12       0  6174.2     .07       0
    6251     .12       0  6463.1     .07       0
Bank Sta=4975.1,5043.5
XS Rating Curve= 0 ,0
Exp/Cntr=0.3,0.1

Type RM Length L Ch R = 1 ,104500  ,1401,1401,1401
BEGIN DESCRIPTION:
SANDY FORK 67.0
END DESCRIPTION:
XS GIS Cut Line= 3
      2467075.01     13798824.99        2467975.       13797825.
      2468575.02     13796224.95
#Sta/Elev= 30
  3655.2  381.13  3655.6  381.13  4007.8  369.76  4136.9  367.18  4328.4  362.18
  4469.5  358.43  4512.1  362.73  4568.9  348.99  4653.2  354.48  4789.7  352.07
  4823.8  345.11  4881.1  344.65  4958.3   344.4  4962.9  337.06  4964.4  336.06
  5031.4  337.06  5032.6  345.96  5059.5  345.63  5344.8  347.41  5452.1  345.25
  5490.3  346.01  5552.7  348.08  5720.2  351.49  5784.6  348.01    6016   361.6
  6280.7  364.97  6384.7  366.78    6401  366.99  6704.5  371.42  6709.4  371.44
#Mann= 20 ,-1 , 0
  3655.2     .05       0  3655.6    .035       0  4007.8     .07       0
  4136.9     .05       0  4328.4     .07       0  4653.2     .07       0
  4789.7     .07       0  4881.1      .1       0  4962.9     .05       0
  5031.4      .1       0  5059.5    .035       0  5344.8     .12       0
  5452.1     .07       0  5490.3    .035       0  5552.7     .07       0
  5720.2     .12       0  6280.7     .07       0  6384.7     .12       0
    6401    .035       0  6704.5     .07       0
Bank Sta=4962.9,5031.4
XS Rating Curve= 0 ,0
Exp/Cntr=0.3,0.1

Type RM Length L Ch R = 1 ,103099  ,711,711,711
BEGIN DESCRIPTION:
SANDY FORK 66.0
END DESCRIPTION:
XS GIS Cut Line= 3
      2467074.99     13799625.01        2469075.       13797625.
      2468775.01     13796825.03
#Sta/Elev= 30
  2171.8  396.86  2204.9  395.02  2272.5  392.58  2408.8  387.57  2652.6  384.19
  3009.7  370.85  3235.5  365.26  3370.8  363.16    3584  357.24  3628.4  353.39
  3642.6  358.05  3778.2  359.93    3782  360.02  3877.1   360.9  4109.3  359.55
  4212.1  354.97  4355.5   350.6  4785.2  343.67  4929.5  343.36  4951.7  335.85
  4953.2  334.85  5020.5  335.85  5021.6  342.16  5192.5  341.98  5211.2  348.14
  5333.4  353.35  5503.1  350.79  5636.4  356.77  5651.3  356.88  5854.6  366.69
#Mann= 19 ,-1 , 0
  2171.8     .07       0  2204.9     .05       0  2272.5     .07       0
  2408.8     .05       0  3009.7    .035       0  3235.5    .063       0
  3370.8     .07       0    3584      .1       0  3778.2     .07       0
    3782      .1       0  3877.1     .07       0  4212.1    .035       0
  4355.5     .12       0  4785.2      .1       0  4951.7     .05       0
  5020.5      .1       0  5333.4     .12       0  5636.4     .07       0
  5651.3    .035       0
Bank Sta=4951.7,5020.5
XS Rating Curve= 0 ,0
Exp/Cntr=0.3,0.1

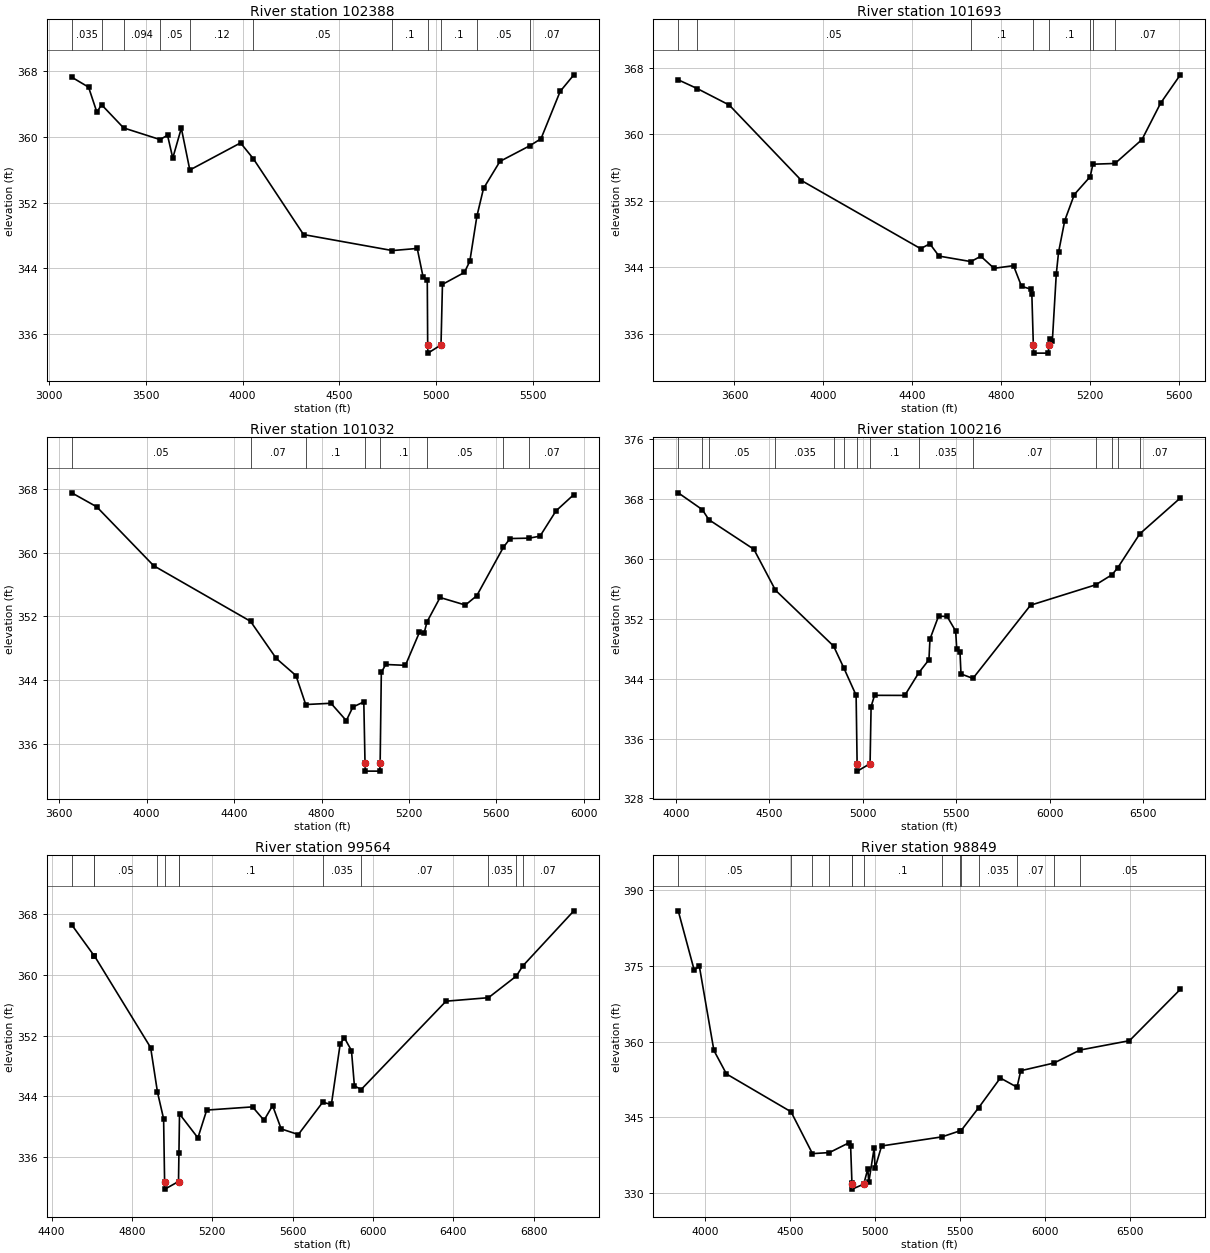
Type RM Length L Ch R = 1 ,102388  ,695,695,695
BEGIN DESCRIPTION:
SANDY FORK 65.0
END DESCRIPTION:
XS GIS Cut Line= 3
      2468675.01     13799324.99        2469675.       13797725.
      2470175.01     13797224.99
#Sta/Elev= 30
  3117.4   367.3  3204.1  366.09  3247.1  363.04  3271.2  363.95  3385.2  361.12
  3573.5   359.7  3612.1  360.23  3639.2  357.44  3683.4  361.09  3727.3  355.99
  3989.4  359.29  4055.3  357.37  4314.9  348.12  4773.9  346.17  4902.2  346.43
  4932.8  342.91  4954.1  342.57  4956.2  334.67  4957.7  333.67    5025  334.67
  5032.5  342.05  5145.6   343.5  5173.9  344.87  5210.5  350.37  5244.6  353.74
  5329.5  357.04  5483.9  358.95  5541.6   359.8  5640.6  365.57  5711.3  367.59
#Mann= 11 ,-1 , 0
  3117.4    .035       0  3271.2    .063       0  3385.2    .094       0
  3573.5     .05       0  3727.3     .12       0  4055.3     .05       0
  4773.9      .1       0  4956.2     .05       0    5025      .1       0
  5210.5     .05       0  5483.9     .07       0
Bank Sta=4956.2,5025
XS Rating Curve= 0 ,0
Exp/Cntr=0.3,0.1

Type RM Length L Ch R = 1 ,101693  ,661,661,661
BEGIN DESCRIPTION:
SANDY FORK 64.0
END DESCRIPTION:
XS GIS Cut Line= 3
      2470674.99     13799574.96        2470275.       13797975.
        2470375.     13797374.97
#Sta/Elev= 30
  3347.1  366.52  3433.2  365.46  3576.4  363.49  3901.1  354.42  4437.1  346.23
  4478.3  346.82  4519.6  345.34  4662.9  344.68  4707.7  345.32  4766.9  343.87
  4854.6  344.19  4890.6  341.71  4931.9  341.37    4937  340.81  4943.7  334.68
  4945.2  333.68  5011.4  333.68  5012.9  334.68  5016.6  335.35  5029.2  335.13
    5047  343.21  5057.1  345.79    5085  349.61  5128.1  352.74  5199.3  354.88
  5211.7  356.38    5311  356.47  5432.2  359.34  5515.9  363.71  5604.6  367.12
#Mann= 8 ,-1 , 0
  3347.1     .07       0  3433.2     .05       0  4662.9      .1       0
  4943.7     .05       0  5012.9      .1       0  5199.3     .05       0
  5211.7    .035       0    5311     .07       0
Bank Sta=4943.7,5012.9
XS Rating Curve= 0 ,0
Exp/Cntr=0.3,0.1

Type RM Length L Ch R = 1 ,101032  ,816,816,816
BEGIN DESCRIPTION:
E20644
END DESCRIPTION:
XS GIS Cut Line= 3
      2470906.25     13799579.13      2470828.82     13798044.61
      2470428.53     13797398.53
#Sta/Elev= 30
  3657.7   367.5    3772  365.74  4032.3  358.35  4475.3  351.37    4593  346.71
  4683.1  344.56  4727.8  340.92  4843.3  341.08  4913.4   338.9  4943.5  340.61
  4993.5  341.25    4999  333.56  5000.5  332.56  5066.7  332.56  5068.2  333.56
  5073.6  344.95  5093.7  345.95  5183.8  345.84  5247.8  349.98    5269  349.85
  5282.6   351.3  5342.3  354.36  5458.1  353.41  5510.1  354.58  5632.1  360.67
  5662.5  361.76    5750  361.81  5799.5  362.06  5872.8  365.24  5954.2  367.28
#Mann= 8 ,-1 , 0
  3657.7     .05       0  4475.3     .07       0  4727.8      .1       0
    4999     .05       0  5068.2      .1       0  5282.6     .05       0
  5632.1    .035       0    5750     .07       0
Bank Sta=4999,5068.2
XS Rating Curve= 0 ,0
Exp/Cntr=0.3,0.1

Type RM Length L Ch R = 1 ,100216  ,652,652,652
BEGIN DESCRIPTION:
E20643
END DESCRIPTION:
XS GIS Cut Line= 4
      2471518.64     13799565.06      2471462.33     13798347.29
      2471286.36     13797967.19      2470427.58     13797368.85
#Sta/Elev= 30
    4013  368.77  4141.6  366.53  4176.6  365.19  4417.5  361.24  4532.9  355.78
  4843.7  348.33  4899.7  345.34  4964.1  341.77  4969.5  332.65    4971  331.65
  5038.8  332.65  5044.2  340.25  5062.6  341.76  5224.4  341.75    5299  344.76
  5353.5  346.51    5359  349.26  5404.8  352.32  5450.7  352.28  5496.5  350.33
    5502  347.97  5519.4   347.6  5524.9  344.61  5588.8  344.02  5896.7  353.78
  6245.2   356.5  6332.5  357.85  6362.9  358.77  6480.6  363.29  6697.6  368.08
#Mann= 14 ,-1 , 0
    4013     .05       0  4141.6    .035       0  4176.6     .05       0
  4532.9    .035       0  4843.7     .05       0  4899.7      .1       0
  4969.5     .05       0  5038.8      .1       0    5299    .035       0
  5588.8     .07       0  6245.2     .05       0  6332.5    .035       0
  6362.9     .05       0  6480.6     .07       0
Bank Sta=4969.5,5038.8
XS Rating Curve= 0 ,0
Exp/Cntr=0.3,0.1

Type RM Length L Ch R = 1 ,99564   ,715,715,715
BEGIN DESCRIPTION:
SANDY FORK 63.0
END DESCRIPTION:
XS GIS Cut Line= 3
      2472375.01     13798925.01        2472075.       13798525.
      2470475.01     13797325.01
#Sta/Elev= 30
  4500.2  366.57  4611.5  362.51  4612.7   362.5  4892.9  350.41    4927  344.53
  4957.5  341.03  4962.4  332.77  4963.9  331.77  5031.7  332.77  5033.8  336.51
  5036.7  341.67  5128.3  338.52  5172.1  342.18  5400.2   342.6  5457.5  340.84
  5500.2  342.77  5542.9   339.7  5628.3  338.96  5749.6  343.21  5792.9  342.92
  5836.7  350.89  5857.5   351.7  5892.9  350.02  5907.5  345.37  5941.2  344.89
  6363.8  356.52  6575.1  356.98  6713.9  359.83  6745.6  361.15  7000.2  368.42
#Mann= 12 ,-1 , 0
  4500.2     .05       0  4611.5     .12       0  4612.7     .05       0
    4927      .1       0  4962.4     .05       0  5031.7      .1       0
  5033.8      .1       0  5749.6    .035       0  5941.2     .07       0
  6575.1    .035       0  6713.9     .05       0  6745.6     .07       0
Bank Sta=4962.4,5031.7
XS Rating Curve= 0 ,0
Exp/Cntr=0.3,0.1

Type RM Length L Ch R = 1 ,98849   ,661,661,661
BEGIN DESCRIPTION:
SANDY FORK 62.0
END DESCRIPTION:
XS GIS Cut Line= 3
      2473125.03     13798525.02        2472125.       13797925.
      2470524.98     13797124.99
#Sta/Elev= 30
  3842.5  385.96  3935.8  374.28  3966.9  374.94  4052.4  358.27  4126.3  353.61
  4506.3  346.11  4632.5  337.81  4732.2  338.02  4847.4  339.96  4857.1  339.31
  4864.9  331.96  4865.1  331.77  4866.6  330.77  4934.6  331.77  4958.2   334.8
    4964  332.11  4995.1  338.83  5000.9  334.94  5039.5  339.33  5394.3  341.13
  5503.2  342.36  5504.8  342.26  5611.4  346.95  5738.2  352.81  5836.5  350.98
  5858.4  354.25  6054.2  355.78  6207.9  358.36  6498.5  360.21  6797.6  370.39
#Mann= 14 ,-1 , 0
  3842.5     .05       0  4506.3     .12       0  4632.5      .1       0
  4732.2     .12       0  4864.9      .1       0  4865.1     .05       0
  4934.6      .1       0  5394.3     .05       0  5503.2    .035       0
  5504.8     .12       0  5611.4    .035       0  5836.5     .07       0
  6054.2    .035       0  6207.9     .05       0
Bank Sta=4865.1,4934.6
XS Rating Curve= 0 ,0
Exp/Cntr=0.3,0.1

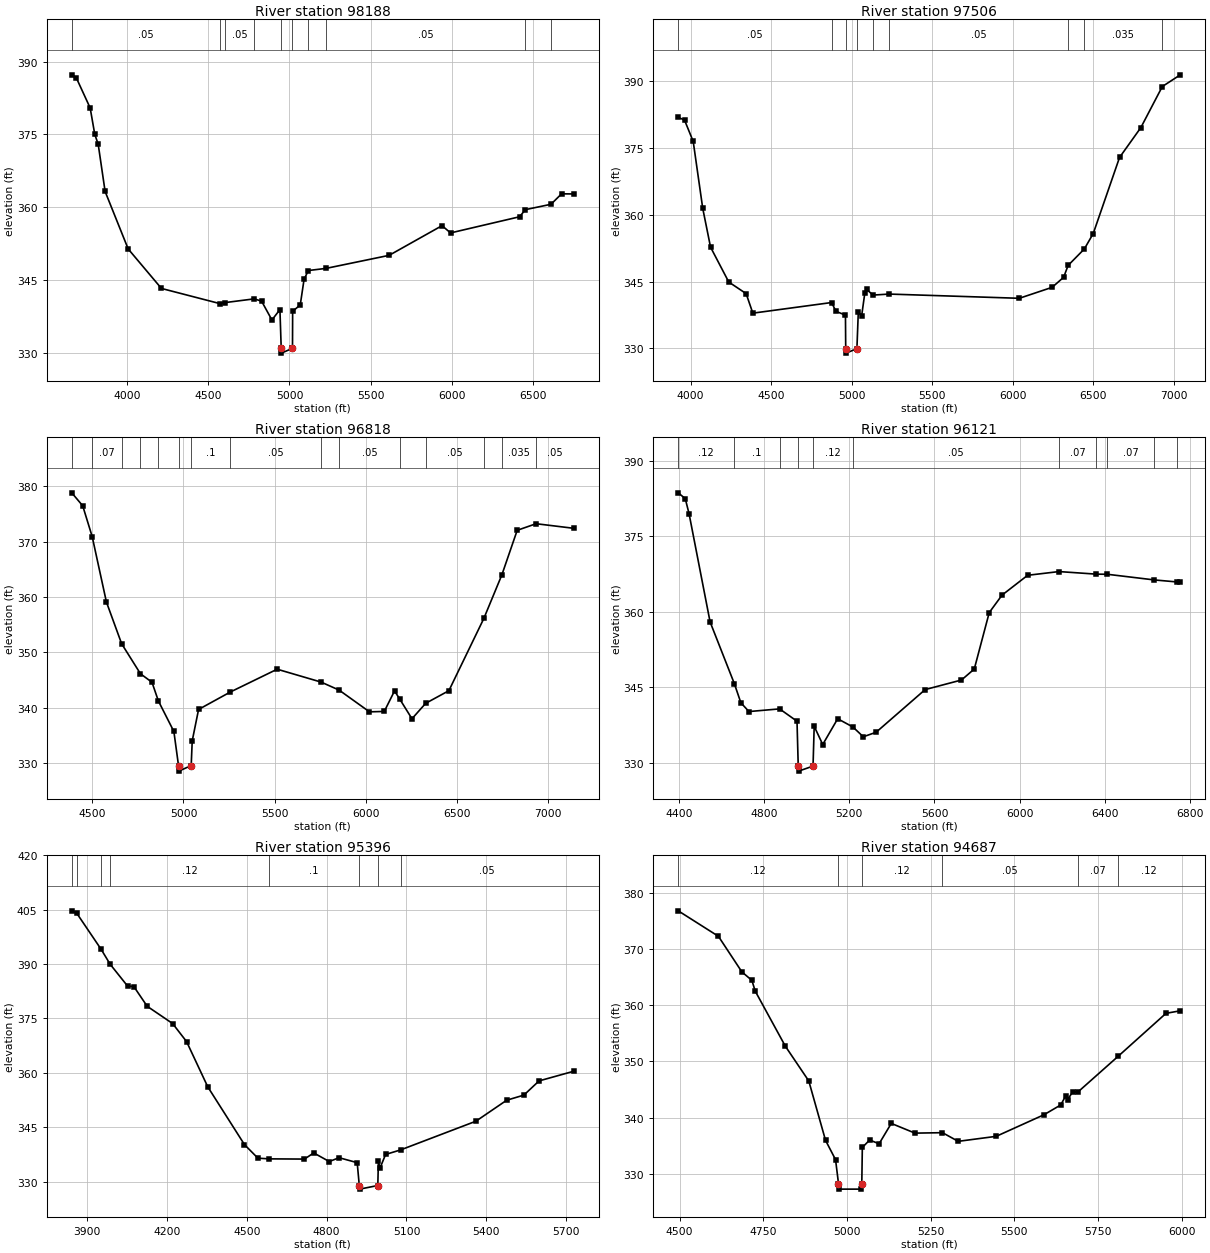
Type RM Length L Ch R = 1 ,98188   ,682,682,682
BEGIN DESCRIPTION:
SANDY FORK 61.0
END DESCRIPTION:
XS GIS Cut Line= 3
      2473175.03     13798525.03        2472275.       13797525.
      2471574.97     13795925.92
#Sta/Elev= 30
  3659.7  387.28  3687.8  386.65    3773  380.45  3801.4  374.99  3822.3     373
  3864.9  363.25  4006.9   351.4  4211.7  343.26    4571  340.14    4600  340.33
  4782.6  341.11  4828.3  340.64  4891.9  336.76  4941.2   338.9  4949.1  330.93
  4950.6  329.93  5018.6  330.93  5019.5  338.56  5066.3  339.85  5089.7  345.11
  5115.9  346.95  5224.7  347.39  5613.5  350.08  5939.3   356.2  5991.6   354.7
  6416.4  358.03  6452.5   359.5  6609.8   360.6  6675.3  362.76  6750.7  362.73
#Mann= 10 ,-1 , 0
  3659.7     .05       0    4571      .1       0    4600     .05       0
  4782.6      .1       0  4949.1     .05       0  5018.6      .1       0
  5115.9    .035       0  5224.7     .05       0  6452.5     .12       0
  6609.8    .035       0
Bank Sta=4949.1,5018.6
XS Rating Curve= 0 ,0
Exp/Cntr=0.3,0.1

Type RM Length L Ch R = 1 ,97506   ,688,688,688
BEGIN DESCRIPTION:
SANDY FORK 60.0
END DESCRIPTION:
XS GIS Cut Line= 3
      2473274.99     13798274.97        2472875.       13797275.
        2472475.       13795275.
#Sta/Elev= 30
    3923   381.9    3962   381.3  4015.9  376.49  4075.1  361.45  4123.6  352.74
  4236.6  344.91  4344.4   342.3  4386.1  337.91  4875.3   340.3  4901.7  338.32
    4961  337.47  4962.6  329.93  4964.1  328.93  5032.1  329.93  5040.8  338.21
  5061.2  337.23  5081.6  342.54  5091.8  343.28  5131.7  341.97  5232.6   342.2
  6040.2  341.25  6244.2  343.72  6315.5  345.98    6343  348.63  6443.9  352.34
  6499.1   355.8  6662.3  372.89  6794.9  379.62  6927.8  388.83  7039.6  391.46
#Mann= 9 ,-1 , 0
    3923     .05       0  4875.3      .1       0  4962.6     .05       0
  5032.1      .1       0  5131.7    .035       0  5232.6     .05       0
    6343     .12       0  6443.9    .035       0  6927.8     .07       0
Bank Sta=4962.6,5032.1
XS Rating Curve= 0 ,0
Exp/Cntr=0.3,0.1

Type RM Length L Ch R = 1 ,96818   ,697,697,697
BEGIN DESCRIPTION:
SANDY FORK 59.0
END DESCRIPTION:
XS GIS Cut Line= 3
        2473325.     13798224.96        2473325.       13797625.
      2473665.25     13795498.21
#Sta/Elev= 30
  4387.5  378.84  4447.5   376.5  4499.5  370.93  4577.5  359.12    4661  351.58
  4764.2  346.16  4827.5  344.62  4862.6  341.24  4947.5  335.73    4973  329.57
  4974.5  328.57  5042.5  329.57  5048.2  334.05    5083  339.71  5257.7  342.87
  5514.1  346.98  5754.5  344.66  5853.7  343.21  6020.4  339.28  6101.5  339.35
  6157.8  343.06  6186.8  341.56  6253.4  338.03  6328.7  340.82  6455.9   343.1
  6647.5  356.14  6746.7  364.04  6830.6  372.07  6934.4  373.26  7141.3  372.43
#Mann= 15 ,-1 , 0
  4387.5     .05       0  4499.5     .07       0    4661     .05       0
  4764.2     .12       0  4862.6      .1       0    4973     .05       0
  5042.5      .1       0  5257.7     .05       0  5754.5    .035       0
  5853.7     .05       0  6186.8     .07       0  6328.7     .05       0
  6647.5     .07       0  6746.7    .035       0  6934.4     .05       0
Bank Sta=4973,5042.5
XS Rating Curve= 0 ,0
Exp/Cntr=0.3,0.1

Type RM Length L Ch R = 1 ,96121   ,725,725,725
BEGIN DESCRIPTION:
SANDY FORK 58.0
END DESCRIPTION:
XS GIS Cut Line= 3
        2473825.     13798024.99        2473925.       13797425.
      2474038.57     13795679.75
#Sta/Elev= 30
    4397  383.61  4429.9  382.46  4447.7  379.49  4546.5  357.96  4660.3   345.7
    4691  341.89    4729  340.14  4872.8  340.67  4954.6  338.22  4960.4   329.3
  4961.9   328.3  5029.9   329.3  5035.3  337.21  5075.4  333.59  5145.6  338.71
  5217.1  337.07  5265.8  335.13  5325.9  336.02  5556.4  344.51  5726.8  346.41
  5786.9  348.59  5857.1  359.81  5917.2  363.28  6037.4  367.22  6184.6  367.96
  6359.3  367.45  6412.1  367.42  6632.1   366.3  6740.7  365.89  6754.2  365.84
#Mann= 11 ,-1 , 0
    4397     .12       0  4660.3      .1       0  4872.8     .12       0
  4960.4     .05       0  5029.9     .12       0  5217.1     .05       0
  6184.6     .07       0  6359.3     .05       0  6412.1     .07       0
  6632.1     .05       0  6740.7    .035       0
Bank Sta=4960.4,5029.9
XS Rating Curve= 0 ,0
Exp/Cntr=0.3,0.1

Type RM Length L Ch R = 1 ,95396   ,709,709,709
BEGIN DESCRIPTION:
SANDY FORK 57.0
END DESCRIPTION:
XS GIS Cut Line= 3
      2475174.99     13798224.98        2474575.       13797225.
      2474174.99     13796624.98
#Sta/Elev= 30
  3841.9  404.68  3861.2  403.95  3952.4  394.05  3986.1  389.95  4051.8  383.91
  4075.1   383.8  4125.6  378.33  4220.9  373.59  4273.4  368.61  4353.1  356.12
  4491.1  340.18  4541.6  336.44  4583.7  336.25  4716.5  336.19  4751.5  337.89
  4809.8  335.51  4846.7  336.57  4914.8   335.2  4922.7   328.9  4924.2   327.9
  4992.3   328.9  4994.5  335.65  5000.3  333.67  5021.6  337.47  5077.6  338.71
  5361.1  346.64  5476.8  352.43  5541.4  353.84  5598.5  357.76  5729.2  360.43
#Mann= 8 ,-1 , 0
  3841.9     .07       0  3861.2     .12       0  3952.4     .07       0
  3986.1     .12       0  4583.7      .1       0  4922.7     .05       0
  4992.3      .1       0  5077.6     .05       0
Bank Sta=4922.7,4992.3
XS Rating Curve= 0 ,0
Exp/Cntr=0.3,0.1

Type RM Length L Ch R = 1 ,94687   ,683,683,683
BEGIN DESCRIPTION:
SANDY FORK 56.0
END DESCRIPTION:
XS GIS Cut Line= 3
        2475275.     13797775.03        2475275.       13797275.
      2474675.02     13796475.03
#Sta/Elev= 30
  4496.1  376.76  4616.1  372.23  4686.1  365.91  4716.1  364.39  4726.1  362.48
  4816.1  352.68  4886.1   346.5  4936.1  335.95  4966.1   332.5  4974.9  328.26
  4976.4  327.26    5043  327.26  5044.5  328.26  5046.1  334.67    5068     336
  5096.1  335.32  5132.6  338.95  5203.4  337.22  5285.5   337.3  5332.6  335.76
  5446.1  336.65  5588.8  340.49  5638.8  342.23  5653.4  343.81  5659.7   343.2
  5674.3  344.54  5690.5  344.55  5809.7  350.85  5953.4  358.53  5996.1  358.98
#Mann= 6 ,-1 , 0
  4496.1     .12       0  4974.9     .05       0  5044.5     .12       0
  5285.5     .05       0  5690.5     .07       0  5809.7     .12       0
Bank Sta=4974.9,5044.5
XS Rating Curve= 0 ,0
Exp/Cntr=0.3,0.1