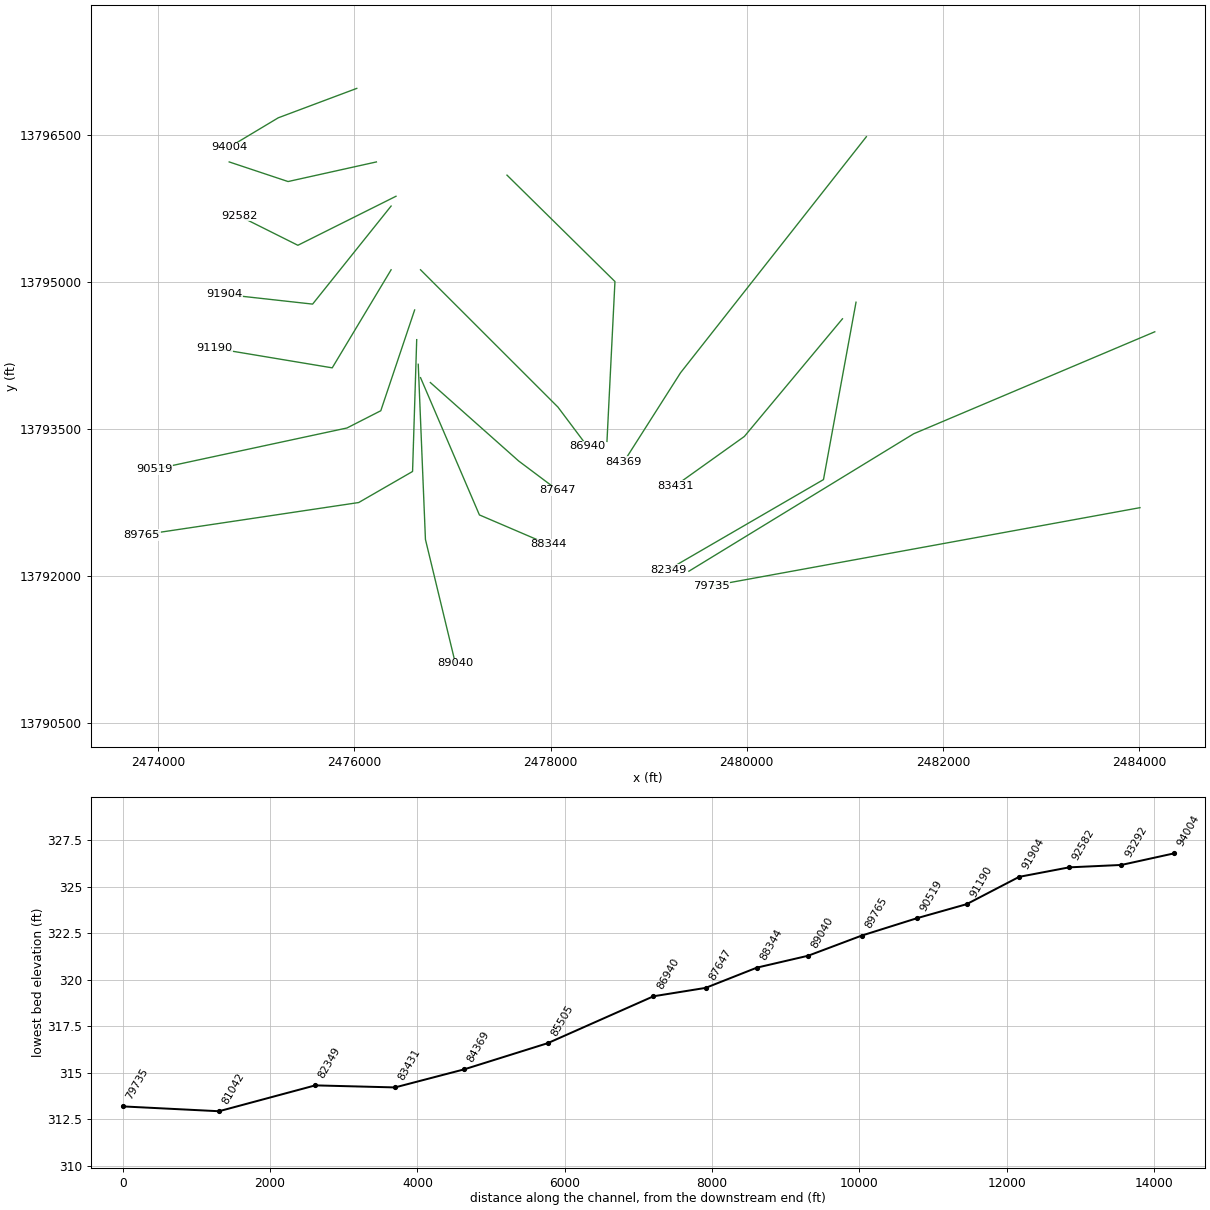
HEC-RAS study SANDY FORK.prj: SANDY FORK Base Level Engineering

--- SANDY FORK.g01 (geometry) --- (continued)

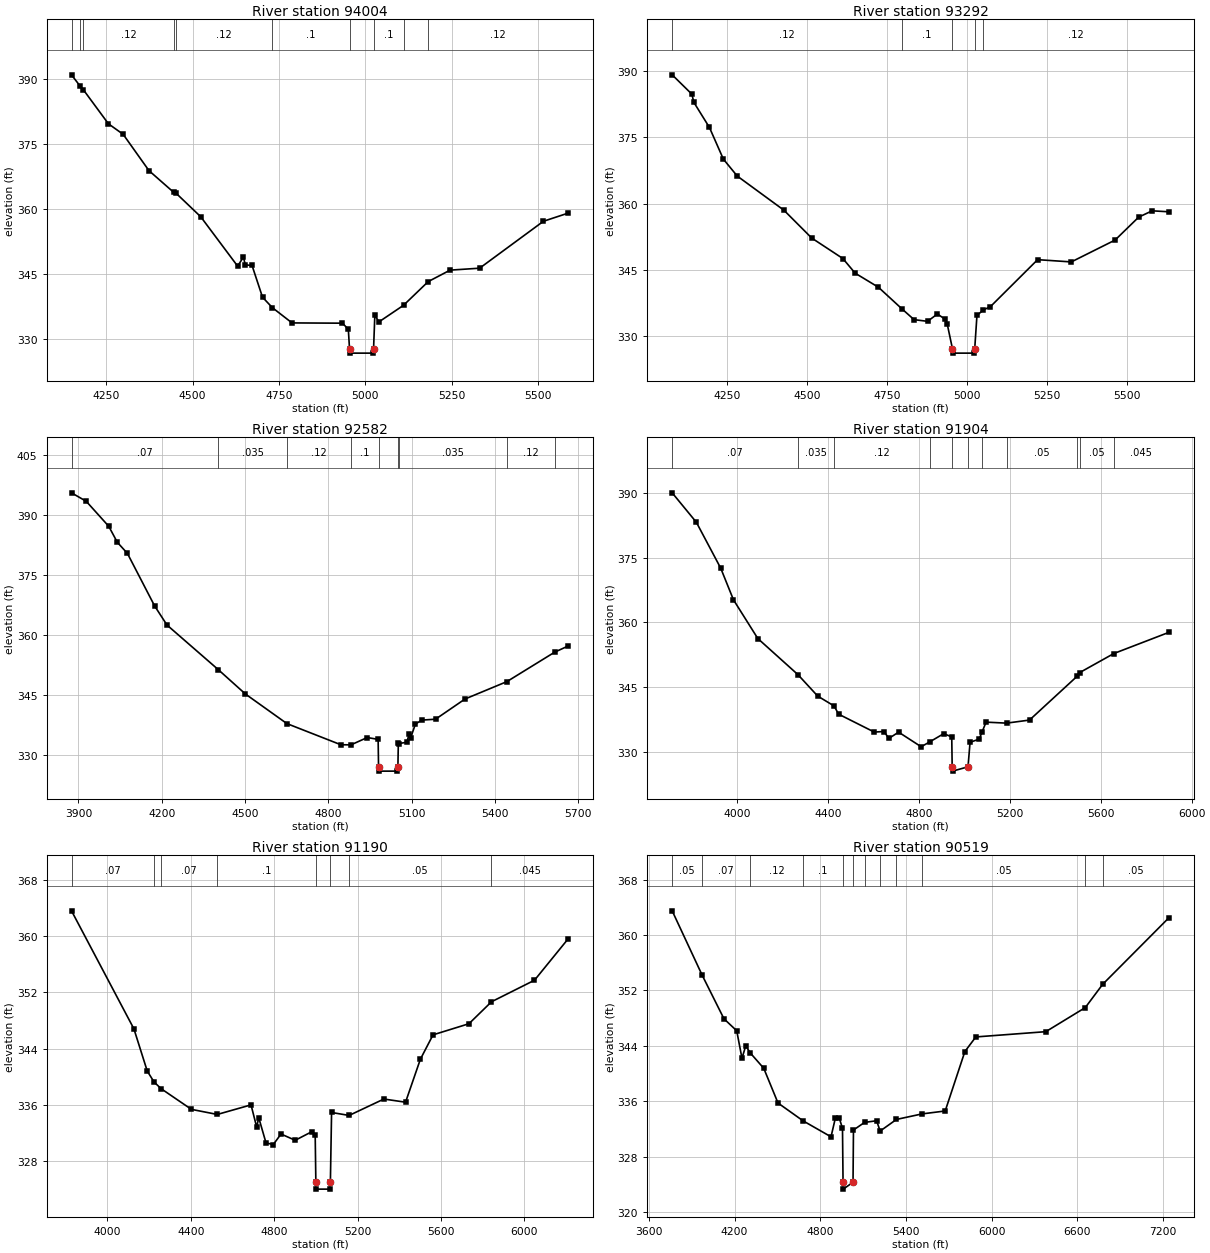
Type RM Length L Ch R = 1 ,94004   ,712,712,712
BEGIN DESCRIPTION:
SANDY FORK 55.0
END DESCRIPTION:
XS GIS Cut Line= 3
      2476024.97     13796974.99        2475225.       13796675.
      2474724.97     13796374.98
#Sta/Elev= 30
  4149.9   390.9  4175.6  388.22  4184.1  387.47  4256.7  379.62  4299.4  377.19
  4374.1  368.82  4445.5  363.83  4451.8  363.67  4523.7  358.21  4630.5  346.83
  4647.4   348.9  4652.7  347.12  4672.3  346.97  4702.6  339.66  4731.2  337.25
    4788  333.74    4934  333.68  4950.9  332.27  4954.3  327.78  4955.8  326.78
  5022.4  326.78  5023.9  327.78  5027.6  335.55  5039.3  333.97  5110.6   337.8
    5182  343.26  5245.3   345.9  5330.8  346.35  5515.4  357.16  5587.4  359.05
#Mann= 10 ,-1 , 0
  4149.9     .12       0  4175.6     .07       0  4184.1     .12       0
  4445.5     .07       0  4451.8     .12       0  4731.2      .1       0
  4954.3     .05       0  5023.9      .1       0  5110.6     .07       0
    5182     .12       0
Bank Sta=4954.3,5023.9
XS Rating Curve= 0 ,0
Exp/Cntr=0.3,0.1

Type RM Length L Ch R = 1 ,93292   ,710,710,710
BEGIN DESCRIPTION:
SANDY FORK 54.0
END DESCRIPTION:
XS GIS Cut Line= 3
      2476225.04     13796225.01        2475325.       13796025.
      2474725.05     13796224.98
#Sta/Elev= 30
    4078  389.17  4139.5   384.8  4145.9  382.93  4194.6  377.25  4238.1  370.09
  4281.6  366.25  4427.6  358.52  4514.7  352.21    4612  347.58  4650.4  344.27
  4723.4  341.07  4795.7  336.26  4834.8  333.74  4877.1  333.36  4907.8  335.02
  4932.1  333.83  4938.5  332.78  4954.9  327.16  4956.4  326.16  5023.1  326.16
  5024.6  327.16  5031.6   334.7  5051.6  335.93  5073.8  336.69  5221.4  347.32
  5326.8  346.81  5463.8  351.76  5537.6  356.95  5579.7  358.38  5632.4  358.16
#Mann= 5 ,-1 , 0
    4078     .12       0  4795.7      .1       0  4954.9     .05       0
  5024.6      .1       0  5051.6     .12       0
Bank Sta=4954.9,5024.6
XS Rating Curve= 0 ,0
Exp/Cntr=0.3,0.1

Type RM Length L Ch R = 1 ,92582   ,678,678,678
BEGIN DESCRIPTION:
SANDY FORK 53.0
END DESCRIPTION:
XS GIS Cut Line= 3
      2476425.02     13795875.01        2475425.       13795375.
      2474824.98     13795675.01
#Sta/Elev= 30
  3874.9  395.54    3928  393.42  4009.1  387.17  4039.8  383.19  4076.2  380.41
    4174  367.31  4218.7  362.52  4403.2  351.39    4501   345.3  4650.5   337.9
  4844.8  332.62  4881.1  332.59  4939.8  334.42    4979  333.96  4980.5  327.03
    4982  326.03  5048.7  326.03  5050.2  327.03  5051.7  333.04  5054.9  332.93
  5082.4  333.25  5090.8  335.35  5096.4  334.41  5113.1  337.76  5135.5  338.77
  5185.8     339    5292  344.05  5442.7  348.39  5614.9  355.75  5663.8   357.3
#Mann= 9 ,-1 , 0
  3874.9     .07       0  4403.2    .035       0  4650.5     .12       0
  4881.1      .1       0  4980.5     .05       0  5050.2      .1       0
  5054.9    .035       0  5442.7     .12       0  5614.9     .07       0
Bank Sta=4980.5,5050.2
XS Rating Curve= 0 ,0
Exp/Cntr=0.3,0.1

Type RM Length L Ch R = 1 ,91904   ,714,714,714
BEGIN DESCRIPTION:
SANDY FORK 52.0
END DESCRIPTION:
XS GIS Cut Line= 3
      2476374.97     13795774.96        2475575.       13794775.
      2474675.01       13794875.
#Sta/Elev= 30
  3714.1     390  3820.5  383.18  3927.8  372.53  3983.8  365.21    4091  356.24
  4267.4  347.88  4354.4  342.91  4426.7  340.61  4446.4  338.72  4603.3  334.57
  4646.5   334.7  4667.3  333.09  4710.5  334.55  4809.8  331.17  4847.8  332.31
    4909   334.2  4944.3  333.45  4946.2  326.52  4947.7  325.52  5015.9  326.52
  5024.9   332.2  5065.1  332.94  5076.8  334.47  5095.3  336.87  5185.6  336.64
  5286.5  337.35  5496.8  347.54  5506.6  348.33  5657.7  352.77  5900.2  357.68
#Mann= 11 ,-1 , 0
  3714.1     .07       0  4267.4    .035       0  4426.7     .12       0
  4847.8      .1       0  4946.2     .05       0  5015.9      .1       0
  5076.8     .07       0  5185.6     .05       0  5496.8     .12       0
  5506.6     .05       0  5657.7    .045       0
Bank Sta=4946.2,5015.9
XS Rating Curve= 0 ,0
Exp/Cntr=0.3,0.1

Type RM Length L Ch R = 1 ,91190   ,671,671,671
BEGIN DESCRIPTION:
SANDY FORK 51.0
END DESCRIPTION:
XS GIS Cut Line= 3
      2476374.99     13795124.98        2475775.       13794125.
      2474575.02       13794325.
#Sta/Elev= 30
  3828.2  363.59  4127.5  346.82  4191.6  340.81  4224.7  339.25  4258.5  338.31
  4403.5  335.38  4527.4  334.66  4689.2  336.02  4716.4  332.85  4726.1  334.21
  4761.1  330.61  4796.1  330.39    4833  331.88  4901.1  330.99  4980.8  332.21
  4996.9  331.75  5000.1  325.05  5001.6  324.05  5068.3  324.05  5069.8  325.05
  5075.5  334.94  5159.6  334.52  5326.4  336.85  5430.3   336.4  5501.3   342.5
  5562.1  345.97  5734.4  347.55  5842.5  350.67  6048.7  353.73  6210.9  359.64
#Mann= 8 ,-1 , 0
  3828.2     .07       0  4224.7    .035       0  4258.5     .07       0
  4527.4      .1       0  5000.1     .05       0  5069.8      .1       0
  5159.6     .05       0  5842.5    .045       0
Bank Sta=5000.1,5069.8
XS Rating Curve= 0 ,0
Exp/Cntr=0.3,0.1

Type RM Length L Ch R = 1 ,90519   ,754,754,754
BEGIN DESCRIPTION:
E20642
END DESCRIPTION:
XS GIS Cut Line= 4
      2476614.85      13794715.2      2476269.94      13793687.5
      2475925.03     13793511.52      2473963.03     13793089.59
#Sta/Elev= 30
  3763.5  363.51  3973.7   354.2  4126.1  347.91  4215.4  346.18  4252.2   342.2
  4278.5     344  4310.1  342.98  4404.6  340.76  4504.5  335.74  4679.7  333.17
  4875.5  330.86  4905.8  333.55  4933.7  333.54  4955.9  332.08  4959.8   324.3
  4961.3   323.3  5029.6   324.3  5032.7  331.84  5110.4  332.94  5194.8  333.18
  5219.4  331.69  5333.7  333.37  5513.3  334.17  5674.9  334.59  5812.7  343.18
  5889.4  345.29  6379.4  346.05  6655.7  349.53  6777.4  352.89  7241.6  362.52
#Mann= 12 ,-1 , 0
  3763.5     .05       0  3973.7     .07       0  4310.1     .12       0
  4679.7      .1       0  4959.8     .05       0  5029.6      .1       0
  5110.4     .12       0  5219.4     .05       0  5333.7     .12       0
  5513.3     .05       0  6655.7     .07       0  6777.4     .05       0
Bank Sta=4959.8,5029.6
XS Rating Curve= 0 ,0
Exp/Cntr=0.3,0.1

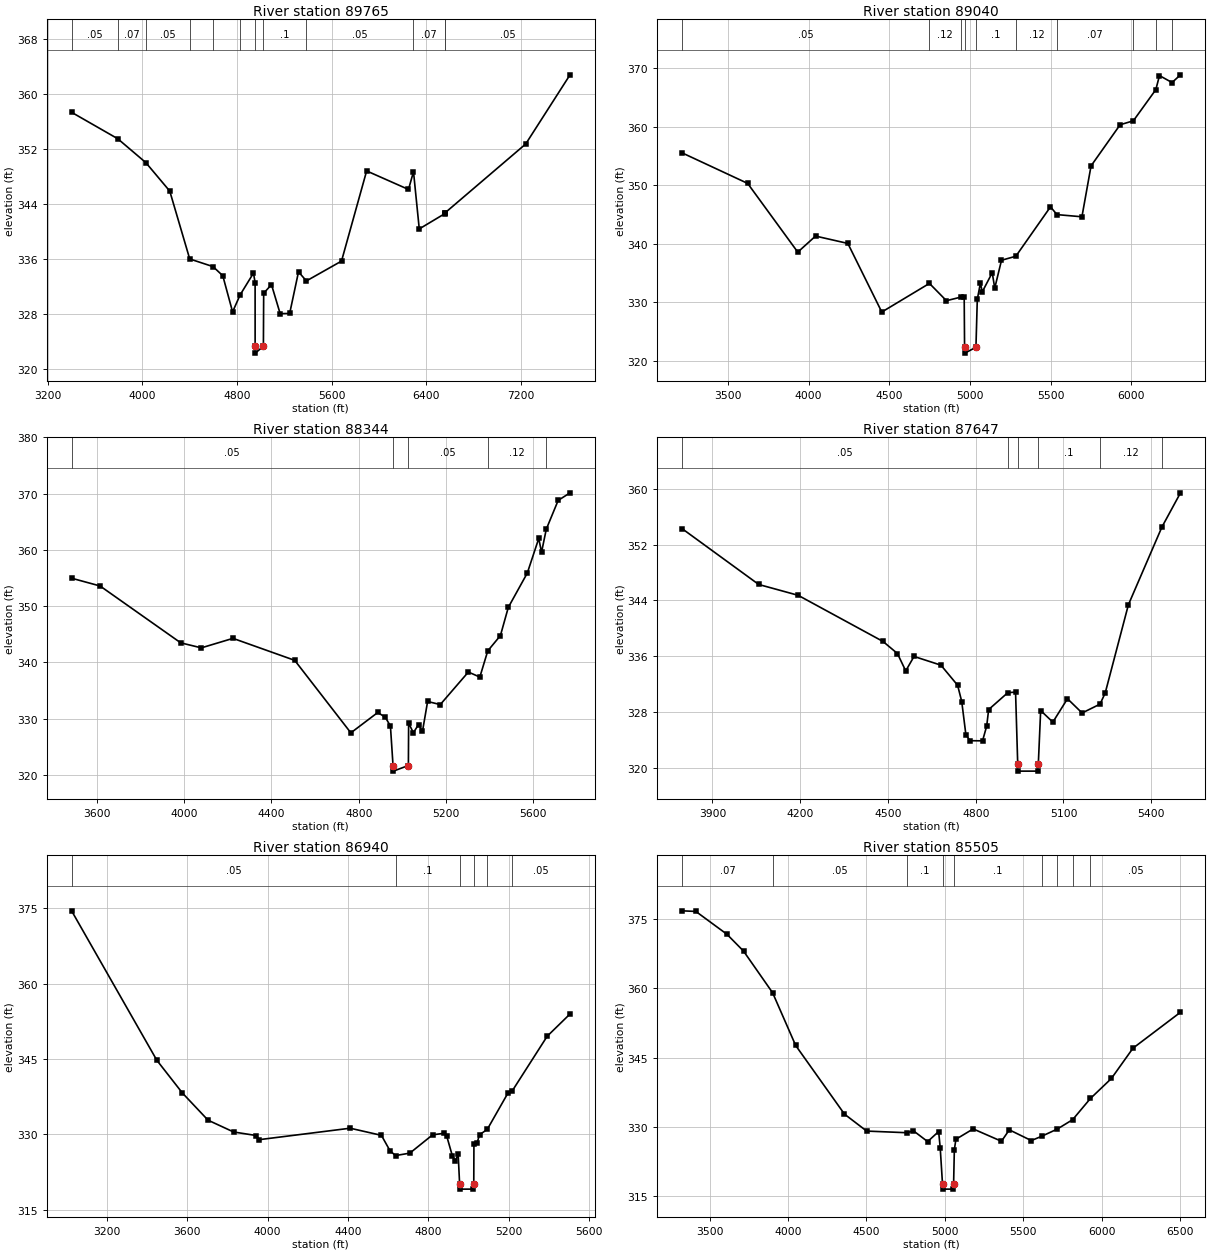
Type RM Length L Ch R = 1 ,89765   ,725,725,725
BEGIN DESCRIPTION:
E20641
END DESCRIPTION:
XS GIS Cut Line= 4
      2476635.97     13794412.55      2476593.73     13793068.07
      2476044.69     13792751.32      2473834.42     13792420.48
#Sta/Elev= 30
  3402.2  357.32  3792.6  353.48  4029.7  350.02  4232.2  345.88  4400.9  336.03
    4598  334.92  4680.4   333.6  4763.3  328.35  4827.3  330.82    4940  333.98
  4953.7  332.59  4953.9  323.36  4955.4  322.36  5023.8  323.36  5026.2  331.06
  5092.2   332.3  5165.5  328.09  5245.9  328.12  5320.6  334.16  5387.3  332.84
  5684.2  335.72  5896.6  348.81  6250.5  346.12  6292.8   348.7  6341.5  340.39
  6555.7  342.59    6557  342.65    6558   342.7  7241.4  352.72  7616.1  362.76
#Mann= 13 ,-1 , 0
  3402.2     .05       0  3792.6     .07       0  4029.7     .05       0
  4400.9     .07       0    4598     .12       0  4827.3      .1       0
  4953.9     .05       0  5023.8      .1       0  5387.3     .05       0
  6292.8     .07       0  6555.7     .05       0    6557     .07       0
    6558     .05       0
Bank Sta=4953.9,5023.8
XS Rating Curve= 0 ,0
Exp/Cntr=0.3,0.1

Type RM Length L Ch R = 1 ,89040   ,696,696,696
BEGIN DESCRIPTION:
SANDY FORK 50.0
END DESCRIPTION:
XS GIS Cut Line= 3
      2476651.69     13794161.07        2476725.       13792375.
      2477030.06     13791111.59
#Sta/Elev= 30
  3216.7  355.55  3623.1  350.32  3933.4  338.56  4043.5  341.31  4243.6  340.05
  4453.8  328.31  4748.9  333.21  4854.2  330.25  4945.7  330.88  4964.2  330.92
  4966.6  322.28  4968.1  321.28    5037  322.28  5045.4  330.48  5064.5  333.24
  5076.3  331.77    5138  335.04  5153.4   332.4  5195.3  337.17  5284.2  337.86
  5498.7  346.31    5539  344.98  5693.5  344.61    5750  353.32  5930.1  360.36
  6011.9  361.03  6151.1  366.36  6173.9  368.77  6251.6  367.58    6304   368.9
#Mann= 10 ,-1 , 0
  3216.7     .05       0  4748.9     .12       0  4945.7      .1       0
  4966.6     .05       0    5037      .1       0  5284.2     .12       0
    5539     .07       0  6011.9    .035       0  6151.1    .063       0
  6251.6    .094       0
Bank Sta=4966.6,5037
XS Rating Curve= 0 ,0
Exp/Cntr=0.3,0.1

Type RM Length L Ch R = 1 ,88344   ,697,697,697
BEGIN DESCRIPTION:
SANDY FORK 49.0
END DESCRIPTION:
XS GIS Cut Line= 3
      2476675.02     13794024.96        2477275.       13792625.
      2477975.01       13792325.
#Sta/Elev= 30
  3483.7  354.96  3614.2  353.58  3984.1  343.46  4078.4  342.57  4223.5  344.26
  4506.4  340.35  4763.8  327.45  4887.1  331.07  4921.6  330.23  4945.2  328.66
  4957.1  321.64  4958.6  320.64  5027.5  321.64  5028.6   329.2  5050.3  327.46
  5073.9  328.92    5092  327.69  5115.6  333.03  5173.6  332.48  5302.4  338.27
    5355  337.37  5391.3  342.03  5449.3  344.75  5485.5  349.77  5572.6  355.88
  5625.1  362.04  5637.8  359.57  5659.6  363.68    5714   368.8  5768.4  370.15
#Mann= 5 ,-1 , 0
  3483.7     .05       0  4957.1     .05       0  5027.5     .05       0
  5391.3     .12       0  5659.6    .035       0
Bank Sta=4957.1,5027.5
XS Rating Curve= 0 ,0
Exp/Cntr=0.3,0.1

Type RM Length L Ch R = 1 ,87647   ,707,707,707
BEGIN DESCRIPTION:
SANDY FORK 48.0
END DESCRIPTION:
XS GIS Cut Line= 3
      2476775.02     13793974.98        2477675.       13793175.
      2478074.98     13792875.02
#Sta/Elev= 30
  3796.1  354.29  4058.2  346.29  4192.9  344.74    4483  338.13  4532.4   336.4
  4560.8  333.91  4589.2  335.98  4681.2  334.73  4738.1  331.86  4752.3  329.52
  4766.5  324.76  4780.7  323.91  4823.4  323.89  4837.6     326  4844.3  328.37
  4909.8  330.79  4936.3  330.87  4943.7  320.55  4945.2  319.55  5012.6  319.55
  5014.1  320.55  5022.1  328.23  5063.8  326.57  5113.8  329.92  5163.8  327.88
  5225.2  329.15  5242.9  330.76  5322.1  343.39  5436.7  354.52  5500.2  359.42
#Mann= 6 ,-1 , 0
  3796.1     .05       0  4909.8      .1       0  4943.7     .05       0
  5014.1      .1       0  5225.2     .12       0  5436.7    .035       0
Bank Sta=4943.7,5014.1
XS Rating Curve= 0 ,0
Exp/Cntr=0.3,0.1

Type RM Length L Ch R = 1 ,86940   ,1435,1435,1435
BEGIN DESCRIPTION:
SANDY FORK 47.0
END DESCRIPTION:
XS GIS Cut Line= 3
      2476674.97     13795125.03        2478075.       13793725.
      2478374.98     13793325.03
#Sta/Elev= 30
  3024.7  374.52    3449  344.75  3576.3  338.23  3703.6  332.83  3830.8  330.48
    3944  329.77  3958.1  328.95  4410.7  331.23  4566.2  329.81  4608.7  326.76
  4636.3  325.78  4707.7  326.27  4820.8  329.91  4877.4  330.22  4891.5  329.61
  4919.8  325.64  4933.9  324.75  4948.1  326.02  4955.3   320.1  4956.8   319.1
  5024.2   319.1  5025.7   320.1  5026.5  327.99  5041.1  328.19  5054.6  329.94
  5092.8  330.99  5197.3  338.34  5217.9  338.71  5391.1  349.55  5504.6  353.98
#Mann= 6 ,-1 , 0
  3024.7     .05       0  4636.3      .1       0  4955.3     .05       0
  5025.7      .1       0  5092.8    .035       0  5217.9     .05       0
Bank Sta=4955.3,5025.7
XS Rating Curve= 0 ,0
Exp/Cntr=0.3,0.1

Type RM Length L Ch R = 1 ,85505   ,1136,1136,1136
BEGIN DESCRIPTION:
SANDY FORK 46.0
END DESCRIPTION:
XS GIS Cut Line= 3
      2477556.03     13796090.42      2478656.37     13795005.15
        2478575.     13793374.98
#Sta/Elev= 30
  3324.6   376.7  3412.5  376.57  3610.6  371.64  3716.6     368  3901.8  359.01
    4049  347.61  4360.1  332.78  4501.6  329.12  4760.8  328.76  4798.5  329.21
  4890.3  326.85  4960.4  329.02  4970.4  325.52  4985.2  317.58  4986.7  316.58
  5054.2  316.58  5055.7  317.58  5060.5  325.09  5070.5  327.35  5180.6  329.59
  5360.9  326.92  5410.9  329.39  5551.1  327.07  5617.3     328  5715.9  329.54
  5814.6  331.58    5928  336.16  6061.7  340.48  6199.2  347.02  6502.3  354.79
#Mann= 9 ,-1 , 0
  3324.6     .07       0  3901.8     .05       0  4760.8      .1       0
  4985.2     .05       0  5055.7      .1       0  5617.3     .12       0
  5715.9     .05       0  5814.6    .035       0    5928     .05       0
Bank Sta=4985.2,5055.7
XS Rating Curve= 0 ,0
Exp/Cntr=0.3,0.1

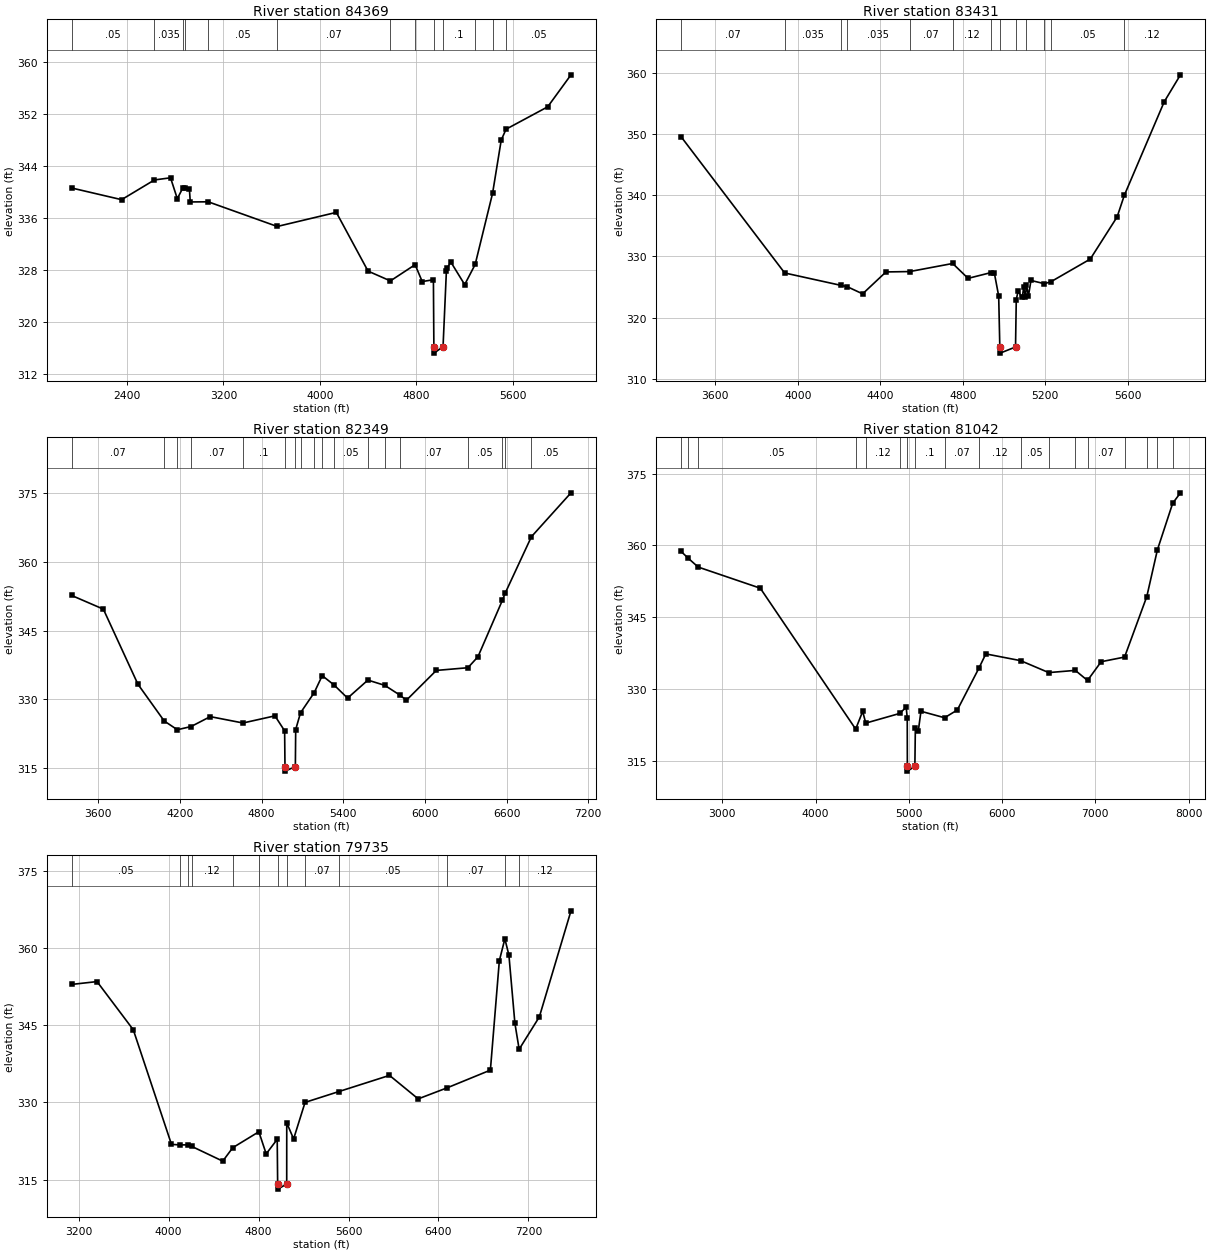
Type RM Length L Ch R = 1 ,84369   ,938,938,938
BEGIN DESCRIPTION:
SANDY FORK 45.0
END DESCRIPTION:
XS GIS Cut Line= 3
      2481218.73     13796482.27        2479325.       13794075.
      2478746.83     13793166.31
#Sta/Elev= 30
  1941.7  340.62  2355.9  338.82  2628.2  341.86  2761.7  342.19  2817.8  338.97
  2863.6  340.63  2883.9  340.68  2917.9  340.49  2925.3  338.47  3074.1  338.49
  3646.3  334.69  4136.1  336.86  4399.1  327.81  4584.4   326.3  4789.2   328.8
  4848.2   326.2    4941  326.48  4944.8  316.17  4946.3  315.17  5020.9  316.17
  5048.6  327.79  5054.5  328.24    5085  329.22  5200.2  325.73  5287.1  328.83
  5431.6  339.81  5503.3  348.01  5543.4  349.68  5888.5  353.13  6081.6  358.06
#Mann= 13 ,-1 , 0
  1941.7     .05       0  2628.2    .035       0  2863.6     .07       0
  2883.9    .035       0  3074.1     .05       0  3646.3     .07       0
  4584.4     .05       0  4789.2      .1       0  4944.8     .05       0
  5020.9      .1       0  5287.1    .035       0  5431.6     .07       0
  5543.4     .05       0
Bank Sta=4944.8,5020.9
XS Rating Curve= 0 ,0
Exp/Cntr=0.3,0.1

Type RM Length L Ch R = 1 ,83431   ,1082,1082,1082
BEGIN DESCRIPTION:
SANDY FORK 44.0
END DESCRIPTION:
XS GIS Cut Line= 3
      2480974.99     13794624.99        2479975.       13793425.
      2479274.97     13792924.98
#Sta/Elev= 30
  3433.5  349.54    3936  327.29  4211.2  325.25  4238.2  325.07  4314.1  323.88
  4427.3  327.46  4542.6  327.52  4750.9  328.84  4825.7  326.41  4935.2  327.34
  4953.2  327.25  4974.1  323.53  4979.6   315.2  4981.1   314.2  5055.8   315.2
  5059.4  322.95    5068  324.27  5088.9  323.33  5095.1  324.93  5103.7  323.32
  5108.9  325.36  5118.4  323.55  5130.7  326.07  5195.8  325.54  5227.5  325.86
  5418.3  329.56  5548.5  336.44  5583.4  339.96  5777.1  355.25  5855.8  359.65
#Mann= 13 ,-1 , 0
  3433.5     .07       0    3936    .035       0  4211.2     .07       0
  4238.2    .035       0  4542.6     .07       0  4750.9     .12       0
  4935.2      .1       0  4979.6     .05       0  5055.8      .1       0
  5108.9     .12       0  5195.8    .035       0  5227.5     .05       0
  5583.4     .12       0
Bank Sta=4979.6,5055.8
XS Rating Curve= 0 ,0
Exp/Cntr=0.3,0.1

Type RM Length L Ch R = 1 ,82349   ,1307,1307,1307
BEGIN DESCRIPTION:
E20640
END DESCRIPTION:
XS GIS Cut Line= 3
      2481113.23     13794794.16      2480781.63      13792985.4
      2479199.53     13792066.28
#Sta/Elev= 30
  3404.7  352.67  3637.7  349.68  3891.8  333.28  4084.8  325.26  4181.1  323.35
  4281.7  324.04  4423.2  326.21  4663.6  324.82  4898.3  326.38  4969.5  323.11
  4972.1  315.31  4973.6  314.31  5048.3  315.31  5050.8  323.39  5086.3  327.05
  5186.9  331.45  5245.7  335.16  5333.5   333.1    5432  330.25  5581.2  334.19
  5705.2  333.04  5815.3  330.93  5864.2  329.79  6083.9   336.3    6316  336.89
  6389.7  339.28  6569.4  351.62  6590.3   353.2  6782.6   365.5  7073.3  375.08
#Mann= 18 ,-1 , 0
  3404.7     .07       0  4084.8    .035       0  4181.1     .12       0
  4281.7     .07       0  4663.6      .1       0  4972.1     .05       0
  5048.3      .1       0  5086.3     .07       0  5186.9     .12       0
  5245.7     .07       0  5333.5     .05       0  5581.2     .07       0
  5705.2    .035       0  5815.3     .07       0    6316     .05       0
  6569.4     .12       0  6590.3     .07       0  6782.6     .05       0
Bank Sta=4972.1,5048.3
XS Rating Curve= 0 ,0
Exp/Cntr=0.3,0.1

Type RM Length L Ch R = 1 ,81042   ,1307,1307,1307
BEGIN DESCRIPTION:
E20639
END DESCRIPTION:
XS GIS Cut Line= 3
       2484157.9     13794492.67      2481701.07     13793452.66
      2479409.98     13792050.87
#Sta/Elev= 30
  2558.3  358.76  2635.9  357.32  2741.5   355.5  3407.4  351.09    4430  321.69
  4505.2  325.38  4538.1  322.94    4901  324.95  4971.6  326.25    4983  324.03
  4984.1  313.92  4985.6  312.92  5064.7  313.92  5069.9  321.86  5100.9  321.23
    5130  325.41  5382.9  324.06  5519.6  325.67  5750.7  334.38  5825.3  337.38
  6198.9  335.97  6499.8  333.48  6784.9  333.94  6915.8  331.84  7062.1  335.75
    7313  336.72  7551.4  349.35  7664.9  359.09    7829  368.82  7912.1  370.99
#Mann= 18 ,-1 , 0
  2558.3     .05       0  2635.9    .035       0  2741.5     .05       0
    4430     .07       0  4538.1     .12       0    4901      .1       0
  4984.1     .05       0  5064.7      .1       0  5382.9     .07       0
  5750.7     .12       0  6198.9     .05       0  6499.8     .07       0
  6784.9    .035       0  6915.8     .07       0    7313     .05       0
  7551.4     .12       0  7664.9     .07       0    7829     .05       0
Bank Sta=4984.1,5064.7
XS Rating Curve= 0 ,0
Exp/Cntr=0.3,0.1

Type RM Length L Ch R = 1 ,79735   ,1580,1580,1580
BEGIN DESCRIPTION:
E20638
END DESCRIPTION:
XS GIS Cut Line= 2
      2484007.17     13792699.02      2479638.04     13791900.52
#Sta/Elev= 30
  3137.3   352.9  3363.2  353.45  3685.7   344.1  4025.4  321.86  4102.1  321.76
  4171.8  321.77  4203.8  321.49  4481.4  318.61  4570.4  321.22  4802.5  324.31
  4867.7  320.02  4965.8  322.84  4969.7  314.18  4971.2  313.18  5050.3  314.18
  5050.6  326.04  5111.6  322.92  5213.5  330.01  5515.4  332.12  5964.5  335.25
  6219.7  330.69    6480  332.86  6861.9  336.27  6941.5   357.5  6990.6  361.74
  7026.7  358.58  7079.9  345.35  7117.7  340.32  7297.3   346.6  7578.8  367.18
#Mann= 13 ,-1 , 0
  3137.3     .05       0  4102.1     .12       0  4171.8     .07       0
  4203.8     .12       0  4570.4     .05       0  4802.5      .1       0
  4969.7     .05       0  5050.3      .1       0  5213.5     .07       0
  5515.4     .05       0    6480     .07       0  6990.6    .035       0
  7117.7     .12       0
Bank Sta=4969.7,5050.3
XS Rating Curve= 0 ,0
Exp/Cntr=0.3,0.1