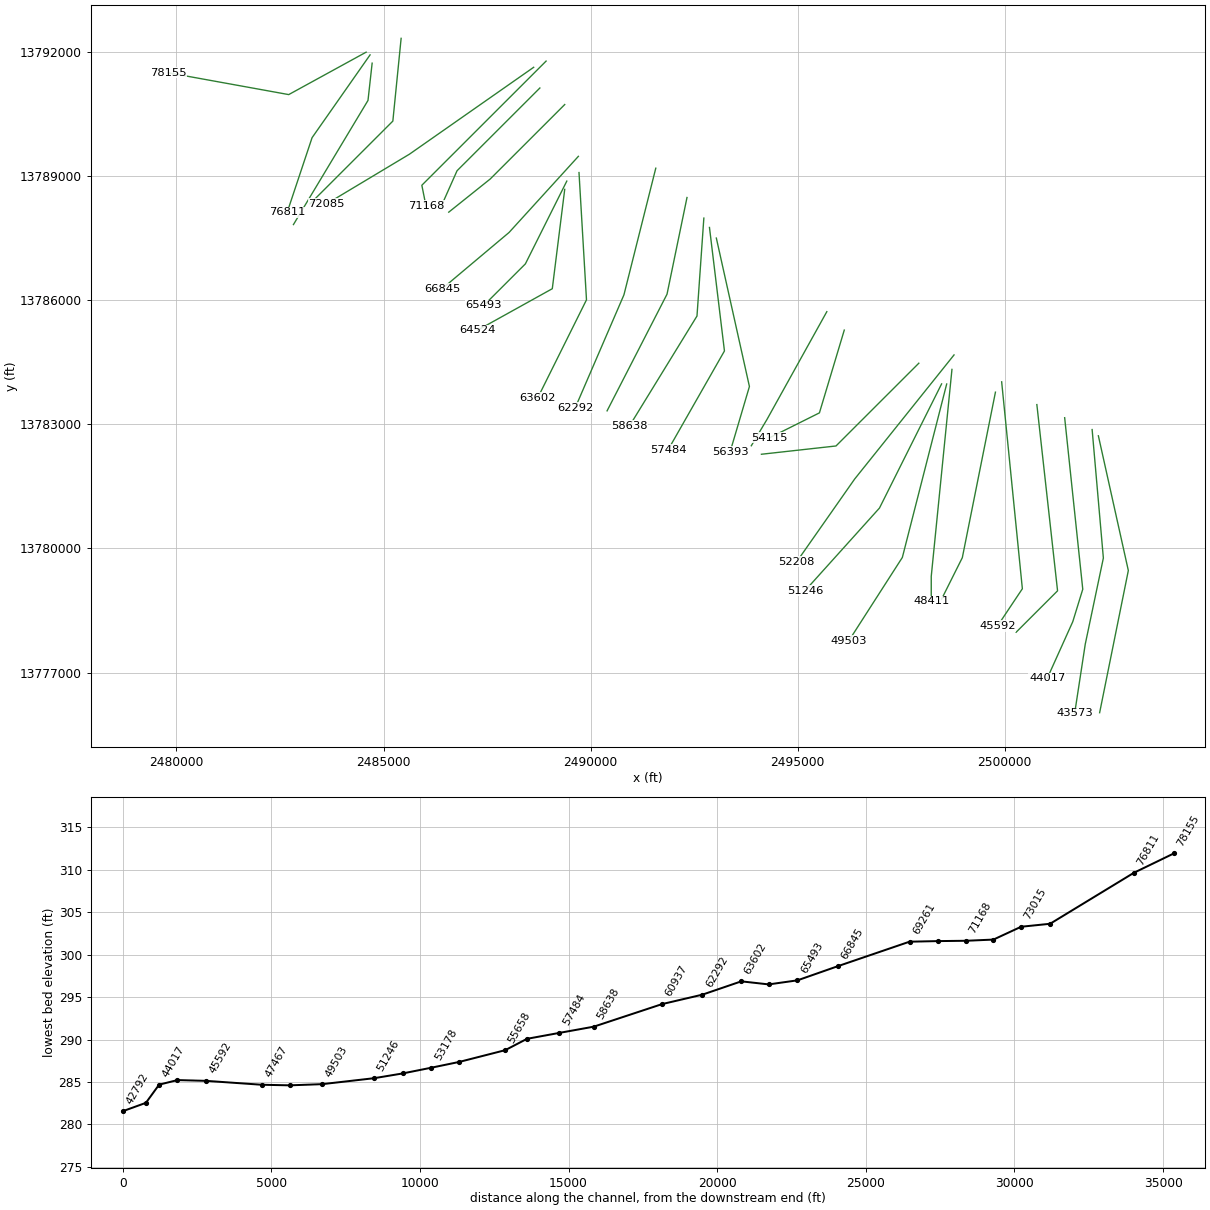
HEC-RAS study SANDY FORK.prj: SANDY FORK Base Level Engineering

--- SANDY FORK.g01 (geometry) --- (continued)

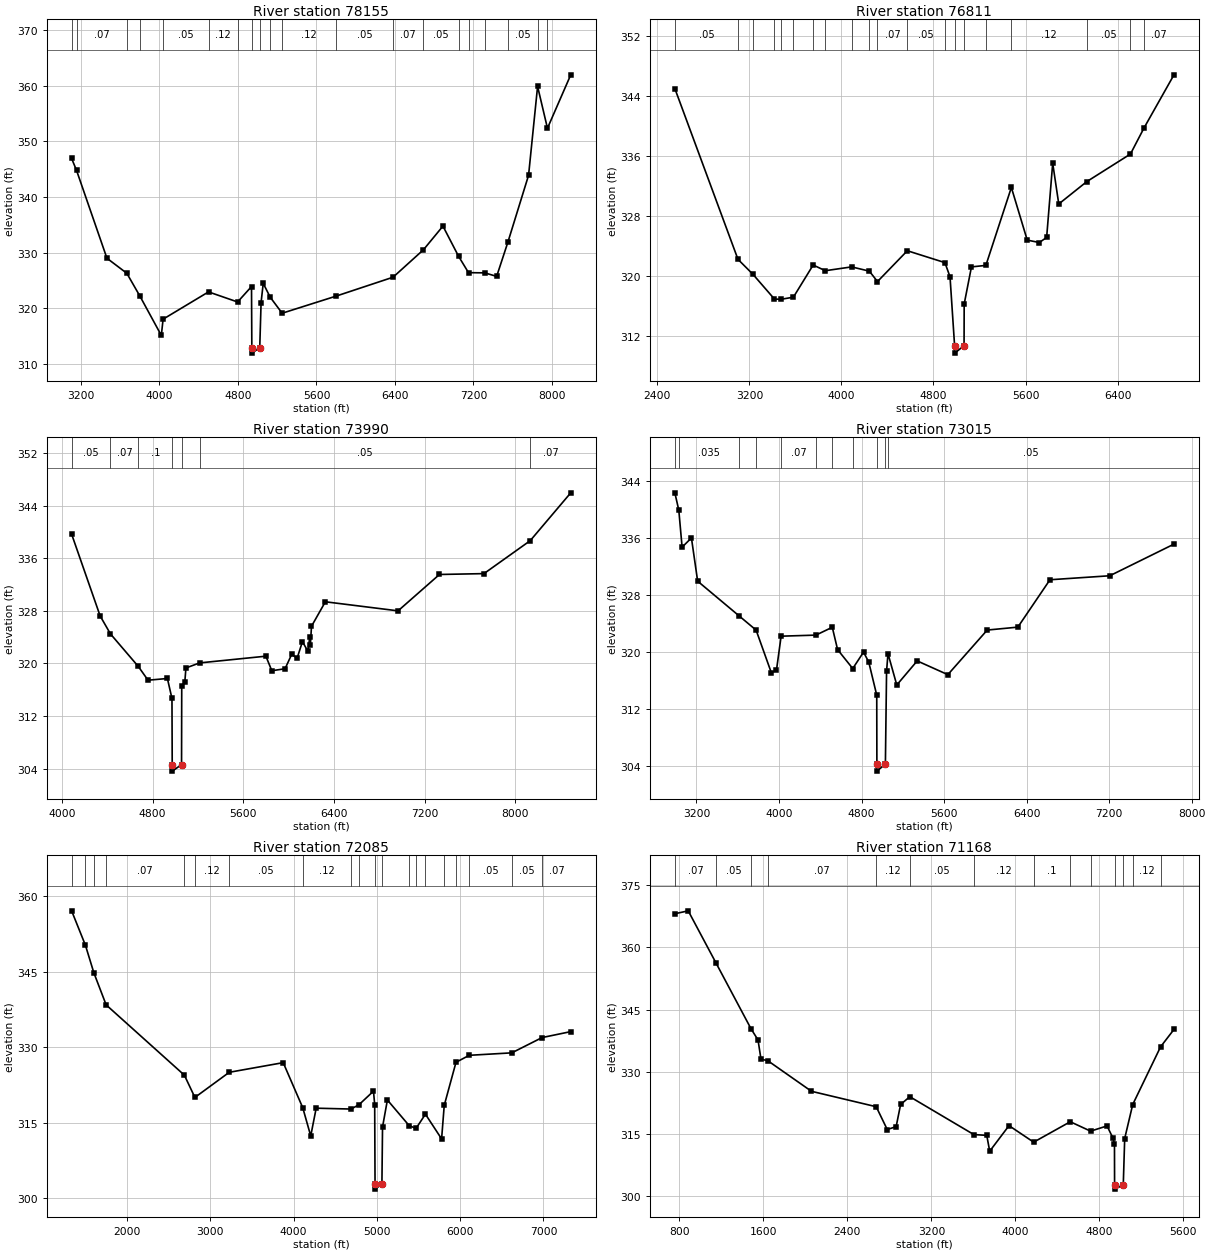
Type RM Length L Ch R = 1 ,78155   ,1344,1344,1344
BEGIN DESCRIPTION:
E20637
END DESCRIPTION:
XS GIS Cut Line= 3
      2484579.97     13791990.61      2482710.94     13790965.65
      2479801.91      13791493.2
#Sta/Elev= 30
  3104.2   346.9  3154.6  344.75  3464.1  328.98  3666.7  326.28  3800.1  322.18
  4018.6  315.11  4036.7  318.03  4499.6  322.93  4796.2  321.12    4938  323.89
  4941.3  312.93  4942.8  311.93    5022  312.93  5035.6  321.01  5057.4  324.47
    5128  321.99  5250.5   319.1  5797.9  322.16  6381.1  325.57  6691.2  330.51
  6889.4  334.75  7049.4  329.31    7150  326.39  7315.1  326.35  7437.1  325.72
  7552.5  331.92  7762.3  343.88  7854.3  359.85  7954.9  352.33  8192.3  361.93
#Mann= 20 ,-1 , 0
  3104.2    .035       0  3154.6     .07       0  3666.7     .05       0
  3800.1     .07       0  4036.7     .05       0  4499.6     .12       0
  4796.2     .05       0  4941.3     .05       0    5022     .05       0
    5128     .07       0  5250.5     .12       0  5797.9     .05       0
  6381.1     .07       0  6691.2     .05       0  7049.4     .07       0
    7150     .12       0  7315.1     .07       0  7552.5     .05       0
  7854.3    .035       0  7954.9     .07       0
Bank Sta=4941.3,5022
XS Rating Curve= 0 ,0
Exp/Cntr=0.3,0.1

Type RM Length L Ch R = 1 ,76811   ,2821,2821,2821
BEGIN DESCRIPTION:
SANDY FORK 41.0
END DESCRIPTION:
XS GIS Cut Line= 3
        2484675.       13791925.        2483275.       13789925.
      2482674.99     13788124.98
#Sta/Elev= 30
  2551.7  345.03  3100.5  322.19  3230.6  320.19  3417.3  316.88  3475.8  316.85
  3582.3  317.13    3754  321.43  3859.9  320.67  4088.6  321.18  4242.5  320.61
  4313.3  319.22  4572.6  323.34  4899.4  321.75  4943.8  319.85  4983.5  310.65
    4985  309.65  5065.8  310.65  5066.8  316.21    5130  321.18  5255.4  321.38
    5477   331.8  5614.9  324.76  5720.3  324.44  5783.6  325.12  5836.3  335.04
    5889  329.59  6132.4  332.58  6512.2  336.27  6629.1  339.73  6890.4  346.86
#Mann= 20 ,-1 , 0
  2551.7     .05       0  3100.5     .07       0  3230.6      .1       0
  3417.3     .12       0  3475.8      .1       0  3582.3     .12       0
    3754     .05       0  3859.9     .12       0  4088.6     .05       0
  4242.5     .05       0  4313.3     .07       0  4572.6     .05       0
  4899.4      .1       0  4983.5     .05       0  5065.8      .1       0
  5255.4     .05       0    5477     .12       0  6132.4     .05       0
  6512.2    .035       0  6629.1     .07       0
Bank Sta=4983.5,5065.8
XS Rating Curve= 0 ,0
Exp/Cntr=0.3,0.1

Type RM Length L Ch R = 1 ,73990   ,975,975,975
BEGIN DESCRIPTION:
SANDY FORK 40.0
END DESCRIPTION:
XS GIS Cut Line= 3
        2484725.     13791724.96        2484625.       13790825.
      2482824.99     13787824.98
#Sta/Elev= 30
  4086.3  339.66  4337.8  327.23  4428.8   324.5  4674.7  319.55  4760.4  317.46
  4931.4  317.72  4971.7  314.68  4973.9  304.64  4975.4  303.64  5056.3  304.64
  5057.9  316.53  5085.1  317.19  5094.8  319.32    5216  320.09  5800.4  321.11
  5852.8   318.9  5969.5   319.2  6027.8  321.38  6076.4  320.82    6123  323.33
  6171.6  321.83  6187.1  323.97    6193  322.76  6202.7  325.65  6325.1  329.38
  6966.6     328    7332  333.53  7724.6  333.66  8132.9  338.67  8490.4  345.94
#Mann= 7 ,-1 , 0
  4086.3     .05       0  4428.8     .07       0  4674.7      .1       0
  4973.9     .05       0  5056.3      .1       0    5216     .05       0
  8132.9     .07       0
Bank Sta=4973.9,5056.3
XS Rating Curve= 0 ,0
Exp/Cntr=0.3,0.1

Type RM Length L Ch R = 1 ,73015   ,930,930,930
BEGIN DESCRIPTION:
SANDY FORK 39.0
END DESCRIPTION:
XS GIS Cut Line= 3
        2485425.     13792324.95        2485225.       13790325.
      2483224.97     13788324.97
#Sta/Elev= 30
  2990.1  342.35  3028.5  339.92  3060.4  334.72  3150.9  336.02  3211.2  329.95
  3614.5  325.06  3777.9  323.08  3924.7  317.13  3974.9  317.42  4020.4  322.23
  4357.6  322.38  4516.3  323.48  4567.9  320.34  4714.7  317.69  4819.1  319.99
  4869.4  318.62  4947.3  313.95  4948.7  304.29  4950.2  303.29  5031.2  304.29
  5042.5  317.29  5056.2  319.79  5141.5  315.38  5339.4  318.76  5636.4  316.83
  6018.3  323.09  6315.2   323.5  6626.4  330.15  7206.2  330.71  7828.5  335.15
#Mann= 11 ,-1 , 0
  2990.1    .094       0  3028.5    .035       0  3614.5     .07       0
  3777.9     .12       0  4020.4     .07       0  4357.6     .05       0
  4516.3     .12       0  4714.7      .1       0  4948.7     .05       0
  5031.2      .1       0  5056.2     .05       0
Bank Sta=4948.7,5031.2
XS Rating Curve= 0 ,0
Exp/Cntr=0.3,0.1

Type RM Length L Ch R = 1 ,72085   ,917,917,917
BEGIN DESCRIPTION:
SANDY FORK 38.0
END DESCRIPTION:
XS GIS Cut Line= 3
      2488624.99       13791625.        2485625.       13789525.
      2483625.03     13788325.02
#Sta/Elev= 30
  1333.9  357.14  1499.7  350.29  1600.8  344.82  1748.5  338.43  2687.9  324.45
  2814.4  320.02  3226.8  325.02    3875  326.94  4110.2  317.95  4205.5  312.36
  4270.9  317.88  4689.1  317.71  4783.5  318.55  4959.2  321.27  4973.6  318.58
  4977.9  302.78  4979.4  301.78  5060.4  302.78  5067.8  314.13  5126.1  319.51
  5387.1  314.42    5470  313.85    5583  316.69  5777.2  311.77  5808.8  318.43
  5950.1  327.01  6109.3   328.4  6620.4  328.89  6984.2  331.93  7328.2  333.11
#Mann= 20 ,-1 , 0
  1333.9     .07       0  1499.7     .05       0  1600.8    .035       0
  1748.5     .07       0  2687.9     .12       0  2814.4     .12       0
  3226.8     .05       0  4110.2     .12       0  4689.1     .07       0
  4783.5     .12       0  4977.9     .05       0  5060.4      .1       0
  5387.1      .1       0    5470     .12       0    5583     .12       0
  5808.8     .07       0  5950.1    .035       0  6109.3     .05       0
  6620.4     .05       0  6984.2     .07       0
Bank Sta=4977.9,5060.4
XS Rating Curve= 0 ,0
Exp/Cntr=0.3,0.1

Type RM Length L Ch R = 1 ,71168   ,965,965,965
BEGIN DESCRIPTION:
SANDY FORK 37.0
END DESCRIPTION:
XS GIS Cut Line= 3
      2488925.03     13791775.03        2485925.       13788775.
        2486025.     13788274.99
#Sta/Elev= 30
   757.2  368.13   884.5  368.84  1148.5  356.28  1482.4  340.37  1549.2  337.66
  1577.5  333.01  1641.8  332.66  2058.3  325.26  2674.6  321.54  2779.6  316.03
  2864.4  316.73  2906.9  322.08  2994.5  323.96  3603.7  314.82  3727.1  314.62
  3755.4   310.8  3939.2  316.97  4173.9  312.98  4522.5  317.91  4715.9  315.64
  4872.6   316.9  4929.2  313.94  4943.3  312.59  4944.4  302.64  4945.9  301.64
  5027.1  302.64  5040.7  313.86    5117  322.06  5382.3     336  5509.8   340.2
#Mann= 14 ,-1 , 0
   757.2     .07       0  1148.5     .05       0  1482.4    .035       0
  1641.8     .07       0  2674.6     .12       0  2994.5     .05       0
  3603.7     .12       0  4173.9      .1       0  4522.5     .12       0
  4715.9      .1       0  4944.4     .05       0  5027.1      .1       0
    5117     .12       0  5382.3     .05       0
Bank Sta=4944.4,5027.1
XS Rating Curve= 0 ,0
Exp/Cntr=0.3,0.1

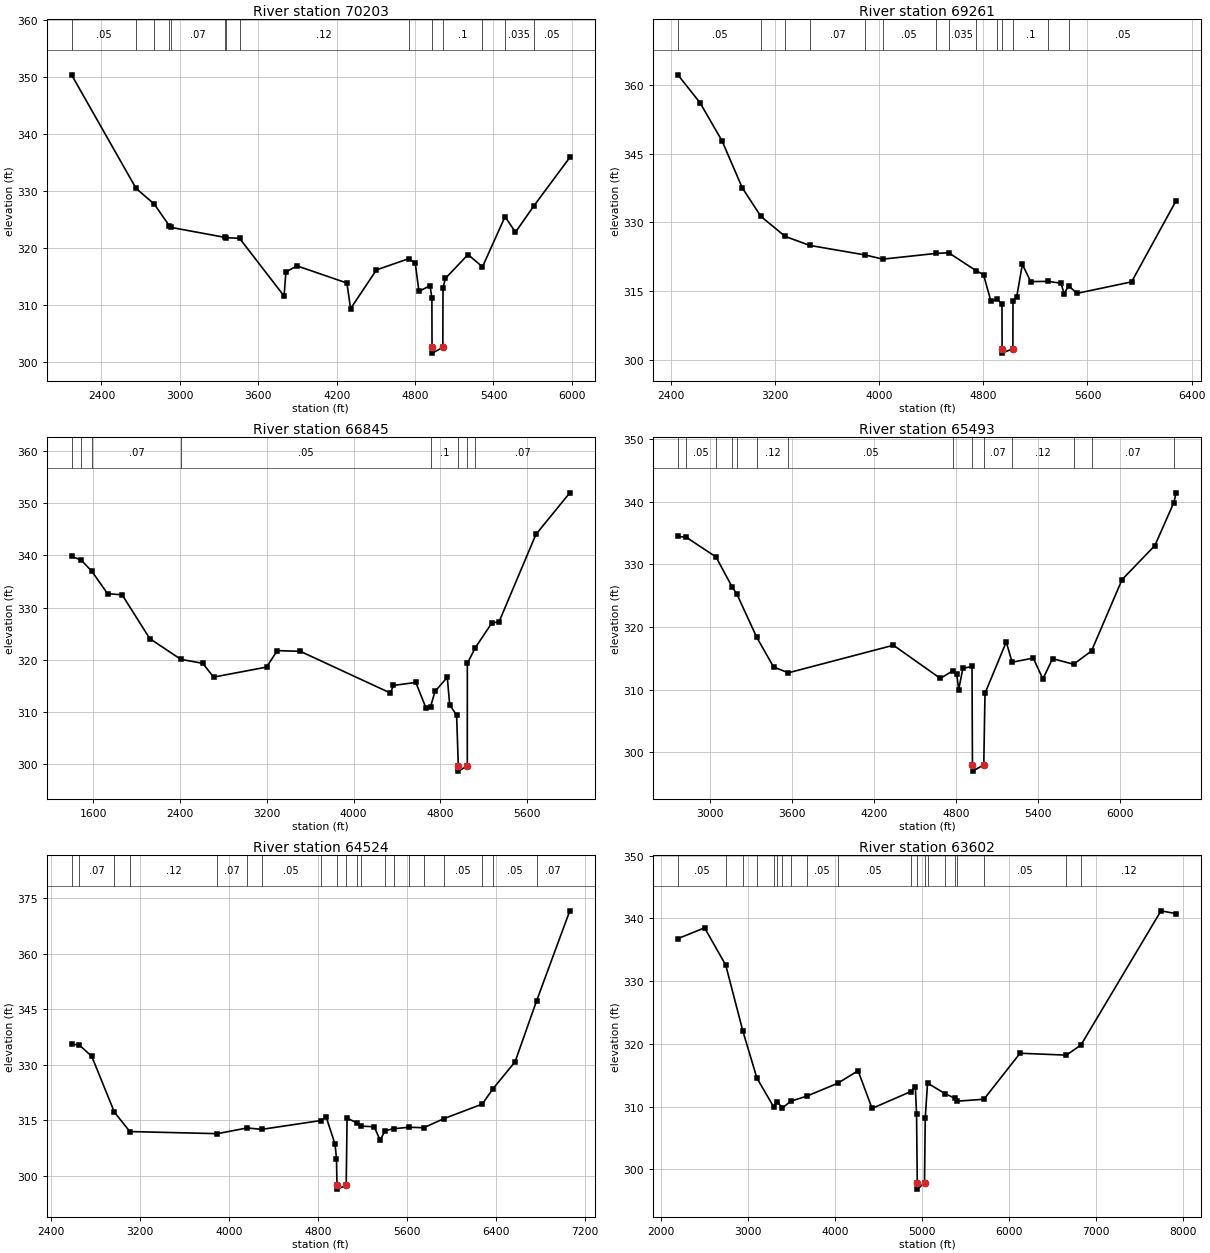
Type RM Length L Ch R = 1 ,70203   ,942,942,942
BEGIN DESCRIPTION:
SANDY FORK 36.0
END DESCRIPTION:
XS GIS Cut Line= 3
      2488775.01     13791125.01        2486775.       13789125.
      2486375.01     13788225.02
#Sta/Elev= 30
  2171.2   350.4  2664.7  330.49  2803.6  327.74  2920.3   323.9  2935.6  323.63
  3344.1   321.9  3350.1  321.85  3456.9  321.73  3797.6  311.61  3811.7  315.83
  3896.6   316.9  4278.4  313.89  4306.7  309.41  4504.7  316.19  4752.8  318.17
  4801.7  317.35  4829.9  312.42  4914.8  313.44  4928.9  311.27    4930   302.6
  4931.5   301.6  5012.7   302.6    5014  313.01  5031.8  314.69  5205.5  318.88
  5316.2  316.73  5488.8  325.53  5568.7   322.8  5706.9  327.34  5984.5  335.91
#Mann= 14 ,-1 , 0
  2171.2     .05       0  2664.7    .035       0  2803.6     .07       0
  2920.3    .035       0  2935.6     .07       0  3344.1     .12       0
  3350.1     .07       0  3456.9     .12       0  4752.8      .1       0
    4930     .05       0  5012.7      .1       0  5316.2     .12       0
  5488.8    .035       0  5706.9     .05       0
Bank Sta=4930,5012.7
XS Rating Curve= 0 ,0
Exp/Cntr=0.3,0.1

Type RM Length L Ch R = 1 ,69261   ,2416,2416,2416
BEGIN DESCRIPTION:
SANDY FORK 35.0
END DESCRIPTION:
XS GIS Cut Line= 3
      2489374.97     13790724.97        2487575.       13788925.
      2486574.97     13788124.98
#Sta/Elev= 30
  2454.5  362.17  2624.2   356.1  2793.9  347.77  2949.4  337.53  3092.4  331.31
  3278.9  326.96  3465.6  325.01  3892.9  322.92  4028.4  322.01  4434.7  323.25
  4534.1   323.4  4745.3  319.49  4802.1  318.62  4858.6  312.81  4905.9  313.34
  4943.5  312.15  4944.4  302.53  4945.9  301.53  5027.3  302.53  5028.1  312.89
  5056.9  313.83  5100.1  320.87  5164.1  317.12  5298.7  317.16  5397.8  316.76
  5420.2  314.46  5455.1  316.21  5519.5  314.55  5938.9  317.06  6280.7  334.74
#Mann= 14 ,-1 , 0
  2454.5     .05       0  3092.4     .07       0  3278.9     .12       0
  3465.6     .07       0  3892.9    .035       0  4028.4     .05       0
  4434.7     .07       0  4534.1    .035       0  4745.3     .12       0
  4905.9      .1       0  4944.4     .05       0  5027.3      .1       0
  5298.7    .035       0  5455.1     .05       0
Bank Sta=4944.4,5027.3
XS Rating Curve= 0 ,0
Exp/Cntr=0.3,0.1

Type RM Length L Ch R = 1 ,66845   ,1352,1352,1352
BEGIN DESCRIPTION:
E20636
END DESCRIPTION:
XS GIS Cut Line= 3
      2489704.73     13789473.48      2488031.63     13787634.58
      2486420.57     13786279.48
#Sta/Elev= 30
  1401.8  339.81  1488.9  339.14  1588.7  336.96  1733.3  332.67  1867.8  332.45
  2122.6  324.05  2408.8  320.08  2611.1  319.31  2710.4  316.67  3198.3  318.59
  3297.6  321.75  3509.8  321.61  4339.9  313.62  4367.3  315.07  4574.1  315.65
  4666.4  310.81  4709.8  310.97    4751  313.93  4864.2  316.63  4886.2  311.35
    4950  309.38  4965.7  299.64  4967.2  298.64  5048.6  299.64  5048.8  319.29
  5121.8  322.29  5276.4  327.11  5340.2  327.22  5680.9  344.04  5993.1  352.01
#Mann= 8 ,-1 , 0
  1401.8     .07       0  1488.9     .05       0  1588.7     .07       0
  2408.8     .05       0  4709.8      .1       0  4965.7     .05       0
  5048.6      .1       0  5121.8     .07       0
Bank Sta=4965.7,5048.6
XS Rating Curve= 0 ,0
Exp/Cntr=0.3,0.1

Type RM Length L Ch R = 1 ,65493   ,969,969,969
BEGIN DESCRIPTION:
SANDY FORK 33.0
END DESCRIPTION:
XS GIS Cut Line= 3
        2489425.     13788875.01        2488425.       13786875.
      2487424.99     13785874.99
#Sta/Elev= 30
  2763.4  334.45  2826.2  334.28  3042.8  331.16  3161.2  326.36  3195.8  325.23
  3341.7  318.31    3465  313.59  3572.9  312.67  4342.6  317.07  4686.4  311.78
  4777.1  312.97  4806.6  312.52  4820.6  309.96  4851.3  313.36  4918.4   313.7
  4921.6  297.98  4923.1  296.98  5004.6  297.98  5013.6   309.4  5169.2  317.58
  5212.4  314.36  5367.2  315.02  5437.9  311.68  5508.6  314.93  5662.7  314.03
    5794  316.16  6017.7  327.54  6258.1  332.97  6397.2  339.84  6413.7  341.39
#Mann= 14 ,-1 , 0
  2763.4     .07       0  2826.2     .05       0  3042.8     .07       0
  3161.2     .05       0  3195.8     .07       0  3341.7     .12       0
  3572.9     .05       0  4777.1     .07       0  4921.6     .05       0
  5004.6     .07       0  5212.4     .12       0  5662.7     .05       0
    5794     .07       0  6397.2     .12       0
Bank Sta=4921.6,5004.6
XS Rating Curve= 0 ,0
Exp/Cntr=0.3,0.1

Type RM Length L Ch R = 1 ,64524   ,922,922,922
BEGIN DESCRIPTION:
SANDY FORK 32.0
END DESCRIPTION:
XS GIS Cut Line= 3
        2489375.     13788675.03        2489075.       13786275.
      2487275.03     13785275.02
#Sta/Elev= 30
  2585.2   335.5  2650.8  335.45  2766.6  332.29  2969.7  317.26  3108.8  312.02
  3895.5  311.45  4162.8  312.99  4293.7  312.61  4824.3  314.98  4872.9  315.98
  4953.5  308.57  4966.1  304.72  4970.4   297.5  4971.9   296.5  5053.4   297.5
  5061.1  315.63  5147.4  314.39  5188.6  313.48  5304.8  313.32  5358.5  309.67
  5402.1  312.26  5480.1  312.77  5615.7  313.18  5750.2  313.05  5932.3  315.51
  6276.8  319.43  6369.6  323.45  6571.1  330.82  6764.4  347.25    7063  371.52
#Mann= 20 ,-1 , 0
  2585.2     .05       0  2650.8     .07       0  2969.7     .05       0
  3108.8     .12       0  3895.5     .07       0  4162.8     .12       0
  4293.7     .05       0  4824.3      .1       0  4970.4     .05       0
  5053.4      .1       0  5147.4     .07       0  5188.6     .05       0
  5402.1     .05       0  5480.1     .12       0  5615.7     .05       0
  5750.2     .07       0  5932.3     .05       0  6276.8     .07       0
  6369.6     .05       0  6764.4     .07       0
Bank Sta=4970.4,5053.4
XS Rating Curve= 0 ,0
Exp/Cntr=0.3,0.1

Type RM Length L Ch R = 1 ,63602   ,1310,1310,1310
BEGIN DESCRIPTION:
E20635
END DESCRIPTION:
XS GIS Cut Line= 3
      2489719.78     13789081.53      2489900.65     13786006.72
      2488724.98      13783640.3
#Sta/Elev= 30
    2198  336.77  2505.1  338.49  2747.8  332.55  2945.7  321.98  3106.1  314.54
  3299.3  309.94  3336.8  310.82  3398.3  309.79  3496.7  310.88  3678.5  311.67
  4032.8  313.72  4268.1  315.72  4428.4  309.72  4874.7  312.41  4925.4   313.2
  4939.3   308.9  4947.8  297.86  4949.3  296.86  5030.8  297.86  5039.4  308.17
  5065.4  313.75  5268.4  312.06  5378.6  311.34  5403.7  310.87    5713  311.18
  6128.4  318.51  6660.5  318.21  6827.6  319.82    7747   341.2  7920.5  340.75
#Mann= 20 ,-1 , 0
    2198     .05       0  2747.8     .07       0  2945.7     .07       0
  3106.1     .05       0  3299.3     .12       0  3336.8     .07       0
  3398.3     .05       0  3496.7     .07       0  3678.5     .05       0
  4032.8     .05       0  4874.7     .12       0  4947.8     .05       0
  5030.8     .12       0  5065.4     .12       0  5268.4     .07       0
  5378.6     .12       0  5403.7     .07       0    5713     .05       0
  6660.5     .07       0  6827.6     .12       0
Bank Sta=4947.8,5030.8
XS Rating Curve= 0 ,0
Exp/Cntr=0.3,0.1

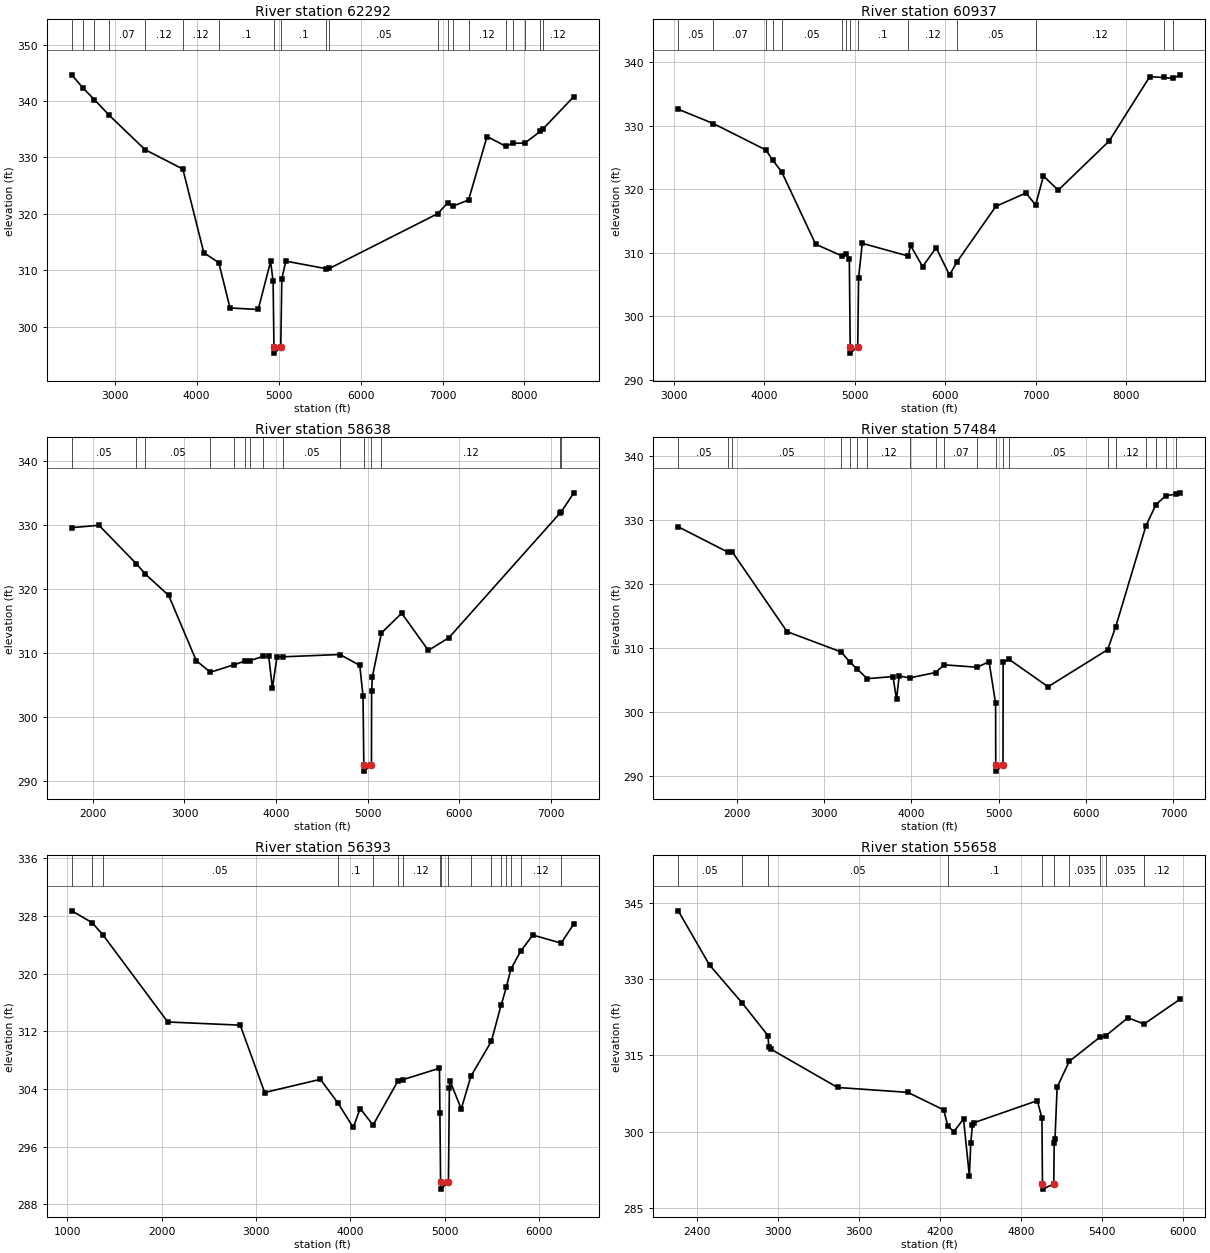
Type RM Length L Ch R = 1 ,62292   ,1355,1355,1355
BEGIN DESCRIPTION:
E20634
END DESCRIPTION:
XS GIS Cut Line= 3
      2491573.73     13789187.09      2490805.01      13786127.3
      2489629.85     13783400.31
#Sta/Elev= 30
  2477.8  344.65  2612.7  342.34  2752.7  340.26  2935.8  337.46  3371.5  331.38
  3832.5  327.94  4088.4   313.1  4271.3  311.33  4408.1   303.3  4751.9  303.03
    4903  311.55  4933.9     308  4943.9  296.29  4945.4  295.29    5027  296.29
  5039.9  308.45  5088.6  311.61    5582  310.26    5619   310.3  6943.2  320.04
  7061.9  321.93  7126.7  321.36  7317.9  322.45  7543.3  333.71  7769.3     332
  7857.5  332.51    8003  332.54  8191.4   334.6    8222     335  8602.1  340.79
#Mann= 20 ,-1 , 0
  2477.8     .12       0  2612.7     .07       0  2752.7     .12       0
  2935.8     .07       0  3371.5     .12       0  3832.5     .12       0
  4271.3      .1       0  4943.9     .05       0    5027      .1       0
    5582     .12       0    5619     .05       0  6943.2     .07       0
  7061.9     .05       0  7126.7     .07       0  7317.9     .12       0
  7769.3     .07       0  7857.5     .12       0    8003    .035       0
  8191.4     .07       0    8222     .12       0
Bank Sta=4943.9,5027
XS Rating Curve= 0 ,0
Exp/Cntr=0.3,0.1

Type RM Length L Ch R = 1 ,60937   ,2299,2299,2299
BEGIN DESCRIPTION:
E20633
END DESCRIPTION:
XS GIS Cut Line= 3
      2492327.36     13788478.66      2491845.03     13786142.37
      2490398.04     13783323.75
#Sta/Elev= 30
  3046.9  332.56  3435.6  330.31  4015.8  326.16    4090  324.59  4191.1  322.71
    4567  311.32  4859.2  309.47  4898.7  309.83  4939.6  309.01    4949  295.18
  4950.5  294.18  5032.4  295.18  5041.8  306.01  5082.6  311.46  5591.3  309.46
  5616.8  311.13  5749.9   307.8  5899.6  310.77  6047.7  306.46  6128.7   308.5
  6559.7  317.27  6892.5  319.38  7000.6  317.51  7086.6  322.05  7250.5  319.83
  7813.2  327.55  8262.2  337.68    8415  337.56  8520.2  337.42  8600.8  337.98
#Mann= 14 ,-1 , 0
  3046.9     .05       0  3435.6     .07       0  4015.8    .035       0
    4090     .07       0  4191.1     .05       0  4859.2     .07       0
  4898.7      .1       0    4949     .05       0  5032.4      .1       0
  5591.3     .12       0  6128.7     .05       0  7000.6     .12       0
    8415    .035       0  8520.2     .12       0
Bank Sta=4949,5032.4
XS Rating Curve= 0 ,0
Exp/Cntr=0.3,0.1

Type RM Length L Ch R = 1 ,58638   ,1154,1154,1154
BEGIN DESCRIPTION:
E20632
END DESCRIPTION:
XS GIS Cut Line= 3
      2492734.32     13787981.21      2492568.53     13785614.83
      2490940.68     13782962.04
#Sta/Elev= 30
  1768.8  329.56  2065.7  329.93  2475.4   323.9  2574.2  322.28  2827.4  318.97
  3128.3  308.79  3282.4  306.97  3544.6  308.15  3661.7  308.72    3716   308.8
  3859.4  309.44  3920.3  309.47  3960.4  304.48  4010.5   309.4  4075.1  309.38
  4698.9  309.74  4915.1  308.04  4950.3  303.24  4959.1  292.52  4960.6  291.52
  5042.5  292.52  5044.2  303.97    5053   306.3  5151.8  313.11  5372.7  316.19
    5664  310.38  5888.9  312.37    7100   331.8  7112.4  331.95  7253.4     335
#Mann= 15 ,-1 , 0
  1768.8     .05       0  2475.4    .035       0  2574.2     .05       0
  3282.4     .12       0  3544.6     .07       0  3661.7     .12       0
    3716     .07       0  3859.4     .12       0  4075.1     .05       0
  4698.9      .1       0  4959.1     .05       0  5042.5      .1       0
  5151.8     .12       0    7100    .035       0  7112.4     .12       0
Bank Sta=4959.1,5042.5
XS Rating Curve= 0 ,0
Exp/Cntr=0.3,0.1

Type RM Length L Ch R = 1 ,57484   ,1091,1091,1091
BEGIN DESCRIPTION:
E20631
END DESCRIPTION:
XS GIS Cut Line= 3
      2492869.98     13787755.18      2493231.73     13784770.75
      2491875.39     13782389.63
#Sta/Elev= 30
  1331.6  328.92  1905.8  324.92  1948.7  325.03  2577.1  312.56  3197.4  309.38
  3292.5  307.84  3381.2   306.7  3495.2  305.22  3789.6  305.55  3829.9  301.99
  3860.2  305.63  3982.5  305.34  4277.1  306.18  4374.9  307.38  4755.1     307
    4889  307.88  4963.9  301.37  4965.5  291.79    4967  290.79  5048.9  291.79
  5050.4  307.76  5114.4  308.27  5564.4  303.96  6246.2  309.74  6339.3  313.34
  6684.7  329.06  6799.8  332.39    6915   333.8  7030.1     334  7078.2  334.22
#Mann= 20 ,-1 , 0
  1331.6     .05       0  1905.8    .035       0  1948.7     .05       0
  3197.4     .05       0  3292.5     .12       0  3381.2     .05       0
  3495.2     .12       0  3982.5     .05       0  4277.1     .07       0
  4374.9     .07       0  4755.1      .1       0  4965.5     .05       0
  5048.9      .1       0  5114.4     .05       0  6246.2     .07       0
  6339.3     .12       0  6684.7    .035       0  6799.8     .12       0
    6915     .07       0  7030.1     .05       0
Bank Sta=4965.5,5048.9
XS Rating Curve= 0 ,0
Exp/Cntr=0.3,0.1

Type RM Length L Ch R = 1 ,56393   ,735,735,735
BEGIN DESCRIPTION:
E20630
END DESCRIPTION:
XS GIS Cut Line= 3
      2493035.78     13787498.95      2493834.64      13783911.6
      2493367.52     13782329.44
#Sta/Elev= 30
  1046.5  328.72    1263  327.07  1374.9  325.42  2064.8  313.29  2833.2  312.85
  3092.3   303.5  3683.3  305.33  3868.2  302.07  4031.8  298.65  4105.5  301.28
  4241.8  298.98  4507.2  305.13  4555.3  305.27  4946.2  306.87  4950.8  300.72
    4958  291.09  4959.5  290.09  5041.5  291.09  5051.3  304.17  5056.5  305.16
    5177  301.22  5280.3  305.78    5496  310.59  5599.5  315.61  5655.6  318.11
    5703  320.61  5806.5  323.09  5935.9  325.36  6236.3  324.24  6371.4   326.9
#Mann= 17 ,-1 , 0
  1046.5     .05       0    1263    .035       0  1374.9     .05       0
  3868.2      .1       0  4241.8     .12       0  4507.2      .1       0
  4555.3     .12       0  4950.8      .1       0    4958     .05       0
  5041.5      .1       0  5280.3     .05       0    5496     .07       0
  5599.5    .035       0  5655.6     .12       0    5703    .035       0
  5806.5     .12       0  6236.3     .05       0
Bank Sta=4958,5041.5
XS Rating Curve= 0 ,0
Exp/Cntr=0.3,0.1

Type RM Length L Ch R = 1 ,55658   ,1543,1543,1543
BEGIN DESCRIPTION:
SANDY FORK 29.0
END DESCRIPTION:
XS GIS Cut Line= 3
      2495703.66     13785720.33      2494256.68     13783112.75
        2493880.     13782479.93
#Sta/Elev= 30
    2261   343.4  2492.7  332.76  2732.4  325.37  2925.5  318.91  2932.1  316.57
  2948.1  316.22  3441.3  308.71    3962  307.75  4227.4   304.3  4257.7   301.1
  4302.8  300.05  4373.9  302.54  4417.4  291.32  4427.7  297.82    4440  301.36
  4455.2  301.83  4920.4  306.12  4954.7   302.7  4958.7  289.75  4960.2  288.75
  5042.2  289.75  5045.6  297.88  5051.4  298.57  5067.4  308.77  5156.7  313.83
  5383.5  318.58  5426.7  318.85    5592  322.41  5710.6  321.16  5979.6  326.08
#Mann= 10 ,-1 , 0
    2261     .05       0  2732.4    .035       0  2925.5     .05       0
  4257.7      .1       0  4958.7     .05       0  5042.2      .1       0
  5156.7    .035       0  5383.5     .05       0  5426.7    .035       0
  5710.6     .12       0
Bank Sta=4958.7,5042.2
XS Rating Curve= 0 ,0
Exp/Cntr=0.3,0.1

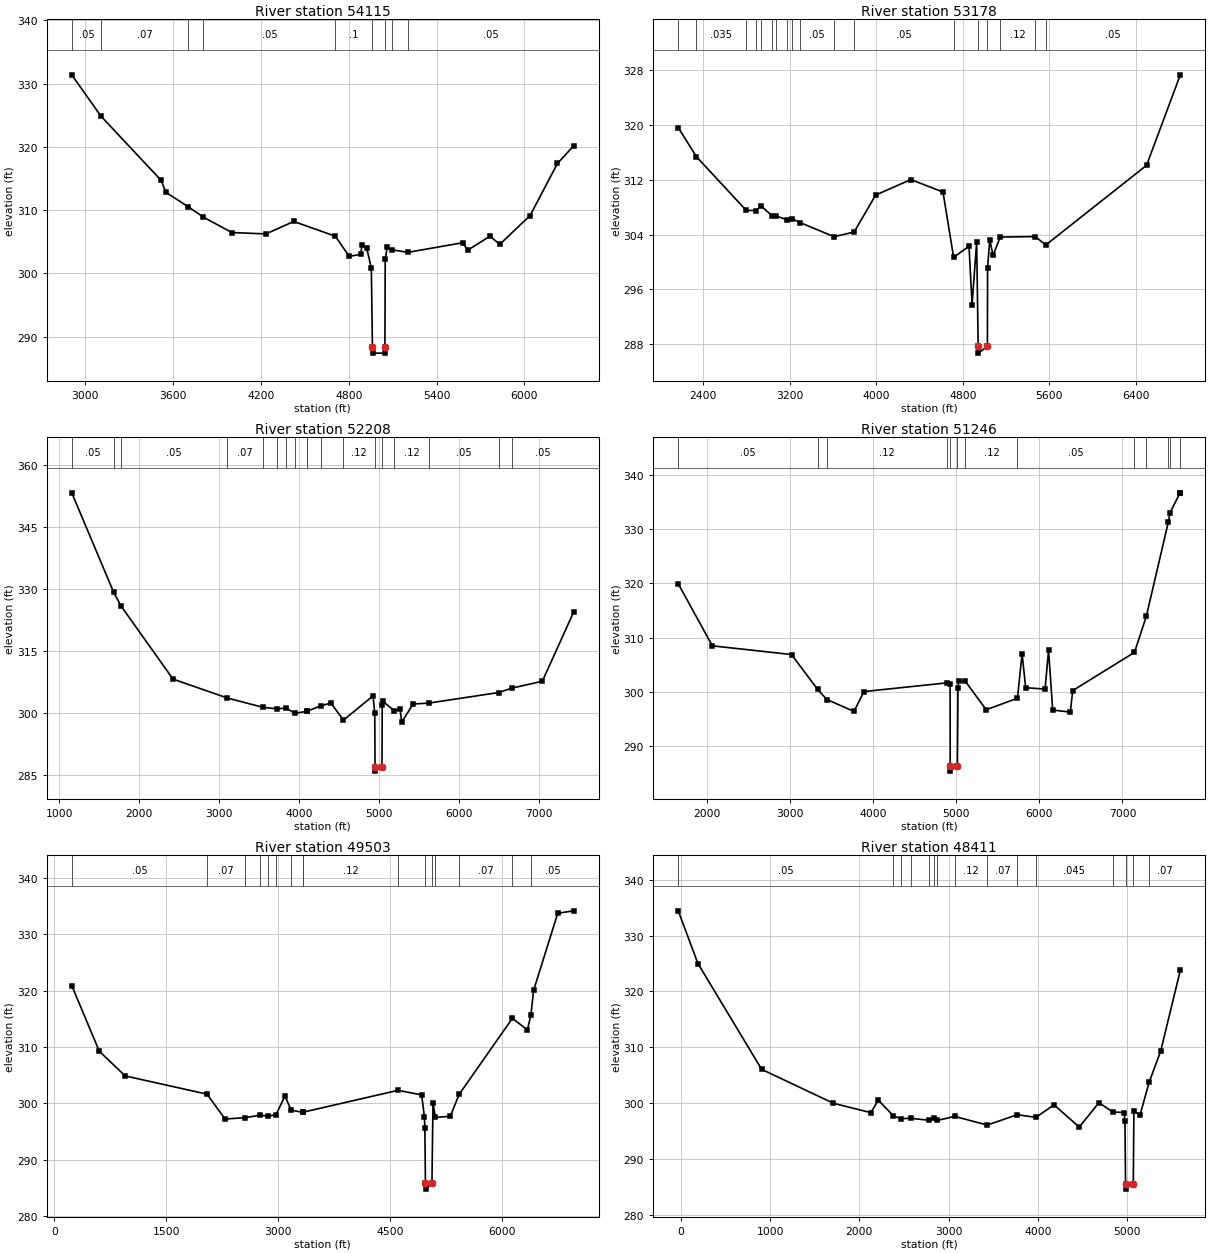
Type RM Length L Ch R = 1 ,54115   ,937,937,937
BEGIN DESCRIPTION:
SANDY FORK 28.0
END DESCRIPTION:
XS GIS Cut Line= 3
      2496125.01     13785275.04        2495525.       13783275.
      2494325.04     13782675.02
#Sta/Elev= 30
  2907.7   331.4  3107.1  324.86  3517.6  314.72  3550.7  312.81  3703.3  310.53
  3806.9  308.88  4001.4  306.45  4233.7  306.23  4424.2   308.2  4707.6  305.87
  4803.5  302.68    4881  302.99  4891.4  304.54  4922.7  303.99    4954  300.81
  4961.6  288.37  4963.1  287.37  5045.3  287.37  5046.8  288.37  5048.9  302.24
  5062.9  304.14  5096.1   303.7  5204.7  303.32  5577.2  304.83  5613.5  303.66
  5764.4  305.88  5831.5  304.58  6038.4  309.14  6225.6  317.38  6337.4   320.2
#Mann= 9 ,-1 , 0
  2907.7     .05       0  3107.1     .07       0  3703.3    .035       0
  3806.9     .05       0  4707.6      .1       0  4961.6     .05       0
  5046.8      .1       0  5096.1    .035       0  5204.7     .05       0
Bank Sta=4961.6,5046.8
XS Rating Curve= 0 ,0
Exp/Cntr=0.3,0.1

Type RM Length L Ch R = 1 ,53178   ,970,970,970
BEGIN DESCRIPTION:
SANDY FORK 27.0
END DESCRIPTION:
XS GIS Cut Line= 3
      2497924.98     13784474.98        2495925.       13782475.
      2494124.98       13782275.
#Sta/Elev= 30
  2171.3  319.64  2339.9  315.37  2799.5  307.54  2891.9  307.51    2935  308.22
  3035.1  306.79  3070.4  306.75  3178.3  306.16  3221.9  306.31  3297.4  305.76
  3610.8   303.7  3796.8  304.38  3995.6  309.78  4320.9  312.04  4617.9  310.22
    4716  300.68  4858.3   302.3  4886.6  293.77    4929  302.95  4942.9  287.69
  4944.4  286.69  5028.2  287.69  5029.9  299.12    5050  303.24  5080.2  300.98
  5146.6  303.64  5469.4  303.72  5568.2  302.49  6498.9  314.12  6810.8  327.34
#Mann= 18 ,-1 , 0
  2171.3     .05       0  2339.9    .035       0  2799.5     .12       0
  2891.9    .035       0    2935     .12       0  3035.1     .05       0
  3070.4     .12       0  3178.3     .05       0  3221.9     .07       0
  3297.4     .05       0  3610.8     .07       0  3796.8     .05       0
    4716      .1       0  4942.9     .05       0  5028.2      .1       0
  5146.6     .12       0  5469.4    .035       0  5568.2     .05       0
Bank Sta=4942.9,5028.2
XS Rating Curve= 0 ,0
Exp/Cntr=0.3,0.1

Type RM Length L Ch R = 1 ,52208   ,962,962,962
BEGIN DESCRIPTION:
SANDY FORK 26.0
END DESCRIPTION:
XS GIS Cut Line= 3
      2498775.02     13784675.02        2496375.       13781675.
      2494975.01     13779675.01
#Sta/Elev= 30
  1158.1   353.3  1682.5  329.24  1775.5  325.91  2425.1  308.26  3106.6  303.68
  3546.2  301.46  3732.2  301.06  3842.9  301.28  3948.6  299.97  4100.8  300.48
  4100.9  300.48  4282.4  301.85  4402.1  302.45  4557.7  298.34  4928.8  304.21
  4949.6  299.96  4953.5  287.01    4955  286.01  5040.2  287.01  5043.2  302.06
  5049.3   302.9  5193.6  300.63  5266.4  300.97  5287.3  297.87  5430.3  302.24
  5623.1  302.45  6501.2  305.02  6666.2  306.08  7046.8  307.74  7441.3  324.58
#Mann= 18 ,-1 , 0
  1158.1     .05       0  1682.5    .035       0  1775.5     .05       0
  3106.6     .07       0  3546.2     .05       0  3732.2     .07       0
  3842.9     .12       0  3948.6     .07       0  4100.8     .12       0
  4100.9     .07       0  4282.4      .1       0  4557.7     .12       0
  4953.5     .05       0  5040.2     .12       0  5193.6     .12       0
  5623.1     .05       0  6501.2    .035       0  6666.2     .05       0
Bank Sta=4953.5,5040.2
XS Rating Curve= 0 ,0
Exp/Cntr=0.3,0.1

Type RM Length L Ch R = 1 ,51246   ,1743,1743,1743
BEGIN DESCRIPTION:
SANDY FORK 25.0
END DESCRIPTION:
XS GIS Cut Line= 3
      2498475.01     13783975.02        2496975.       13780975.
      2495175.03     13778975.04
#Sta/Elev= 30
  1651.4  319.92  2062.3   308.5  3015.4   306.9  3328.1  300.51  3441.6  298.62
  3767.3  296.43  3887.5  300.09  4882.1  301.68  4924.5   301.5  4925.8  286.45
  4927.3  285.45  5012.5  286.45  5019.4  300.67  5026.8  302.03  5107.7  301.98
  5359.4  296.74  5735.4  298.86  5791.4  307.07    5834   300.8    6068  300.54
  6109.8  307.68  6159.9  296.69  6372.2  296.31  6400.6  300.27  7144.4   307.3
  7287.1  313.94  7552.2   331.3  7572.6  333.01  7692.6  336.63  7696.2  336.65
#Mann= 13 ,-1 , 0
  1651.4     .05       0  3328.1     .07       0  3441.6     .12       0
  4882.1      .1       0  4925.8     .05       0  5012.5      .1       0
  5107.7     .12       0  5735.4     .05       0  7144.4    .035       0
  7287.1     .05       0  7552.2    .035       0  7572.6     .05       0
  7692.6    .035       0
Bank Sta=4925.8,5012.5
XS Rating Curve= 0 ,0
Exp/Cntr=0.3,0.1

Type RM Length L Ch R = 1 ,49503   ,1092,1092,1092
BEGIN DESCRIPTION:
E20629
END DESCRIPTION:
XS GIS Cut Line= 3
      2498597.63     13783971.91      2497527.46     13779781.67
      2496231.19      13777761.9
#Sta/Elev= 30
   234.6  320.88     603  309.23   950.6  304.84  2046.1  301.61  2288.2  297.19
  2559.9  297.44  2758.8  297.88  2858.7  297.71  2969.2  297.93  3089.7  301.29
  3173.9  298.75    3327  298.39  3327.7  298.39  4605.2  302.29  4921.4  301.47
  4957.7  297.59  4963.6  295.67  4971.7  285.75  4973.2  284.75  5058.6  285.75
  5072.7  300.04  5104.9  297.49    5304  297.67  5423.1  301.57  6135.6  315.06
  6337.8  313.02  6384.8  315.74  6419.8  320.01  6743.5  333.72  6959.3  334.15
#Mann= 16 ,-1 , 0
   234.6     .05       0  2046.1     .07       0  2559.9     .05       0
  2758.8     .07       0  2858.7     .12       0  2969.2     .07       0
  3173.9     .12       0    3327     .07       0  3327.7     .12       0
  4605.2      .1       0  4971.7     .05       0  5058.6      .1       0
  5104.9     .12       0  5423.1     .07       0  6135.6     .12       0
  6384.8     .05       0
Bank Sta=4971.7,5058.6
XS Rating Curve= 0 ,0
Exp/Cntr=0.3,0.1

Type RM Length L Ch R = 1 ,48411   ,944,944,944
BEGIN DESCRIPTION:
SANDY FORK 24.0
END DESCRIPTION:
XS GIS Cut Line= 3
        2498725.     13784325.02        2498225.       13779325.
        2498225.     13778724.96
#Sta/Elev= 30
     -30  334.43   191.1  324.98   904.7  306.05  1708.7  299.98  2128.2   298.3
  2211.1  300.54  2381.3  297.72  2463.8  297.23  2576.5  297.28  2778.8  296.94
  2838.8  297.35  2874.1  296.91  3066.8  297.63  3431.9  296.08  3769.9  297.94
  3975.1  297.45  4180.9   299.7  4462.3  295.71  4683.4  300.08  4839.4  298.42
  4964.8  298.32  4974.9  296.83  4981.5  285.61    4983  284.61  5068.4  285.61
    5075  298.52    5145  297.94  5246.2  303.77    5375  309.31    5595  323.79
#Mann= 15 ,-1 , 0
     -30     .05       0  2381.3     .12       0  2463.8     .05       0
  2576.5     .12       0  2778.8    .035       0  2838.8     .12       0
  2874.1     .07       0  3066.8     .12       0  3431.9     .07       0
  3769.9     .05       0  3975.1    .045       0  4839.4     .12       0
  4981.5     .05       0  5068.4    .045       0  5246.2     .07       0
Bank Sta=4981.5,5068.4
XS Rating Curve= 0 ,0
Exp/Cntr=0.3,0.1

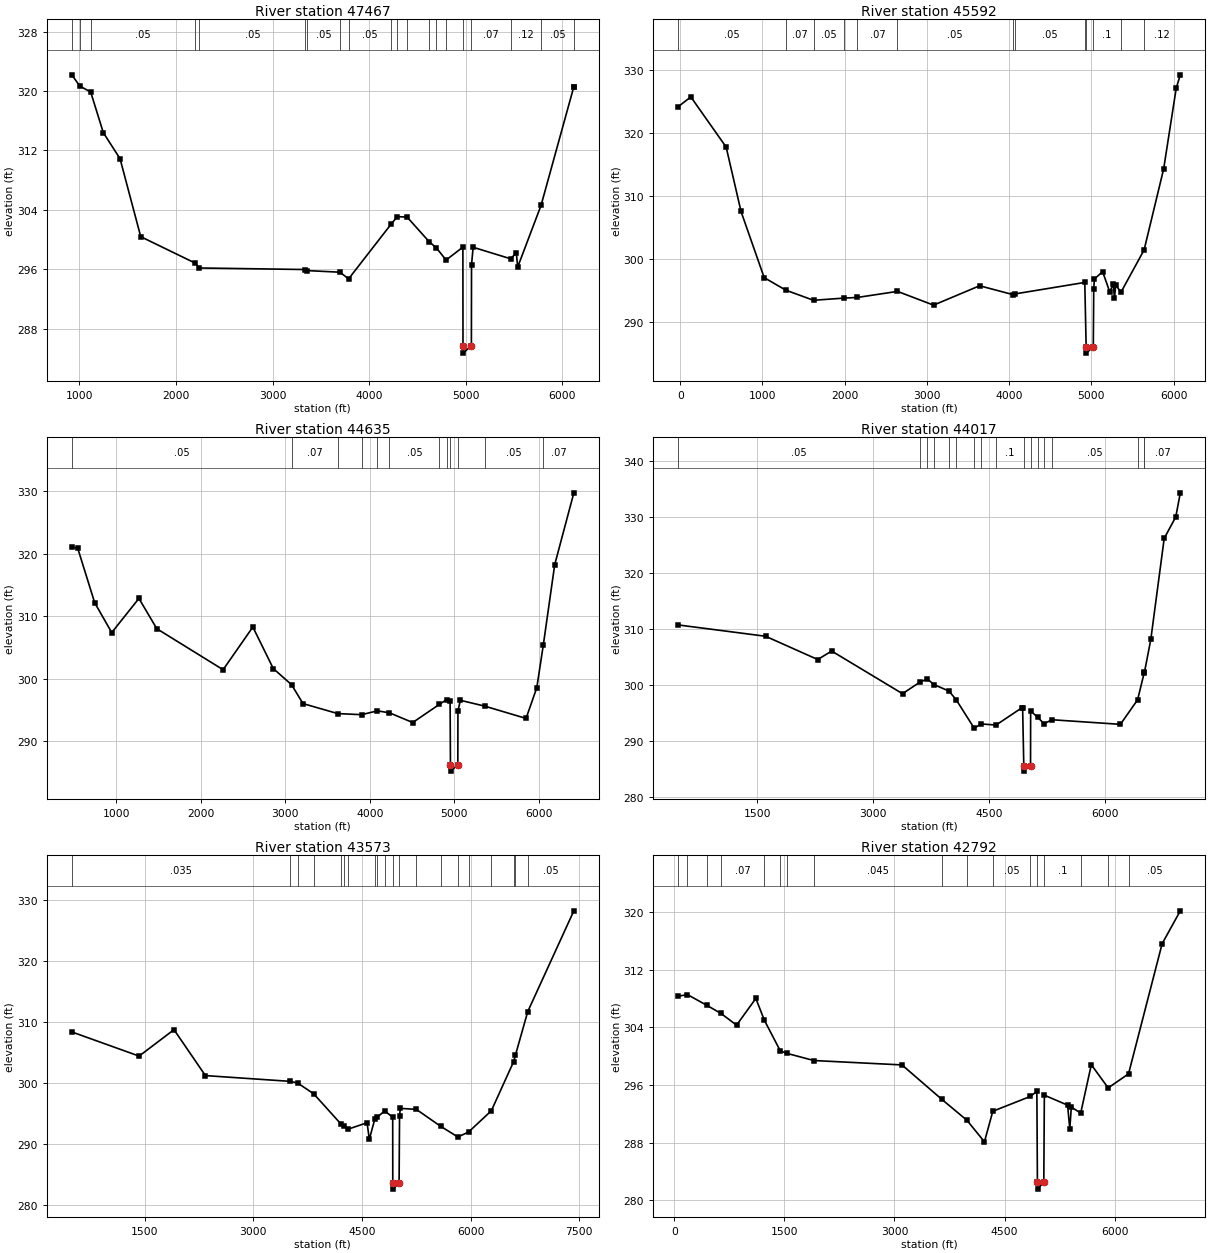
Type RM Length L Ch R = 1 ,47467   ,1875,1875,1875
BEGIN DESCRIPTION:
SANDY FORK 23.0
END DESCRIPTION:
XS GIS Cut Line= 3
      2499775.01     13783775.04        2498975.       13779775.
        2498475.     13778774.99
#Sta/Elev= 30
   921.2   322.2  1004.9  320.68  1117.1  319.88  1247.6  314.41  1420.9  310.89
  1635.1  300.38  2201.2   296.8  2240.9  296.16  3339.6  295.95  3354.1  295.81
  3697.4  295.59  3786.7  294.69  4230.5  302.13  4291.4  303.08  4392.4  303.02
  4619.6  299.72  4695.2  298.87  4796.1  297.23  4969.9  298.97    4971  285.68
  4972.5  284.68  5057.9  285.68  5059.2  296.56  5075.9  298.95  5464.2   297.4
  5523.1  298.21  5537.1  296.28  5779.1   304.6  6117.5  320.56  6118.5  320.56
#Mann= 20 ,-1 , 0
   921.2     .05       0  1004.9     .07       0  1117.1     .05       0
  2201.2     .07       0  2240.9     .05       0  3339.6     .12       0
  3354.1     .05       0  3697.4    .035       0  3786.7     .05       0
  4230.5     .07       0  4291.4     .05       0  4392.4    .035       0
  4619.6     .07       0  4695.2    .035       0  4796.1     .07       0
    4971    .045       0  5057.9     .07       0  5464.2     .12       0
  5779.1     .05       0  6117.5     .07       0
Bank Sta=4971,5057.9
XS Rating Curve= 0 ,0
Exp/Cntr=0.3,0.1

Type RM Length L Ch R = 1 ,45592   ,957,957,957
BEGIN DESCRIPTION:
SANDY FORK 22.0
END DESCRIPTION:
XS GIS Cut Line= 3
        2499925.     13784024.98        2500425.       13779025.
      2499824.99     13778124.99
#Sta/Elev= 30
   -24.6  324.22   128.6  325.77   558.3  317.81   739.2   307.6  1020.6  297.11
  1284.6  295.12  1620.6  293.52  1985.8  293.86    2155  293.97  2641.9  294.93
  3080.8  292.75  3641.1  295.82  4043.3  294.43  4076.4  294.54  4920.2  296.35
  4936.7  286.14  4938.2  285.14  5023.7  286.14  5028.9  295.25  5036.4  296.87
    5137  298.07  5224.2  294.83  5266.2   296.1  5281.3  293.88  5296.3  295.94
  5360.4   294.8  5641.8  301.51  5879.2  314.34  6032.4  327.16    6082  329.27
#Mann= 13 ,-1 , 0
   -24.6     .05       0  1284.6     .07       0  1620.6     .05       0
  1985.8     .12       0    2155     .07       0  2641.9     .05       0
  4043.3    .035       0  4076.4     .05       0  4920.2      .1       0
  4936.7     .05       0  5023.7      .1       0  5360.4     .05       0
  5641.8     .12       0
Bank Sta=4936.7,5023.7
XS Rating Curve= 0 ,0
Exp/Cntr=0.3,0.1

Type RM Length L Ch R = 1 ,44635   ,618,618,618
BEGIN DESCRIPTION:
SANDY FORK 21.0
END DESCRIPTION:
XS GIS Cut Line= 3
        2500775.     13783474.98        2501275.       13778975.
      2500274.99     13777974.99
#Sta/Elev= 30
   472.9  321.05   543.3  320.88   744.5  312.15   945.8  307.39  1267.7  312.85
    1479  308.01  2263.8  301.45    2616  308.28  2857.5  301.64    3074  299.05
  3209.6  296.03  3621.2  294.43  3903.8  294.26    4089  294.87  4232.8  294.56
  4507.6     293  4821.6  295.89  4910.3  296.68  4950.3  296.49  4954.5  286.23
    4956  285.23  5041.7  286.23    5043   294.8  5071.3  296.56  5361.4  295.62
  5849.1  293.66  5976.4  298.58  6054.3  305.48  6188.5  318.26  6414.8  329.74
#Mann= 12 ,-1 , 0
   472.9     .05       0    3074     .07       0  3621.2     .12       0
  3903.8     .05       0    4089    .035       0  4232.8     .05       0
  4821.6     .07       0  4910.3     .05       0  4954.5     .05       0
  5041.7     .05       0  5361.4     .05       0  6054.3     .07       0
Bank Sta=4954.5,5041.7
XS Rating Curve= 0 ,0
Exp/Cntr=0.3,0.1

Type RM Length L Ch R = 1 ,44017   ,444,444,444
BEGIN DESCRIPTION:
E20628
END DESCRIPTION:
XS GIS Cut Line= 4
      2501446.38     13783157.98      2501883.49     13779012.96
      2501642.33     13778229.17       2501024.9     13776858.79
#Sta/Elev= 30
   481.3  310.78  1610.5  308.76  2284.2  304.61  2465.2  306.12  3380.9  298.51
  3603.2  300.55  3701.8  301.15  3785.7  300.14  3980.4  298.99    4073  297.47
    4309  292.32  4392.6  293.12  4589.9  292.91  4928.8  296.04    4934  295.87
  4948.8  285.69  4950.3  284.69    5036  285.69  5037.4  295.44  5129.8  294.28
  5210.1  293.16    5314  293.86  6197.8  293.04  6419.9  297.41  6505.1  302.22
  6508.6  302.32    6591   308.2    6764  326.22  6913.8  330.07  6972.4  334.36
#Mann= 17 ,-1 , 0
   481.3     .05       0  3603.2    .035       0  3701.8     .05       0
  3785.7     .07       0  3980.4     .05       0    4073     .07       0
    4309     .05       0  4392.6     .07       0  4589.9      .1       0
  4948.8     .05       0    5036      .1       0  5129.8     .05       0
  5210.1      .1       0    5314     .05       0  6419.9     .07       0
  6505.1    .033       0  6508.6     .07       0
Bank Sta=4948.8,5036
XS Rating Curve= 0 ,0
Exp/Cntr=0.3,0.1

Type RM Length L Ch R = 1 ,43573   ,781,781,781
BEGIN DESCRIPTION:
E20627
END DESCRIPTION:
XS GIS Cut Line= 4
      2502109.58     13782871.63      2502380.89      13779766.6
      2501943.78     13777686.55      2501687.55      13776013.5
#Sta/Elev= 30
   491.9  308.36  1422.1  304.39  1903.9  308.73  2337.7  301.19  3511.6  300.24
  3610.9  299.98  3833.5   298.2    4207  293.28  4255.6   292.9  4308.1  292.39
  4570.9  293.45  4601.6  290.72  4677.6  294.05  4712.8  294.38    4814  295.39
  4924.7  294.35  4925.8  283.55  4927.3  282.55    5013  283.55  5019.3  294.63
  5030.8  295.81  5251.2  295.64  5586.5  292.87  5824.7  291.11  5971.8  291.92
    6287  295.41  6595.8   303.5    6619   304.5  6789.7  311.69  7426.8  328.24
#Mann= 20 ,-1 , 0
   491.9    .035       0  3511.6    .045       0  3610.9    .035       0
  3833.5     .05       0    4207     .07       0  4255.6    .094       0
  4308.1     .12       0  4677.6    .063       0  4712.8      .1       0
    4814    .035       0  4925.8     .05       0    5013      .1       0
  5251.2     .05       0  5586.5    .035       0  5824.7     .07       0
  5971.8     .12       0    6287     .07       0  6595.8     .12       0
    6619     .07       0  6789.7     .05       0
Bank Sta=4925.8,5013
XS Rating Curve= 0 ,0
Exp/Cntr=0.3,0.1

Type RM Length L Ch R = 1 ,42792   ,1727,1727,1727
BEGIN DESCRIPTION:
E20626
END DESCRIPTION:
XS GIS Cut Line= 3
      2502260.31     13782720.85       2502983.8     13779465.14
      2502290.61      13776029.3
#Sta/Elev= 30
    53.8  308.33   178.2  308.57   445.7  307.06   637.2  305.94   848.6  304.32
  1111.2  308.03  1227.3     305  1444.3  300.75  1533.1  300.41  1901.2  299.41
  3102.2   298.8  3641.6  294.05  3986.6  291.12  4225.6  288.13  4339.4  292.37
  4848.9  294.42  4939.7  295.12  4947.1  282.56  4948.6  281.56  5034.3  282.56
  5041.7   294.6    5358  293.22  5388.6  289.89    5409  292.94    5537  292.12
  5681.4  298.83  5911.1  295.61  6188.5  297.56  6646.4  315.63    6894  320.19
#Mann= 17 ,-1 , 0
    53.8    .035       0   178.2     .07       0   445.7    .035       0
   637.2     .07       0  1227.3    .035       0  1444.3     .05       0
  1533.1    .035       0  1901.2    .045       0  3641.6     .05       0
  3986.6     .12       0  4339.4     .05       0  4848.9      .1       0
  4947.1     .05       0  5034.3      .1       0    5537     .05       0
  5911.1     .07       0  6188.5     .05       0
Bank Sta=4947.1,5034.3
XS Rating Curve= 0 ,0
Exp/Cntr=0.3,0.1