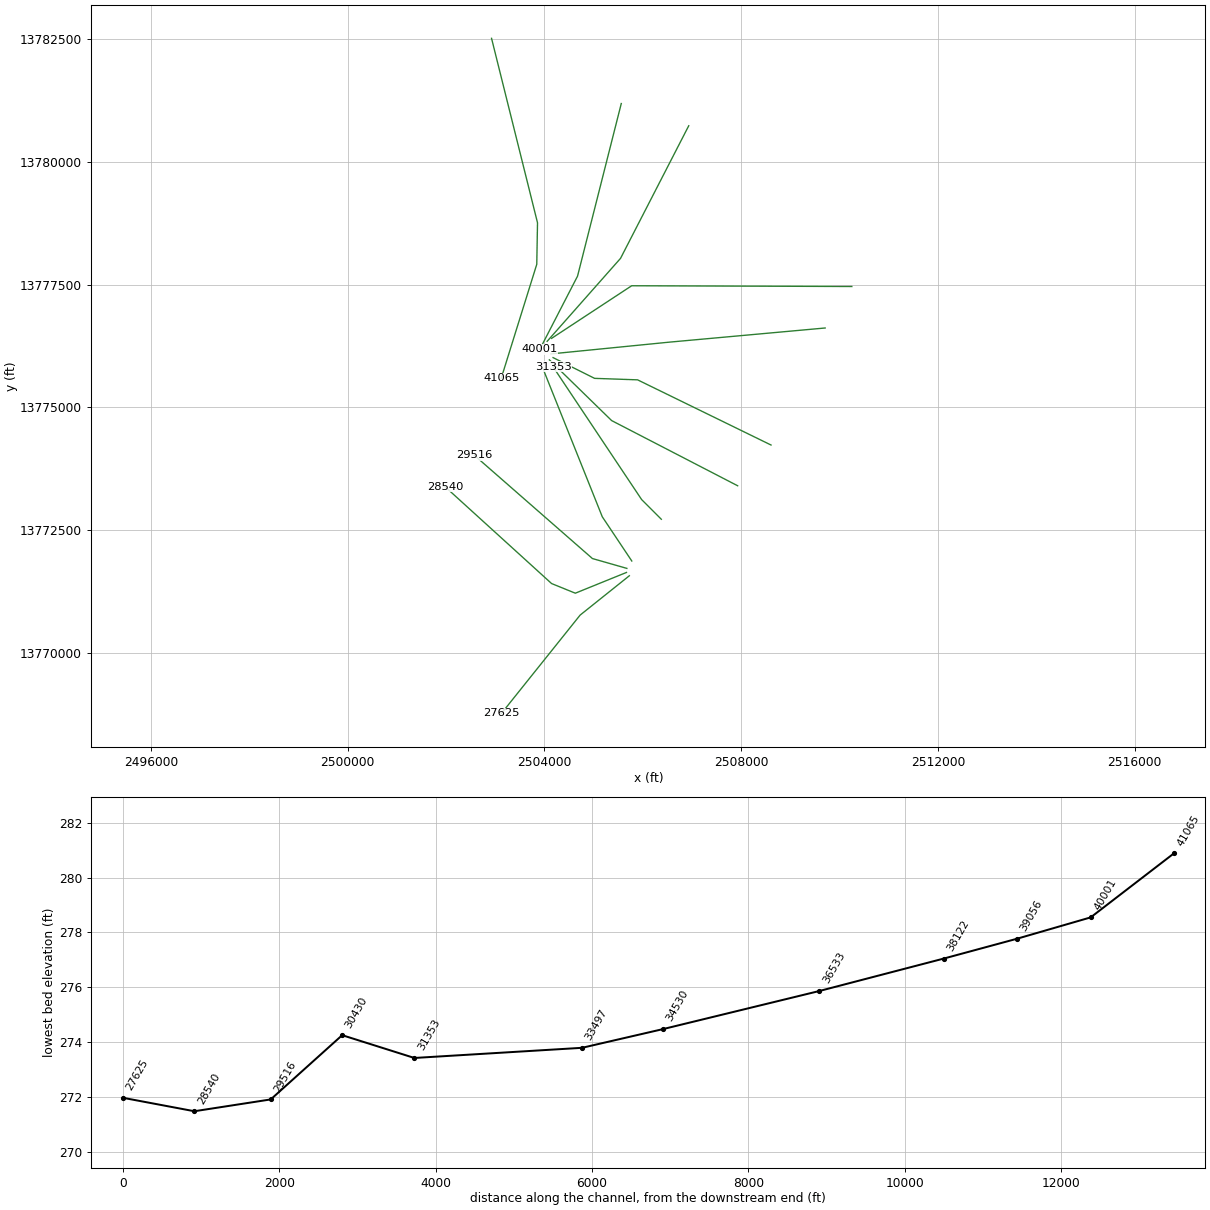
HEC-RAS study SANDY FORK.prj: SANDY FORK Base Level Engineering

--- SANDY FORK.g01 (geometry) --- (continued)

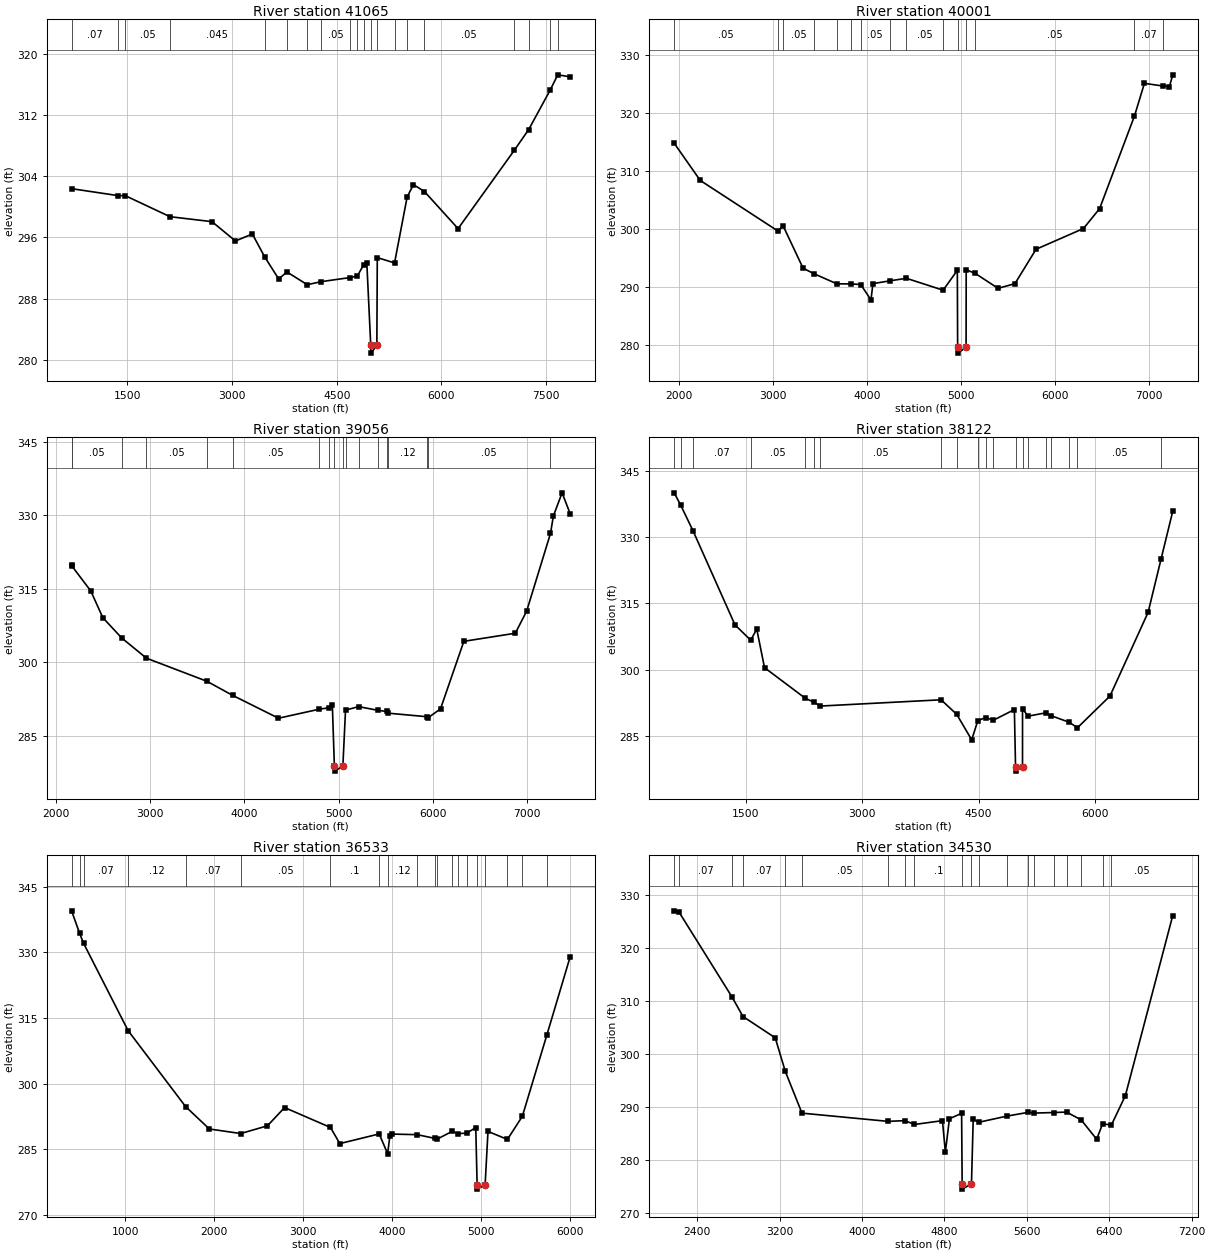
Type RM Length L Ch R = 1 ,41065   ,1064,1064,1064
BEGIN DESCRIPTION:
E20625
END DESCRIPTION:
XS GIS Cut Line= 4
      2502923.51     13782509.85      2503858.02     13778756.72
      2503842.95     13777912.65      2503119.72     13775592.28
#Sta/Elev= 30
   700.9  302.36  1368.5  301.45  1469.3  301.45  2110.6   298.7  2712.3  298.05
  3047.9  295.53  3290.6  296.44  3467.8  293.44  3667.5  290.57  3785.8  291.48
  4076.9  289.82  4279.9  290.22  4682.3  290.74  4793.3  290.93  4882.9  292.38
  4930.4  292.64  4986.8  281.88  4988.3  280.88  5074.1  281.88  5080.4  293.36
  5327.6  292.66  5508.2  301.28  5598.9  302.89  5755.5  301.99  6237.9  297.14
  7041.3  307.35  7249.3  310.08  7561.4  315.31  7665.4  317.23  7843.3  316.97
#Mann= 20 ,-1 , 0
   700.9     .07       0  1368.5    .035       0  1469.3     .05       0
  2110.6    .045       0  3467.8    .045       0  3785.8     .07       0
  4076.9     .07       0  4279.9     .05       0  4682.3     .07       0
  4793.3     .05       0  4882.9     .07       0  4986.8     .05       0
  5074.1     .07       0  5327.6     .05       0  5508.2    .035       0
  5755.5     .05       0  7041.3    .035       0  7249.3     .07       0
  7561.4    .035       0  7665.4     .07       0
Bank Sta=4986.8,5074.1
XS Rating Curve= 0 ,0
Exp/Cntr=0.3,0.1

Type RM Length L Ch R = 1 ,40001   ,945,945,945
BEGIN DESCRIPTION:
E20624
END DESCRIPTION:
XS GIS Cut Line= 3
      2505561.25     13781183.47      2504671.95     13777671.48
      2503903.42     13776179.63
#Sta/Elev= 30
  1948.6  314.77  2225.5  308.35  3048.5  299.65  3108.3  300.46    3319  293.21
  3434.7  292.25  3678.3  290.51  3829.8  290.49    3932  290.39  4041.1  287.73
  4061.7  290.54  4240.3  291.02  4417.6  291.46  4808.1  289.41  4959.2  292.83
  4962.4  279.55  4963.9  278.55  5052.3  279.55  5053.5  292.93  5150.2   292.3
  5392.4  289.73  5571.4  290.53  5796.1  296.47  6300.3  300.05    6472  303.48
  6842.8  319.47  6948.4   325.1  7140.9  324.65  7214.4  324.54  7249.6  326.57
#Mann= 15 ,-1 , 0
  1948.6     .05       0  3048.5     .07       0  3108.3     .05       0
  3434.7     .07       0  3678.3     .05       0  3829.8    .035       0
    3932     .05       0  4240.3     .07       0  4417.6     .05       0
  4808.1      .1       0  4962.4     .05       0  5052.3      .1       0
  5150.2     .05       0  6842.8     .07       0  7140.9     .05       0
Bank Sta=4962.4,5052.3
XS Rating Curve= 0 ,0
Exp/Cntr=0.3,0.1

Type RM Length L Ch R = 1 ,39056   ,934,934,934
BEGIN DESCRIPTION:
E20623
END DESCRIPTION:
XS GIS Cut Line= 3
      2506932.88     13780731.28      2505546.17     13778033.23
      2504053.95     13776345.06
#Sta/Elev= 30
    2167  319.98  2173.5  319.59  2370.5  314.58    2498  309.13  2697.7  304.99
  2960.1  300.85  3602.9  296.12  3874.5  293.25  4360.9  288.58  4795.5  290.43
    4892   290.7    4932   291.3  4953.6  278.77  4955.1  277.77  5043.5  278.77
  5071.8  290.23  5210.2  290.95  5415.1  290.19  5507.9  289.96  5523.8  289.61
  5933.3  288.89  5944.2  288.63    6079  290.49  6326.6  304.29    6872  305.94
  6992.4  310.46  7245.1  326.33    7276   329.9    7368  334.63  7453.7  330.37
#Mann= 18 ,-1 , 0
    2167    .035       0  2173.5     .05       0  2697.7     .07       0
  2960.1     .05       0  3602.9    .035       0  3874.5     .05       0
  4795.5     .12       0    4892      .1       0  4953.6     .05       0
  5043.5      .1       0  5071.8     .12       0  5210.2     .05       0
  5415.1     .12       0  5507.9     .05       0  5523.8     .12       0
  5933.3     .07       0  5944.2     .05       0  7245.1     .07       0
Bank Sta=4953.6,5043.5
XS Rating Curve= 0 ,0
Exp/Cntr=0.3,0.1

Type RM Length L Ch R = 1 ,38122   ,1589,1589,1589
BEGIN DESCRIPTION:
SANDY FORK 20.0
END DESCRIPTION:
XS GIS Cut Line= 3
      2510248.86     13777460.46      2505772.26     13777475.54
      2504144.44     13776405.39
#Sta/Elev= 30
   576.2  340.01   662.3  337.15   821.7  331.31  1360.1  310.13  1562.5  306.67
  1640.1  309.18  1740.1  300.46  2265.9  293.53  2381.2  292.61  2459.8  291.77
  4015.3  293.19  4217.3  289.89  4410.1  284.13  4489.3  288.48  4591.2  289.17
  4689.6  288.57  4960.1  290.97  4975.1  278.05  4976.6  277.05    5065  278.05
  5065.2  291.13  5136.8  289.49    5364  290.23  5436.1  289.57  5667.5   288.1
  5772.7  286.86    6192  294.04  6683.1  312.95  6852.1  325.15  7000.9  335.83
#Mann= 20 ,-1 , 0
   576.2     .07       0   662.3     .12       0   821.7     .07       0
  1562.5     .05       0  2265.9     .05       0  2381.2     .07       0
  2459.8     .05       0  4015.3     .07       0  4217.3     .12       0
  4489.3     .07       0  4591.2     .12       0  4689.6      .1       0
  4975.1     .05       0    5065      .1       0  5136.8      .1       0
    5364     .07       0  5436.1     .05       0  5667.5     .07       0
  5772.7     .05       0  6852.1     .07       0
Bank Sta=4975.1,5065
XS Rating Curve= 0 ,0
Exp/Cntr=0.3,0.1

Type RM Length L Ch R = 1 ,36533   ,2003,2003,2003
BEGIN DESCRIPTION:
SANDY FORK 19.0
END DESCRIPTION:
XS GIS Cut Line= 3
      2509706.23     13776616.39      2506556.05     13776330.01
      2504129.67     13776088.88
#Sta/Elev= 30
   398.6   339.5   488.8  334.34   534.5  332.03  1033.1  312.12  1678.8  294.76
  1946.2  289.62  2299.3  288.58  2598.9  290.35  2791.7  294.52  3307.2  289.97
  3412.2  286.28  3854.5  288.49  3949.6  283.97  3974.8  288.11  3994.9  288.46
  4282.5  288.32  4480.7  287.47  4509.1  287.34  4672.4  289.05  4740.4  288.56
    4839  288.67  4939.6  289.95  4954.9  276.87  4956.4  275.87  5044.8  276.87
  5076.9  289.07  5295.3  287.23  5462.9  292.52    5740  311.22  6000.1  328.98
#Mann= 20 ,-1 , 0
   398.6     .07       0   488.8     .12       0   534.5     .07       0
  1033.1     .12       0  1678.8     .07       0  2299.3     .05       0
  3307.2      .1       0  3854.5      .1       0  3949.6     .12       0
  4282.5     .05       0  4480.7      .1       0  4509.1     .05       0
  4672.4      .1       0  4740.4     .05       0    4839      .1       0
  4954.9     .05       0  5044.8      .1       0  5295.3     .05       0
  5462.9     .07       0    5740     .05       0
Bank Sta=4954.9,5044.8
XS Rating Curve= 0 ,0
Exp/Cntr=0.3,0.1

Type RM Length L Ch R = 1 ,34530   ,1033,1033,1033
BEGIN DESCRIPTION:
E20622
END DESCRIPTION:
XS GIS Cut Line= 4
      2508605.93      13774234.9      2505892.84      13775561.3
      2505018.63     13775591.44      2504174.56     13776013.48
#Sta/Elev= 30
  2177.4  327.04  2222.5  326.86  2739.5  310.74    2845  307.08    3158  303.06
  3255.4  296.73  3417.6  288.83    4251  287.28    4418  287.41  4508.5  286.69
  4781.1  287.41  4809.1  281.47  4848.6  287.77  4966.8   288.8  4972.1  275.48
  4973.6  274.48  5062.5  275.48  5079.3  287.66  5138.8  287.13  5404.1  288.26
  5607.6  288.96  5670.8  288.84  5863.4  288.95  5985.2  289.03  6127.1  287.56
  6277.4   283.9  6335.4  286.82  6420.4  286.58  6556.1  292.14  7015.8  326.15
#Mann= 20 ,-1 , 0
  2177.4     .05       0  2222.5     .07       0  2739.5     .12       0
    2845     .07       0  3255.4    .035       0  3417.6     .05       0
    4251     .12       0    4418     .05       0  4508.5      .1       0
  4972.1     .05       0  5062.5      .1       0  5138.8     .12       0
  5404.1      .1       0  5607.6     .12       0  5670.8      .1       0
  5863.4      .1       0  5985.2    .035       0  6127.1    .035       0
  6335.4      .1       0  6420.4     .05       0
Bank Sta=4972.1,5062.5
XS Rating Curve= 0 ,0
Exp/Cntr=0.3,0.1

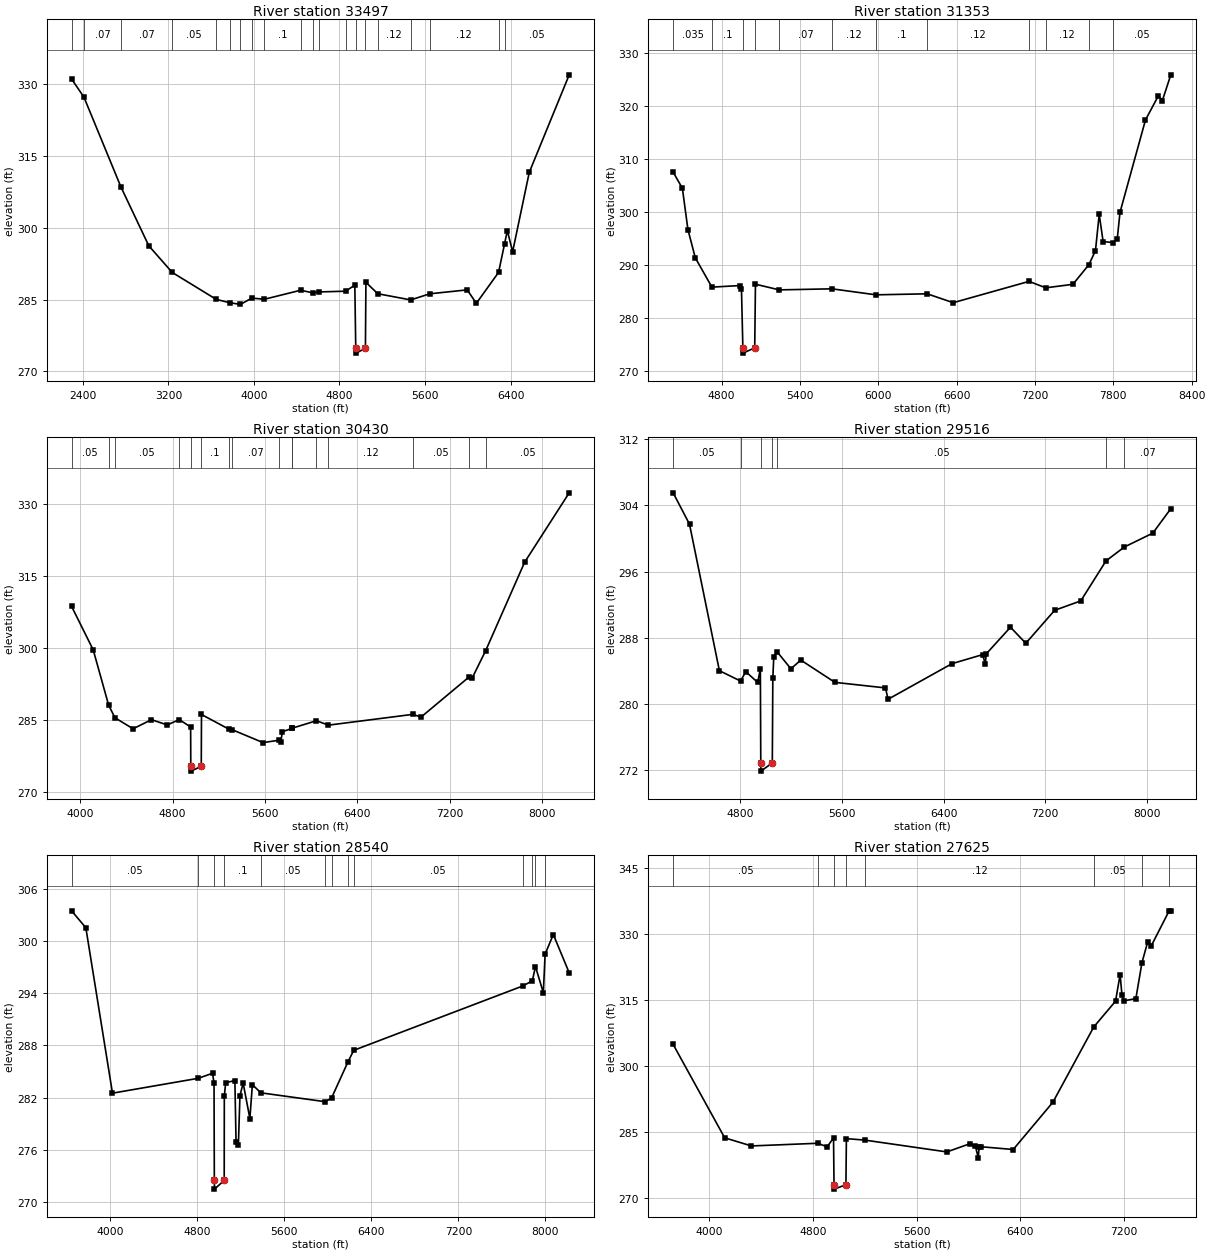
Type RM Length L Ch R = 1 ,33497   ,2144,2144,2144
BEGIN DESCRIPTION:
E20621
END DESCRIPTION:
XS GIS Cut Line= 3
      2507927.64     13773405.91       2505365.3     13774732.29
      2504099.58     13775967.87
#Sta/Elev= 30
  2294.3   331.1  2410.5  327.28  2755.8  308.54  3016.7  296.23    3236  290.66
  3648.3  285.02    3777  284.33  3873.4  283.98  3980.1   285.3  4098.5  285.06
  4436.1  286.94  4548.6  286.41  4610.5  286.59  4856.6  286.74  4943.5     288
  4952.2   274.8  4953.7   273.8  5042.6   274.8  5047.3  288.59  5158.5  286.21
  5466.1  284.92  5644.5   286.2  5994.9  287.02  6079.8   284.2  6287.7  290.67
  6344.5   296.7  6369.7  299.41  6419.3  294.99  6574.9  311.58  6948.4  331.96
#Mann= 20 ,-1 , 0
  2294.3    .035       0  2410.5     .07       0  2755.8     .07       0
    3236     .05       0  3648.3    .035       0    3777    .035       0
  3873.4     .07       0  3980.1    .035       0  4098.5      .1       0
  4436.1     .07       0  4548.6      .1       0  4610.5     .07       0
  4856.6      .1       0  4952.2     .05       0  5042.6      .1       0
  5158.5     .12       0  5466.1    .035       0  5644.5     .12       0
  6287.7     .07       0  6344.5     .05       0
Bank Sta=4952.2,5042.6
XS Rating Curve= 0 ,0
Exp/Cntr=0.3,0.1

Type RM Length L Ch R = 1 ,31353   ,923,923,923
BEGIN DESCRIPTION:
SANDY FORK 18.0
END DESCRIPTION:
XS GIS Cut Line= 3
      2506374.97     13772725.03        2505975.       13773125.
      2504175.02     13775824.96
#Sta/Elev= 30
  4429.7  307.52  4500.4  304.47  4542.8   296.7  4599.4  291.37  4726.4  285.86
  4938.8  286.15  4952.9  285.43  4963.5  274.43    4965  273.43  5054.3  274.43
  5059.9  286.41  5242.4  285.34  5645.2  285.54  5983.2  284.41  6374.6   284.6
  6574.3  282.93  7154.6  286.94    7283  285.73  7490.7  286.39  7613.6   290.1
  7663.5  292.75    7692  299.57    7722  294.45    7799  294.24  7830.2  294.94
  7851.2  299.94  8046.5  317.35  8145.7  321.92  8175.7  320.99  8240.3  325.84
#Mann= 12 ,-1 , 0
  4429.7    .035       0  4726.4      .1       0  4963.5     .05       0
  5054.3      .1       0  5242.4     .07       0  5645.2     .12       0
  5983.2      .1       0  6374.6     .12       0  7154.6    .035       0
    7283     .12       0  7613.6     .07       0    7799     .05       0
Bank Sta=4963.5,5054.3
XS Rating Curve= 0 ,0
Exp/Cntr=0.3,0.1

Type RM Length L Ch R = 1 ,30430   ,914,914,914
BEGIN DESCRIPTION:
SANDY FORK 17.0
END DESCRIPTION:
XS GIS Cut Line= 3
      2505775.01     13771874.98        2505175.       13772775.
        2503975.     13775775.01
#Sta/Elev= 30
  3923.7  308.64  4111.5  299.54  4245.1  288.02  4299.8  285.39    4457  283.09
  4616.3  284.99    4753  283.89  4857.1     285  4955.8  283.47    4957  275.26
  4958.5  274.26  5047.8  275.26  5049.8  286.07  5287.6  283.01  5311.8  282.94
    5583  280.21  5721.1   280.7  5737.8  280.36  5749.9  282.46  5832.5  283.16
  5836.2  283.22  6045.6  284.77  6150.4  283.85  6878.5  286.09  6953.5  285.55
  7364.5  293.81  7396.4  293.71  7513.1  299.41  7850.1  317.82  8236.5   332.3
#Mann= 16 ,-1 , 0
  3923.7     .05       0  4245.1    .035       0  4299.8     .05       0
  4857.1      .1       0    4957     .05       0  5047.8      .1       0
  5287.6     .12       0  5311.8     .07       0  5721.1     .05       0
  5832.5     .07       0  5836.2     .05       0  6045.6    .035       0
  6150.4     .12       0  6878.5     .05       0  7364.5    .035       0
  7513.1     .05       0
Bank Sta=4957,5047.8
XS Rating Curve= 0 ,0
Exp/Cntr=0.3,0.1

Type RM Length L Ch R = 1 ,29516   ,976,976,976
BEGIN DESCRIPTION:
SANDY FORK 16.0
END DESCRIPTION:
XS GIS Cut Line= 3
        2505675.       13771725.        2504975.       13771925.
      2502574.97     13774025.03
#Sta/Elev= 30
    4272  305.53  4400.7  301.74    4636  284.05  4802.5   282.8    4844  283.93
  4937.6  282.63  4958.4  284.28  4961.7  272.92  4963.2  271.92  5052.5  272.92
  5056.5  283.13  5064.1  285.76    5091  286.32  5198.9  284.28  5276.7  285.33
  5545.3  282.64    5943  281.97  5963.8   280.6  6466.9   284.9    6708  285.99
  6728.8  284.85  6736.4  286.08  6927.2   289.3  7047.7  287.36  7274.6  291.34
  7480.5  292.48    7679  297.31  7823.8  298.99  8047.2  300.66  8189.1  303.61
#Mann= 7 ,-1 , 0
    4272     .05       0  4802.5      .1       0  4961.7     .05       0
  5052.5      .1       0    5091     .05       0    7679    .035       0
  7823.8     .07       0
Bank Sta=4961.7,5052.5
XS Rating Curve= 0 ,0
Exp/Cntr=0.3,0.1

Type RM Length L Ch R = 1 ,28540   ,915,915,915
BEGIN DESCRIPTION:
E20620
END DESCRIPTION:
XS GIS Cut Line= 4
      2505666.74     13771642.38      2504626.73     13771220.34
      2504144.41     13771416.29      2501974.39      13773390.4
#Sta/Elev= 30
  3642.9  303.45  3774.3  301.51  4019.3  282.51  4809.6  284.22  4939.8   284.8
  4953.2  283.64    4956  272.49  4957.5  271.49  5046.8  272.49  5047.8  282.18
  5060.3  283.71  5144.9  283.96  5155.7  276.92  5177.3   276.6  5191.5  282.22
    5221  283.67  5282.9   279.6  5305.8  283.49  5383.5  282.55  5975.9  281.53
  6033.7  281.95  6185.2  286.11  6237.9  287.43  7792.2  294.82  7880.4  295.41
  7909.2  297.05  7981.6  294.05  7997.9  298.48  8073.5  300.73  8219.5  296.33
#Mann= 13 ,-1 , 0
  3642.9     .05       0  4809.6      .1       0    4956     .05       0
  5046.8      .1       0  5383.5     .05       0  5975.9    .035       0
  6033.7     .05       0  6185.2    .035       0  6237.9     .05       0
  7792.2     .07       0  7880.4     .05       0  7909.2     .07       0
  7997.9     .05       0
Bank Sta=4956,5046.8
XS Rating Curve= 0 ,0
Exp/Cntr=0.3,0.1

Type RM Length L Ch R = 1 ,27625   ,921,921,921
BEGIN DESCRIPTION:
SANDY FORK 15.0
END DESCRIPTION:
XS GIS Cut Line= 3
      2505724.98     13771574.99        2504725.       13770775.
      2503124.97     13768774.96
#Sta/Elev= 30
  3719.4  304.92  4117.2  283.66  4323.7  281.81    4837  282.42    4908   281.6
  4957.6  283.64  4961.3  272.98  4962.8  271.98  5053.2  272.98  5056.8  283.48
  5201.7  283.13  5832.4  280.45  6010.9  282.32  6052.5  281.82  6074.9  279.08
  6081.3  281.47  6095.7  281.63  6344.7     281  6651.2  291.77  6966.8  308.91
  7134.6  314.76  7169.9  320.82  7184.3  316.14  7198.7  314.83  7291.5  315.35
  7338.5  323.52  7382.8  328.25  7411.6  327.43  7548.6  335.33  7561.3  335.23
#Mann= 8 ,-1 , 0
  3719.4     .05       0    4837      .1       0  4961.3     .05       0
  5053.2      .1       0  5201.7     .12       0  6966.8     .05       0
  7338.5    .035       0  7548.6     .05       0
Bank Sta=4961.3,5053.2
XS Rating Curve= 0 ,0
Exp/Cntr=0.3,0.1