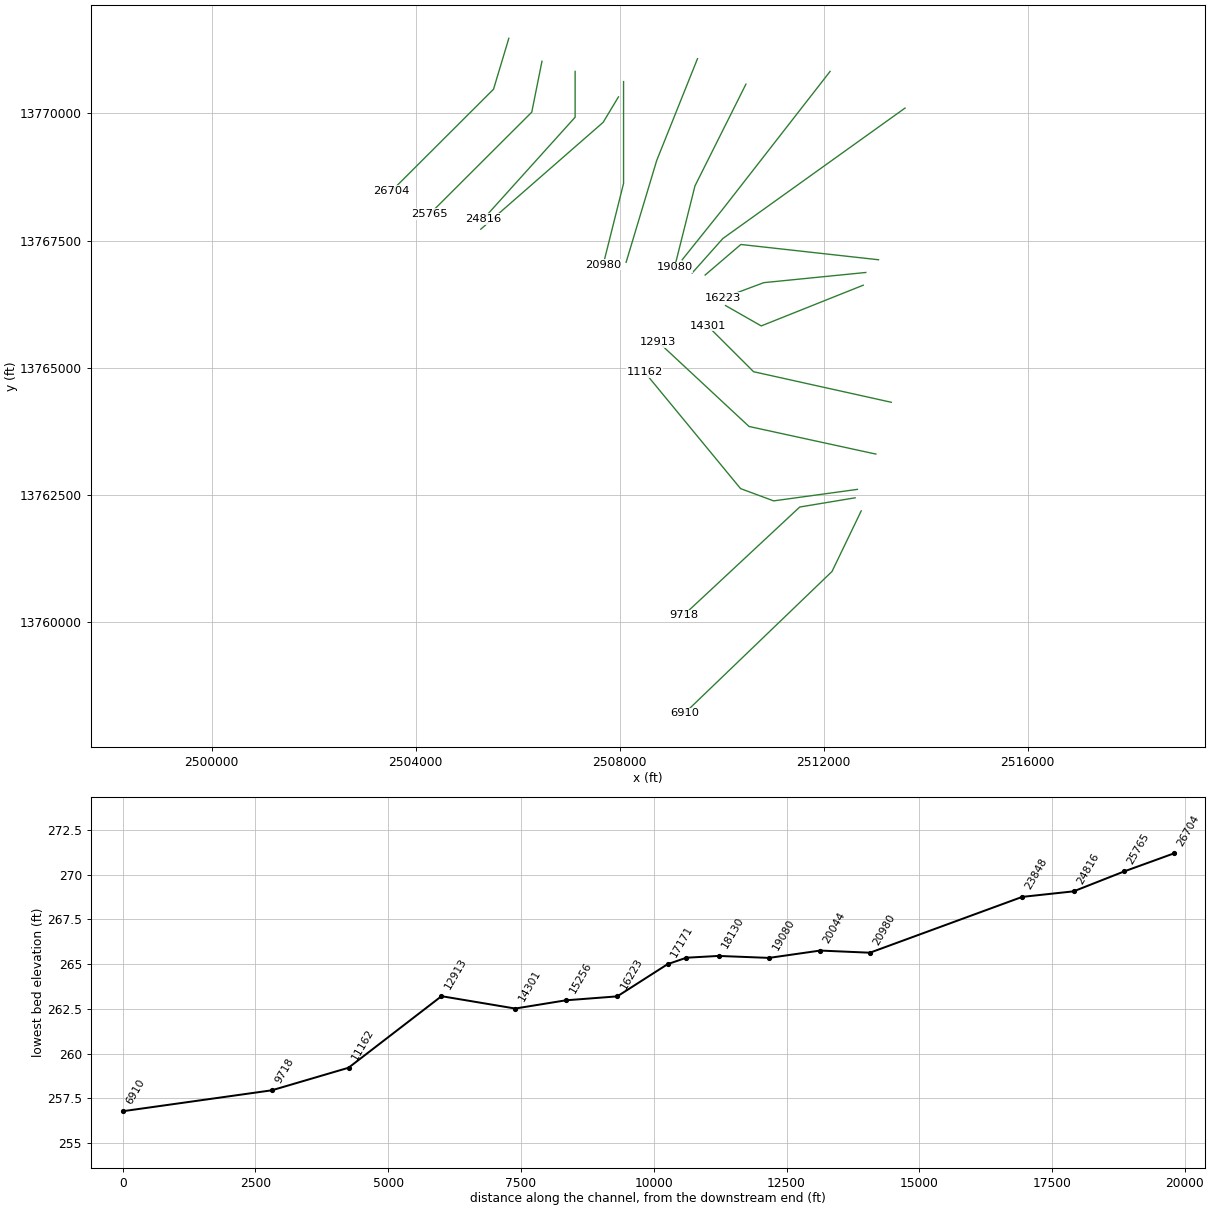
HEC-RAS study SANDY FORK.prj: SANDY FORK Base Level Engineering

--- SANDY FORK.g01 (geometry) --- (continued)

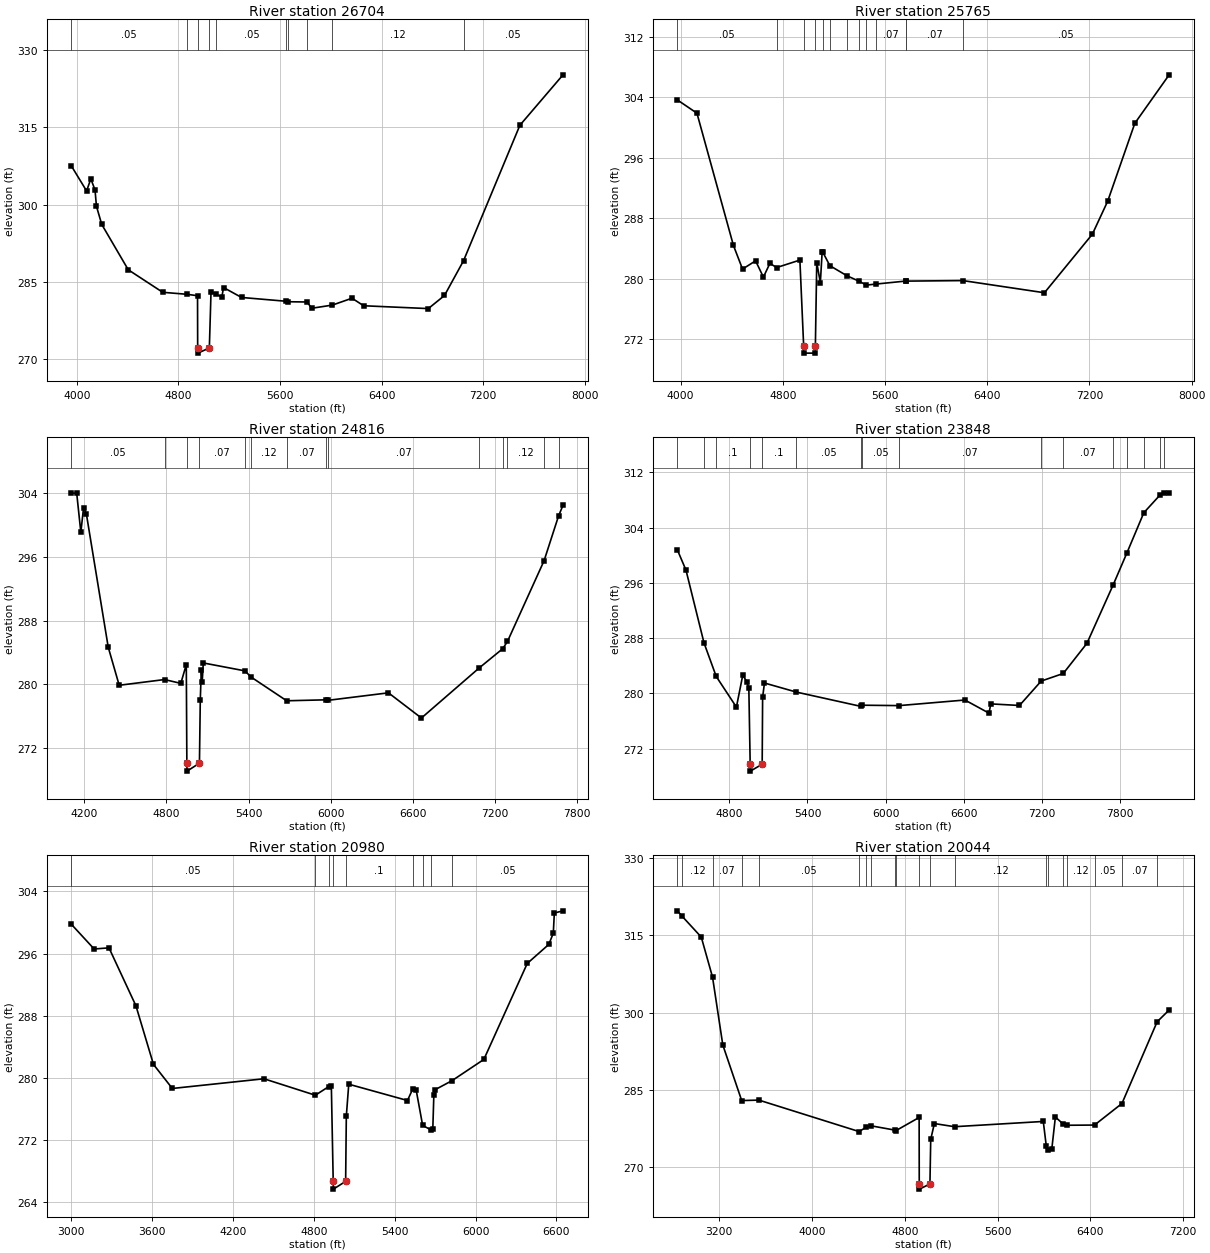
Type RM Length L Ch R = 1 ,26704   ,939,939,939
BEGIN DESCRIPTION:
SANDY FORK 14.0
END DESCRIPTION:
XS GIS Cut Line= 3
        2505825.       13771475.        2505525.       13770475.
      2503524.97     13768474.97
#Sta/Elev= 30
  3955.5  307.54  4076.4  302.65  4109.5     305  4142.6  302.85  4153.9  299.68
  4195.6  296.16  4404.4  287.36  4675.9  282.99  4864.2  282.61  4949.9  282.33
    4951  272.19  4952.5  271.19  5042.9  272.19  5056.1  283.04    5099  282.59
  5140.9  282.07  5155.1  283.91  5296.5  281.99  5648.7  281.25  5659.8  281.16
  5813.5  281.11  5848.1  279.89  6011.6  280.51  6166.3  281.84  6258.2  280.38
  6767.3  279.83  6894.6  282.37  7044.5  289.11  7488.5   315.4    7828  325.18
#Mann= 10 ,-1 , 0
  3955.5     .05       0  4864.2      .1       0    4951     .05       0
  5042.9      .1       0    5099     .05       0  5648.7     .07       0
  5659.8     .05       0  5813.5     .07       0  6011.6     .12       0
  7044.5     .05       0
Bank Sta=4951,5042.9
XS Rating Curve= 0 ,0
Exp/Cntr=0.3,0.1

Type RM Length L Ch R = 1 ,25765   ,949,949,949
BEGIN DESCRIPTION:
SANDY FORK 13.0
END DESCRIPTION:
XS GIS Cut Line= 3
        2506475.       13771025.        2506275.       13770025.
      2504275.02     13768025.02
#Sta/Elev= 30
  3975.6  303.65  4128.6   301.9  4414.1  284.42  4485.5  281.29  4587.5  282.38
  4648.7  280.23  4699.7  282.05  4752.1  281.49  4934.2  282.48  4963.6  271.18
  4965.1  270.18    5054  270.18  5055.5  271.18  5066.1  282.16  5094.4   279.5
  5108.5  283.58  5113.2  283.54  5168.8  281.74  5304.3  280.39  5399.7  279.67
  5454.2  279.17    5529  279.31    5765  279.71  5766.6   279.7  6209.5  279.77
    6848  278.16  7222.8   285.9    7343  290.27  7555.1  300.56  7823.8  306.97
#Mann= 13 ,-1 , 0
  3975.6     .05       0  4752.1      .1       0  4963.6    .035       0
  5055.5      .1       0  5113.2     .05       0  5168.8    .035       0
  5304.3     .05       0  5399.7     .07       0  5454.2     .05       0
    5529     .07       0    5765     .05       0  5766.6     .07       0
  6209.5     .05       0
Bank Sta=4963.6,5055.5
XS Rating Curve= 0 ,0
Exp/Cntr=0.3,0.1

Type RM Length L Ch R = 1 ,24816   ,968,968,968
BEGIN DESCRIPTION:
SANDY FORK 12.0
END DESCRIPTION:
XS GIS Cut Line= 3
        2507125.       13770825.        2507125.       13769925.
      2505325.02     13767925.02
#Sta/Elev= 30
    4105  304.08    4145     304    4175  299.11    4195  302.22    4215  301.47
    4375  284.66    4455  279.87    4786  280.59    4905  280.11    4945  282.48
  4949.1  270.07  4950.6  269.07    5041  270.07  5047.2  278.07  5054.7  281.84
  5061.4  280.34  5068.9  282.68  5373.6  281.68  5416.6  280.92    5678  277.92
    5966  278.04  5976.7  277.97    6421  278.92  6661.7  275.75  7085.7  282.08
  7255.5  284.47  7290.2  285.39  7557.4  295.54  7663.1  301.17  7695.7  302.52
#Mann= 14 ,-1 , 0
    4105     .05       0    4786     .07       0  4949.1     .05       0
    5041     .07       0  5373.6     .05       0  5416.6     .12       0
    5678     .07       0    5966     .12       0  5976.7     .07       0
  7085.7     .12       0  7255.5     .07       0  7290.2     .12       0
  7557.4     .07       0  7663.1     .05       0
Bank Sta=4949.1,5041
XS Rating Curve= 0 ,0
Exp/Cntr=0.3,0.1

Type RM Length L Ch R = 1 ,23848   ,2868,2868,2868
BEGIN DESCRIPTION:
SANDY FORK 11.0
END DESCRIPTION:
XS GIS Cut Line= 3
      2507974.98     13770324.96        2507675.       13769825.
      2505274.99       13767725.
#Sta/Elev= 30
    4402  300.77    4468  297.84  4606.3  287.31  4699.9  282.46  4854.8  278.02
  4903.4  282.64  4934.5  281.71  4950.1  280.74  4960.4  269.76  4961.9  268.76
  5052.4  269.76  5055.8  279.46    5070  281.51  5314.3   280.2  5807.4  278.14
  5817.4   278.3  6102.2  278.24  6607.6  279.05  6792.2  277.15  6805.9  278.49
  7026.1  278.26  7192.5  281.79    7362  282.89  7543.4  287.25  7744.7  295.71
  7850.5  300.35  7979.9  306.15  8105.9  308.75  8134.3  309.03  8174.1  308.99
#Mann= 16 ,-1 , 0
    4402     .05       0  4606.3     .07       0  4699.9      .1       0
  4960.4     .05       0  5052.4      .1       0  5314.3     .05       0
  5807.4     .07       0  5817.4     .05       0  6102.2     .07       0
  7192.5     .12       0    7362     .07       0  7744.7     .12       0
  7850.5     .05       0  7979.9     .07       0  8105.9     .05       0
  8134.3    .035       0
Bank Sta=4960.4,5052.4
XS Rating Curve= 0 ,0
Exp/Cntr=0.3,0.1

Type RM Length L Ch R = 1 ,20980   ,936,936,936
BEGIN DESCRIPTION:
SANDY FORK 10.0
END DESCRIPTION:
XS GIS Cut Line= 3
        2508075.     13770624.98        2508075.       13768625.
      2507675.01     13767025.02
#Sta/Elev= 30
  2999.6  299.78  3169.6  296.58  3279.6  296.73  3479.6  289.26  3609.6  281.71
  3749.6  278.61  4429.6  279.86  4810.9  277.74  4909.3  278.84  4929.6  278.95
  4943.5  266.64    4945  265.64  5035.7  266.64  5040.8  275.04  5058.8  279.16
  5494.4  277.06  5532.8  278.51  5558.8  278.44    5607  273.86  5671.6  273.24
  5682.5  273.38  5690.2  277.73  5700.5  278.46  5825.5  279.62  6061.3  282.35
  6383.4  294.72  6543.2  297.17  6576.7  298.62  6584.4  301.22  6648.8   301.5
#Mann= 9 ,-1 , 0
  2999.6     .05       0  4810.9     .12       0  4909.3      .1       0
  4943.5     .05       0  5035.7      .1       0  5532.8     .07       0
    5607      .1       0  5671.6     .07       0  5825.5     .05       0
Bank Sta=4943.5,5035.7
XS Rating Curve= 0 ,0
Exp/Cntr=0.3,0.1

Type RM Length L Ch R = 1 ,20044   ,964,964,964
BEGIN DESCRIPTION:
SANDY FORK 9.0
END DESCRIPTION:
XS GIS Cut Line= 3
        2509525.     13771075.01        2508725.       13769075.
      2508125.01     13767075.04
#Sta/Elev= 30
  2838.1  319.75  2880.5  318.66  3044.1  314.66  3141.3  306.89  3229.9  293.73
  3392.8  282.94  3541.3  283.03    4405  276.93  4469.1  277.79  4506.3  278.05
  4716.8   277.2  4720.7  277.07  4923.5  279.66  4924.5  266.76    4926  265.76
  5016.7  266.76  5023.5  275.41  5054.8  278.48  5229.1  277.87  5994.4  278.89
  6020.9  274.03  6035.8  273.42  6067.5  273.46  6098.8  279.75  6161.8  278.47
  6197.9  278.15  6436.5  278.19    6673  282.37  6976.7  298.23  7080.2  300.51
#Mann= 20 ,-1 , 0
  2838.1     .07       0  2880.5     .12       0  3141.3     .07       0
  3392.8    .035       0  3541.3     .05       0    4405     .12       0
  4469.1     .05       0  4506.3     .12       0  4716.8     .07       0
  4720.7      .1       0  4924.5     .05       0  5016.7      .1       0
  5229.1     .12       0  6020.9      .1       0  6035.8     .12       0
  6161.8     .05       0  6197.9     .12       0  6436.5     .05       0
    6673     .07       0  6976.7     .05       0
Bank Sta=4924.5,5016.7
XS Rating Curve= 0 ,0
Exp/Cntr=0.3,0.1

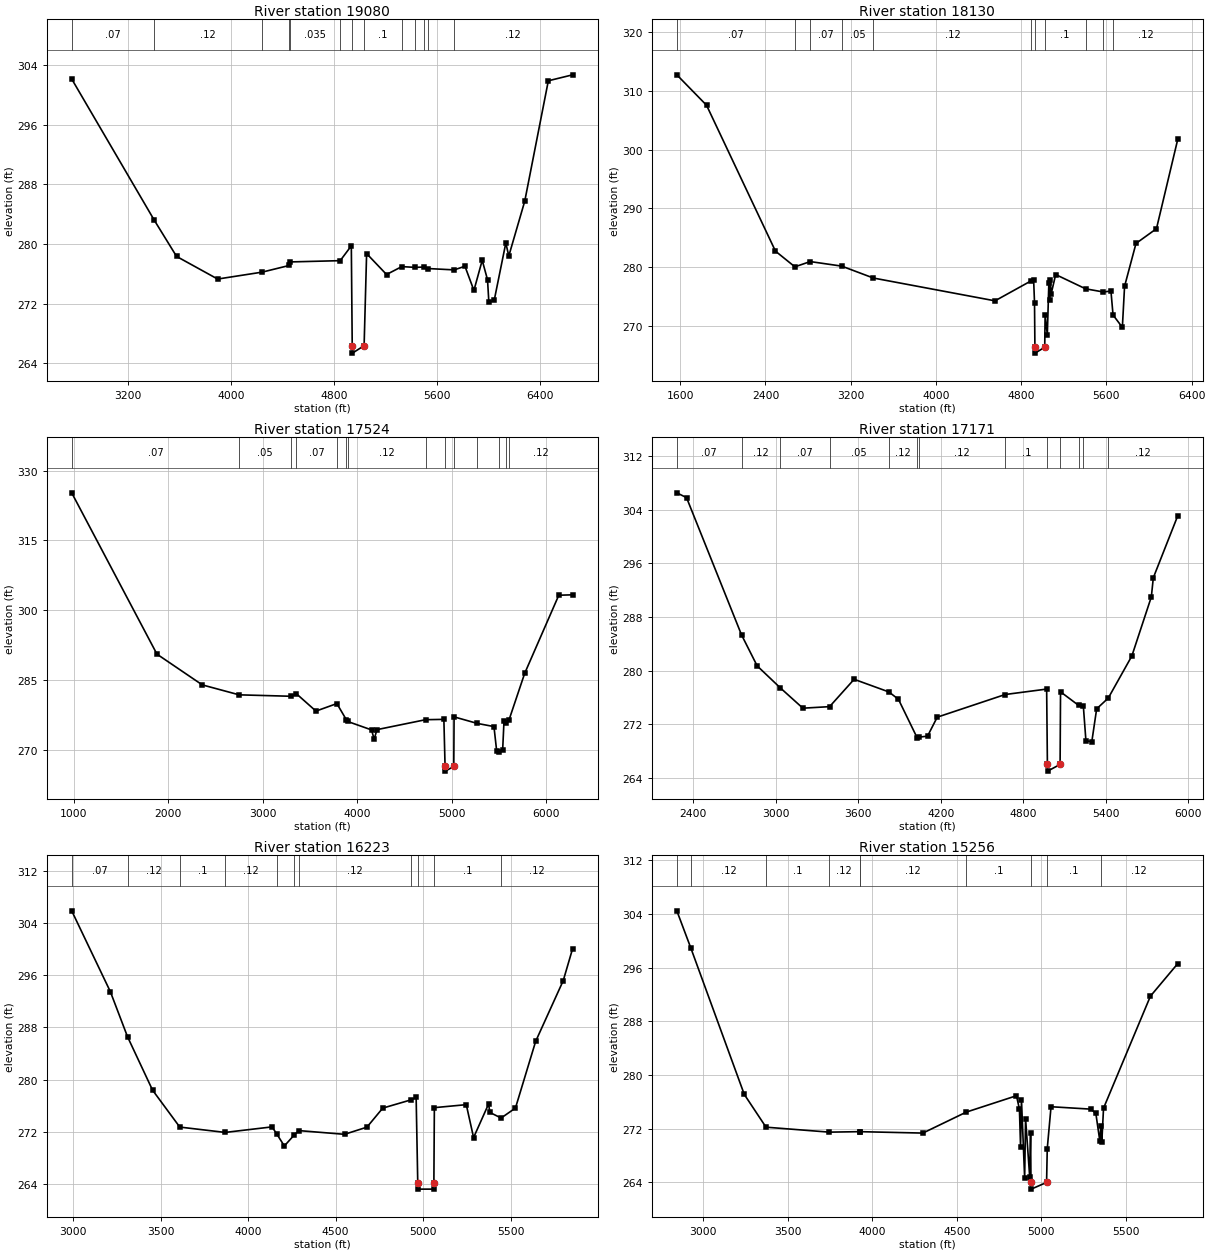
Type RM Length L Ch R = 1 ,19080   ,950,950,950
BEGIN DESCRIPTION:
SANDY FORK 8.0
END DESCRIPTION:
XS GIS Cut Line= 3
      2510475.01     13770575.02        2509475.       13768575.
      2509075.01     13766975.03
#Sta/Elev= 30
  2764.4  302.17  3403.9  283.23  3577.8  278.34  3896.4   275.3    4242  276.23
  4450.4  277.12  4459.4   277.6  4847.2  277.77  4933.4  279.76  4940.4  266.35
  4941.9  265.35  5032.6  266.35    5052  278.72  5206.6  275.91  5324.8  276.97
    5427  276.87    5497  276.91  5529.2  276.71  5731.1  276.53  5814.8  277.02
  5884.4  273.77  5948.8  277.82    5990   275.2  6000.3  272.18  6041.6  272.42
  6131.8  280.14    6155   278.4  6278.7  285.76  6461.6  301.93  6649.7  302.73
#Mann= 13 ,-1 , 0
  2764.4     .07       0  3403.9     .12       0    4242    .035       0
  4450.4     .05       0  4459.4    .035       0  4847.2      .1       0
  4940.4     .05       0  5032.6      .1       0  5324.8     .12       0
    5427     .07       0    5497     .12       0  5529.2    .035       0
  5731.1     .12       0
Bank Sta=4940.4,5032.6
XS Rating Curve= 0 ,0
Exp/Cntr=0.3,0.1

Type RM Length L Ch R = 1 ,18130   ,606,606,606
BEGIN DESCRIPTION:
SANDY FORK 7.0
END DESCRIPTION:
XS GIS Cut Line= 3
      2512125.01     13770825.01        2510025.       13768125.
      2509224.98     13767124.97
#Sta/Elev= 30
    1568  312.67  1846.7  307.51  2493.7  282.76  2675.9   280.1  2819.9  280.99
  3115.4  280.22  3412.5   278.2  4554.2  274.33  4896.2  277.75  4917.1  277.82
  4925.2  274.03  4928.9  266.46  4930.4  265.46  5021.1  266.46  5024.6  271.96
  5045.4  268.59  5059.8   277.4  5066.2  274.54  5074.2  277.92  5080.6  275.46
  5123.8  278.79  5404.8  276.37  5572.5  275.83  5642.5     276  5662.3  271.93
  5749.7  269.83  5770.5   276.8  5877.8  284.07  6069.9  286.57  6269.2   301.7
#Mann= 11 ,-1 , 0
    1568     .07       0  2675.9     .05       0  2819.9     .07       0
  3115.4     .05       0  3412.5     .12       0  4896.2      .1       0
  4928.9     .05       0  5021.1      .1       0  5404.8     .12       0
  5572.5     .12       0  5662.3     .12       0
Bank Sta=4928.9,5021.1
XS Rating Curve= 0 ,0
Exp/Cntr=0.3,0.1

Type RM Length L Ch R = 1 ,17524   ,353,353,353
BEGIN DESCRIPTION:
E20619
END DESCRIPTION:
XS GIS Cut Line= 3
      2513594.99     13770104.93      2510022.78     13767542.59
      2509419.92     13766864.37
#Sta/Elev= 30
   976.1  325.26  1878.7  290.54  2358.8  283.92  2749.1  281.78  3301.9  281.47
  3355.7  282.01  3562.4  278.28  3783.9   279.9    3883  276.46  3897.7  276.05
  4151.2  274.23  4178.8  272.21  4208.3  274.29  4723.4  276.43  4916.9   276.5
  4929.6  266.36  4931.1  265.36  5021.8  266.36    5025  277.04  5270.3  275.63
  5447.2  274.95  5475.6  269.78  5503.1  269.38  5539.2  269.84  5553.4  276.05
  5578.7  275.76  5606.1  276.34  5772.5   286.4  6133.7  303.22  6279.7  303.31
#Mann= 14 ,-1 , 0
   976.1     .07       0  2749.1     .05       0  3301.9    .035       0
  3355.7     .07       0  3783.9     .12       0    3883     .07       0
  3897.7     .12       0  4723.4      .1       0  4929.6     .05       0
  5021.8      .1       0  5270.3     .12       0  5503.1     .12       0
  5578.7      .1       0  5606.1     .12       0
Bank Sta=4929.6,5021.8
XS Rating Curve= 0 ,0
Exp/Cntr=0.3,0.1

Type RM Length L Ch R = 1 ,17171   ,948,948,948
BEGIN DESCRIPTION:
SANDY FORK 6.0
END DESCRIPTION:
XS GIS Cut Line= 3
      2513075.04       13767125.        2510375.       13767425.
      2509675.01     13766825.01
#Sta/Elev= 30
  2283.1  306.52  2353.6   305.8  2753.2  285.32  2866.7   280.7  3034.8  277.42
  3198.7  274.39  3392.7  274.62    3571   278.7  3824.1  276.81    3893  275.71
  4029.4  269.95  4042.7  270.07  4104.3  270.22  4174.7  273.05  4668.2  276.43
  4969.6  277.24  4975.1     266  4976.6     265  5067.3     266  5070.5  276.83
  5201.2  274.82  5236.3  274.68  5254.9  269.53  5297.7  269.39  5332.9  274.29
  5417.3   275.9  5588.6  282.18  5730.2     291  5744.5  293.85  5921.7  303.08
#Mann= 13 ,-1 , 0
  2283.1     .07       0  2753.2     .12       0  3034.8     .07       0
  3392.7     .05       0  3824.1     .12       0  4029.4     .12       0
  4042.7     .12       0  4668.2      .1       0  4975.1     .05       0
  5067.3      .1       0  5201.2     .12       0  5236.3      .1       0
  5417.3     .12       0
Bank Sta=4975.1,5067.3
XS Rating Curve= 0 ,0
Exp/Cntr=0.3,0.1

Type RM Length L Ch R = 1 ,16223   ,967,967,967
BEGIN DESCRIPTION:
SANDY FORK 5.0
END DESCRIPTION:
XS GIS Cut Line= 3
      2512824.99       13766875.        2510825.       13766675.
      2510024.97     13766374.99
#Sta/Elev= 30
  2990.4   305.9  3211.5  293.49  3309.6  286.58  3452.7  278.39  3608.5  272.72
  3868.1   271.9  4136.1  272.75  4164.1  271.62  4206.4  269.82  4262.8   271.5
  4289.6  272.18  4550.6  271.61  4678.8  272.71  4769.2  275.63  4928.7  276.88
  4960.2  277.26  4969.4   264.2  4970.9   263.2  5060.1   263.2  5061.6   264.2
  5064.4   275.7  5246.9  276.16  5288.7  271.11  5374.2  276.25  5382.2  274.96
  5446.2  274.11  5528.1  275.64  5643.8  285.88  5801.4  295.19  5854.8  300.08
#Mann= 11 ,-1 , 0
  2990.4     .07       0  3309.6     .12       0  3608.5      .1       0
  3868.1     .12       0  4164.1     .12       0  4262.8      .1       0
  4289.6     .12       0  4928.7      .1       0  4969.4     .05       0
  5061.6      .1       0  5446.2     .12       0
Bank Sta=4969.4,5061.6
XS Rating Curve= 0 ,0
Exp/Cntr=0.3,0.1

Type RM Length L Ch R = 1 ,15256   ,955,955,955
BEGIN DESCRIPTION:
SANDY FORK 4.0
END DESCRIPTION:
XS GIS Cut Line= 3
      2512774.96     13766624.99        2510775.       13765825.
      2510074.96     13766225.02
#Sta/Elev= 30
  2845.5  304.49  2928.5  298.92    3244  277.11  3372.5  272.22  3746.1  271.48
  3925.2  271.55  3928.3  271.55  4299.5  271.34  4556.4  274.47  4852.8  276.91
  4870.3  274.92    4877  269.32  4882.4   276.3  4901.2  264.63  4906.6  273.51
  4930.9  264.84  4936.3   271.4  4938.6  263.98  4940.1  262.98  5030.8  263.98
  5034.8  269.03  5057.1  275.27  5292.5  274.91    5322  274.28  5345.1  270.23
    5352  272.33  5357.3  270.03  5367.4  275.05  5644.5  291.76  5805.8  296.61
#Mann= 10 ,-1 , 0
  2845.5     .07       0  2928.5     .12       0  3372.5      .1       0
  3746.1     .12       0  3925.2      .1       0  3928.3     .12       0
  4556.4      .1       0  4938.6     .05       0  5030.8      .1       0
    5352     .12       0
Bank Sta=4938.6,5030.8
XS Rating Curve= 0 ,0
Exp/Cntr=0.3,0.1

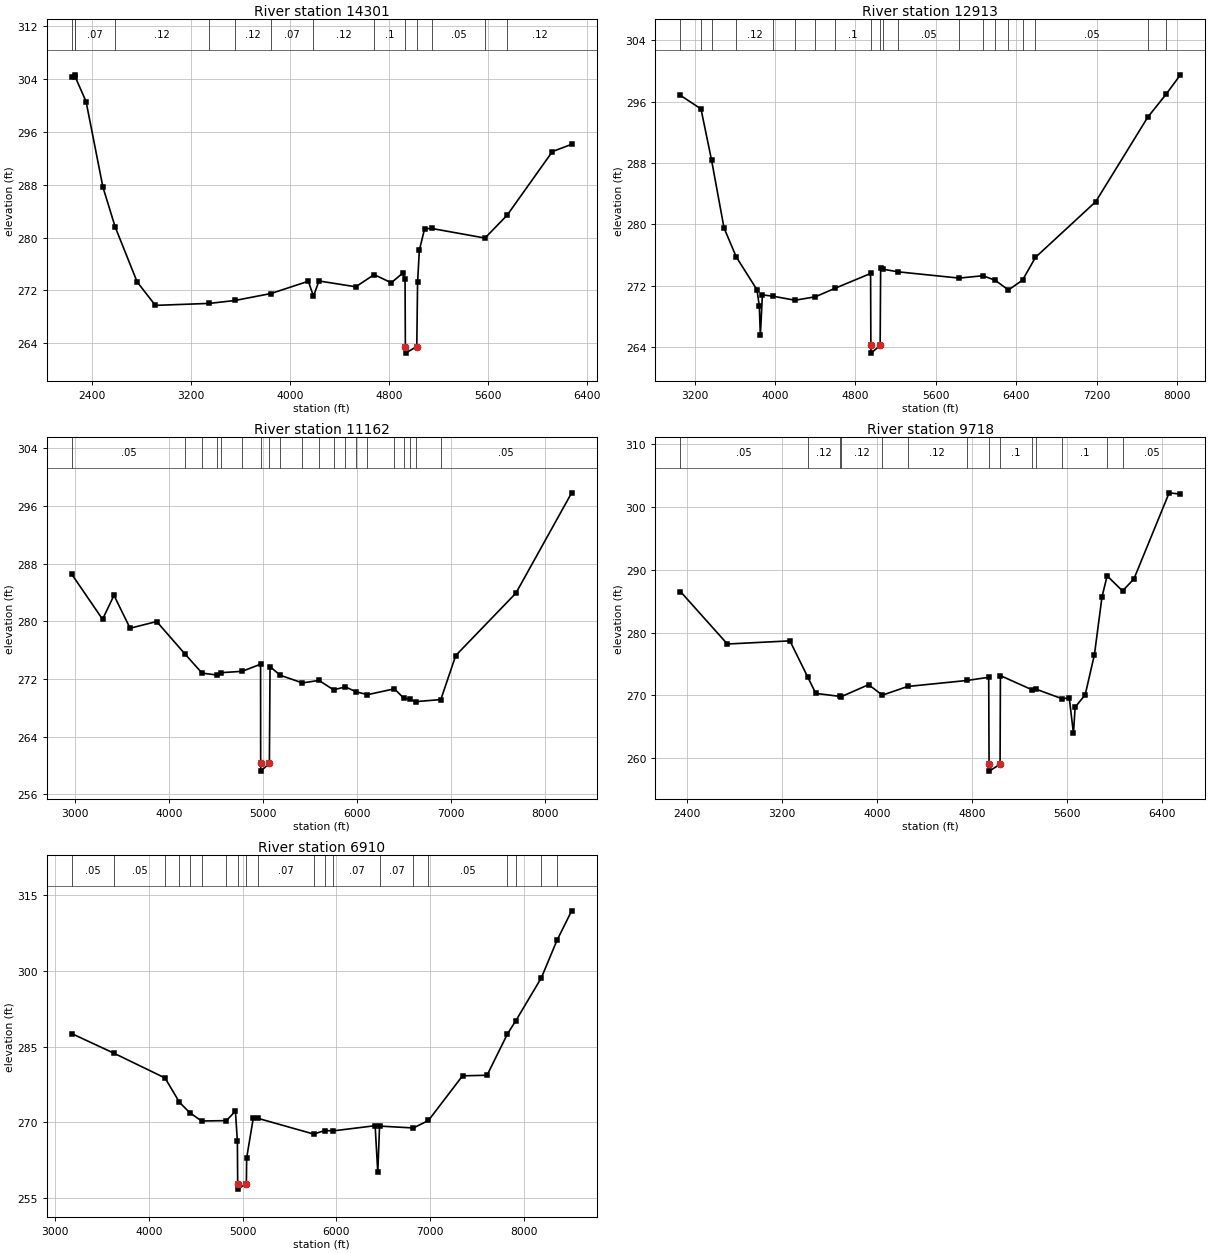
Type RM Length L Ch R = 1 ,14301   ,1388,1388,1388
BEGIN DESCRIPTION:
SANDY FORK 3.0
END DESCRIPTION:
XS GIS Cut Line= 3
      2513324.99       13764325.        2510625.       13764925.
      2509725.03     13765824.97
#Sta/Elev= 30
  2233.6   304.2  2257.9   304.6  2264.1  304.22  2350.1  300.55  2485.8  287.64
    2585   281.6  2762.4  273.29  2909.7  269.74  3346.9  270.04  3552.1  270.48
    3843  271.53  4145.4  273.39  4186.7  271.12  4231.2  273.43  4528.2  272.55
  4676.9  274.39  4815.1  273.16  4907.3  274.61  4926.5  273.67    4929  263.52
  4930.5  262.52  5021.3  263.52  5027.7   273.2  5041.9  278.06  5084.3  281.33
  5141.8  281.37  5572.2  279.92  5750.8  283.37  6116.7     293  6272.2  294.09
#Mann= 14 ,-1 , 0
  2233.6    .035       0  2257.9     .05       0  2264.1     .07       0
    2585     .12       0  3346.9      .1       0  3552.1     .12       0
    3843     .07       0  4186.7     .12       0  4676.9      .1       0
    4929     .05       0  5021.3      .1       0  5141.8     .05       0
  5572.2    .035       0  5750.8     .12       0
Bank Sta=4929,5021.3
XS Rating Curve= 0 ,0
Exp/Cntr=0.3,0.1

Type RM Length L Ch R = 1 ,12913   ,1751,1751,1751
BEGIN DESCRIPTION:
E20618
END DESCRIPTION:
XS GIS Cut Line= 3
      2513022.28     13763307.14      2510535.25     13763849.76
      2508756.64     13765507.79
#Sta/Elev= 30
    3058  296.84  3262.7  295.07  3367.6  288.41  3491.9  279.55  3614.2  275.75
  3819.9  271.48  3843.3  269.34  3853.6  265.51    3874  270.81  3982.2  270.63
    4199  270.11  4400.7  270.56  4597.2  271.67  4950.9   273.6  4953.8  264.21
  4955.3  263.21  5046.1  264.21  5051.1  274.36  5077.5  274.15  5223.2  273.82
  5831.9     273  6070.8  273.31    6193   272.7    6323  271.45  6463.2  272.73
  6592.5  275.71  7192.2  282.97  7709.9  293.99  7891.4  296.97  8035.1  299.52
#Mann= 20 ,-1 , 0
    3058     .05       0  3262.7     .07       0  3367.6     .05       0
  3614.2     .12       0  3982.2      .1       0    4199     .07       0
  4400.7     .05       0  4597.2      .1       0  4953.8     .05       0
  5046.1      .1       0  5077.5     .12       0  5223.2     .05       0
  5831.9     .07       0  6070.8     .05       0    6193     .05       0
    6323     .12       0  6463.2     .12       0  6592.5     .05       0
  7709.9    .035       0  7891.4     .12       0
Bank Sta=4953.8,5046.1
XS Rating Curve= 0 ,0
Exp/Cntr=0.3,0.1

Type RM Length L Ch R = 1 ,11162   ,1444,1444,1444
BEGIN DESCRIPTION:
E20617
END DESCRIPTION:
XS GIS Cut Line= 4
      2512660.56      13762613.8      2511017.58     13762387.71
      2510369.45     13762628.87      2508485.34     13764919.95
#Sta/Elev= 30
  2966.8  286.55  3295.4  280.28  3416.6   283.6  3588.2  279.04  3870.3  279.97
  4174.1  275.43  4353.3  272.81  4510.4  272.55  4551.3  272.87  4779.9  273.06
  4975.4  274.05  4976.4  260.31  4977.9  259.21  5069.2  260.31  5076.2  273.71
  5183.3  272.52  5420.3  271.45  5596.2   271.8  5751.6  270.49  5876.2   270.9
  5991.8  270.22  6112.1  269.82  6398.9  270.63  6498.9  269.32  6559.4  269.19
  6623.5  268.85    6892  269.14  7050.5  275.25  7690.4  283.91  8283.1  297.83
#Mann= 20 ,-1 , 0
  2966.8     .05       0  4174.1     .07       0  4353.3     .05       0
  4510.4     .07       0  4551.3     .12       0  4779.9     .12       0
  4976.4     .05       0  5069.2     .12       0  5183.3     .12       0
  5420.3     .12       0  5596.2    .035       0  5751.6     .05       0
  5876.2     .12       0  5991.8     .05       0  6112.1     .12       0
  6398.9     .07       0  6498.9     .05       0  6559.4     .07       0
  6623.5     .12       0    6892     .05       0
Bank Sta=4976.4,5069.2
XS Rating Curve= 0 ,0
Exp/Cntr=0.3,0.1

Type RM Length L Ch R = 1 ,9718    ,2808,2808,2808
BEGIN DESCRIPTION:
SANDY FORK 2.0
END DESCRIPTION:
XS GIS Cut Line= 3
      2512615.25     13762447.99      2511530.06     13762267.12
       2509254.1     13760141.89
#Sta/Elev= 30
  2344.9  286.53  2740.5  278.18  3267.7  278.68  3419.4  272.87  3485.5  270.32
  3690.9  269.84  3700.7   269.8    3931  271.71  4047.2  270.04  4259.1  271.42
  4760.9  272.38  4943.2  272.88  4946.2  259.05  4947.7  257.95    5039  259.05
  5041.9  273.15  5304.3  270.93  5338.3  271.02  5560.4  269.48  5622.3  269.59
  5657.5  263.94  5671.6  268.12  5756.6  270.11  5834.3   276.5  5898.3  285.71
  5941.3  289.02  6071.2  286.63    6167  288.53    6464  302.24    6559  302.03
#Mann= 14 ,-1 , 0
  2344.9     .05       0  3419.4     .12       0  3690.9     .07       0
  3700.7     .12       0  4047.2      .1       0  4259.1     .12       0
  4760.9      .1       0  4946.2     .05       0    5039      .1       0
  5304.3     .12       0  5338.3     .07       0  5560.4      .1       0
  5941.3     .07       0  6071.2     .05       0
Bank Sta=4946.2,5039
XS Rating Curve= 0 ,0
Exp/Cntr=0.3,0.1

Type RM Length L Ch R = 1 ,6910    ,0,0,0
BEGIN DESCRIPTION:
SANDY FORK 1.0
END DESCRIPTION:
XS GIS Cut Line= 3
      2512735.87     13762191.75      2512163.11     13761001.01
      2509269.58     13758212.97
#Sta/Elev= 30
  3173.9   287.6  3625.2  283.71  4171.1   278.8  4324.5     274  4435.2  271.91
  4562.1  270.28  4826.6  270.35  4922.6  272.24  4943.7  266.22  4946.7  257.88
  4948.2  256.78  5039.5  257.88  5042.7  262.96  5113.5  270.86  5164.6   270.8
  5758.5  267.69  5877.4  268.39  5966.5  268.32  6414.7  269.35    6443  260.09
    6462  269.27  6823.4   268.9  6983.9  270.38  7348.3  279.23  7609.9  279.34
  7827.7  287.53  7917.5  290.16  8189.4  298.63  8356.4  306.06  8513.4  311.92
#Mann= 20 ,-1 , 0
  3173.9     .05       0  3625.2     .05       0  4171.1     .07       0
  4324.5     .05       0  4435.2     .07       0  4562.1     .12       0
  4826.6      .1       0  4946.7     .05       0  5039.5      .1       0
  5164.6     .07       0  5758.5    .035       0  5877.4     .12       0
  5966.5     .07       0    6462     .07       0  6823.4    .035       0
  6983.9     .05       0  7827.7    .035       0  7917.5     .05       0
  8189.4     .07       0  8356.4     .05       0
Bank Sta=4946.7,5039.5
XS Rating Curve= 0 ,0
Exp/Cntr=0.3,0.1

Chan Stop Cuts=-1
Use User Specified Reach Order=0
Composite Channel Slope=5