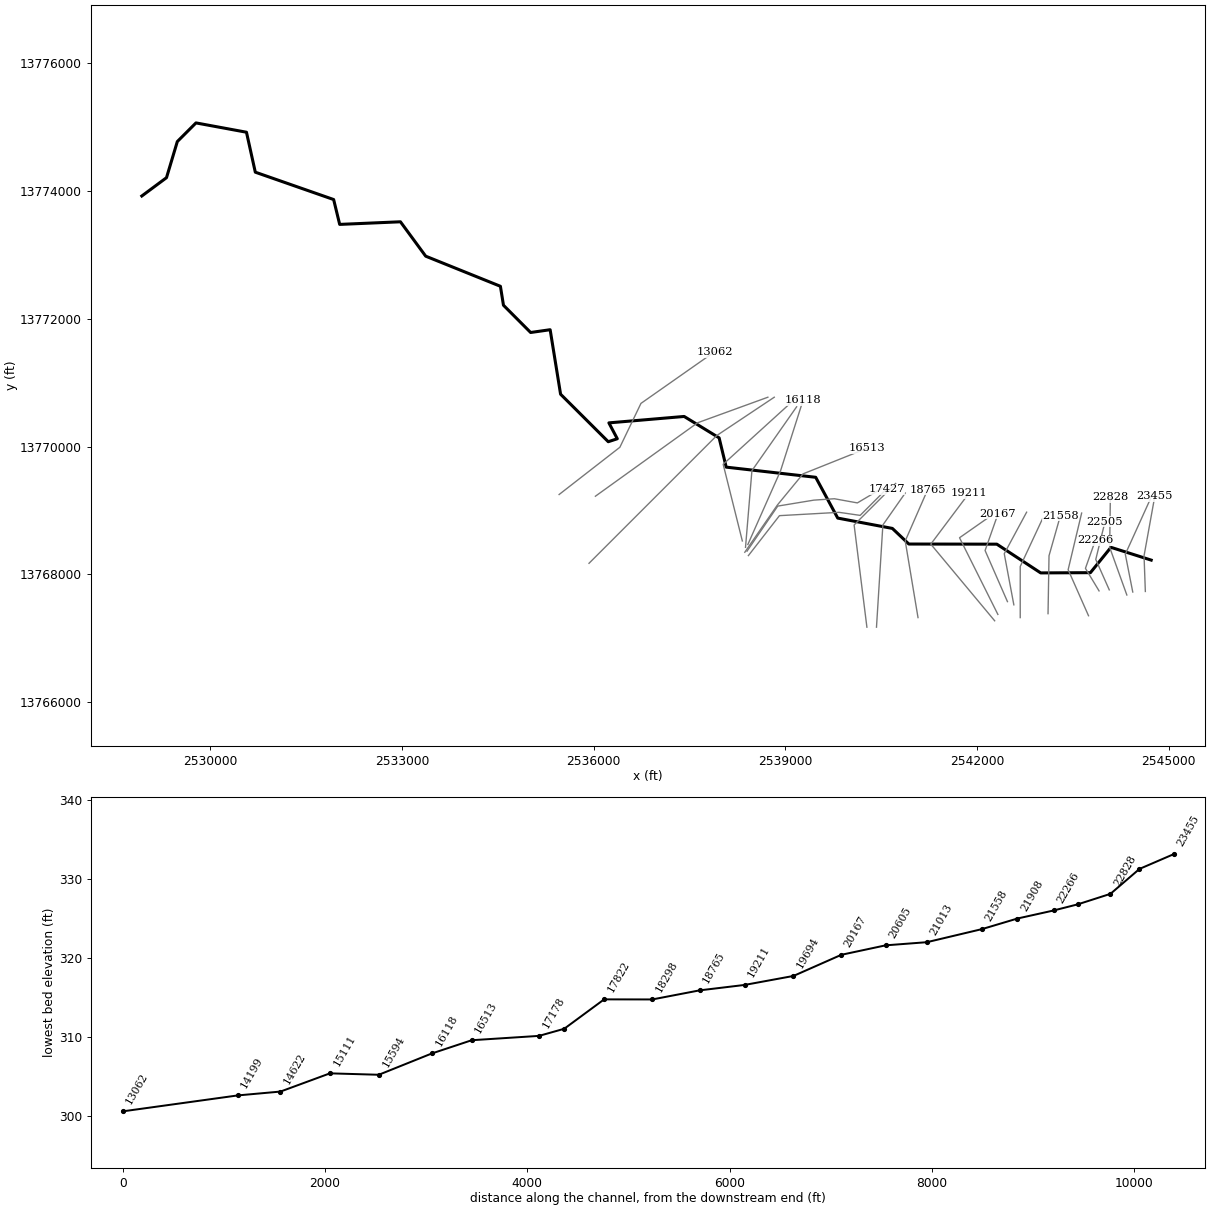
--- SULPHUR BRANCH.prj (project) ---

Proj Title=SULPHUR BRANCH Base Level Engineering
Current Plan=p01
Default Exp/Contr=0.3,0.1
English Units
Geom File=g01
Flow File=f01
Plan File=p01
Y Axis Title=Elevation
X Axis Title(PF)=Main Channel Distance
X Axis Title(XS)=Station
BEGIN DESCRIPTION:
SULPHUR BRANCH
END DESCRIPTION:
DSS Export Rating Curves= 0
DSS Export Rating Curve Sorted= 0
DSS Export Volume Flow Curves= 0
DXF OffsetX= 0
DXF OffsetY= 0
DXF ScaleX= 1
DXF ScaleY= 10

--- SULPHUR BRANCH.p01 (plan) ---

Plan Title=Multiple Run
Program Version=4.10
Short Identifier=Multiple
Geom File=g01
Flow File=f01
Subcritical Flow
K Sum by GR= 0
Std Step Tol= 0.01
Critical Tol= 0.01
Num of Std Step Trials= 20
Max Error Tol= 0.3
Flow Tol Ratio= 0.001
Split Flow NTrial= 30
Split Flow Tol= 0.02
Split Flow Ratio= 0.02
Log Output Level= 0
Friction Slope Method= 1
Unsteady Friction Slope Method= 2
Unsteady Bridges Friction Slope Method= 1
Parabolic Critical Depth
Global Vel Dist= 1 , 1 , 1
Global Log Level= 0
CheckData=True
Encroach Param=-1 ,0,0, 0
BEGIN DESCRIPTION:
Multiple Run
END DESCRIPTION:
Computation Interval=1HOUR
Output Interval=1HOUR
Run HTab= 0
Run UNet= 0
Run PostProcess= 0
Run WQNet= 0
UNET Theta= 1
UNET Theta Warmup= 1
UNET ZTol= 0.02
UNET ZSATol= 0.05
UNET MxIter= 20
UNET MaxInSteps= 0
UNET DtIC= 0
UNET DtMin= 0
UNET MaxCRTS= 20
UNET WFStab= 2
UNET SFStab= 1
UNET WFX= 1
UNET SFX= 1
UNET DSS MLevel= 4
UNET DZMax Abort= 100
UNET Convert EG Bridges= 0
UNET Use Existing IB Tables=-1
UNET Froude Reduction=False
UNET Froude Limit= 1
UNET Froude Power= 10
UNET Time Slicing=0,0, 5
UNET Junction Losses=0
Instantaneous Interval=1HOUR
Write IC File= 0
Write IC File at Sim End=0
Echo Input=False
Echo Parameters=False
Echo Output=False
Write Detailed= 0
WQ AD Non Conservative
WQ ULTIMATE=-1
WQ Max Comp Step=1HOUR
WQ Output Interval=15MIN
WQ Output Selected Increments= 0
WQ Output face flow=0
WQ Output face velocity=0
WQ Output face area=0
WQ Output face dispersion=0
WQ Output cell volume=0
WQ Output cell surface area=0
WQ Output cell continuity=0
WQ Output cumulative cell continuity=0
WQ Output face conc=0
WQ Output face dconc_dx=0
WQ Output face courant=0
WQ Output face peclet=0
WQ Output face adv mass=0
WQ Output face disp mass=0
WQ Output cell mass=0
WQ Output cell source sink temp=0
WQ Output cell source sink nsm=0
WQ Output MaxMinRange=-1
WQ Daily Max Min Mean=-1
WQ Daily Range=0
WQ Daily Time=0
WQ Create Restart=0
WQ Fixed Restart=0
WQ System Summary=0
WQ Use Fixed Temperature=0
Sorting and Armoring Iterations= 10
XS Update Threshold= 0.02
Hydraulics Update Threshold= 0.02
Energy Slope Method= 1
Volume Change Method= 0
XS Weighting Method= 0
Number of US Weighted Cross Sections= 1
Number of DS Weighted Cross Sections= 1
Upstream XS Weight=0.25
Main XS Weight=0.5
Downstream XS Weight=0.25
Number of DS XS's Weighted with US Boundary= 1
Upstream Boundary Weight= 1
Weight of XSs Associated with US Boundary= 0
Number of US XS's Weighted with DS Boundary= 1
Downstream Boundary Weight= 0.5
Weight of XSs Associated with DS Boundary= 0.5
Sediment Output Level= 4
Mass or Volume Output= 0
Output Increment Type= 1
Profile and TS Output Increment= 10
XS Output Flag= 0
XS Output Increment= 10
Disregard all LS=0
Disregard all Conn=0
Disregard all Breaches=0
Disregard all Pumps=0

--- SULPHUR BRANCH.f01 (steady flow) ---

Flow Title=Multiple
Number of Profiles=7
Profile Names=10-year,25-year,50-year,1pct_min,100-year,1pct_plu,500-year
River Rch & RM= SULPHUR BRANCH,Reach-1,23455
    1077    1781    2434    1611    3215    6414    5547
River Rch & RM= SULPHUR BRANCH,Reach-1,23115
    1365    2268    3107    2058    4106    8193    7099
River Rch & RM= SULPHUR BRANCH,Reach-1,17427
    2226    3791    5282    3551    7086   14138   12632
River Rch & RM= SULPHUR BRANCH,Reach-1,10732
    2238    3805    5294    3553    7089   14145   12597
River Rch & RM= SULPHUR BRANCH,Reach-1,9643
    2844    4859    6783    4562    9103   18162   16245
Boundary for River Rch & Prof#=SULPHUR BRANCH,Reach-1,1
Up Type=0
Dn Type=3
Dn Slope=0.005
Boundary for River Rch & Prof#=SULPHUR BRANCH,Reach-1,2
Up Type=0
Dn Type=3
Dn Slope=0.005
Boundary for River Rch & Prof#=SULPHUR BRANCH,Reach-1,3
Up Type=0
Dn Type=3
Dn Slope=0.005
Boundary for River Rch & Prof#=SULPHUR BRANCH,Reach-1,4
Up Type=0
Dn Type=3
Dn Slope=0.005
Boundary for River Rch & Prof#=SULPHUR BRANCH,Reach-1,5
Up Type=0
Dn Type=3
Dn Slope=0.005
Boundary for River Rch & Prof#=SULPHUR BRANCH,Reach-1,6
Up Type=0
Dn Type=3
Dn Slope=0.005
Boundary for River Rch & Prof#=SULPHUR BRANCH,Reach-1,7
Up Type=0
Dn Type=3
Dn Slope=0.005

--- SULPHUR BRANCH.g01 (geometry) ---

Geom Title=Existing Conditions
Program Version=4.10

River Reach=SULPHUR BRANCH  ,Reach-1
Reach XY= 30
        2544725.       13768225.       2544095.2     13768424.97
      2543773.72     13768028.37      2542995.28     13768024.62
      2542308.98     13768474.54      2540931.04     13768476.65
      2540673.42     13768721.18      2539818.55     13768882.74
       2539473.5     13769521.39      2538072.53     13769680.45
       2537961.8     13770138.74       2537414.5     13770473.78
      2536236.14     13770373.38      2536367.82     13770124.66
      2536226.29     13770078.37      2535479.97     13770822.42
      2535316.84     13771831.71      2535011.33     13771788.22
      2534585.95     13772214.98       2534538.3      13772511.6
      2533368.57     13772983.01      2532973.42     13773521.33
      2532022.23     13773480.36       2531927.7     13773869.64
      2530701.47     13774297.86      2530563.19     13774923.37
      2529772.71      13775069.2      2529480.83      13774777.3
      2529311.35     13774211.67        2528925.       13773925.

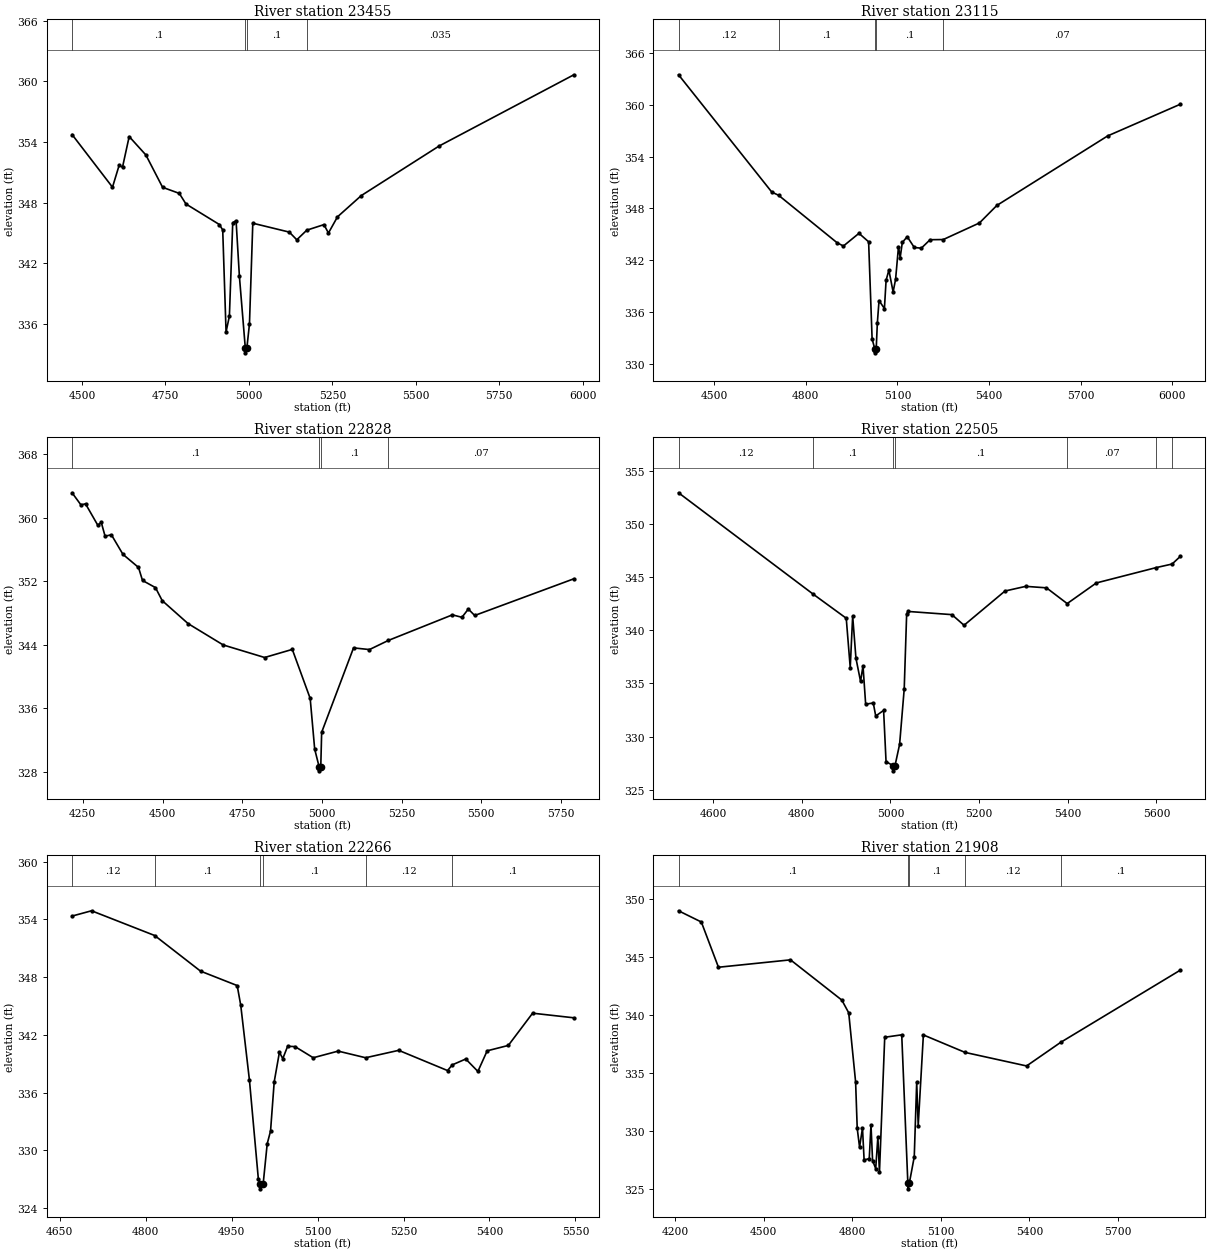
Type RM Length L Ch R = 1 ,23455   ,340,340,340
BEGIN DESCRIPTION:
SULPHUR BRANCH 31.0
END DESCRIPTION:
XS GIS Cut Line= 3
      2544633.54       13767734.      2544613.26      13768293.3
      2544781.02     13769221.79
#Sta/Elev= 30
  4470.2  354.74  4591.3  349.53  4611.3  351.71  4621.3  351.51  4641.3  354.54
  4691.3  352.72  4741.4  349.52  4791.4  348.92  4811.4  347.87  4911.5  345.84
  4921.5   345.3  4931.5  335.22  4941.5  336.78  4951.5  346.01  4961.5  346.22
  4971.5   340.7  4989.1  333.65  4989.5  333.15  4993.9  333.65  5001.6     336
  5011.6  345.97    5121  345.09  5143.4  344.33  5173.3  345.28  5224.7  345.83
  5238.2     345  5265.3   346.6  5336.5   348.7  5569.5   353.6  5973.4  360.65
#Mann= 4 ,-1 , 0
  4470.2      .1       0  4989.1     .05       0  4993.9      .1       0
  5173.3    .035       0
Bank Sta=4989.1,4993.9
XS Rating Curve= 0 ,0
Exp/Cntr=0.3,0.1

Type RM Length L Ch R = 1 ,23115   ,287,287,287
BEGIN DESCRIPTION:
XS7842
END DESCRIPTION:
XS GIS Cut Line= 3
      2544436.49     13767725.31      2544319.88     13768316.88
      2544749.45     13769264.07
#Sta/Elev= 30
  4383.2  363.47  4688.7  349.88  4710.7  349.52  4902.7  344.01  4923.1  343.64
    4974  345.11  5005.6  344.13    5017  332.88  5025.5  331.77  5025.9  331.27
  5030.5  331.77  5034.2  334.75  5039.7  337.32  5057.3   336.4  5062.8  339.67
  5071.9  340.85  5085.8  338.32  5093.9  339.79  5103.4  343.57  5108.9  342.29
  5115.9  344.05    5132  344.72  5155.1  343.47  5178.2  343.39  5206.8  344.37
    5250  344.39  5368.4  346.31  5425.5  348.34  5788.3  356.39  6026.2  360.06
#Mann= 5 ,-1 , 0
  4383.2     .12       0  4710.7      .1       0  5025.5     .05       0
  5030.5      .1       0    5250     .07       0
Bank Sta=5025.5,5030.5
XS Rating Curve= 0 ,0
Exp/Cntr=0.3,0.1

Type RM Length L Ch R = 1 ,22828   ,323,323,323
BEGIN DESCRIPTION:
SULPHUR BRANCH 30.0
END DESCRIPTION:
XS GIS Cut Line= 3
      2544343.77     13767678.92        2544075.       13768425.
      2544085.85     13769206.11
#Sta/Elev= 30
  4216.3  363.12    4244   361.6  4258.5  361.73  4297.2  359.02  4307.8  359.41
  4319.8  357.66  4339.7  357.83  4375.9  355.37  4424.7  353.72  4437.3  352.08
  4477.9  351.18  4499.1  349.54  4580.2  346.65  4690.4  343.96  4820.4  342.38
  4907.2   343.4  4963.3  337.23  4977.4  330.85  4991.4  328.61  4991.8  328.11
  4996.5  328.61  4999.3  332.96  5099.3  343.59  5149.3  343.38  5208.6  344.53
  5409.4  347.75  5439.4  347.44  5459.4  348.48  5479.4  347.67  5790.5  352.29
#Mann= 4 ,-1 , 0
  4216.3      .1       0  4991.4     .05       0  4996.5      .1       0
  5208.6     .07       0
Bank Sta=4991.4,4996.5
XS Rating Curve= 0 ,0
Exp/Cntr=0.3,0.1

Type RM Length L Ch R = 1 ,22505   ,239,239,239
BEGIN DESCRIPTION:
XS7839
END DESCRIPTION:
XS GIS Cut Line= 3
       2544068.8      13767759.2      2543857.48     13768234.67
      2544002.78     13768829.06
#Sta/Elev= 30
  4521.8  352.93  4825.8  343.39  4900.2  341.13  4909.2  336.49  4914.7  341.33
  4922.1  337.37  4932.5  335.19    4938  336.66    4944  333.05  4961.2  333.16
  4966.7  331.94  4984.5  332.46    4990  327.65  5005.2  327.28  5005.6  326.78
  5010.3  327.28  5020.6  329.27    5031  334.48  5036.5  341.52  5039.6  341.77
  5138.6  341.47    5166  340.47  5258.4  343.69  5305.2  344.13    5352  343.99
  5398.7  342.51  5464.5  344.45  5599.2  345.89  5635.5  346.23    5654  346.95
#Mann= 7 ,-1 , 0
  4521.8     .12       0  4825.8      .1       0  5005.2     .05       0
  5010.3      .1       0  5398.7     .07       0  5599.2     .12       0
  5635.5     .07       0
Bank Sta=5005.2,5010.3
XS Rating Curve= 0 ,0
Exp/Cntr=0.3,0.1

Type RM Length L Ch R = 1 ,22266   ,358,358,358
BEGIN DESCRIPTION:
XS7841
END DESCRIPTION:
XS GIS Cut Line= 3
      2543908.94     13767743.07      2543695.69     13768095.89
      2543850.38     13768532.87
#Sta/Elev= 30
  4671.5  354.34  4705.5  354.89  4815.7  352.32  4895.7  348.62  4959.7  347.12
  4965.9  345.07  4981.1  337.28  4996.6  327.04  4999.9   326.5  5000.3     326
    5005   326.5  5012.1  330.69  5017.9     332  5024.3  337.12  5033.4  340.19
  5039.3  339.53  5047.7  340.81  5060.6  340.78  5092.4  339.62  5135.9  340.31
  5183.9  339.62  5241.6  340.39  5326.8  338.29  5335.1  338.88  5358.6  339.49
  5379.8   338.2    5396  340.34  5432.9   340.9  5475.3  344.25  5547.3  343.77
#Mann= 6 ,-1 , 0
  4671.5     .12       0  4815.7      .1       0  4999.9     .05       0
    5005      .1       0  5183.9     .12       0  5335.1      .1       0
Bank Sta=4999.9,5005
XS Rating Curve= 0 ,0
Exp/Cntr=0.3,0.1

Type RM Length L Ch R = 1 ,21908   ,350,350,350
BEGIN DESCRIPTION:
SULPHUR BRANCH 29.0
END DESCRIPTION:
XS GIS Cut Line= 3
      2543743.89     13767354.45        2543425.       13768075.
      2543636.38     13768961.38
#Sta/Elev= 30
    4212  349.01  4289.2  348.04  4347.2  344.13  4591.1  344.77    4765  341.29
  4788.3  340.19  4811.6  334.22  4817.1   330.2    4825  328.58  4834.9  330.23
  4840.4  327.48  4857.8  327.59  4863.7  330.49  4869.1  327.42  4879.7  326.73
    4887  329.46  4892.4  326.42  4910.2  338.08  4967.8  338.29  4988.5  325.48
  4988.9  324.98  4993.6  325.48  5010.2  327.75  5018.5   334.2  5023.6  330.45
  5041.1  338.28  5182.3  336.77  5390.6   335.6  5505.5  337.63  5911.2  343.88
#Mann= 5 ,-1 , 0
    4212      .1       0  4988.5     .05       0  4993.6      .1       0
  5182.3     .12       0  5505.5      .1       0
Bank Sta=4988.5,4993.6
XS Rating Curve= 0 ,0
Exp/Cntr=0.3,0.1

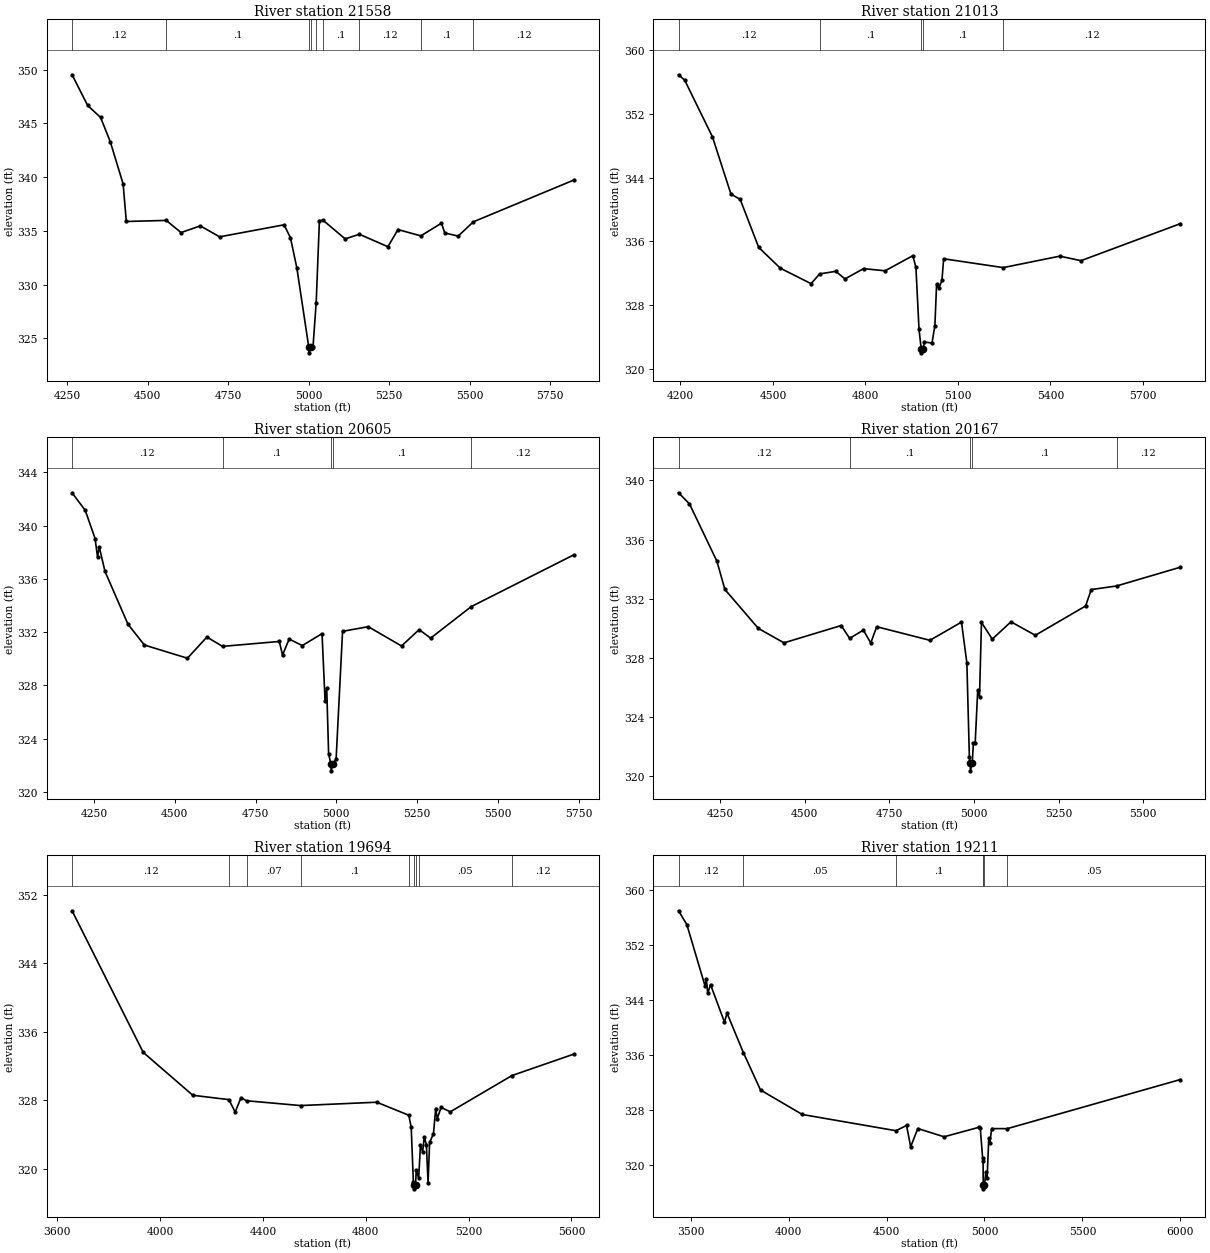
Type RM Length L Ch R = 1 ,21558   ,545,545,545
BEGIN DESCRIPTION:
XS7840
END DESCRIPTION:
XS GIS Cut Line= 3
      2543110.28     13767386.46      2543125.79     13768293.62
      2543303.89     13768920.83
#Sta/Elev= 30
  4264.5  349.53    4313  346.67    4353  345.56  4383.1  343.31  4423.1  339.37
  4433.1  335.87  4557.2  335.97  4603.1  334.84  4663.1  335.46  4723.1  334.44
  4923.1  335.56  4943.1  334.36  4963.1  331.53  5000.2  324.14  5000.7  323.64
    5006  324.14  5013.1  324.16  5023.1  328.32  5033.1  335.95    5045  335.97
  5113.2  334.25  5157.3  334.68    5246  333.52  5277.2  335.12  5348.2  334.53
  5412.3  335.71  5422.7   334.8  5464.3  334.51  5511.6  335.84  5823.8  339.73
#Mann= 9 ,-1 , 0
  4264.5     .12       0  4557.2      .1       0  5000.2     .05       0
    5006      .1       0  5023.1     .12       0    5045      .1       0
  5157.3     .12       0  5348.2      .1       0  5511.6     .12       0
Bank Sta=5000.2,5006
XS Rating Curve= 0 ,0
Exp/Cntr=0.3,0.1

Type RM Length L Ch R = 1 ,21013   ,408,408,408
BEGIN DESCRIPTION:
SULPHUR BRANCH 28.0
END DESCRIPTION:
XS GIS Cut Line= 3
        2542675.       13767325.        2542675.       13768125.
      2543024.98     13768874.96
#Sta/Elev= 30
    4194  356.92    4214  356.24    4304  349.12    4364  341.93    4394  341.26
    4454  335.23    4524  332.62    4624  330.67  4651.6   331.9    4704  332.22
    4734  331.27    4794  332.56    4864  332.29    4954  334.19    4964  332.71
    4974  324.95  4981.1  322.48  4981.5  321.98  4986.9  322.48  4991.5  323.34
  5016.1  323.21  5025.5  325.39    5031   330.6  5038.1  330.09  5048.4  331.07
  5053.9   333.8  5247.2  332.69  5430.7  334.13  5499.3  333.56  5821.6  338.21
#Mann= 5 ,-1 , 0
    4194     .12       0  4651.6      .1       0  4981.1     .05       0
  4986.9      .1       0  5247.2     .12       0
Bank Sta=4981.1,4986.9
XS Rating Curve= 0 ,0
Exp/Cntr=0.3,0.1

Type RM Length L Ch R = 1 ,20605   ,438,438,438
BEGIN DESCRIPTION:
SULPHUR BRANCH 27.0
END DESCRIPTION:
XS GIS Cut Line= 3
        2542575.       13767525.        2542425.       13768325.
      2542775.01     13768975.02
#Sta/Elev= 30
  4182.5  342.47  4223.2  341.15  4253.7  339.03  4261.3  337.64  4266.4  338.42
  4284.2  336.57  4355.5  332.59  4406.3  331.03  4539.4  330.04  4599.6  331.63
  4647.9  330.93  4823.5   331.3  4833.6  330.28    4854  331.48  4894.7  330.99
  4955.7  331.89  4965.1  326.84  4970.2  327.79  4976.1  322.84  4983.3  322.08
  4983.8  321.58  4989.2  322.08  4999.3  322.47  5019.2  332.06  5098.7  332.41
  5201.7  330.96    5256  332.19  5291.7  331.55  5417.4  333.92  5734.7  337.81
#Mann= 5 ,-1 , 0
  4182.5     .12       0  4647.9      .1       0  4983.3     .05       0
  4989.2      .1       0  5417.4     .12       0
Bank Sta=4983.3,4989.2
XS Rating Curve= 0 ,0
Exp/Cntr=0.3,0.1

Type RM Length L Ch R = 1 ,20167   ,473,473,473
BEGIN DESCRIPTION:
SULPHUR BRANCH 26.0
END DESCRIPTION:
XS GIS Cut Line= 3
      2542474.98     13767575.04        2542125.       13768375.
      2542327.12     13768948.77
#Sta/Elev= 30
  4127.8  339.17  4160.1  338.42  4241.2  334.54  4264.6  332.64  4363.6     330
  4439.2  329.03    4608   330.2    4633  329.33  4673.5  329.89  4695.3  329.02
  4712.9  330.12    4870   329.2  4963.2  330.43  4979.1  327.66  4986.5  321.29
    4989  320.88  4989.5  320.38    4995  320.88  4998.2  322.24  5003.6  322.24
  5011.1  325.82  5016.4  325.39  5022.2  330.41    5054  329.28  5109.3  330.45
  5181.2  329.54  5329.6  331.52  5346.3  332.63  5420.9  332.87  5609.3  334.14
#Mann= 5 ,-1 , 0
  4127.8     .12       0    4633      .1       0    4989     .05       0
    4995      .1       0  5420.9     .12       0
Bank Sta=4989,4995
XS Rating Curve= 0 ,0
Exp/Cntr=0.3,0.1

Type RM Length L Ch R = 1 ,19694   ,483,483,483
BEGIN DESCRIPTION:
SULPHUR BRANCH 25.0
END DESCRIPTION:
XS GIS Cut Line= 3
      2542325.02     13767374.97        2541725.       13768575.
      2542224.99       13768925.
#Sta/Elev= 30
  3657.5  350.12  3934.3  333.61  4127.1  328.61  4267.7   328.1    4292  326.64
  4314.4  328.31  4336.2  327.97  4546.2  327.41  4842.7   327.8  4967.5  326.28
  4976.8  324.86  4985.2  318.48  4987.7   318.2  4988.2   317.7  4993.8   318.2
  4996.4  319.91  5005.8  318.94  5012.7  322.79  5021.4  322.02  5027.5  323.75
  5035.8  322.85  5042.3  318.37  5048.4  323.11  5063.3  324.12    5072  327.06
  5078.1  325.88  5092.9  327.19  5128.7  326.68  5368.8  330.91  5609.5  333.41
#Mann= 9 ,-1 , 0
  3657.5     .12       0  4267.7     .05       0  4336.2     .07       0
  4546.2      .1       0  4967.5     .07       0  4987.7     .05       0
  4993.8     .07       0  5005.8     .05       0  5368.8     .12       0
Bank Sta=4987.7,4993.8
XS Rating Curve= 0 ,0
Exp/Cntr=0.3,0.1

Type RM Length L Ch R = 1 ,19211   ,446,446,446
BEGIN DESCRIPTION:
SULPHUR BRANCH 24.0
END DESCRIPTION:
XS GIS Cut Line= 3
      2542274.98     13767275.03        2541275.       13768475.
      2541874.99     13769274.99
#Sta/Elev= 30
  3438.1  356.99  3480.4  354.99  3572.8  346.12  3580.6  347.01  3587.1  344.97
  3601.4  346.26  3672.4  340.82    3686  342.08  3769.1  336.37  3856.6  330.93
    4070  327.37  4548.2  325.01  4602.4  325.78  4623.3  322.67  4659.7  325.33
  4793.8  324.13  4972.1  325.51  4978.6  325.42  4990.7  321.05    4993  320.67
  4993.8  317.06  4994.3  316.56    5000  317.06  5007.4  319.07  5013.7  318.15
    5022  323.88  5028.2  323.28  5036.6  325.32  5116.4  325.31  6000.1  332.45
#Mann= 7 ,-1 , 0
  3438.1     .12       0  3769.1     .05       0  4548.2      .1       0
  4990.7     .07       0  4993.8     .05       0    5000     .07       0
  5116.4     .05       0
Bank Sta=4993.8,5000
XS Rating Curve= 0 ,0
Exp/Cntr=0.3,0.1

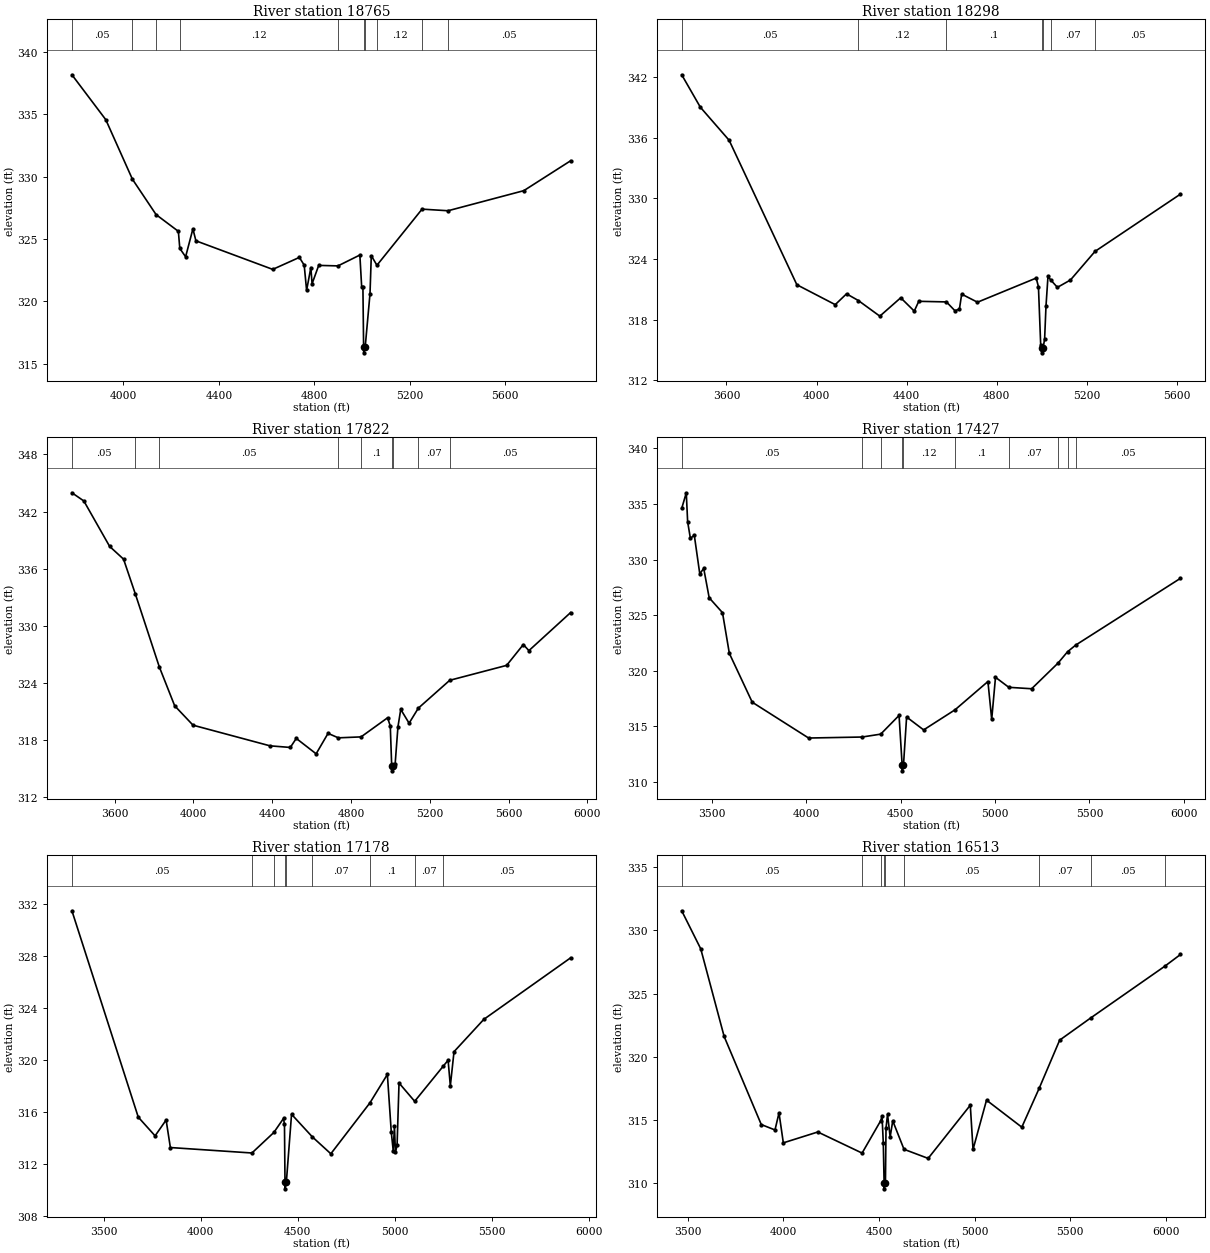
Type RM Length L Ch R = 1 ,18765   ,467,467,467
BEGIN DESCRIPTION:
SULPHUR BRANCH 23.0
END DESCRIPTION:
XS GIS Cut Line= 3
      2541074.99     13767325.04        2540875.       13768525.
      2541224.99     13769324.98
#Sta/Elev= 30
  3784.3  338.16  3926.2  334.56  4037.7  329.79    4137  326.95  4230.3  325.61
  4236.3  324.24  4260.7  323.57  4291.2  325.81  4303.8  324.85  4625.7  322.56
  4737.2  323.52  4757.5   322.9  4767.6  320.88  4785.4  322.71  4790.5  321.41
  4818.3  322.88    4899  322.84  4990.7  323.71  4998.3  321.15  5003.5  321.15
  5006.4  316.37  5006.9  315.87  5013.2  316.37  5033.2  320.61  5038.6  323.66
  5062.2  322.89  5251.3  327.39  5360.1  327.26  5677.6  328.87    5874  331.27
#Mann= 10 ,-1 , 0
  3784.3     .05       0  4037.7     .07       0    4137     .05       0
  4236.3     .12       0    4899      .1       0  5006.4     .05       0
  5013.2      .1       0  5062.2     .12       0  5251.3     .07       0
  5360.1     .05       0
Bank Sta=5006.4,5013.2
XS Rating Curve= 0 ,0
Exp/Cntr=0.3,0.1

Type RM Length L Ch R = 1 ,18298   ,476,476,476
BEGIN DESCRIPTION:
SULPHUR BRANCH 22.0
END DESCRIPTION:
XS GIS Cut Line= 3
        2540425.       13767175.        2540525.       13768775.
      2540874.97     13769274.96
#Sta/Elev= 30
  3401.4  342.24  3484.1  339.03  3611.8  335.76  3912.4  321.46  4082.7  319.49
  4132.8  320.56  4185.1   319.9  4280.6  318.35  4373.3  320.17  4433.4  318.85
  4453.4  319.82  4576.1  319.76  4613.8  318.89  4633.8  319.05  4643.8  320.53
    4714  319.73  4974.5  322.12  4984.5  321.26  4994.5  315.48  4998.6  315.22
  4999.1  314.72  5005.5  315.22  5011.9   316.1    5018  319.35  5026.8  322.28
  5039.9  321.91  5068.6   321.2  5126.6  321.93  5235.6  324.76  5614.8  330.43
#Mann= 7 ,-1 , 0
  3401.4     .05       0  4185.1     .12       0  4576.1      .1       0
  4998.6     .05       0  5005.5      .1       0  5039.9     .07       0
  5235.6     .05       0
Bank Sta=4998.6,5005.5
XS Rating Curve= 0 ,0
Exp/Cntr=0.3,0.1

Type RM Length L Ch R = 1 ,17822   ,395,395,395
BEGIN DESCRIPTION:
SULPHUR BRANCH 21.0
END DESCRIPTION:
XS GIS Cut Line= 3
      2540275.01     13767174.96        2540075.       13768775.
      2540724.98     13769424.98
#Sta/Elev= 30
    3383  343.97  3443.5  343.11  3574.5  338.33  3645.1  336.99  3705.4   333.3
  3826.6  325.66  3904.6  321.57  3997.8  319.53  4388.3  317.36  4491.6  317.19
  4521.8  318.14  4622.6  316.52  4683.1  318.67  4735.3   318.2  4850.7   318.3
  4985.4  320.31    4999  319.44  5006.2  315.23  5006.7  314.73  5013.1  315.23
  5023.8  315.49  5037.9  319.36  5052.1  321.19  5094.5  319.74  5141.3  321.32
  5300.7  324.25  5589.5  325.82  5674.3  328.01  5702.6  327.37  5914.7  331.38
#Mann= 9 ,-1 , 0
    3383     .05       0  3705.4     .07       0  3826.6     .05       0
  4735.3     .07       0  4850.7      .1       0  5006.2     .05       0
  5013.1      .1       0  5141.3     .07       0  5300.7     .05       0
Bank Sta=5006.2,5013.1
XS Rating Curve= 0 ,0
Exp/Cntr=0.3,0.1

Type RM Length L Ch R = 1 ,17427   ,249,249,249
BEGIN DESCRIPTION:
SULPHUR BRANCH 20.0
END DESCRIPTION:
XS GIS Cut Line= 5
      2538420.16     13768295.86      2538906.25     13768920.83
      2539839.41     13768972.92      2540169.27     13768925.17
      2540580.76     13769336.67
#Sta/Elev= 30
  3340.8  334.59    3365     336  3372.2  333.39  3386.7  331.91  3407.5  332.18
  3436.5  328.71  3457.3   329.2  3486.3  326.56  3556.8  325.22  3593.1  321.56
  3714.3  317.17  4012.9  313.95  4296.2  314.04  4394.7   314.3  4491.9  315.98
  4508.4   311.5  4508.9     311  4515.3   311.5  4531.9  315.84  4622.1  314.68
  4788.6  316.49  4962.6  319.03  4982.6  315.63  5002.7  319.41  5073.2  318.51
  5194.1  318.38  5334.1  320.69  5384.4  321.71  5427.8  322.31  5982.4  328.31
#Mann= 10 ,-1 , 0
  3340.8     .05       0  4296.2     .07       0  4394.7     .12       0
  4508.4     .05       0  4515.3     .12       0  4788.6      .1       0
  5073.2     .07       0  5334.1      .1       0  5384.4     .07       0
  5427.8     .05       0
Bank Sta=4508.4,4515.3
XS Rating Curve= 0 ,0
Exp/Cntr=0.3,0.1

Type RM Length L Ch R = 1 ,17178   ,665,665,665
BEGIN DESCRIPTION:
SULPHUR BRANCH 19.0
END DESCRIPTION:
XS GIS Cut Line= 6
      2538398.45     13768365.29      2538879.13     13769070.57
      2539444.44     13769163.89      2539765.63     13769185.59
      2540125.87     13769120.49      2540520.38     13769354.59
#Sta/Elev= 30
  3334.8  331.51  3677.1  315.62  3763.9  314.18  3820.8   315.4  3842.7  313.28
  4263.5  312.86  4376.6  314.44  4426.4  315.52  4431.4  315.07  4434.1   310.6
  4434.6   310.1    4441   310.6  4467.9  315.84  4575.2   314.1  4670.6   312.8
  4872.3  316.72  4962.3  318.91  4982.3  314.49  4992.4  313.05  4998.8  314.91
  5003.8   312.9  5012.4  313.47  5022.4  318.25  5103.1  316.84  5251.2  319.56
  5275.6     320  5287.1  318.03  5306.1  320.66  5459.9  323.15    5908  327.89
#Mann= 9 ,-1 , 0
  3334.8     .05       0  4263.5     .07       0  4376.6     .12       0
  4434.1     .05       0    4441     .12       0  4575.2     .07       0
  4872.3      .1       0  5103.1     .07       0  5251.2     .05       0
Bank Sta=4434.1,4441
XS Rating Curve= 0 ,0
Exp/Cntr=0.3,0.1

Type RM Length L Ch R = 1 ,16513   ,395,395,395
BEGIN DESCRIPTION:
SULPHUR BRANCH 18.0
END DESCRIPTION:
XS GIS Cut Line= 4
      2538363.71      13768347.9      2538875.87      13769090.1
        2539275.       13769575.      2540274.97     13769974.99
#Sta/Elev= 30
  3469.3  331.56  3568.7  328.55  3691.1  321.61  3885.1  314.64  3956.8  314.21
  3977.8  315.56  4000.4  313.19  4180.6  314.05    4412  312.38  4509.3  314.94
  4516.3   315.3  4522.8  313.21  4527.1  310.05  4527.6  309.55  4534.1  310.05
  4537.1  314.35    4545  315.45  4558.7  313.66  4572.3  314.93  4631.1  312.68
  4757.3  311.96  4977.6  316.17  4991.9  312.67  5062.4  316.57  5246.8  314.43
  5338.5  317.54  5444.7  321.32  5607.2  323.08  5993.2  327.16  6076.1   328.1
#Mann= 9 ,-1 , 0
  3469.3     .05       0    4412     .07       0  4509.3     .12       0
  4527.1     .05       0  4534.1     .12       0  4631.1     .05       0
  5338.5     .07       0  5607.2     .05       0  5993.2     .07       0
Bank Sta=4527.1,4534.1
XS Rating Curve= 0 ,0
Exp/Cntr=0.3,0.1

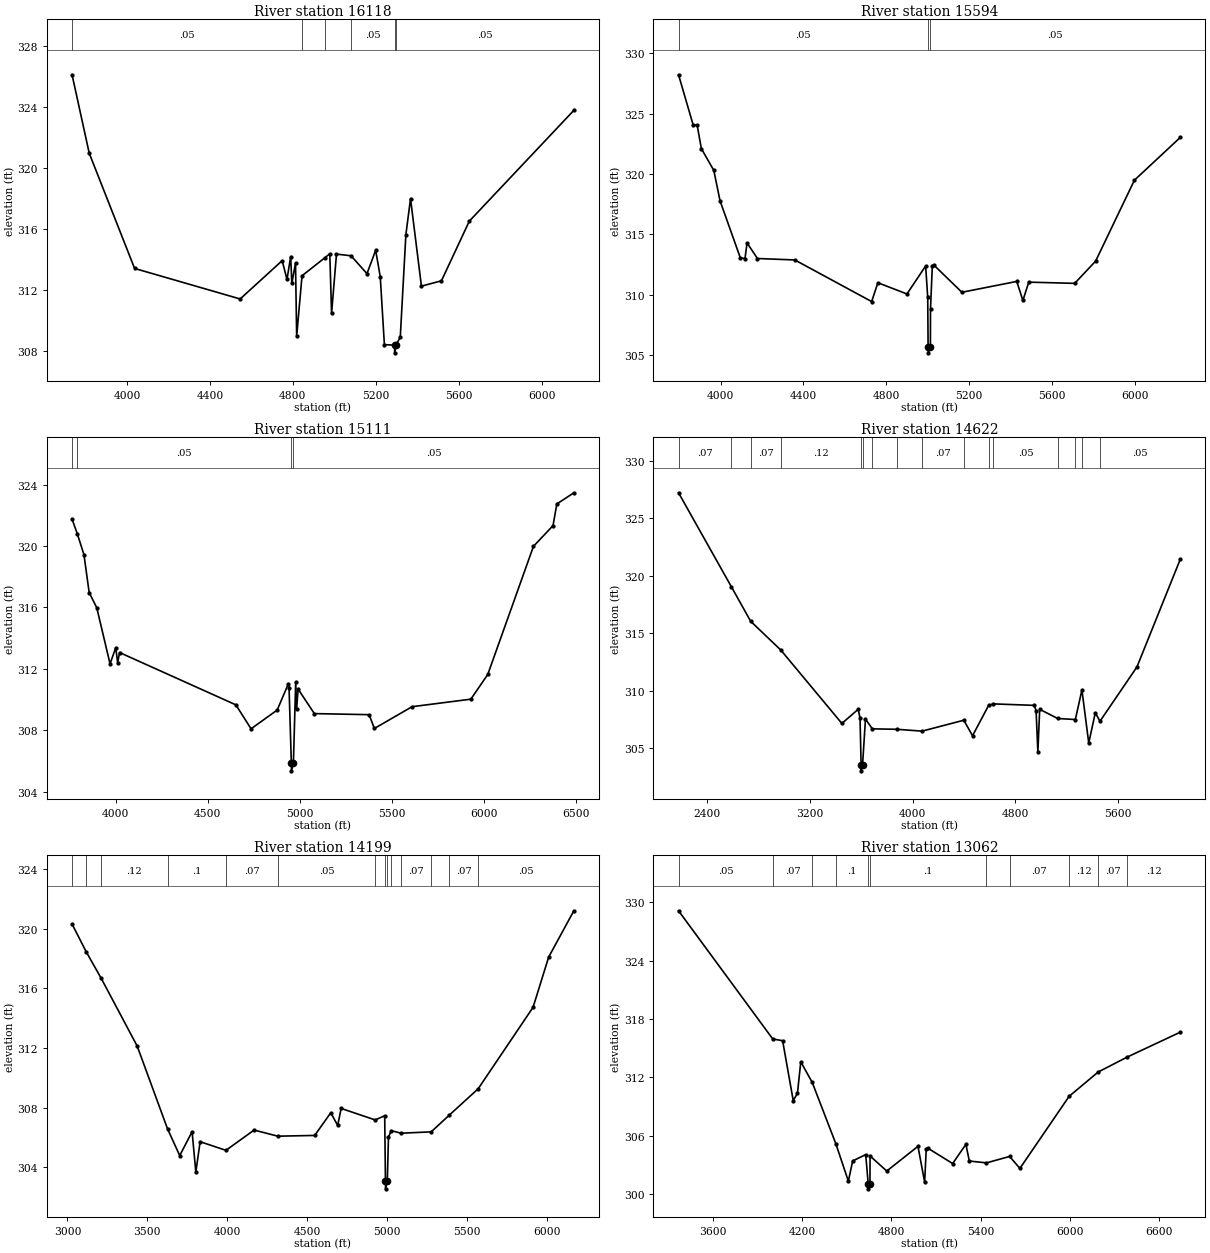
Type RM Length L Ch R = 1 ,16118   ,524,524,524
BEGIN DESCRIPTION:
SULPHUR BRANCH 17.0
END DESCRIPTION:
XS GIS Cut Line= 3
      2538411.46     13768469.45      2538923.61     13769623.96
      2539275.01     13770725.04
#Sta/Elev= 30
  3735.8  326.09  3818.5  320.95  4037.2   313.4    4546   311.4  4748.5  313.91
  4771.8  312.68  4789.6  314.18  4795.1  312.43  4812.9  313.75  4818.4  308.96
  4844.3  312.92  4953.3  314.09  4978.1  314.36  4986.7  310.46  5010.4  314.34
  5080.4  314.23  5157.4  313.06  5199.3  314.59  5221.4  312.85  5241.3  308.41
  5290.3  308.37  5290.8  307.87  5297.3  308.37  5317.9  308.91  5344.9  315.62
  5367.3  317.97  5419.8  312.24  5516.3  312.59  5650.7   316.5  6154.6  323.76
#Mann= 6 ,-1 , 0
  3735.8     .05       0  4844.3     .12       0  4953.3     .07       0
  5080.4     .05       0  5290.3     .05       0  5297.3     .05       0
Bank Sta=5290.3,5297.3
XS Rating Curve= 0 ,0
Exp/Cntr=0.3,0.1

Type RM Length L Ch R = 1 ,15594   ,483,483,483
BEGIN DESCRIPTION:
SULPHUR BRANCH 16.0
END DESCRIPTION:
XS GIS Cut Line= 3
        2538375.     13768425.05        2538475.       13769625.
      2539175.02     13770625.03
#Sta/Elev= 30
  3796.2  328.22  3866.4  324.09  3886.5  324.02  3906.5   322.1  3966.7  320.29
  3996.8  317.77  4094.7  313.05  4117.3  312.98  4127.3  314.28  4177.5  312.99
  4358.1  312.87  4729.4  309.42  4759.5  310.98    4900  310.05  4990.3  312.37
  5000.3  309.78  5002.2  305.67  5002.7  305.17  5013.3  305.67  5013.8  308.82
  5022.5  312.35  5028.6  312.47  5165.5  310.19  5430.6  311.09  5460.2  309.51
  5488.6  311.03  5710.5  310.93  5811.6  312.77  5999.1  319.48    6221  323.03
#Mann= 3 ,-1 , 0
  3796.2     .05       0  5002.2     .05       0  5013.3     .05       0
Bank Sta=5002.2,5013.3
XS Rating Curve= 0 ,0
Exp/Cntr=0.3,0.1

Type RM Length L Ch R = 1 ,15111   ,489,489,489
BEGIN DESCRIPTION:
SULPHUR BRANCH 15.0
END DESCRIPTION:
XS GIS Cut Line= 3
      2538325.01     13768524.97        2538025.       13769725.
      2539125.03     13770725.02
#Sta/Elev= 30
    3764  321.75  3792.3   320.8  3828.5  319.44  3856.8  316.97    3898  315.98
  3970.2  312.32  4001.1  313.38  4011.4  312.39  4021.7  313.06  4653.1  309.65
  4735.5  308.09  4877.3  309.31  4936.5  310.98  4941.7  310.78  4954.2  305.85
  4954.7  305.35  4965.3  305.85  4977.8  311.13  4982.9  309.38  4990.7  310.68
    5079  309.08  5376.3  309.01  5404.7  308.11  5609.5  309.53  5928.4  310.02
  6020.3  311.63  6268.3  319.98  6374.4  321.33  6395.3  322.74  6487.6  323.47
#Mann= 4 ,-1 , 0
    3764    .035       0  3792.3     .05       0  4954.2     .05       0
  4965.3     .05       0
Bank Sta=4954.2,4965.3
XS Rating Curve= 0 ,0
Exp/Cntr=0.3,0.1

Type RM Length L Ch R = 1 ,14622   ,423,423,423
BEGIN DESCRIPTION:
SULPHUR BRANCH 14.0
END DESCRIPTION:
XS GIS Cut Line= 3
      2535925.03     13768175.03        2537925.       13770175.
      2538825.04     13770775.03
#Sta/Elev= 30
  2175.7  327.21    2588  319.03  2737.8  316.04  2972.6  313.54  3448.5  307.16
  3575.7  308.39  3589.9  307.63  3598.5  303.54    3599  303.04  3609.6  303.54
  3632.3  307.54    3686  306.69  3880.2  306.65  4073.3  306.49  4398.5  307.44
  4466.7  306.09  4591.6  308.72  4628.4  308.86  4947.5  308.73  4961.7  308.28
  4975.8  304.69  4989.9  308.39  5130.2  307.59  5267.8   307.5    5319  310.07
  5372.2  305.46  5423.2  308.09  5459.6  307.35  5747.7  312.07  6085.8  321.44
#Mann= 16 ,-1 , 0
  2175.7     .07       0    2588     .12       0  2737.8     .07       0
  2972.6     .12       0  3598.5     .05       0  3609.6     .12       0
    3686     .07       0  3880.2     .05       0  4073.3     .07       0
  4398.5     .05       0  4591.6     .07       0  4628.4     .05       0
  5130.2     .07       0  5267.8     .05       0    5319     .07       0
  5459.6     .05       0
Bank Sta=3598.5,3609.6
XS Rating Curve= 0 ,0
Exp/Cntr=0.3,0.1

Type RM Length L Ch R = 1 ,14199   ,1137,1137,1137
BEGIN DESCRIPTION:
SULPHUR BRANCH 13.0
END DESCRIPTION:
XS GIS Cut Line= 3
      2536025.03     13769225.02        2537625.       13770375.
      2538724.96     13770774.99
#Sta/Elev= 30
  3029.1   320.3  3117.1  318.45  3211.5  316.66  3436.7  312.12  3626.7  306.57
    3703  304.78  3780.4  306.38  3803.7  303.67  3830.7  305.71  3992.2  305.13
  4168.3  306.49    4317  306.08  4547.7  306.13  4648.4  307.65  4691.6   306.8
  4713.4  307.94  4926.2  307.17  4985.9  307.45  4990.6  303.05  4991.1  302.55
  5002.2  303.05  5009.4     306  5026.4  306.45  5088.4  306.28  5276.8  306.37
  5390.1  307.49  5571.1  309.26  5914.6  314.72  6012.3  318.09  6169.9  321.19
#Mann= 14 ,-1 , 0
  3029.1     .05       0  3117.1     .07       0  3211.5     .12       0
  3626.7      .1       0  3992.2     .07       0    4317     .05       0
  4926.2     .07       0  4990.6     .05       0  5002.2     .07       0
  5026.4     .05       0  5088.4     .07       0  5276.8     .05       0
  5390.1     .07       0  5571.1     .05       0
Bank Sta=4990.6,5002.2
XS Rating Curve= 0 ,0
Exp/Cntr=0.3,0.1

Type RM Length L Ch R = 1 ,13062   ,1543,1543,1543
BEGIN DESCRIPTION:
XS7838
END DESCRIPTION:
XS GIS Cut Line= 4
      2535456.98     13769251.74      2536407.95     13769991.39
      2536738.16     13770678.22       2537887.3     13771483.94
#Sta/Elev= 30
  3370.1  329.12  4002.8  315.94  4069.2  315.76  4140.4  309.61  4168.7  310.34
  4191.1  313.59  4268.1  311.47  4426.1  305.19  4510.8  301.32  4539.7   303.4
  4627.3  304.05  4644.1  301.03  4644.6  300.53  4655.8  301.03  4656.5  303.91
  4768.6  302.36  4978.3   304.9  5023.2  301.21  5033.8  304.63  5045.8   304.7
  5211.3  303.13  5300.3  305.11    5323  303.39  5438.5   303.2  5593.9  303.86
  5662.8  302.63  5993.4  310.04  6188.5  312.54  6383.7  314.08  6740.4  316.64
#Mann= 11 ,-1 , 0
  3370.1     .05       0  4002.8     .07       0  4268.1     .12       0
  4426.1      .1       0  4644.1     .05       0  4655.8      .1       0
  5438.5     .12       0  5593.9     .07       0  5993.4     .12       0
  6188.5     .07       0  6383.7     .12       0
Bank Sta=4644.1,4655.8
XS Rating Curve= 0 ,0
Exp/Cntr=0.3,0.1