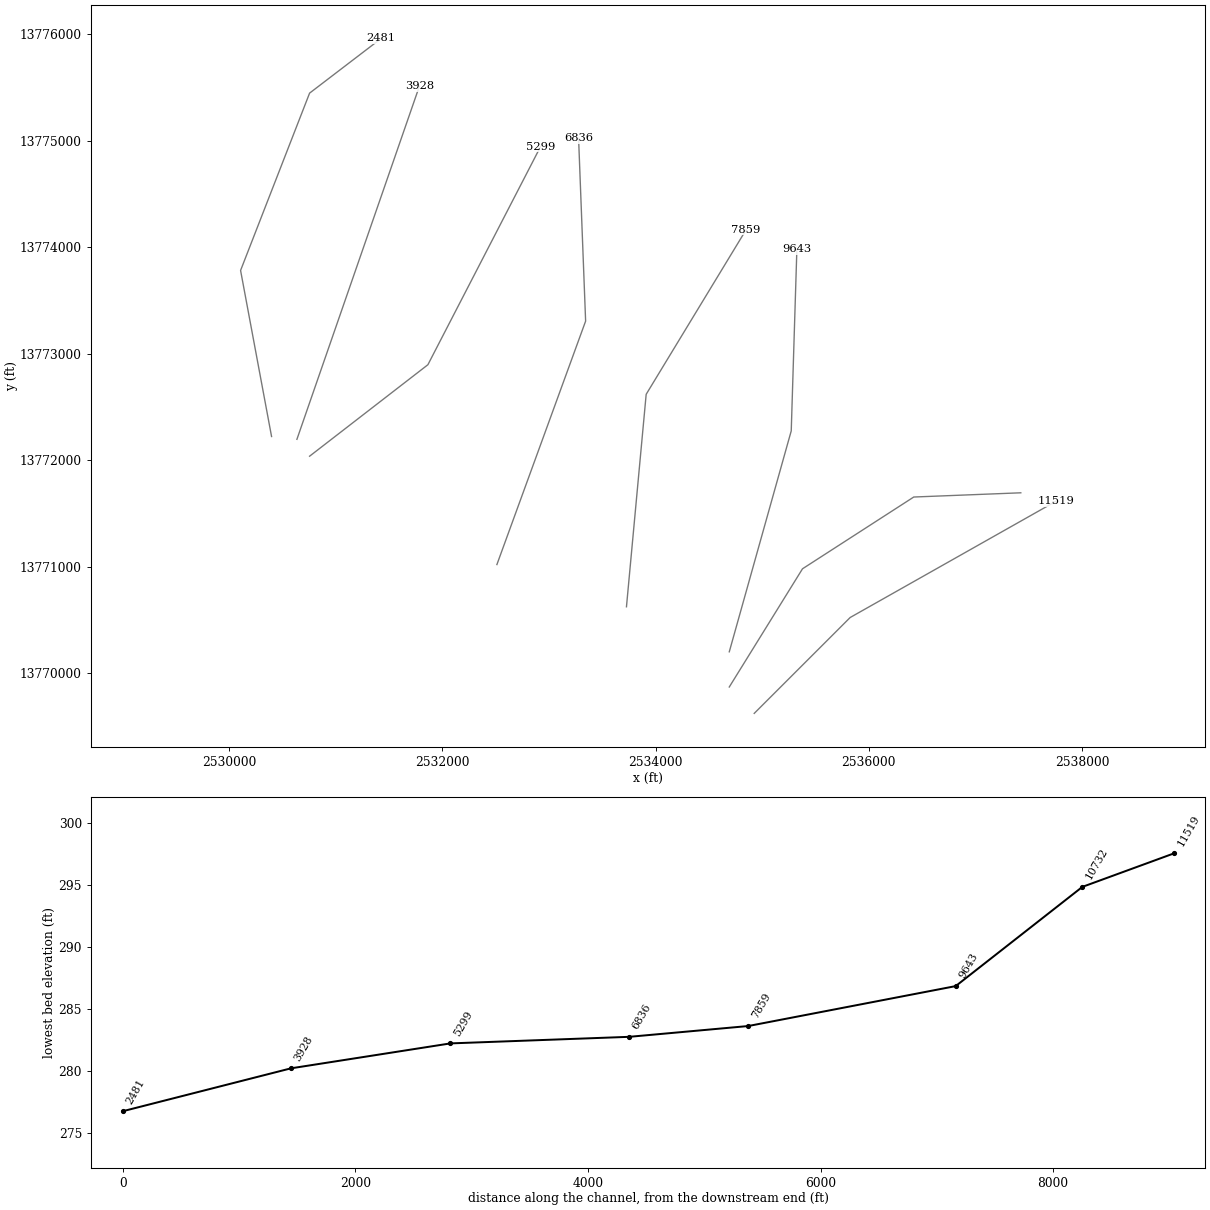
HEC-RAS study SULPHUR BRANCH.prj: SULPHUR BRANCH Base Level Engineering

--- SULPHUR BRANCH.g01 (geometry) --- (continued)

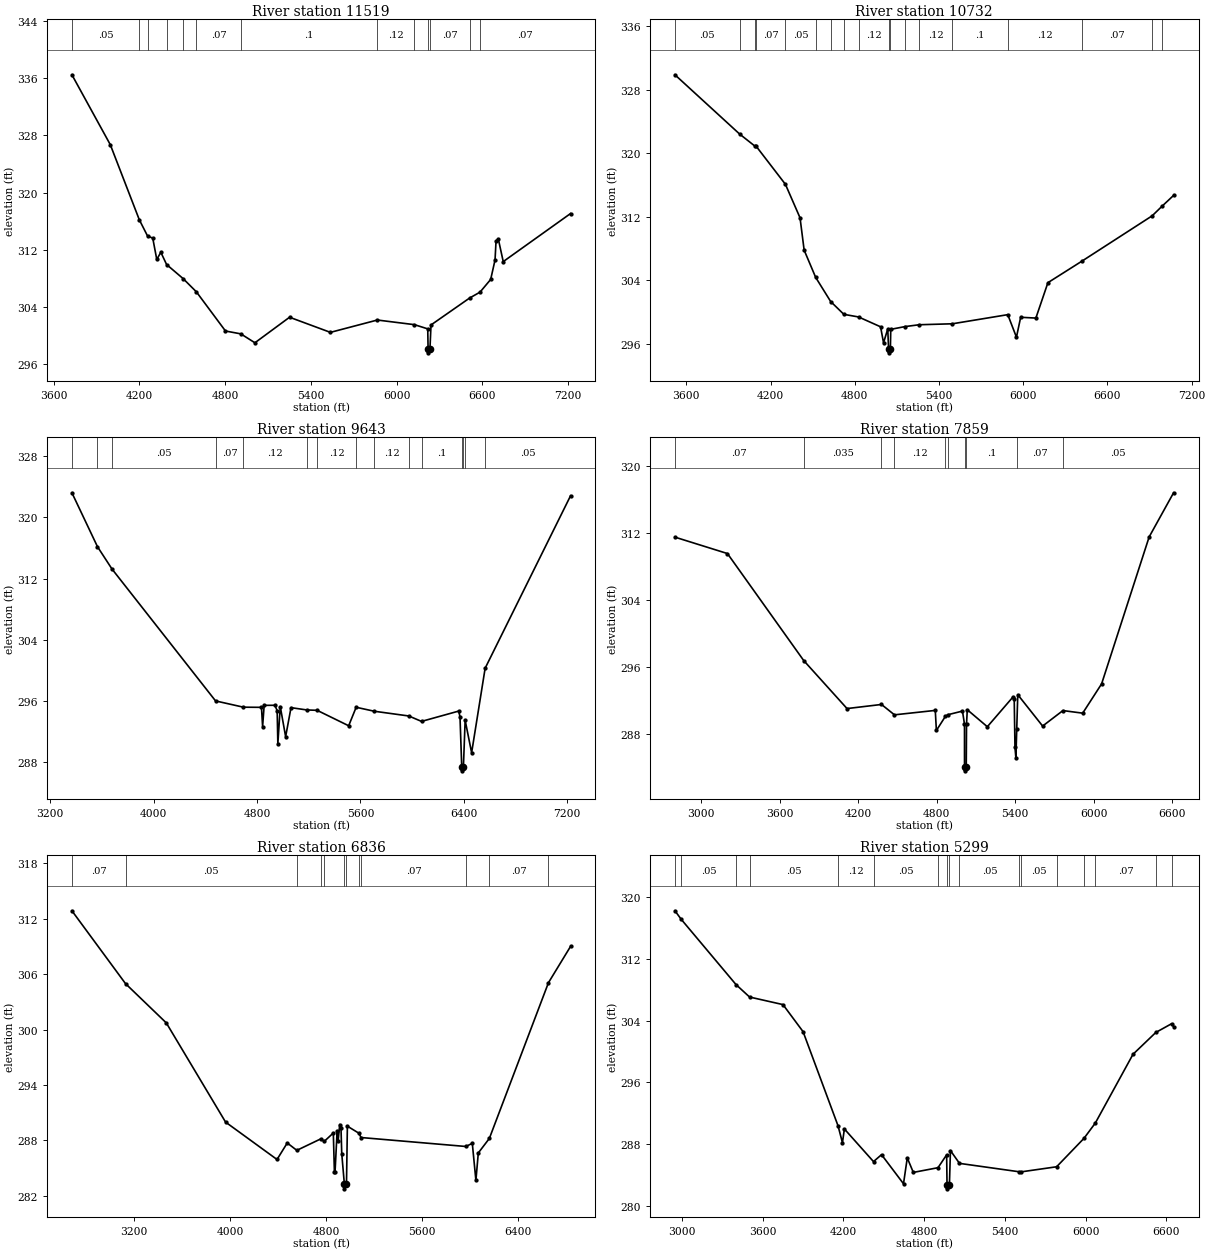
Type RM Length L Ch R = 1 ,11519   ,787,787,787
BEGIN DESCRIPTION:
SULPHUR BRANCH 12.0
END DESCRIPTION:
XS GIS Cut Line= 3
      2534924.98     13769624.98        2535825.       13770525.
      2537755.18       13771616.
#Sta/Elev= 30
  3727.2  336.51  3995.9  326.71    4199  316.18  4257.3  313.88  4292.9  313.62
  4321.2  310.62  4349.5  311.63  4389.9  309.91  4505.3  307.94    4598  306.09
    4802  300.59  4909.3  300.19    5008  298.94  5250.5  302.52  5536.4   300.4
  5864.9  302.13  6124.4  301.48  6217.6  300.89  6220.1  298.03  6220.6  297.53
  6232.9  298.03  6240.6  301.44  6510.4  305.21  6583.5  306.04  6658.1  307.82
  6688.6  310.55  6695.6   313.2  6711.5  313.49    6746  310.32  7217.2  317.06
#Mann= 13 ,-1 , 0
  3727.2     .05       0    4199     .07       0  4257.3     .05       0
  4389.9     .07       0  4505.3     .05       0    4598     .07       0
  4909.3      .1       0  5864.9     .12       0  6124.4     .07       0
  6220.1     .05       0  6232.9     .07       0  6510.4     .12       0
  6583.5     .07       0
Bank Sta=6220.1,6232.9
XS Rating Curve= 0 ,0
Exp/Cntr=0.3,0.1

Type RM Length L Ch R = 1 ,10732   ,1089,1089,1089
BEGIN DESCRIPTION:
XS7837
END DESCRIPTION:
XS GIS Cut Line= 4
      2534690.88     13769872.54       2535377.7     13770982.02
      2536421.16     13771655.64      2537425.01     13771695.27
#Sta/Elev= 30
  3519.3  329.86  3980.3  322.39  4090.6  320.85  4094.7  320.93  4306.3  316.06
  4410.4  311.84  4439.6  307.77  4521.9  304.33  4628.7  301.29  4722.5  299.68
  4827.2  299.35    4984  298.11  5005.1  296.09  5035.2  297.85  5040.9  295.33
  5041.4  294.83  5053.8  295.33  5056.6  297.79  5158.9  298.14  5259.7  298.37
  5495.3  298.49  5889.9  299.64  5951.7   296.8  5981.7  299.31    6090  299.21
  6175.8  303.67  6419.7   306.4  6918.1  312.09    6988  313.29  7070.8  314.66
#Mann= 18 ,-1 , 0
  3519.3     .05       0  3980.3     .07       0  4090.6     .05       0
  4094.7     .07       0  4306.3     .05       0  4521.9     .07       0
  4628.7     .12       0  4722.5     .07       0  4827.2     .12       0
  5040.9     .05       0  5053.8     .12       0  5158.9     .07       0
  5259.7     .12       0  5495.3      .1       0  5889.9     .12       0
  6419.7     .07       0  6918.1     .12       0    6988     .07       0
Bank Sta=5040.9,5053.8
XS Rating Curve= 0 ,0
Exp/Cntr=0.3,0.1

Type RM Length L Ch R = 1 ,9643    ,1784,1784,1784
BEGIN DESCRIPTION:
SULPHUR BRANCH 11.0
END DESCRIPTION:
XS GIS Cut Line= 3
      2534690.87     13770202.75      2535272.03     13772276.44
      2535324.86     13773980.14
#Sta/Elev= 30
  3367.7  323.22  3565.6  316.16  3677.9  313.24  4479.2  295.98  4694.5  295.16
  4834.4  295.14  4843.1  292.62  4855.1   295.4  4938.2  295.41  4955.8   294.7
    4961  290.37  4979.8  295.24  5021.3   291.3  5062.8   295.1  5184.3   294.8
  5264.9  294.75    5509  292.73  5566.9  295.15  5706.8  294.63  5974.1  294.01
  6072.7   293.3  6360.2  294.65  6370.3  293.91  6383.8  287.33  6384.3  286.83
  6396.7  287.33  6410.2  293.45  6460.3   289.2  6564.9  300.26  7225.8  322.83
#Mann= 15 ,-1 , 0
  3367.7     .05       0  3565.6     .07       0  3677.9     .05       0
  4479.2     .07       0  4694.5     .12       0  5184.3     .07       0
  5264.9     .12       0  5566.9     .07       0  5706.8     .12       0
  5974.1     .07       0  6072.7      .1       0  6383.8     .05       0
  6396.7      .1       0  6410.2     .07       0  6564.9     .05       0
Bank Sta=6383.8,6396.7
XS Rating Curve= 0 ,0
Exp/Cntr=0.3,0.1

Type RM Length L Ch R = 1 ,7859    ,1023,1023,1023
BEGIN DESCRIPTION:
SULPHUR BRANCH 10.0
END DESCRIPTION:
XS GIS Cut Line= 3
      2533726.65     13770625.37      2533911.57     13772619.86
      2534849.36     13774165.23
#Sta/Elev= 30
  2800.8  311.53  3202.1  309.57  3784.8  296.79    4116  291.05  4379.4  291.54
  4478.5   290.3  4790.4  290.83  4798.9  288.43  4868.1  290.13  4887.9  290.32
  4998.2  290.75  5013.7  289.18  5013.8  284.11  5014.3  283.61  5027.1  284.11
  5029.2  289.18    5035  290.91  5188.2  288.88    5384  292.43  5393.6  292.23
  5399.5   286.4  5406.4  285.17    5413  288.63  5420.8  292.71  5610.8  288.96
  5765.9  290.81    5917   290.5  6061.5     294  6424.9  311.56  6611.5  316.83
#Mann= 10 ,-1 , 0
  2800.8     .07       0  3784.8    .035       0  4379.4     .07       0
  4478.5     .12       0  4868.1     .07       0  4887.9      .1       0
  5013.8     .05       0  5027.1      .1       0    5413     .07       0
  5765.9     .05       0
Bank Sta=5013.8,5027.1
XS Rating Curve= 0 ,0
Exp/Cntr=0.3,0.1

Type RM Length L Ch R = 1 ,6836    ,1537,1537,1537
BEGIN DESCRIPTION:
XS7836
END DESCRIPTION:
XS GIS Cut Line= 3
      2532511.47     13771021.61      2533343.61     13773306.69
      2533277.64     13775021.94
#Sta/Elev= 30
  2685.3  312.87  3131.6  304.97  3470.6  300.72  3963.8  289.97  4391.7  285.92
  4476.8  287.71  4556.4  286.91    4755  288.15  4785.1  287.89    4860  288.79
  4869.1  284.55  4874.4   284.6  4891.9  289.04  4899.6  287.87  4913.2  289.71
  4923.8  289.33  4930.2  286.54    4952  283.24  4952.5  282.74  4969.5  283.24
    4977  289.53  5072.5  288.77  5090.8   288.3  5962.4  287.33  6016.2  287.67
  6046.2  283.66  6066.2  286.63    6158   288.2  6649.9  305.08  6833.7  309.01
#Mann= 12 ,-1 , 0
  2685.3     .07       0  3131.6     .05       0  4556.4     .07       0
    4755     .12       0  4785.1      .1       0    4952     .05       0
  4969.5      .1       0  5072.5     .12       0  5090.8     .07       0
  5962.4     .05       0    6158     .07       0  6649.9    .035       0
Bank Sta=4952,4969.5
XS Rating Curve= 0 ,0
Exp/Cntr=0.3,0.1

Type RM Length L Ch R = 1 ,5299    ,1371,1371,1371
BEGIN DESCRIPTION:
XS7835
END DESCRIPTION:
XS GIS Cut Line= 3
      2530754.76     13772038.69      2531864.27     13772897.23
      2532920.48     13774943.64
#Sta/Elev= 30
  2947.9  318.25  2995.8  317.12  3402.1  308.68  3502.7  307.07  3750.9  306.09
  3900.3  302.58  4160.3  290.37  4192.8  288.19  4207.3  289.97  4423.7  285.74
  4483.3  286.64  4646.6  282.87  4674.6  286.22  4719.6  284.34    4903  284.95
  4967.2  286.62  4970.1  282.71  4970.6  282.21  4987.7  282.71  4995.5  287.17
  5062.7  285.51  5507.4  284.42  5516.7   284.4  5784.4  285.07  5988.1  288.76
  6072.2  290.74  6352.2  299.65  6521.7  302.48  6638.7  303.61  6653.7  303.25
#Mann= 17 ,-1 , 0
  2947.9     .07       0  2995.8     .05       0  3402.1    .035       0
  3502.7     .05       0  4160.3     .12       0  4423.7     .05       0
    4903      .1       0  4970.1     .05       0  4987.7      .1       0
  5062.7     .05       0  5507.4     .12       0  5516.7     .05       0
  5784.4     .07       0  5988.1     .12       0  6072.2     .07       0
  6521.7    .035       0  6638.7     .05       0
Bank Sta=4970.1,4987.7
XS Rating Curve= 0 ,0
Exp/Cntr=0.3,0.1

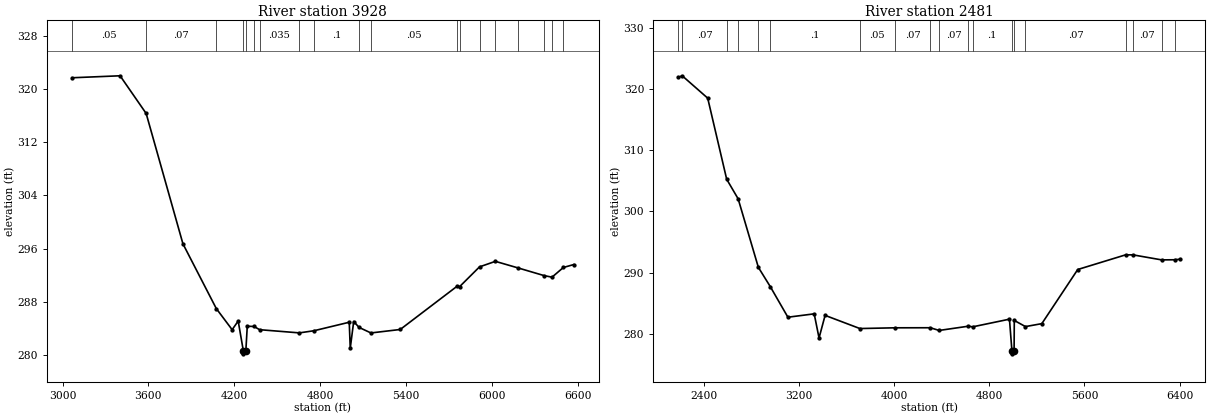
Type RM Length L Ch R = 1 ,3928    ,1447,1447,1447
BEGIN DESCRIPTION:
XS7834
END DESCRIPTION:
XS GIS Cut Line= 2
      2530635.87     13772197.14      2531784.57     13775511.21
#Sta/Elev= 30
  3065.9  321.69  3402.3  321.99  3584.5  316.33  3841.7  296.73  4074.9     287
  4185.5  283.83  4227.8  285.13  4263.4   280.7  4263.9   280.2  4281.4   280.7
  4291.3  284.35  4339.4  284.31  4377.2  283.83  4655.3  283.35  4757.2  283.67
    5004  284.95    5011  281.04  5035.1  285.06  5072.8  284.17  5155.5  283.34
  5360.3  283.86  5758.9  290.38    5775  290.29  5914.4  293.27  6025.3   294.1
  6184.2  293.11  6365.6  291.96  6421.1  291.72  6500.5  293.18  6573.4  293.62
#Mann= 19 ,-1 , 0
  3065.9     .05       0  3584.5     .07       0  4074.9      .1       0
  4263.4     .05       0  4281.4      .1       0  4339.4     .05       0
  4377.2    .035       0  4655.3     .07       0  4757.2      .1       0
  5072.8     .07       0  5155.5     .05       0  5758.9     .07       0
    5775     .05       0  5914.4    .035       0  6025.3     .05       0
  6184.2     .07       0  6365.6     .05       0  6421.1     .07       0
  6500.5     .05       0
Bank Sta=4263.4,4281.4
XS Rating Curve= 0 ,0
Exp/Cntr=0.3,0.1

Type RM Length L Ch R = 1 ,2481    ,0,0,0
BEGIN DESCRIPTION:
XS7833
END DESCRIPTION:
XS GIS Cut Line= 4
      2530398.14     13772223.61      2530107.55      13773782.2
      2530754.76     13775446.45      2531427.33     13775960.77
#Sta/Elev= 30
  2188.2  321.88  2219.5  322.14  2433.8  318.49  2593.3  305.25  2689.7  302.05
  2859.6  290.86  2959.3  287.73  3107.9  282.72  3328.9  283.27  3369.6  279.33
  3420.5  283.02  3712.8  280.87    4006  280.99  4304.6     281  4379.1  280.56
  4623.7  281.25    4661  281.15  4969.9   282.4  4990.7  277.24  4991.2  276.74
  5008.9  277.24  5010.6  282.19  5104.4  281.19    5242  281.67  5543.9  290.51
  5945.7   292.9  6007.7   292.9  6248.9  292.08  6357.9   292.1    6406  292.19
#Mann= 19 ,-1 , 0
  2188.2     .05       0  2219.5     .07       0  2593.3     .05       0
  2689.7     .07       0  2859.6     .12       0  2959.3      .1       0
  3712.8     .05       0    4006     .07       0  4304.6     .12       0
  4379.1     .07       0  4623.7     .12       0    4661      .1       0
  4990.7     .05       0  5008.9      .1       0  5104.4     .07       0
  5945.7     .05       0  6007.7     .07       0  6248.9     .05       0
  6357.9     .07       0
Bank Sta=4990.7,5008.9
XS Rating Curve= 0 ,0
Exp/Cntr=0.3,0.1

Chan Stop Cuts=-1
Use User Specified Reach Order=0
Composite Channel Slope=5