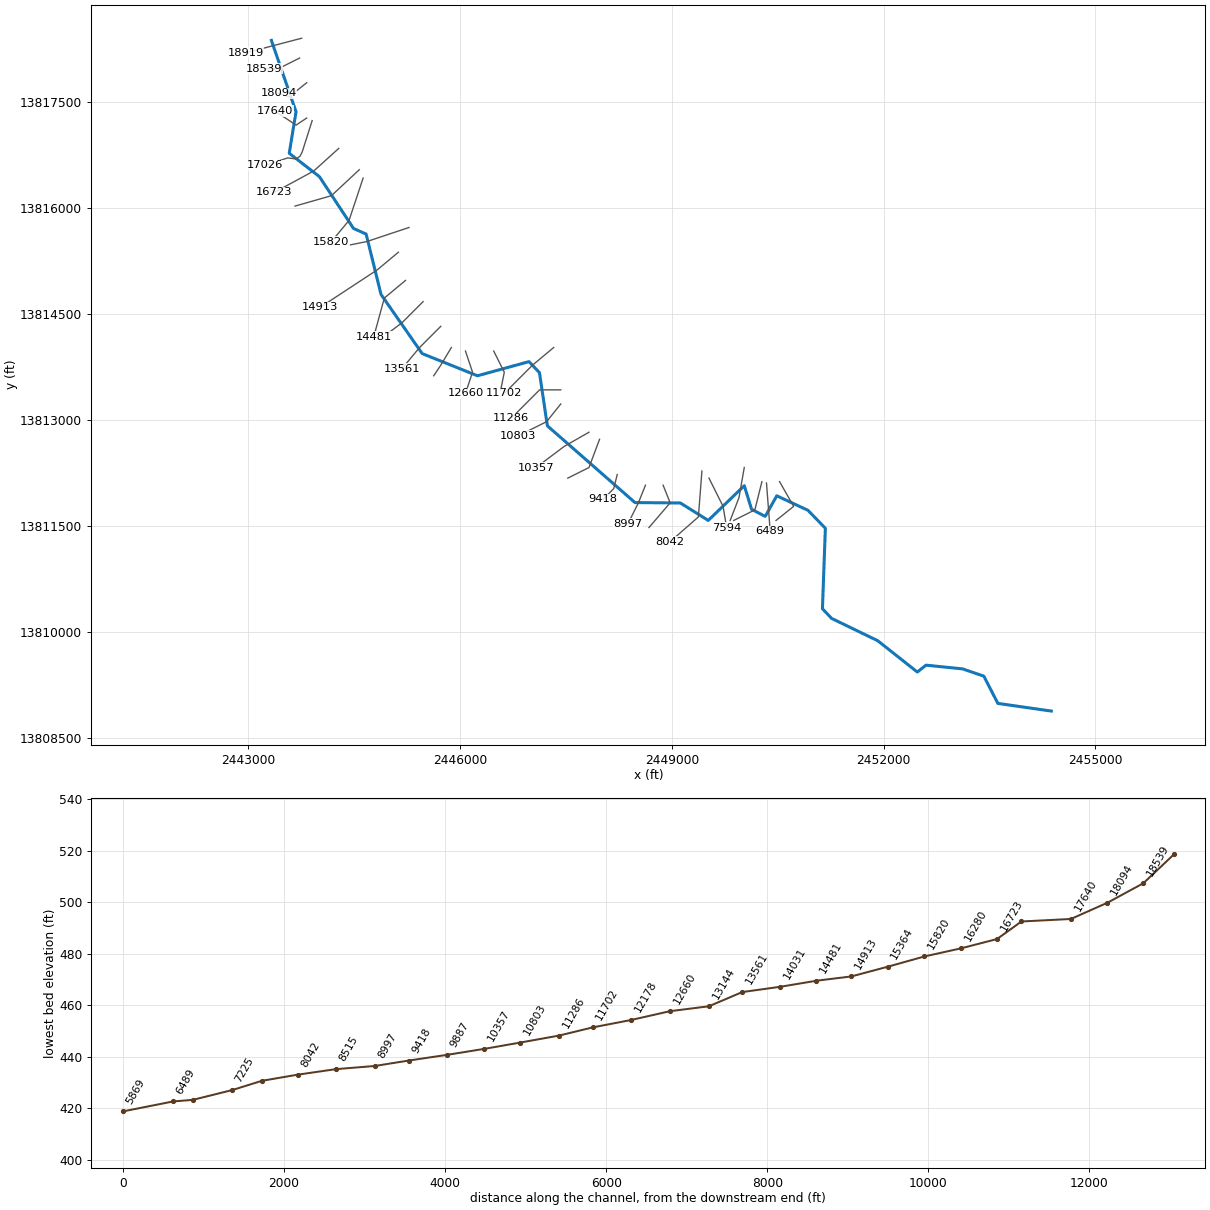
--- Scruggs Creek.prj (project) ---

Proj Title=Scruggs Creek Base Level Engineering
Current Plan=p01
Default Exp/Contr=0.3,0.1
English Units
Geom File=g01
Flow File=f01
Plan File=p01
Y Axis Title=Elevation
X Axis Title(PF)=Main Channel Distance
X Axis Title(XS)=Station
BEGIN DESCRIPTION:
Scruggs Creek
END DESCRIPTION:
DSS Export Rating Curves= 0
DSS Export Rating Curve Sorted= 0
DSS Export Volume Flow Curves= 0
DXF OffsetX= 0
DXF OffsetY= 0
DXF ScaleX= 1
DXF ScaleY= 10

--- Scruggs Creek.p01 (plan) ---

Plan Title=Multiple Run
Short Identifier=Multiple
Geom File=g01
Flow File=f01
Subcritical Flow
K Sum by GR= 0
Std Step Tol= 0.01
Critical Tol= 0.01
Num of Std Step Trials= 20
Max Error Tol= 0.3
Flow Tol Ratio= 0.001
Split Flow NTrial= 30
Split Flow Tol= 0.02
Split Flow Ratio= 0.02
Log Output Level= 0
Friction Slope Method= 1
Unsteady Friction Slope Method= 2
Unsteady Bridges Friction Slope Method= 1
Parabolic Critical Depth
Global Vel Dist=  1 , 1 , 1
Global Log Level= 0
CheckData=True
Encroach Param= -1, 0, 0, 0
BEGIN DESCRIPTION:
Multiple Run
END DESCRIPTION:

--- Scruggs Creek.f01 (steady flow) ---

Flow Title=Multiple
Number of Profiles=7
Profile Names=10-year,25-year,50-year,1pct_min,100-year,1pct_plu,500-year
River Rch & RM= Scruggs Creek,Reach-1,18919
     666    1077    1451     947    1889    3769    3170
River Rch & RM= Scruggs Creek,Reach-1,11702
     834    1358    1836    1201    2396    4781    4044
River Rch & RM= Scruggs Creek,Reach-1,5408
    2193    3755    5250    3542    7068   14102   12694
River Rch & RM= Scruggs Creek,Reach-1,2335
    2444    4208    5905    3998    7977   15917   14430
River Rch & RM= Scruggs Creek,Reach-1,1380
    2451    4218    5917    4004    7989   15941   14439
Boundary for River Rch & Prof#=Scruggs Creek,Reach-1,1
Up Type=0
Dn Type=3
Dn Slope=0.005
Boundary for River Rch & Prof#=Scruggs Creek,Reach-1,2
Up Type=0
Dn Type=3
Dn Slope=0.005
Boundary for River Rch & Prof#=Scruggs Creek,Reach-1,3
Up Type=0
Dn Type=3
Dn Slope=0.005
Boundary for River Rch & Prof#=Scruggs Creek,Reach-1,4
Up Type=0
Dn Type=3
Dn Slope=0.005
Boundary for River Rch & Prof#=Scruggs Creek,Reach-1,5
Up Type=0
Dn Type=3
Dn Slope=0.005
Boundary for River Rch & Prof#=Scruggs Creek,Reach-1,6
Up Type=0
Dn Type=3
Dn Slope=0.005
Boundary for River Rch & Prof#=Scruggs Creek,Reach-1,7
Up Type=0
Dn Type=3
Dn Slope=0.005

--- Scruggs Creek.g01 (geometry) ---

Geom Title=Existing Conditions

River Reach=Scruggs Creek,Reach-1
Reach XY= 30
      2443325.00     13818375.00      2443673.89     13817364.45
      2443578.01     13816776.43      2444005.21     13816445.09
      2444488.45     13815711.37      2444667.27     13815631.50
      2444878.62     13814776.50      2445461.44     13813938.49
      2446245.18     13813624.72      2446975.00     13813825.00
      2447122.94     13813669.15      2447235.52     13812915.21
      2448476.47     13811828.55      2449119.15     13811822.94
      2449514.38     13811575.59      2450025.23     13812068.04
      2450128.50     13811733.46      2450321.77     13811632.84
      2450485.43     13811924.47      2450927.30     13811719.17
      2451174.09     13811464.53      2451132.55     13810324.99
      2451261.68     13810188.37      2451916.51     13809871.47
      2452476.76     13809428.30      2452599.88     13809525.52
      2453119.06     13809472.74      2453419.53     13809369.74
      2453617.98     13808984.01      2454375.00     13808875.00

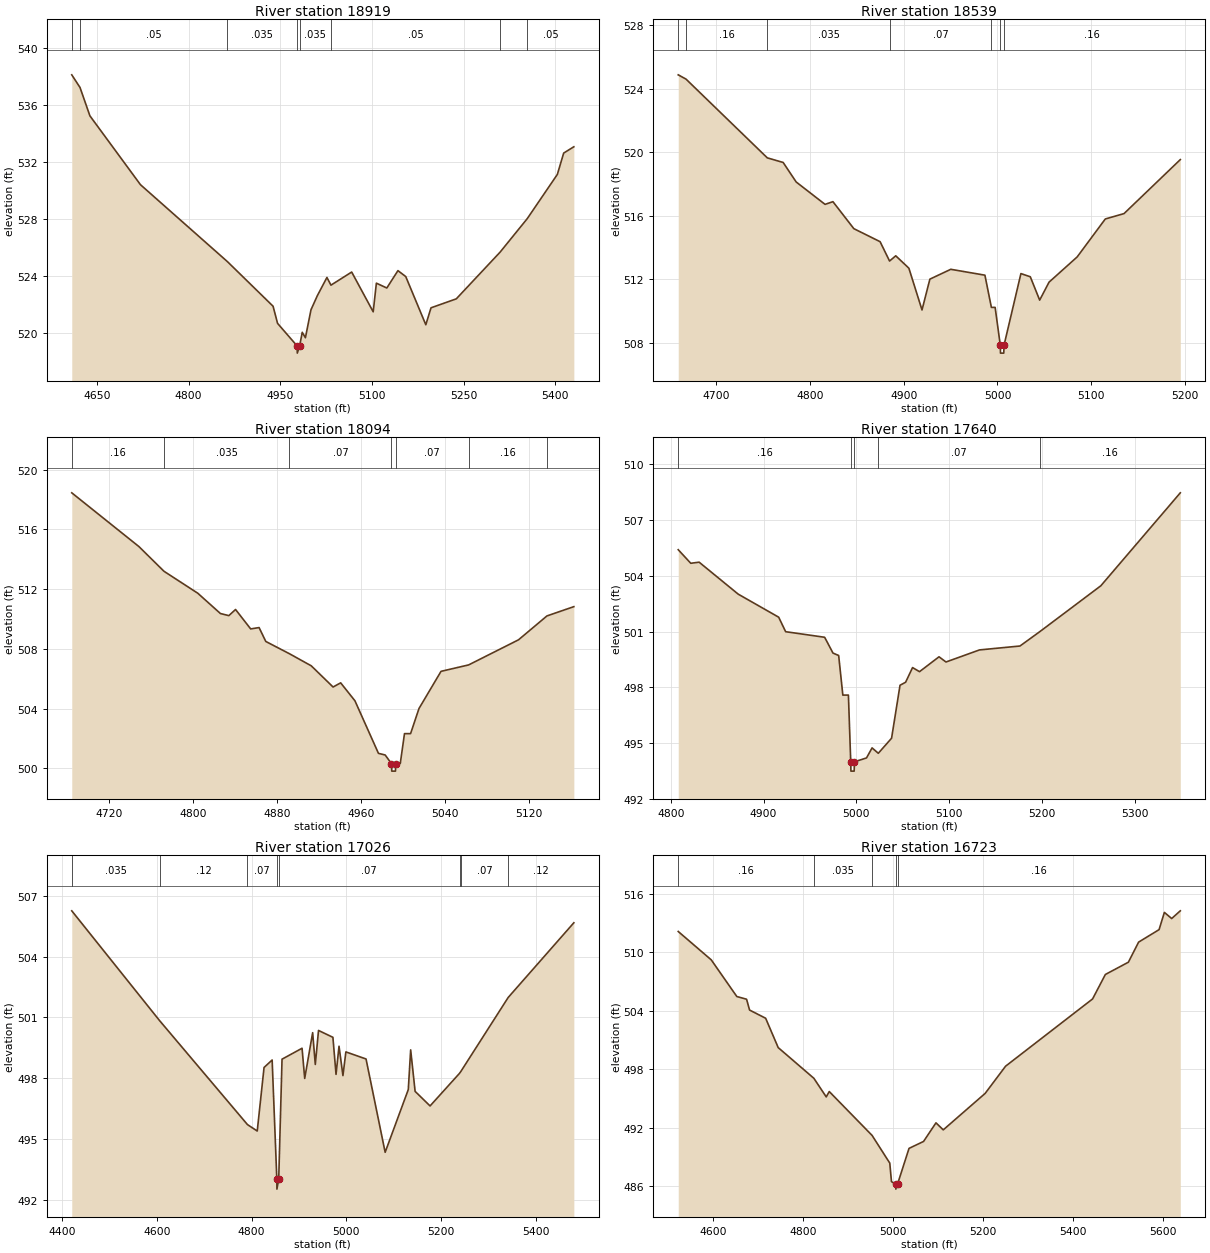
Type RM Length L Ch R = 1,18919,380,380,380
BEGIN DESCRIPTION:
E20780
END DESCRIPTION:
XS GIS Cut Line= 2
      2443753.70     13818405.68      2442958.92     13818197.89
#Sta/Elev= 30
  4609.0  538.11  4622.5  537.22  4638.7  535.23  4721.4  530.40  4863.7  525.00
  4938.4  521.87  4945.7  520.67  4977.8  519.08  4978.0  518.58  4981.8  519.08
  4986.1  520.04  4991.3  519.66  5000.4  521.62  5010.8  522.61  5026.5  523.89
  5033.1  523.35  5067.0  524.27  5102.2  521.48  5107.4  523.49  5124.5  523.15
  5142.7  524.37  5155.5  523.95  5188.3  520.57  5196.8  521.76  5238.2  522.39
  5309.9  525.67  5354.3  528.02  5403.5  531.12  5413.9  532.62  5430.5  533.06
#Mann=8,-1,0
  4609.0    0.07       0  4622.5    0.05       0  4863.7   0.035       0
  4977.8   0.035       0  4981.8   0.035       0  5033.1    0.05       0
  5309.9    0.07       0  5354.3    0.05       0
Bank Sta=4977.8,4981.8
Exp/Cntr=0.3,0.1

Type RM Length L Ch R = 1,18539,445,445,445
BEGIN DESCRIPTION:
Scruggs Creek 38.0
END DESCRIPTION:
XS GIS Cut Line= 3
      2443725.04     13818125.02      2443425.00     13817975.00
      2443224.96     13817975.00
#Sta/Elev= 30
  4659.5  524.89  4667.8  524.62  4754.5  519.66  4771.4  519.37  4785.3  518.14
  4816.1  516.73  4824.5  516.90  4846.8  515.20  4874.8  514.38  4884.9  513.16
  4891.5  513.49  4905.5  512.71  4919.5  510.08  4927.9  512.02  4950.2  512.64
  4986.6  512.27  4993.5  510.24  4997.5  510.24  5003.0  507.86  5003.2  507.36
  5006.7  507.36  5007.0  507.86  5025.0  512.37  5035.0  512.17  5045.0  510.70
  5055.0  511.83  5085.0  513.42  5115.0  515.81  5135.0  516.15  5195.0  519.55
#Mann=7,-1,0
  4659.5    0.05       0  4667.8    0.16       0  4754.5   0.035       0
  4884.9    0.07       0  4993.5    0.16       0  5003.0    0.07       0
  5007.0    0.16       0
Bank Sta=5003,5007
Exp/Cntr=0.3,0.1

Type RM Length L Ch R = 1,18094,454,454,454
BEGIN DESCRIPTION:
Scruggs Creek 37.0
END DESCRIPTION:
XS GIS Cut Line= 3
      2443824.96     13817774.97      2443575.00     13817575.00
      2443425.02     13817624.99
#Sta/Elev= 30
  4684.7  518.44  4748.7  514.84  4772.5  513.19  4804.7  511.72  4826.3  510.36
  4834.3  510.22  4840.7  510.63  4855.1  509.33  4863.1  509.42  4869.5  508.49
  4892.0  507.67  4912.8  506.86  4933.6  505.44  4940.8  505.72  4954.4  504.52
  4976.8  501.00  4983.2  500.89  4989.2  500.31  4989.5  499.81  4993.0  499.81
  4993.2  500.31  4997.6  500.33  5001.6  502.32  5007.4  502.32  5015.4  504.00
  5036.4  506.49  5062.7  506.92  5110.2  508.60  5137.3  510.20  5162.9  510.82
#Mann=7,-1,0
  4684.7    0.16       0  4772.5   0.035       0  4892.0    0.07       0
  4989.2    0.07       0  4993.2    0.07       0  5062.7    0.16       0
  5137.3    0.07       0
Bank Sta=4989.2,4993.2
Exp/Cntr=0.3,0.1

Type RM Length L Ch R = 1,17640,614,614,614
BEGIN DESCRIPTION:
Scruggs Creek 36.0
END DESCRIPTION:
XS GIS Cut Line= 3
      2443824.99     13817275.00      2443675.00     13817175.00
      2443375.02     13817374.99
#Sta/Elev= 30
  4808.1  505.40  4821.6  504.67  4830.6  504.73  4872.7  503.01  4916.3  501.77
  4923.8  500.99  4965.8  500.69  4974.8  499.84  4980.9  499.71  4985.4  497.58
  4991.4  497.58  4993.9  493.99  4994.1  493.49  4997.6  493.49  4997.9  493.99
  5010.9  494.20  5016.9  494.74  5023.6  494.45  5037.9  495.26  5047.0  498.11
  5053.0  498.27  5060.5  499.06  5068.0  498.84  5089.0  499.64  5096.5  499.36
  5132.6  500.01  5176.2  500.22  5197.5  500.99  5263.3  503.46  5348.9  508.46
#Mann=5,-1,0
  4808.1    0.16       0  4993.9    0.07       0  4997.9    0.16       0
  5023.6    0.07       0  5197.5    0.16       0
Bank Sta=4993.9,4997.9
Exp/Cntr=0.3,0.1

Type RM Length L Ch R = 1,17026,303,303,303
BEGIN DESCRIPTION:
Scruggs Creek 35.0
END DESCRIPTION:
XS GIS Cut Line= 6
      2443902.59     13817238.50      2443761.98     13816795.83
      2443732.70     13816737.69      2443676.91     13816695.14
      2443557.12     13816710.76      2443234.22     13816603.13
#Sta/Elev= 30
  4419.9  506.27  4605.3  500.85  4791.1  495.71  4811.8  495.39  4826.2  498.53
  4843.3  498.90  4853.2  493.02  4853.4  492.52  4857.2  493.02  4864.2  498.94
  4906.5  499.48  4912.1  497.99  4928.9  500.25  4934.5  498.68  4941.3  500.36
  4971.7  500.02  4978.3  498.19  4984.6  499.58  4992.9  498.13  4999.1  499.30
  5041.7  498.95  5082.1  494.34  5131.0  497.44  5136.0  499.40  5145.4  497.35
  5177.0  496.63  5239.2  498.24  5242.5  498.35  5342.1  501.99  5480.8  505.68
#Mann=8,-1,0
  4419.9   0.035       0  4605.3    0.12       0  4791.1    0.07       0
  4853.2    0.05       0  4857.2    0.07       0  5239.2    0.12       0
  5242.5    0.07       0  5342.1    0.12       0
Bank Sta=4853.2,4857.2
Exp/Cntr=0.3,0.1

Type RM Length L Ch R = 1,16723,443,443,443
BEGIN DESCRIPTION:
Scruggs Creek 34.0
END DESCRIPTION:
XS GIS Cut Line= 3
      2444279.22     13816844.97      2443925.00     13816525.00
      2443363.53     13816220.64
#Sta/Elev= 30
  4522.7  512.13  4596.1  509.22  4652.9  505.46  4674.6  505.18  4681.3  504.07
  4717.0  503.23  4744.9  500.22  4824.2  497.07  4851.7  495.16  4858.4  495.71
  4953.6  491.21  4992.9  488.37  4996.7  486.47  5006.1  486.20  5006.4  485.70
  5010.1  486.20  5035.7  489.88  5068.0  490.59  5095.6  492.50  5111.8  491.78
  5204.9  495.52  5250.3  498.31  5443.7  505.21  5472.1  507.72  5523.3  508.98
  5546.0  511.04  5591.5  512.32  5603.3  514.09  5619.5  513.46  5638.7  514.25
#Mann=5,-1,0
  4522.7    0.16       0  4824.2   0.035       0  4953.6    0.16       0
  5006.1    0.07       0  5010.1    0.16       0
Bank Sta=5006.1,5010.1
Exp/Cntr=0.3,0.1

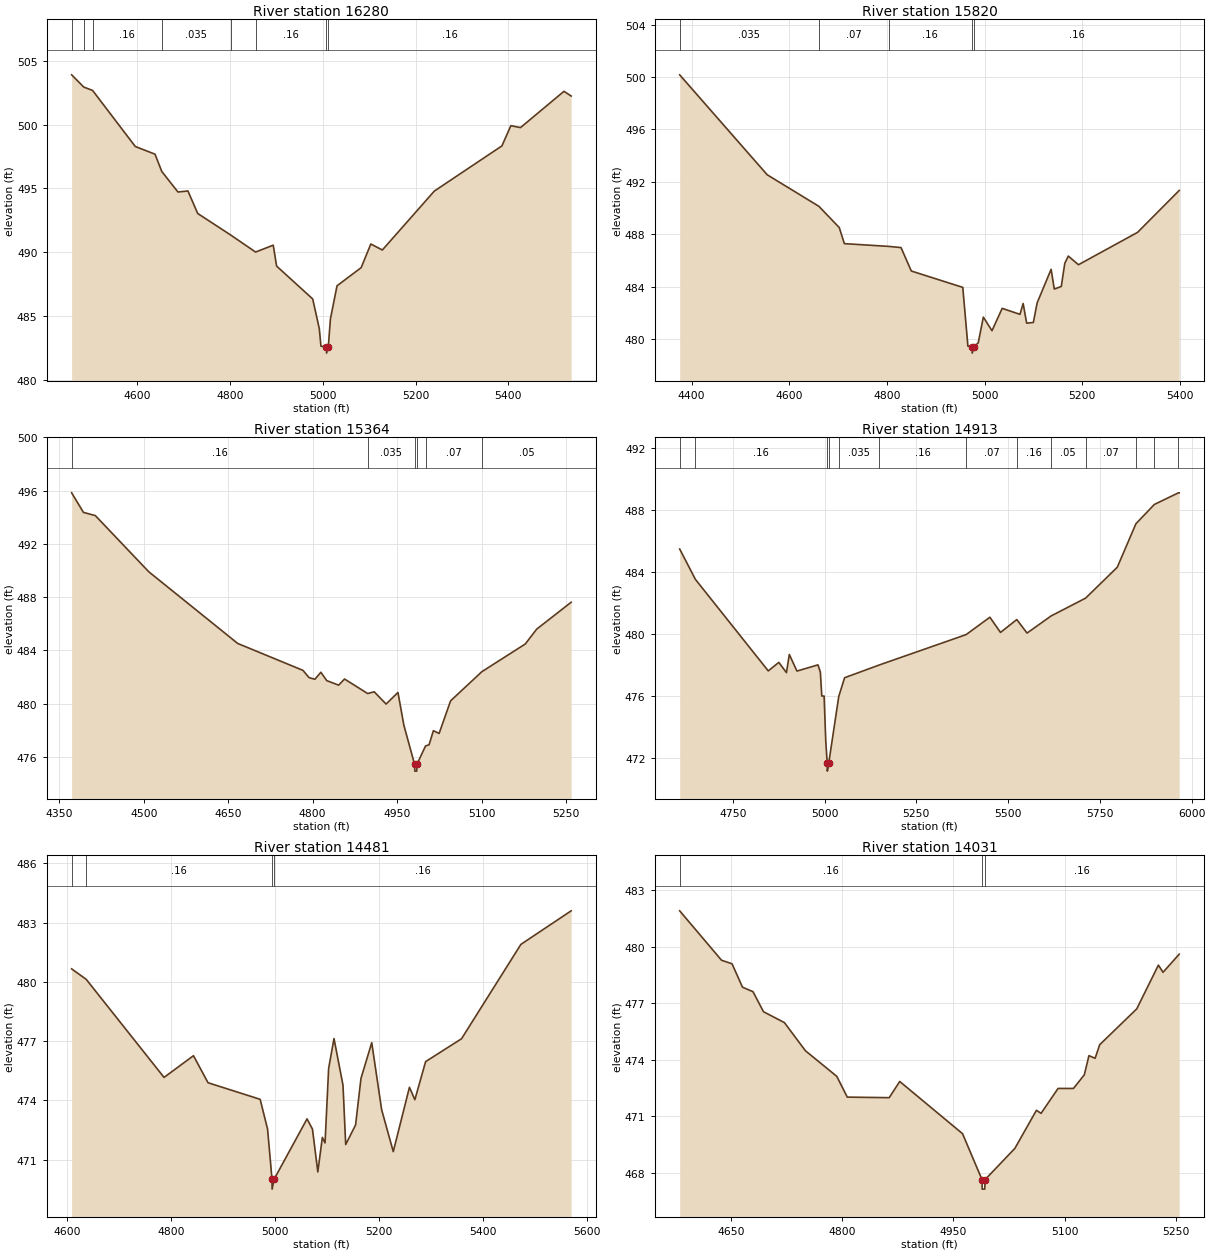
Type RM Length L Ch R = 1,16280,460,460,460
BEGIN DESCRIPTION:
Scruggs Creek 33.0
END DESCRIPTION:
XS GIS Cut Line= 3
      2444570.57     13816543.24      2444175.00     13816175.00
      2443660.07     13816028.15
#Sta/Elev= 30
  4459.3  503.89  4485.5  502.93  4504.4  502.67  4596.4  498.28  4638.9  497.68
  4653.4  496.33  4688.3  494.72  4709.8  494.80  4730.8  493.04  4802.4  491.34
  4855.5  490.02  4893.5  490.56  4900.8  488.92  4978.5  486.35  4992.7  484.03
  4996.3  482.65  5008.1  482.61  5008.4  482.11  5012.1  482.61  5016.7  484.79
  5030.9  487.38  5082.9  488.80  5103.7  490.65  5128.5  490.18  5240.4  494.79
  5386.1  498.33  5405.3  499.91  5426.1  499.76  5519.7  502.60  5535.2  502.23
#Mann=8,-1,0
  4459.3   0.035       0  4485.5    0.07       0  4504.4    0.16       0
  4653.4   0.035       0  4802.4    0.07       0  4855.5    0.16       0
  5008.1    0.07       0  5012.1    0.16       0
Bank Sta=5008.1,5012.1
Exp/Cntr=0.3,0.1

Type RM Length L Ch R = 1,15820,456,456,456
BEGIN DESCRIPTION:
Scruggs Creek 32.0
END DESCRIPTION:
XS GIS Cut Line= 3
      2444625.01     13816425.03      2444425.00     13815825.00
      2444175.00     13815525.00
#Sta/Elev= 30
  4375.7  500.17  4554.9  492.54  4660.8  490.13  4702.5  488.51  4713.0  487.28
  4803.6  487.07  4829.0  486.98  4850.1  485.19  4955.5  483.94  4966.0  479.45
  4974.6  479.42  4974.8  478.92  4978.6  479.42  4987.1  479.70  4997.6  481.67
  5015.3  480.63  5036.2  482.34  5072.6  481.88  5079.1  482.71  5086.3  481.21
  5100.0  481.26  5107.8  482.76  5136.4  485.32  5142.9  483.81  5157.2  484.01
  5164.4  485.78  5171.6  486.33  5192.4  485.67  5313.4  488.14  5398.7  491.34
#Mann=5,-1,0
  4375.7   0.035       0  4660.8    0.07       0  4803.6    0.16       0
  4974.6    0.07       0  4978.6    0.16       0
Bank Sta=4974.6,4978.6
Exp/Cntr=0.3,0.1

Type RM Length L Ch R = 1,15364,451,451,451
BEGIN DESCRIPTION:
Scruggs Creek 31.0
END DESCRIPTION:
XS GIS Cut Line= 3
      2445274.96     13815724.99      2444675.00     13815525.00
      2444424.96     13815474.99
#Sta/Elev= 30
  4371.8  495.83  4392.8  494.36  4413.9  494.12  4508.8  489.90  4666.9  484.51
  4782.8  482.49  4793.4  481.95  4803.9  481.82  4814.5  482.35  4825.0  481.72
  4846.1  481.38  4856.6  481.84  4897.7  480.75  4909.3  480.88  4930.4  479.96
  4951.5  480.83  4962.0  478.37  4981.1  475.42  4981.4  474.92  4984.9  474.92
  4985.1  475.42  5000.5  476.81  5006.8  476.90  5014.4  477.96  5024.6  477.75
  5045.0  480.20  5100.5  482.39  5177.6  484.47  5198.0  485.59  5259.2  487.61
#Mann=6,-1,0
  4371.8    0.16       0  4897.7   0.035       0  4981.1   0.035       0
  4985.1   0.035       0  5000.5    0.07       0  5100.5    0.05       0
Bank Sta=4981.1,4985.1
Exp/Cntr=0.3,0.1

Type RM Length L Ch R = 1,14913,432,432,432
BEGIN DESCRIPTION:
Scruggs Creek 30.0
END DESCRIPTION:
XS GIS Cut Line= 3
      2445124.98     13815374.98      2444825.00     13815125.00
      2444013.88     13814592.29
#Sta/Elev= 30
  4605.3  485.48  4648.2  483.52  4846.7  477.62  4875.4  478.17  4896.2  477.51
  4904.0  478.68  4924.8  477.61  4982.1  478.01  4988.6  477.54  4992.5  476.00
  4998.8  476.00  5003.3  473.10  5007.3  471.66  5007.6  471.16  5011.3  471.66
  5038.7  475.97  5054.6  477.18  5148.8  478.00  5385.7  479.96  5450.4  481.08
  5479.4  480.10  5523.7  480.93  5551.7  480.06  5617.0  481.16  5711.1  482.31
  5797.4  484.30  5848.4  487.11  5898.5  488.35  5964.1  489.10  5966.2  489.10
#Mann=13,-1,0
  4605.3   0.035       0  4648.2    0.16       0  5007.3    0.07       0
  5011.3    0.16       0  5038.7   0.035       0  5148.8    0.16       0
  5385.7    0.07       0  5523.7    0.16       0  5617.0    0.05       0
  5711.1    0.07       0  5848.4    0.16       0  5898.5    0.07       0
  5964.1    0.05       0
Bank Sta=5007.3,5011.3
Exp/Cntr=0.3,0.1

Type RM Length L Ch R = 1,14481,450,450,450
BEGIN DESCRIPTION:
Scruggs Creek 29.0
END DESCRIPTION:
XS GIS Cut Line= 3
      2445225.00     13814975.00      2444925.00     13814725.00
      2444775.00     13814175.00
#Sta/Elev= 30
  4609.5  480.66  4637.5  480.13  4787.2  475.16  4843.8  476.26  4871.8  474.89
  4972.0  474.05  4986.3  472.54  4994.8  470.00  4995.0  469.50  4998.8  470.00
  5062.2  473.06  5072.6  472.54  5082.9  470.37  5091.6  472.12  5096.8  471.84
  5103.7  475.61  5114.0  477.13  5131.3  474.77  5136.5  471.76  5155.5  472.75
  5165.9  475.11  5186.6  476.92  5205.6  473.53  5228.0  471.40  5259.1  474.66
  5269.5  474.03  5290.2  475.96  5359.3  477.12  5473.4  481.90  5570.1  483.60
#Mann=4,-1,0
  4609.5   0.035       0  4637.5    0.16       0  4994.8    0.07       0
  4998.8    0.16       0
Bank Sta=4994.8,4998.8
Exp/Cntr=0.3,0.1

Type RM Length L Ch R = 1,14031,470,470,470
BEGIN DESCRIPTION:
Scruggs Creek 28.0
END DESCRIPTION:
XS GIS Cut Line= 3
      2445474.98     13814674.98      2445175.00     13814375.00
      2444975.03     13814225.02
#Sta/Elev= 30
  4580.6  481.90  4637.1  479.28  4651.3  479.09  4665.4  477.85  4679.6  477.61
  4693.7  476.55  4722.0  475.97  4750.3  474.48  4792.7  473.12  4806.8  472.02
  4863.4  471.99  4877.6  472.85  4962.4  470.08  4988.7  467.64  4988.9  467.14
  4992.4  467.14  4992.7  467.64  5033.0  469.30  5062.1  471.32  5068.4  471.16
  5091.3  472.48  5112.1  472.48  5126.7  473.20  5133.0  474.22  5141.3  474.08
  5147.5  474.80  5197.5  476.70  5226.7  479.02  5233.0  478.64  5254.8  479.60
#Mann=3,-1,0
  4580.6    0.16       0  4988.7    0.07       0  4992.7    0.16       0
Bank Sta=4988.7,4992.7
Exp/Cntr=0.3,0.1

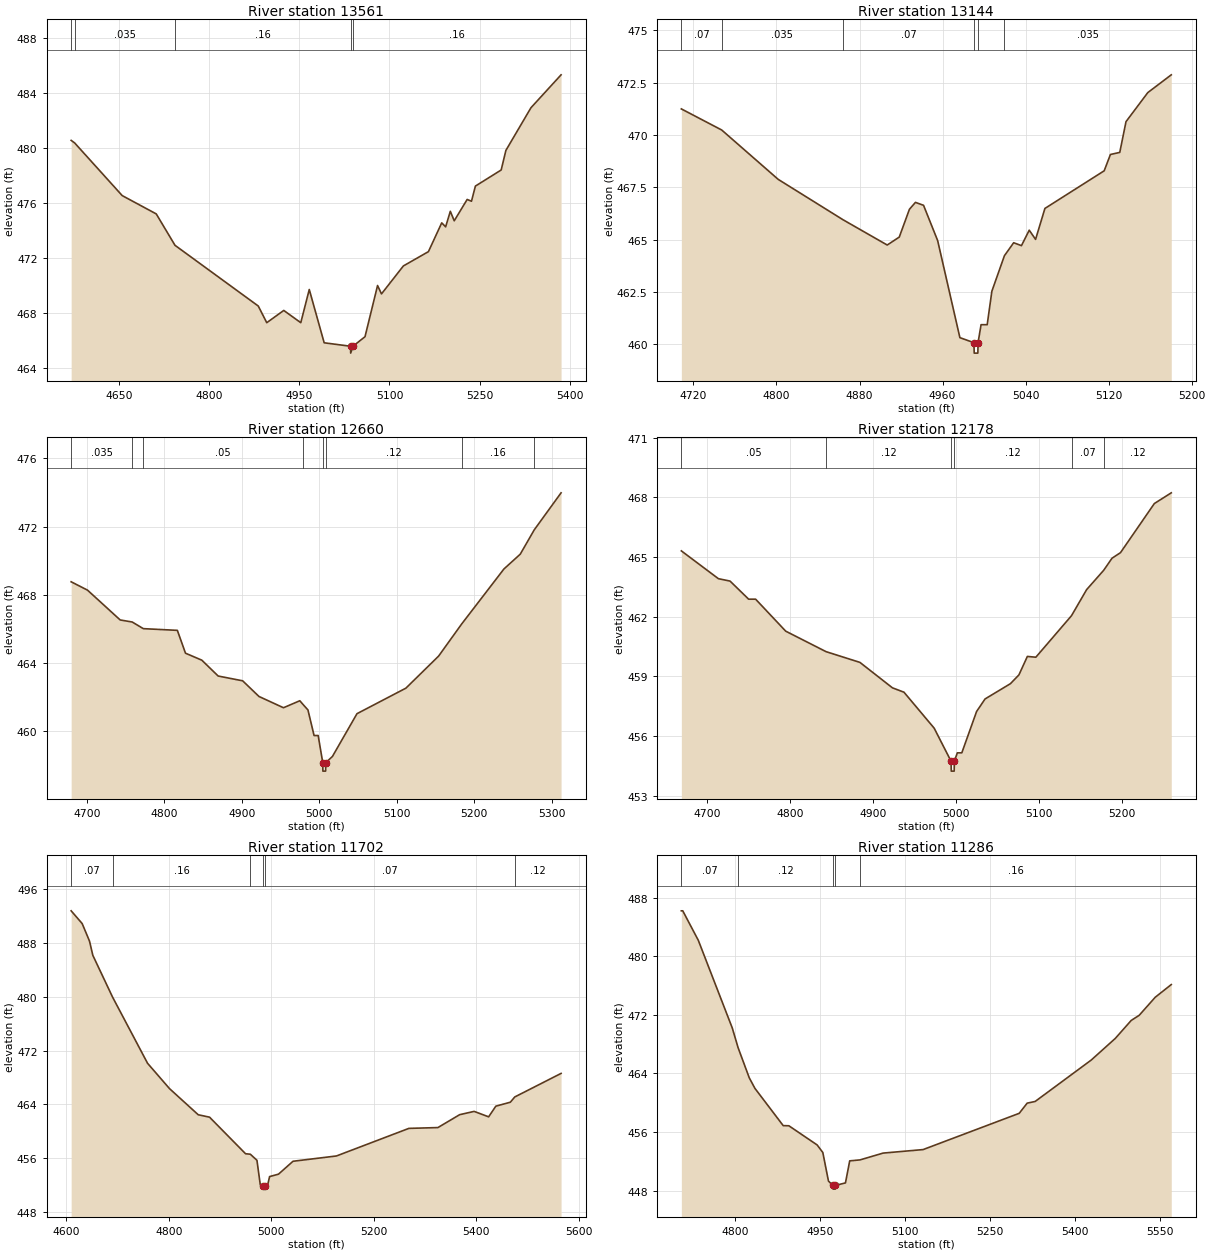
Type RM Length L Ch R = 1,13561,417,417,417
BEGIN DESCRIPTION:
Scruggs Creek 27.0
END DESCRIPTION:
XS GIS Cut Line= 3
      2445725.02     13814325.02      2445425.00     13814025.00
      2445175.01     13813725.01
#Sta/Elev= 30
  4570.6  480.55  4576.5  480.36  4655.5  476.54  4712.1  475.21  4743.3  472.93
  4881.8  468.52  4895.9  467.31  4924.2  468.20  4952.5  467.31  4966.6  469.72
  4991.4  465.85  5035.2  465.60  5035.5  465.10  5039.2  465.60  5059.3  466.29
  5080.2  470.01  5086.7  469.40  5123.1  471.43  5164.8  472.47  5186.9  474.56
  5193.4  474.27  5201.2  475.40  5207.7  474.71  5229.2  476.26  5236.4  476.13
  5242.9  477.23  5285.8  478.40  5293.6  479.82  5335.3  482.92  5385.4  485.31
#Mann=5,-1,0
  4570.6    0.07       0  4576.5   0.035       0  4743.3    0.16       0
  5035.2    0.07       0  5039.2    0.16       0
Bank Sta=5035.2,5039.2
Exp/Cntr=0.3,0.1

Type RM Length L Ch R = 1,13144,484,484,484
BEGIN DESCRIPTION:
Scruggs Creek 26.0
END DESCRIPTION:
XS GIS Cut Line= 3
      2445875.01     13814025.02      2445725.00     13813775.00
      2445624.97     13813624.96
#Sta/Elev= 30
  4708.4  471.25  4747.3  470.24  4801.7  467.88  4864.1  465.95  4906.7  464.74
  4918.3  465.12  4928.1  466.45  4933.9  466.78  4941.7  466.64  4955.3  464.95
  4976.7  460.31  4990.2  460.07  4990.5  459.57  4994.0  459.57  4994.2  460.07
  4997.1  460.93  5003.0  460.93  5007.5  462.53  5019.6  464.23  5028.5  464.85
  5036.0  464.71  5043.5  465.45  5049.6  465.01  5058.6  466.49  5115.7  468.29
  5121.7  469.07  5130.7  469.17  5136.7  470.64  5157.7  472.03  5180.3  472.88
#Mann=6,-1,0
  4708.4    0.07       0  4747.3   0.035       0  4864.1    0.07       0
  4990.2    0.07       0  4994.2    0.07       0  5019.6   0.035       0
Bank Sta=4990.2,4994.2
Exp/Cntr=0.3,0.1

Type RM Length L Ch R = 1,12660,482,482,482
BEGIN DESCRIPTION:
Scruggs Creek 25.0
END DESCRIPTION:
XS GIS Cut Line= 3
      2446074.99     13813975.02      2446175.00     13813675.00
      2446074.99     13813374.98
#Sta/Elev= 30
  4679.6  468.76  4700.7  468.27  4742.9  466.52  4758.4  466.40  4772.8  466.01
  4816.7  465.91  4827.2  464.57  4848.3  464.16  4869.4  463.23  4901.0  462.95
  4922.1  462.03  4953.7  461.37  4974.8  461.78  4979.2  461.55  4985.3  461.24
  4993.2  459.74  4998.5  459.74  5004.4  458.15  5004.6  457.65  5008.1  457.65
  5008.4  458.15  5016.9  458.51  5048.6  461.02  5111.8  462.52  5154.0  464.40
  5183.7  466.28  5238.3  469.51  5259.4  470.38  5277.5  471.81  5312.1  473.98
#Mann=8,-1,0
  4679.6   0.035       0  4758.4    0.07       0  4772.8    0.05       0
  4979.2    0.12       0  5004.4    0.07       0  5008.4    0.12       0
  5183.7    0.16       0  5277.5    0.07       0
Bank Sta=5004.4,5008.4
Exp/Cntr=0.3,0.1

Type RM Length L Ch R = 1,12178,476,476,476
BEGIN DESCRIPTION:
Scruggs Creek 24.0
END DESCRIPTION:
XS GIS Cut Line= 3
      2446475.00     13813975.01      2446625.00     13813675.00
      2446574.99     13813424.97
#Sta/Elev= 30
  4668.7  465.31  4713.4  463.91  4727.4  463.79  4749.8  462.88  4758.2  462.88
  4794.5  461.27  4843.1  460.24  4883.9  459.70  4923.1  458.42  4937.0  458.20
  4973.4  456.39  4993.7  454.73  4994.0  454.23  4997.5  454.23  4997.7  454.73
  5001.3  455.15  5006.7  455.15  5024.5  457.23  5034.7  457.86  5065.3  458.63
  5075.5  459.07  5085.7  460.00  5095.9  459.96  5138.9  462.05  5157.1  463.36
  5177.6  464.33  5187.7  464.94  5197.9  465.22  5238.7  467.69  5259.1  468.23
#Mann=6,-1,0
  4668.7    0.05       0  4843.1    0.12       0  4993.7    0.07       0
  4997.7    0.12       0  5138.9    0.07       0  5177.6    0.12       0
Bank Sta=4993.7,4997.7
Exp/Cntr=0.3,0.1

Type RM Length L Ch R = 1,11702,416,416,416
BEGIN DESCRIPTION:
Scruggs Creek 23.0
END DESCRIPTION:
XS GIS Cut Line= 3
      2447325.02     13814025.02      2447025.00     13813775.00
      2446625.02     13813375.02
#Sta/Elev= 30
  4609.5  492.82  4631.0  490.92  4645.3  488.31  4651.8  486.19  4690.3  479.97
  4758.6  470.11  4801.5  466.33  4857.5  462.44  4879.6  462.08  4949.9  456.63
  4959.2  456.56  4972.1  455.66  4978.6  452.02  4984.4  451.86  4984.6  451.36
  4988.4  451.86  4992.9  451.94  4996.8  453.23  5014.2  453.59  5042.5  455.51
  5127.3  456.30  5268.7  460.41  5325.3  460.53  5367.7  462.45  5396.0  462.94
  5424.3  462.13  5438.4  463.72  5466.7  464.31  5475.3  465.09  5565.7  468.60
#Mann=6,-1,0
  4609.5    0.07       0  4690.3    0.16       0  4959.2    0.07       0
  4984.4    0.07       0  4988.4    0.07       0  5475.3    0.12       0
Bank Sta=4984.4,4988.4
Exp/Cntr=0.3,0.1

Type RM Length L Ch R = 1,11286,483,483,483
BEGIN DESCRIPTION:
Scruggs Creek 22.0
END DESCRIPTION:
XS GIS Cut Line= 3
      2447424.97     13813425.00      2447125.00     13813425.00
      2446724.97     13813024.97
#Sta/Elev= 30
  4704.8  486.19  4707.3  486.19  4734.8  482.16  4794.8  470.19  4805.1  467.50
  4824.8  463.39  4834.8  461.95  4884.8  456.86  4894.8  456.84  4944.8  454.22
  4954.8  453.19  4964.8  449.28  4972.7  448.69  4973.0  448.19  4976.6  448.19
  4976.8  448.69  4994.8  449.04  5002.3  452.05  5020.5  452.18  5061.3  453.11
  5132.0  453.59  5301.8  458.54  5315.9  459.93  5330.0  460.16  5429.0  465.81
  5471.5  468.76  5499.7  471.22  5513.9  471.93  5542.2  474.39  5570.5  476.12
#Mann=5,-1,0
  4704.8    0.07       0  4805.1    0.12       0  4972.7    0.07       0
  4976.8    0.12       0  5020.5    0.16       0
Bank Sta=4972.7,4976.8
Exp/Cntr=0.3,0.1

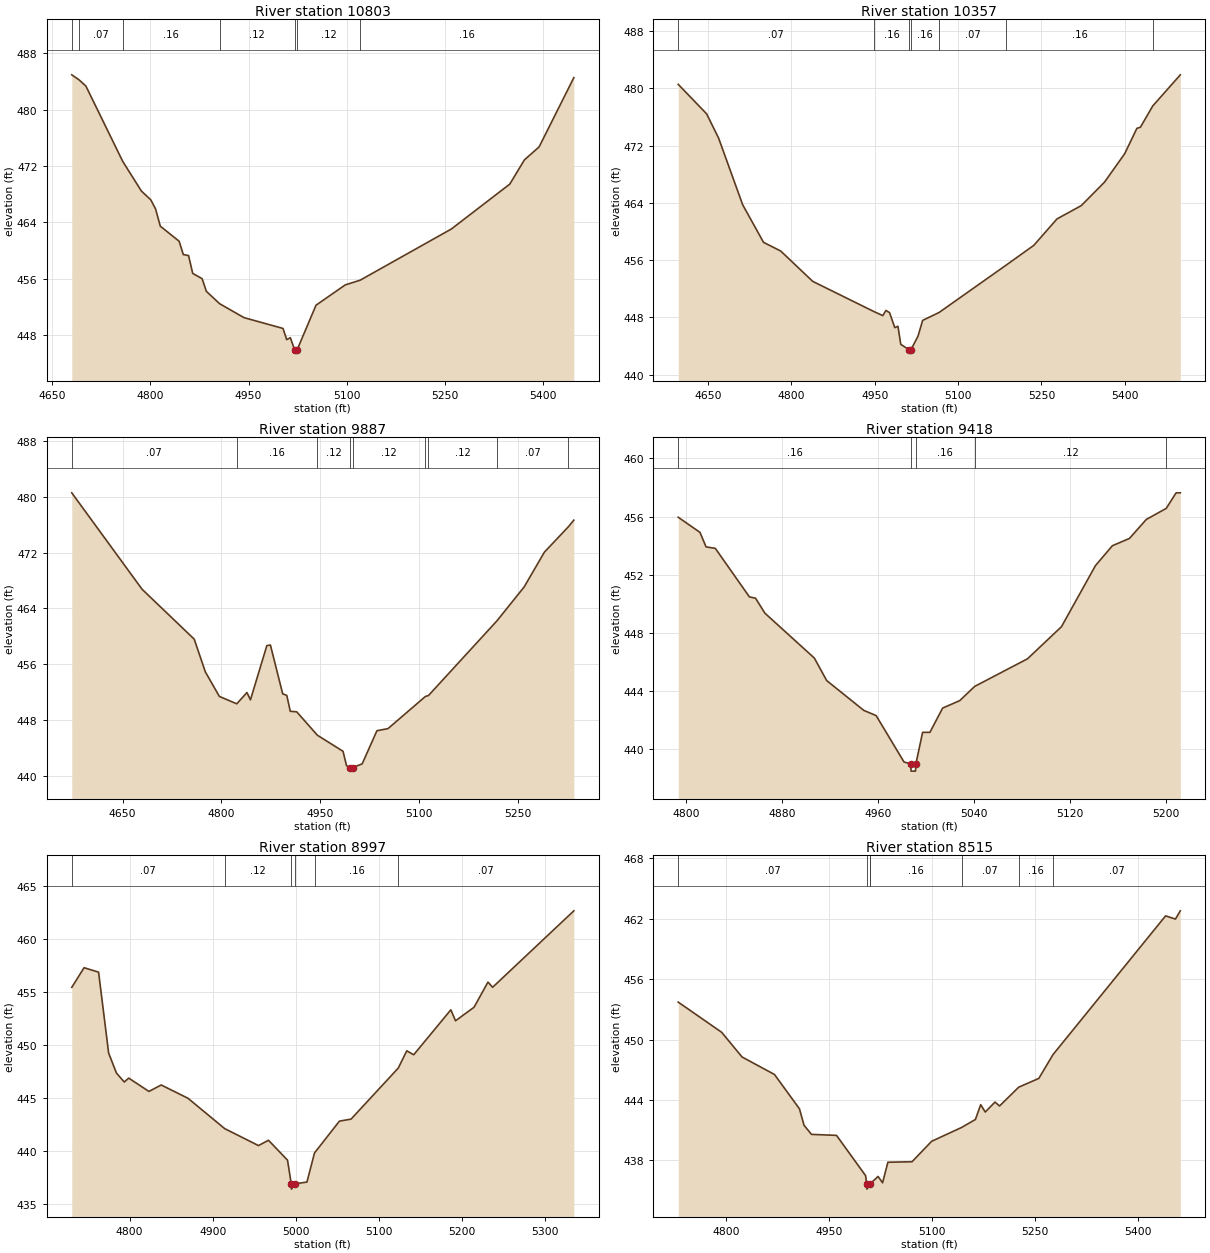
Type RM Length L Ch R = 1,10803,446,446,446
BEGIN DESCRIPTION:
Scruggs Creek 21.0
END DESCRIPTION:
XS GIS Cut Line= 3
      2447424.99     13813224.99      2447225.00     13812975.00
      2446824.96     13812774.98
#Sta/Elev= 30
  4679.8  484.92  4690.4  484.25  4701.4  483.33  4757.7  472.65  4786.2  468.45
  4800.6  467.20  4807.9  465.91  4815.1  463.47  4843.9  461.33  4850.3  459.44
  4858.3  459.30  4864.7  456.77  4879.1  456.02  4885.5  454.23  4905.9  452.47
  4943.1  450.50  5002.7  448.97  5008.3  447.39  5013.9  447.65  5020.3  445.97
  5020.5  445.47  5024.4  445.97  5053.1  452.26  5097.8  455.14  5120.6  455.81
  5259.9  463.06  5349.3  469.43  5371.7  472.87  5394.1  474.70  5447.2  484.52
#Mann=7,-1,0
  4679.8    0.16       0  4690.4    0.07       0  4757.7    0.16       0
  4905.9    0.12       0  5020.3    0.07       0  5024.4    0.12       0
  5120.6    0.16       0
Bank Sta=5020.3,5024.4
Exp/Cntr=0.3,0.1

Type RM Length L Ch R = 1,10357,470,470,470
BEGIN DESCRIPTION:
Scruggs Creek 20.0
END DESCRIPTION:
XS GIS Cut Line= 3
      2447825.03     13812825.02      2447475.00     13812625.00
      2447075.04     13812325.03
#Sta/Elev= 30
  4596.6  480.55  4647.7  476.43  4669.3  473.03  4712.5  463.74  4750.0  458.49
  4780.9  457.28  4838.5  453.04  4949.2  448.80  4964.5  448.26  4970.2  448.98
  4976.7  448.68  4986.1  446.58  4991.8  446.77  4996.9  444.25  5011.2  443.52
  5011.4  443.02  5015.4  443.52  5027.9  445.39  5036.2  447.59  5065.7  448.69
  5186.3  455.30  5236.2  458.07  5277.9  461.76  5321.6  463.62  5363.3  466.89
  5399.7  470.87  5421.6  474.41  5427.9  474.56  5450.2  477.54  5499.7  481.88
#Mann=7,-1,0
  4596.6    0.07       0  4949.2    0.16       0  5011.2    0.07       0
  5015.4    0.16       0  5065.7    0.07       0  5186.3    0.16       0
  5450.2   0.035       0
Bank Sta=5011.2,5015.4
Exp/Cntr=0.3,0.1

Type RM Length L Ch R = 1,9887,469,469,469
BEGIN DESCRIPTION:
Scruggs Creek 19.0
END DESCRIPTION:
XS GIS Cut Line= 3
      2447974.99     13812724.96      2447825.00     13812325.00
      2447524.98     13812174.99
#Sta/Elev= 30
  4572.8  480.60  4679.6  466.76  4758.8  459.60  4775.7  454.90  4797.0  451.38
  4823.4  450.32  4838.9  451.94  4844.2  450.89  4869.1  458.67  4874.5  458.76
  4893.2  451.75  4899.4  451.53  4904.7  449.25  4914.5  449.17  4945.9  445.81
  4984.8  443.51  4990.2  441.43  4995.1  441.16  4995.4  440.66  4999.4  441.16
  5013.9  441.70  5036.3  446.46  5053.1  446.76  5110.0  451.38  5114.6  451.51
  5218.6  462.23  5259.9  467.09  5290.7  472.09  5327.1  475.73  5335.4  476.68
#Mann=9,-1,0
  4572.8    0.07       0  4823.4    0.16       0  4945.9    0.12       0
  4995.1    0.07       0  4999.4    0.12       0  5110.0    0.16       0
  5114.6    0.12       0  5218.6    0.07       0  5327.1    0.16       0
Bank Sta=4995.1,4999.4
Exp/Cntr=0.3,0.1

Type RM Length L Ch R = 1,9418,421,421,421
BEGIN DESCRIPTION:
Scruggs Creek 18.0
END DESCRIPTION:
XS GIS Cut Line= 3
      2448225.01     13812225.02      2448175.00     13812025.00
      2448025.01     13811875.01
#Sta/Elev= 30
  4793.6  455.95  4811.7  454.91  4816.8  453.91  4824.5  453.81  4852.9  450.47
  4858.0  450.38  4865.8  449.35  4907.0  446.26  4917.3  444.71  4948.2  442.66
  4958.5  442.30  4981.7  439.11  4987.3  438.98  4987.6  438.48  4991.3  438.48
  4991.6  438.98  4997.2  441.15  5003.3  441.15  5013.9  442.82  5028.1  443.33
  5040.6  444.31  5084.6  446.21  5112.9  448.42  5141.2  452.62  5155.3  453.99
  5169.5  454.49  5183.6  455.80  5200.2  456.56  5208.4  457.63  5211.9  457.63
#Mann=5,-1,0
  4793.6    0.16       0  4987.3    0.07       0  4991.6    0.16       0
  5040.6    0.12       0  5200.2    0.16       0
Bank Sta=4987.3,4991.6
Exp/Cntr=0.3,0.1

Type RM Length L Ch R = 1,8997,482,482,482
BEGIN DESCRIPTION:
Scruggs Creek 17.0
END DESCRIPTION:
XS GIS Cut Line= 3
      2448624.99     13812074.96      2448525.00     13811825.00
      2448375.01     13811525.03
#Sta/Elev= 30
  4730.3  455.45  4745.1  457.31  4762.6  456.89  4774.7  449.24  4784.1  447.35
  4793.5  446.50  4798.9  446.87  4823.2  445.61  4838.0  446.22  4870.3  444.96
  4914.5  442.09  4955.1  440.49  4967.2  440.99  4990.1  439.11  4994.6  436.87
  4994.9  436.37  4999.1  436.87  5013.5  437.04  5022.6  439.79  5052.6  442.80
  5066.6  442.99  5123.5  447.82  5133.7  449.45  5142.1  449.08  5186.8  453.33
  5192.4  452.29  5214.7  453.57  5231.5  455.95  5237.1  455.46  5334.9  462.69
#Mann=6,-1,0
  4730.3    0.07       0  4914.5    0.12       0  4994.6    0.07       0
  4999.1    0.12       0  5022.6    0.16       0  5123.5    0.07       0
Bank Sta=4994.6,4999.1
Exp/Cntr=0.3,0.1

Type RM Length L Ch R = 1,8515,473,473,473
BEGIN DESCRIPTION:
Scruggs Creek 16.0
END DESCRIPTION:
XS GIS Cut Line= 3
      2448875.02     13812074.96      2448975.00     13811825.00
      2448674.99     13811474.99
#Sta/Elev= 30
  4730.9  453.72  4794.1  450.72  4823.7  448.27  4870.9  446.53  4907.2  443.12
  4913.9  441.48  4924.7  440.58  4961.1  440.48  5003.4  436.48  5005.0  435.64
  5005.3  435.14  5009.5  435.64  5010.3  435.68  5021.5  436.40  5028.1  435.77
  5035.8  437.81  5070.9  437.86  5099.4  439.89  5143.1  441.27  5163.1  442.06
  5170.8  443.53  5177.4  442.80  5191.6  443.79  5198.2  443.40  5226.1  445.27
  5255.3  446.14  5276.0  448.51  5439.7  462.29  5454.0  461.97  5461.1  462.79
#Mann=7,-1,0
  4730.9    0.07       0  5005.0    0.07       0  5009.5    0.07       0
  5010.3    0.16       0  5143.1    0.07       0  5226.1    0.16       0
  5276.0    0.07       0
Bank Sta=5005,5009.5
Exp/Cntr=0.3,0.1

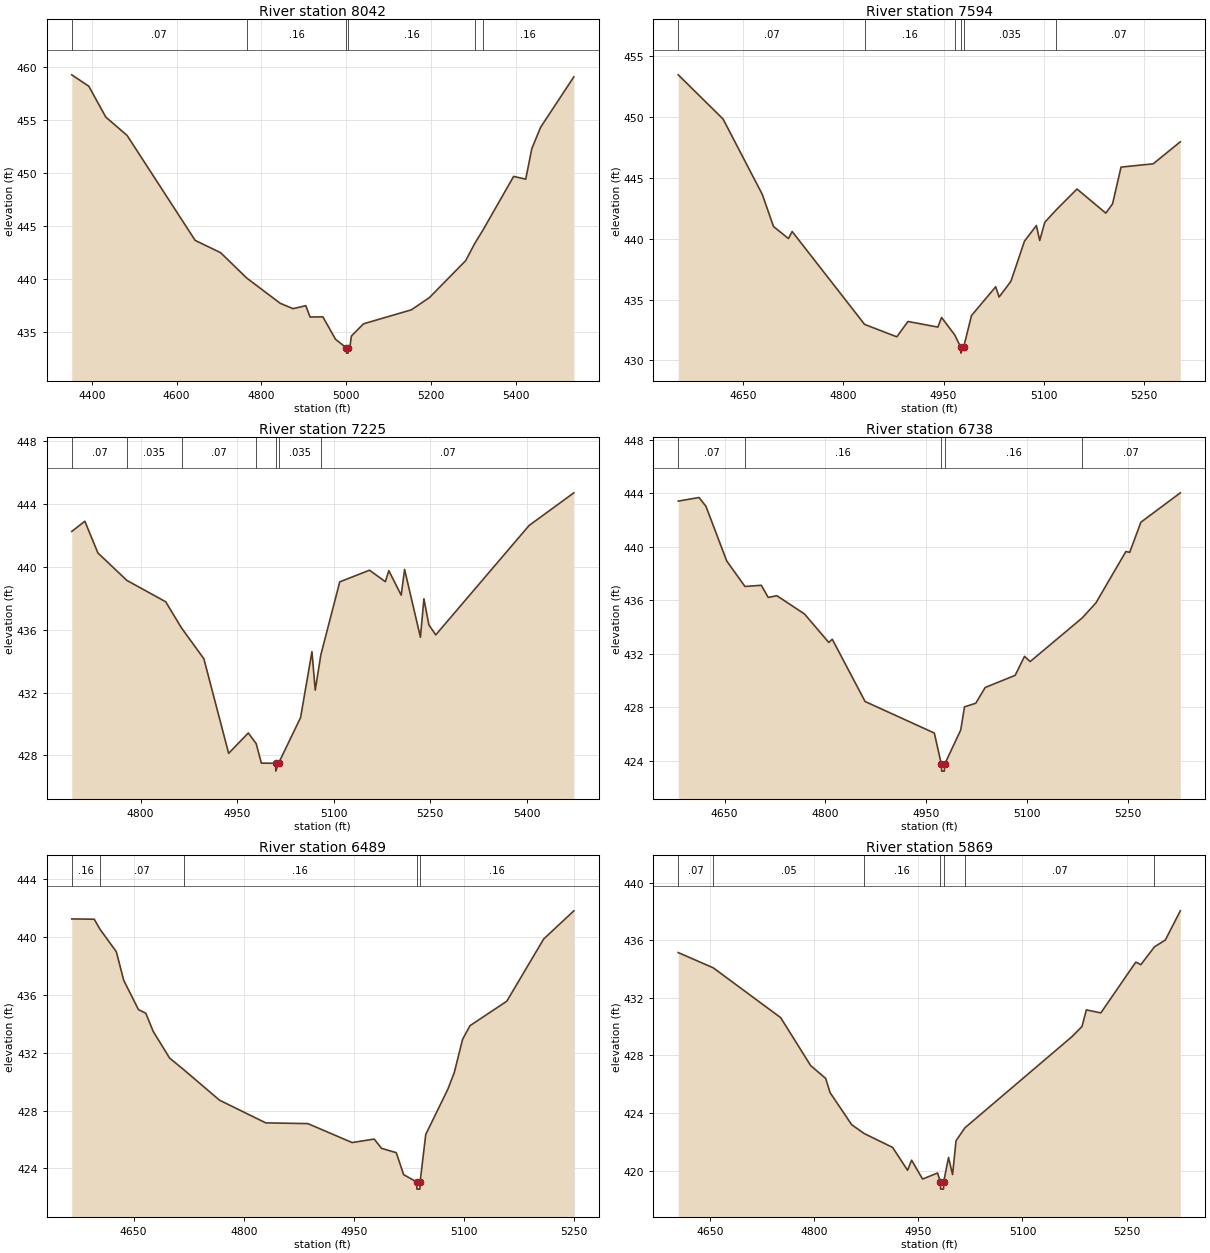
Type RM Length L Ch R = 1,8042,448,448,448
BEGIN DESCRIPTION:
Scruggs Creek 15.0
END DESCRIPTION:
XS GIS Cut Line= 3
      2449425.00     13812275.01      2449375.00     13811625.00
      2448975.03     13811275.03
#Sta/Elev= 30
  4352.9  459.23  4393.0  458.16  4433.1  455.25  4483.3  453.52  4643.8  443.63
  4703.9  442.47  4765.1  440.09  4844.4  437.70  4874.4  437.20  4904.5  437.48
  4914.6  436.41  4944.7  436.43  4974.7  434.31  5000.0  433.51  5000.4  433.01
  5004.3  433.01  5004.6  433.51  5008.2  433.51  5012.0  434.62  5040.4  435.77
  5153.4  437.09  5196.1  438.25  5281.5  441.73  5302.7  443.34  5321.9  444.59
  5394.4  449.66  5422.9  449.40  5437.2  452.27  5458.0  454.29  5536.3  459.04
#Mann=6,-1,0
  4352.9    0.07       0  4765.1    0.16       0  5000.0    0.07       0
  5004.6    0.16       0  5302.7   0.035       0  5321.9    0.16       0
Bank Sta=5000,5004.6
Exp/Cntr=0.3,0.1

Type RM Length L Ch R = 1,7594,369,369,369
BEGIN DESCRIPTION:
Scruggs Creek 14.0
END DESCRIPTION:
XS GIS Cut Line= 3
      2449524.98     13812175.04      2449725.00     13811775.00
      2449775.00     13811474.99
#Sta/Elev= 30
  4553.0  453.46  4620.1  449.83  4678.8  443.64  4695.6  441.00  4718.0  440.01
  4723.5  440.59  4831.9  432.96  4880.1  431.94  4896.8  433.20  4941.6  432.74
  4947.1  433.53  4966.9  432.09  4975.6  431.10  4975.9  430.60  4980.2  431.10
  4991.9  433.69  5028.1  436.05  5033.2  435.21  5050.9  436.50  5071.2  439.80
  5089.0  441.08  5094.0  439.85  5101.6  441.35  5118.9  442.38  5149.8  444.08
  5192.9  442.10  5203.0  442.86  5215.7  445.88  5263.8  446.15  5304.4  447.96
#Mann=6,-1,0
  4553.0    0.07       0  4831.9    0.16       0  4966.9   0.035       0
  4975.6   0.035       0  4980.2   0.035       0  5118.9    0.07       0
Bank Sta=4975.6,4980.2
Exp/Cntr=0.3,0.1

Type RM Length L Ch R = 1,7225,487,487,487
BEGIN DESCRIPTION:
Scruggs Creek 13.0
END DESCRIPTION:
XS GIS Cut Line= 3
      2450025.00     13812325.02      2449949.88     13811897.41
      2449825.00     13811575.01
#Sta/Elev= 30
  4693.0  442.27  4713.3  442.92  4733.6  440.90  4778.6  439.15  4838.9  437.79
  4863.5  436.12  4898.2  434.16  4936.7  428.13  4967.2  429.43  4979.5  428.75
  4987.5  427.51  5009.6  427.50  5009.9  427.00  5014.2  427.50  5048.4  430.41
  5066.1  434.61  5071.2  432.16  5079.9  434.41  5109.3  439.06  5155.5  439.80
  5180.1  439.07  5185.5  439.77  5204.7  438.21  5210.0  439.85  5234.6  435.53
  5240.0  437.98  5247.7  436.32  5258.4  435.68  5403.4  442.65  5472.9  444.73
#Mann=7,-1,0
  4693.0    0.07       0  4778.6   0.035       0  4863.5    0.07       0
  4979.5   0.035       0  5009.6   0.035       0  5014.2   0.035       0
  5079.9    0.07       0
Bank Sta=5009.6,5014.2
Exp/Cntr=0.3,0.1

Type RM Length L Ch R = 1,6738,249,249,249
BEGIN DESCRIPTION:
Scruggs Creek 12.0
END DESCRIPTION:
XS GIS Cut Line= 3
      2450275.00     13812125.02      2450175.00     13811725.00
      2449875.04     13811575.02
#Sta/Elev= 30
  4580.9  443.42  4611.8  443.69  4622.2  443.03  4653.1  438.94  4680.3  437.03
  4704.6  437.12  4714.9  436.21  4727.8  436.34  4769.0  434.97  4805.1  432.84
  4810.3  433.08  4859.2  428.42  4962.3  426.06  4972.8  423.71  4973.2  423.21
  4977.2  423.21  4977.5  423.71  5001.6  426.29  5007.2  428.02  5024.0  428.29
  5038.0  429.47  5082.7  430.38  5096.6  431.80  5105.0  431.41  5182.6  434.68
  5202.9  435.80  5247.6  439.65  5253.2  439.58  5269.9  441.84  5328.6  444.04
#Mann=5,-1,0
  4580.9    0.07       0  4680.3    0.16       0  4972.8    0.07       0
  4977.5    0.16       0  5182.6    0.07       0
Bank Sta=4972.8,4977.5
Exp/Cntr=0.3,0.1

Type RM Length L Ch R = 1,6489,620,620,620
BEGIN DESCRIPTION:
E20779
END DESCRIPTION:
XS GIS Cut Line= 2
      2450340.06     13812105.50      2450392.09     13811423.98
#Sta/Elev= 30
  4565.8  441.25  4596.4  441.23  4604.2  440.54  4626.5  438.98  4636.5  437.01
  4656.6  434.98  4666.6  434.73  4676.6  433.48  4699.0  431.63  4718.0  430.84
  4766.9  428.72  4829.9  427.15  4887.2  427.10  4947.4  425.79  4977.5  426.03
  4987.5  425.39  5007.6  425.09  5017.6  423.57  5035.3  423.07  5035.7  422.57
  5039.7  422.57  5040.0  423.07  5047.7  426.35  5077.8  429.48  5086.6  430.64
  5097.8  432.92  5107.9  433.87  5158.0  435.56  5208.2  439.86  5249.3  441.81
#Mann=5,-1,0
  4565.8    0.16       0  4604.2    0.07       0  4718.0    0.16       0
  5035.3    0.07       0  5040.0    0.16       0
Bank Sta=5035.3,5040
Exp/Cntr=0.3,0.1

Type RM Length L Ch R = 1,5869,461,461,461
BEGIN DESCRIPTION:
Scruggs Creek 11.0
END DESCRIPTION:
XS GIS Cut Line= 3
      2450525.00     13812125.00      2450725.00     13811775.00
      2450474.97     13811574.98
#Sta/Elev= 30
  4604.1  435.14  4654.6  434.08  4751.7  430.62  4794.9  427.29  4816.5  426.40
  4822.9  425.41  4853.9  423.19  4872.0  422.57  4912.9  421.61  4934.5  420.02
  4940.3  420.72  4956.1  419.41  4977.7  419.83  4981.8  419.21  4982.2  418.71
  4986.2  418.71  4986.5  419.21  4993.5  420.91  4999.3  419.72  5004.3  422.07
  5017.1  422.97  5171.3  429.30  5185.7  430.00  5192.1  431.16  5212.9  430.95
  5263.3  434.48  5270.5  434.30  5290.2  435.54  5305.8  436.01  5327.4  438.04
#Mann=7,-1,0
  4604.1    0.07       0  4654.6    0.05       0  4872.0    0.16       0
  4981.8    0.07       0  4986.5    0.16       0  5017.1    0.07       0
  5290.2    0.16       0
Bank Sta=4981.8,4986.5
Exp/Cntr=0.3,0.1