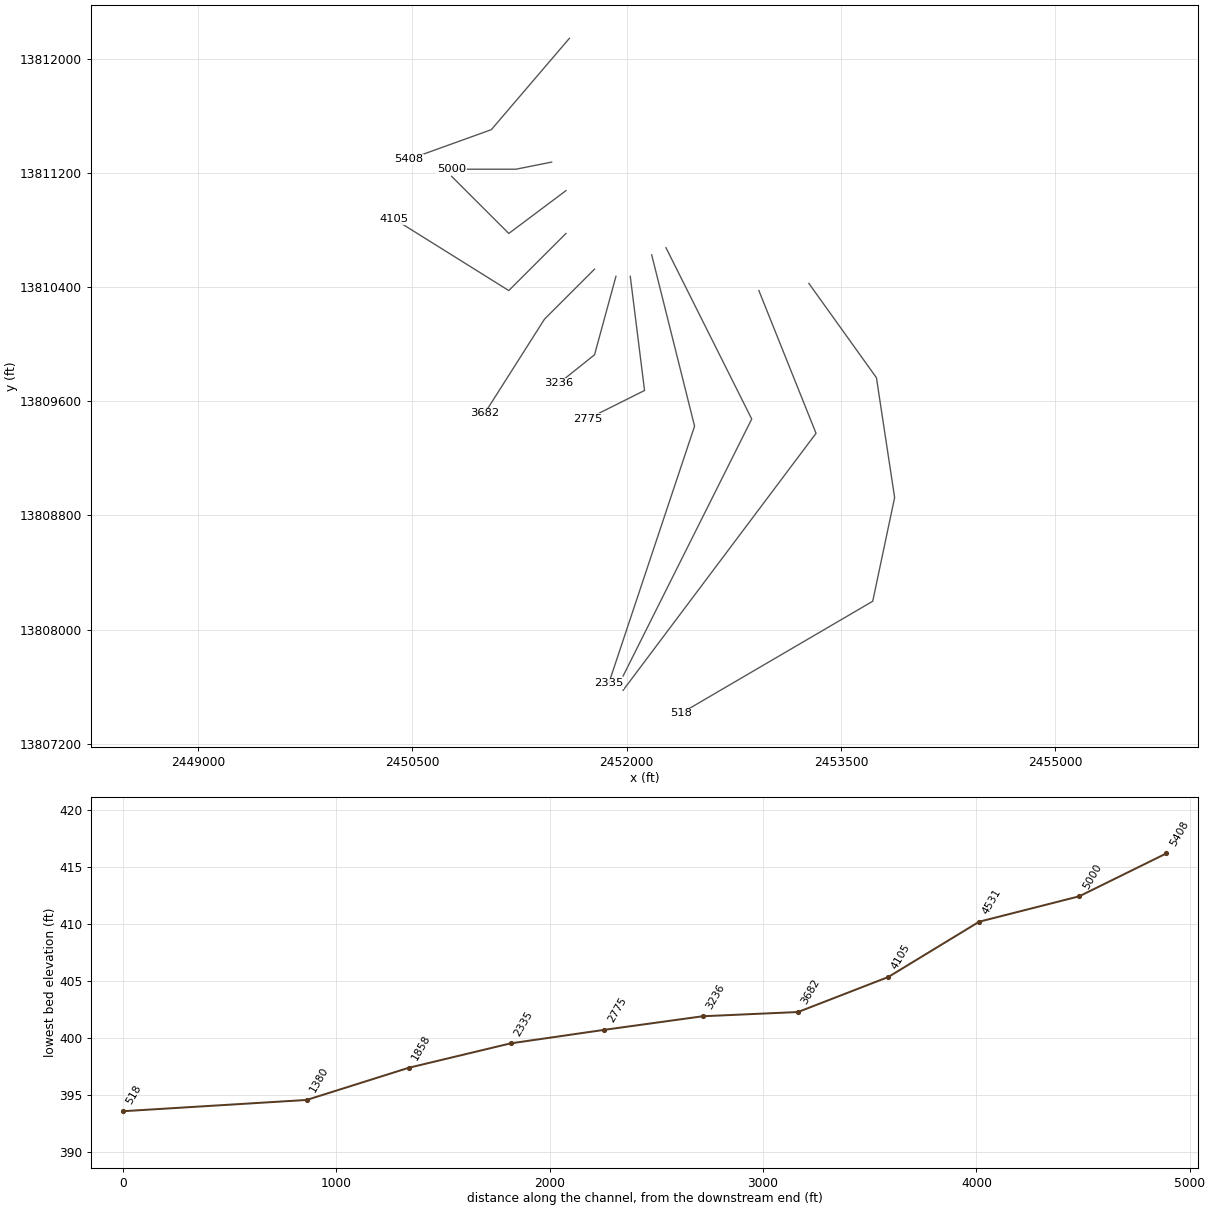
HEC-RAS study Scruggs Creek.prj: Scruggs Creek Base Level Engineering

--- Scruggs Creek.g01 (geometry) --- (continued)

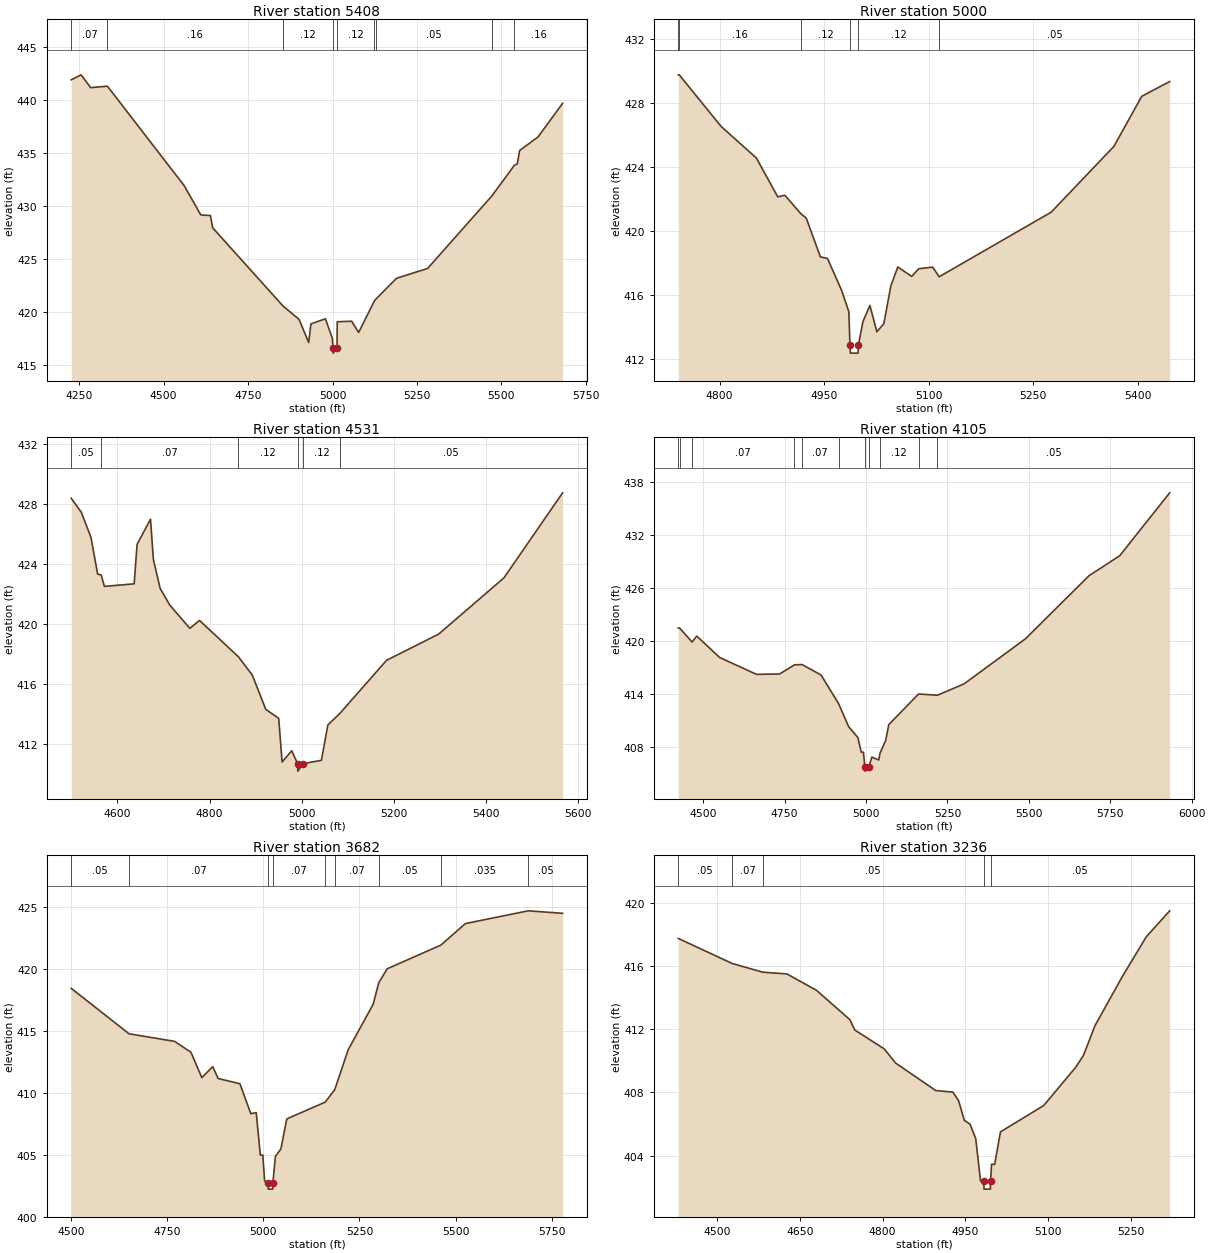
Type RM Length L Ch R = 1,5408,408,408,408
BEGIN DESCRIPTION:
E20778
END DESCRIPTION:
XS GIS Cut Line= 3
      2451599.04     13812141.90      2451052.80     13811502.02
      2450475.37     13811293.94
#Sta/Elev= 30
  4226.3  441.94  4255.4  442.41  4283.9  441.20  4333.4  441.34  4560.6  431.96
  4610.0  429.19  4638.5  429.13  4645.1  427.98  4853.3  420.60  4900.9  419.34
  4929.5  417.15  4936.1  418.91  4978.9  419.39  4999.7  417.54  5001.4  416.65
  5001.9  416.15  5013.4  416.65  5014.0  419.11  5056.8  419.16  5077.4  418.10
  5124.0  421.07  5127.9  421.23  5189.5  423.21  5281.6  424.14  5471.6  430.97
  5538.5  433.87  5547.2  434.01  5554.2  435.27  5608.6  436.55  5681.4  439.72
#Mann=9,-1,0
  4226.3    0.07       0  4333.4    0.16       0  4853.3    0.12       0
  5001.4    0.07       0  5013.4    0.12       0  5124.0    0.07       0
  5127.9    0.05       0  5471.6    0.07       0  5538.5    0.16       0
Bank Sta=5001.4,5013.4
Exp/Cntr=0.3,0.1

Type RM Length L Ch R = 1,5000,469,469,469
BEGIN DESCRIPTION:
Scruggs Creek 10.0
END DESCRIPTION:
XS GIS Cut Line= 3
      2451474.97     13811274.99      2451225.00     13811225.00
      2450775.02     13811225.00
#Sta/Elev= 30
  4740.8  429.77  4742.2  429.77  4802.0  426.56  4852.9  424.57  4883.5  422.15
  4893.7  422.25  4917.0  421.08  4924.3  420.83  4944.7  418.40  4954.9  418.30
  4975.3  416.29  4985.5  414.97  4987.1  412.89  4987.6  412.39  4998.7  412.39
  4999.2  412.89  5005.7  414.36  5015.7  415.37  5025.7  413.72  5035.7  414.23
  5045.7  416.58  5055.7  417.77  5075.7  417.18  5085.7  417.66  5105.7  417.76
  5115.1  417.16  5275.7  421.19  5365.7  425.30  5405.7  428.43  5445.7  429.35
#Mann=6,-1,0
  4740.8    0.07       0  4742.2    0.16       0  4917.0    0.12       0
  4987.1    0.07       0  4999.2    0.12       0  5115.1    0.05       0
Bank Sta=4987.1,4999.2
Exp/Cntr=0.3,0.1

Type RM Length L Ch R = 1,4531,426,426,426
BEGIN DESCRIPTION:
Scruggs Creek 9.0
END DESCRIPTION:
XS GIS Cut Line= 3
      2451575.04     13811075.03      2451175.00     13810775.00
      2450775.02     13811174.98
#Sta/Elev= 30
  4500.0  428.36  4521.9  427.42  4542.8  425.75  4557.3  423.30  4565.0  423.24
  4571.9  422.48  4636.5  422.65  4642.8  425.28  4671.9  426.96  4678.2  424.27
  4692.8  422.35  4713.6  421.24  4757.3  419.68  4778.2  420.21  4862.5  417.79
  4892.8  416.56  4921.9  414.28  4950.0  413.68  4957.3  410.77  4978.2  411.52
  4990.9  410.66  4991.4  410.16  5003.0  410.66  5042.5  410.88  5056.6  413.24
  5082.3  414.00  5183.9  417.55  5297.0  419.30  5438.5  423.05  5565.7  428.72
#Mann=6,-1,0
  4500.0    0.05       0  4565.0    0.07       0  4862.5    0.12       0
  4990.9    0.07       0  5003.0    0.12       0  5082.3    0.05       0
Bank Sta=4990.9,5003
Exp/Cntr=0.3,0.1

Type RM Length L Ch R = 1,4105,423,423,423
BEGIN DESCRIPTION:
Scruggs Creek 8.0
END DESCRIPTION:
XS GIS Cut Line= 3
      2451574.98     13810774.98      2451175.00     13810375.00
      2450374.97     13810875.02
#Sta/Elev= 30
  4423.3  421.50  4427.5  421.48  4465.9  419.90  4479.8  420.58  4550.6  418.15
  4663.7  416.25  4734.4  416.29  4780.0  417.32  4803.2  417.36  4861.7  416.18
  4915.5  412.95  4946.5  410.34  4974.8  409.11  4985.4  407.45  4991.9  407.45
  4996.5  405.81  4997.0  405.31  5008.6  405.81  5017.9  406.90  5039.1  406.57
  5043.0  407.36  5060.3  408.78  5069.7  410.56  5161.3  414.03  5219.2  413.89
  5300.9  415.17  5489.6  420.27  5684.7  427.40  5779.1  429.66  5932.4  436.77
#Mann=11,-1,0
  4423.3    0.07       0  4427.5    0.05       0  4465.9    0.07       0
  4780.0   0.035       0  4803.2    0.07       0  4915.5   0.035       0
  4996.5   0.035       0  5008.6   0.035       0  5043.0    0.12       0
  5161.3    0.07       0  5219.2    0.05       0
Bank Sta=4996.5,5008.6
Exp/Cntr=0.3,0.1

Type RM Length L Ch R = 1,3682,446,446,446
BEGIN DESCRIPTION:
Scruggs Creek 7.0
END DESCRIPTION:
XS GIS Cut Line= 3
      2451774.98     13810524.98      2451425.00     13810175.00
      2451005.98     13809514.68
#Sta/Elev= 30
  4501.1  418.45  4651.5  414.78  4769.8  414.17  4812.2  413.29  4840.5  411.24
  4868.8  412.13  4882.9  411.17  4939.5  410.75  4967.8  408.33  4981.9  408.42
  4992.5  404.99  4999.0  404.99  5003.7  402.89  5012.7  402.74  5013.2  402.24
  5024.7  402.24  5025.2  402.74  5031.6  404.87  5046.0  405.49  5061.3  407.91
  5160.9  409.26  5185.8  410.26  5221.1  413.51  5285.8  417.17  5300.3  418.90
  5322.2  420.03  5461.6  421.94  5525.5  423.68  5688.7  424.71  5778.1  424.51
#Mann=9,-1,0
  4501.1    0.05       0  4651.5    0.07       0  5012.7    0.07       0
  5025.2    0.07       0  5160.9    0.05       0  5185.8    0.07       0
  5300.3    0.05       0  5461.6   0.035       0  5688.7    0.05       0
Bank Sta=5012.7,5025.2
Exp/Cntr=0.3,0.1

Type RM Length L Ch R = 1,3236,461,461,461
BEGIN DESCRIPTION:
Scruggs Creek 6.0
END DESCRIPTION:
XS GIS Cut Line= 3
      2451924.99     13810474.96      2451775.00     13809925.00
      2451525.00     13809725.00
#Sta/Elev= 30
  4429.9  417.76  4527.8  416.17  4583.0  415.62  4626.8  415.51  4680.4  414.47
  4740.8  412.61  4749.5  411.96  4803.0  410.76  4823.7  409.86  4896.3  408.12
  4927.4  408.02  4937.8  407.47  4948.1  406.23  4958.5  405.99  4968.8  405.07
  4977.5  402.38  4983.3  402.37  4983.8  401.87  4995.3  401.87  4995.8  402.37
  4997.4  403.44  5003.1  403.44  5013.6  405.50  5092.0  407.17  5149.6  409.58
  5164.0  410.35  5184.8  412.23  5234.5  415.35  5277.7  417.86  5320.1  419.51
#Mann=5,-1,0
  4429.9    0.05       0  4527.8    0.07       0  4583.0    0.05       0
  4983.3    0.05       0  4995.8    0.05       0
Bank Sta=4983.3,4995.8
Exp/Cntr=0.3,0.1

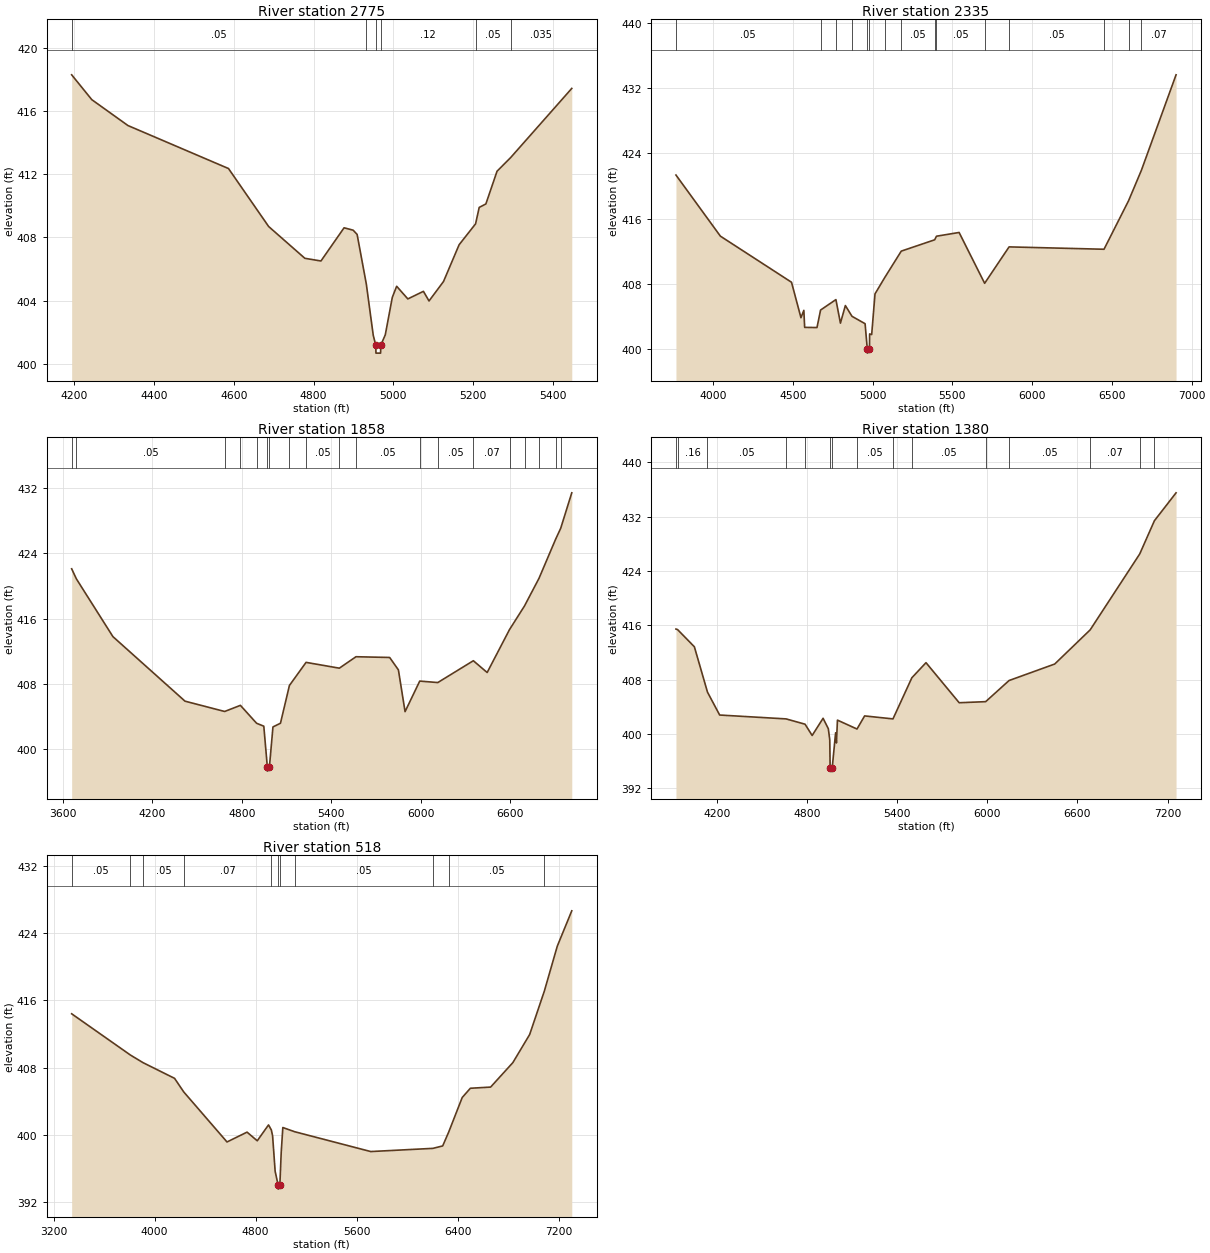
Type RM Length L Ch R = 1,2775,440,440,440
BEGIN DESCRIPTION:
Scruggs Creek 5.0
END DESCRIPTION:
XS GIS Cut Line= 3
      2452025.00     13810475.02      2452125.00     13809675.00
      2451724.96     13809474.98
#Sta/Elev= 30
  4193.8  418.29  4244.2  416.72  4334.9  415.08  4586.9  412.36  4687.6  408.69
  4778.3  406.68  4818.6  406.51  4876.6  408.61  4899.3  408.46  4909.3  408.19
  4932.3  405.06  4949.7  401.81  4956.0  401.18  4956.5  400.68  4968.1  400.68
  4968.6  401.18  4979.9  401.84  4997.5  404.21  5008.4  404.91  5036.4  404.11
  5075.5  404.59  5089.5  403.98  5125.8  405.21  5165.0  407.54  5206.2  408.86
  5215.3  409.90  5232.0  410.12  5260.0  412.19  5294.0  413.05  5447.3  417.43
#Mann=6,-1,0
  4193.8    0.05       0  4932.3    0.12       0  4956.0    0.07       0
  4968.6    0.12       0  5206.2    0.05       0  5294.0   0.035       0
Bank Sta=4956,4968.6
Exp/Cntr=0.3,0.1

Type RM Length L Ch R = 1,2335,477,477,477
BEGIN DESCRIPTION:
Scruggs Creek 4.0
END DESCRIPTION:
XS GIS Cut Line= 3
      2452174.99     13810625.03      2452475.00     13809425.00
      2451875.01     13807625.03
#Sta/Elev= 30
  3768.0  421.35  4046.3  413.85  4492.2  408.19  4551.4  403.84  4569.5  404.74
  4574.6  402.65  4651.9  402.63  4674.4  404.78  4770.5  406.06  4798.8  403.17
  4829.7  405.33  4871.2  404.01  4953.4  403.10  4967.2  399.99  4967.7  399.49
  4980.9  399.99  4981.8  401.85  4994.7  401.77  5015.5  406.76  5075.4  408.73
  5180.1  412.01  5389.5  413.40  5400.7  413.84  5542.6  414.30  5702.6  408.06
  5855.8  412.53  6450.8  412.24  6604.8  418.20  6684.8  421.92  6902.3  433.65
#Mann=15,-1,0
  3768.0    0.05       0  4674.4    0.07       0  4770.5   0.035       0
  4871.2    0.12       0  4967.2    0.07       0  4980.9    0.12       0
  5075.4    0.07       0  5180.1    0.05       0  5389.5   0.035       0
  5400.7    0.05       0  5702.6    0.07       0  5855.8    0.05       0
  6450.8    0.07       0  6604.8    0.05       0  6684.8    0.07       0
Bank Sta=4967.2,4980.9
Exp/Cntr=0.3,0.1

Type RM Length L Ch R = 1,1858,478,478,478
BEGIN DESCRIPTION:
Scruggs Creek 3.0
END DESCRIPTION:
XS GIS Cut Line= 3
      2452274.99     13810675.02      2452875.00     13809475.00
      2451975.01     13807675.02
#Sta/Elev= 30
  3658.3  422.11  3690.2  420.87  3935.0  413.81  4418.6  405.91  4684.4  404.65
  4790.0  405.40  4898.5  403.21  4946.9  402.85  4970.7  397.85  4971.2  397.35
  4984.5  397.85  5008.3  402.76  5058.7  403.21  5118.7  407.83  5230.4  410.66
  5453.6  409.95  5565.2  411.35  5791.0  411.26  5849.7  409.74  5894.4  404.63
  5992.8  408.37  6113.9  408.19  6352.2  410.86  6445.0  409.42  6594.8  414.67
  6695.6  417.57  6793.0  420.96  6904.6  425.75  6938.2  427.07  7012.4  431.41
#Mann=19,-1,0
  3658.3    0.07       0  3690.2    0.05       0  4684.4    0.07       0
  4790.0   0.035       0  4898.5    0.12       0  4970.7    0.07       0
  4984.5    0.12       0  5118.7    0.07       0  5230.4    0.05       0
  5453.6   0.035       0  5565.2    0.05       0  5992.8    0.07       0
  6113.9    0.05       0  6352.2    0.07       0  6594.8    0.05       0
  6695.6    0.07       0  6793.0    0.05       0  6904.6    0.16       0
  6938.2    0.07       0
Bank Sta=4970.7,4984.5
Exp/Cntr=0.3,0.1

Type RM Length L Ch R = 1,1380,862,862,862
BEGIN DESCRIPTION:
Scruggs Creek 2.0
END DESCRIPTION:
XS GIS Cut Line= 3
      2452924.99     13810375.02      2453325.00     13809375.00
      2451974.97     13807574.97
#Sta/Elev= 30
  3929.3  415.45  3940.1  415.37  4051.8  412.84  4139.1  406.16  4220.1  402.79
  4662.0  402.22  4788.1  401.44  4835.4  399.78  4908.1  402.31  4943.1  400.77
  4952.5  399.13  4955.0  395.03  4955.5  394.53  4968.9  395.03  4991.5  400.18
  4996.9  398.68  5003.7  402.04  5133.7  400.73  5184.5  402.66  5373.1  402.22
  5498.8  408.28  5592.8  410.50  5813.6  404.60  5989.8  404.76  6145.3  407.87
  6449.1  410.30  6685.0  415.33  7014.7  426.51  7112.4  431.40  7256.4  435.51
#Mann=15,-1,0
  3929.3    0.07       0  3940.1    0.16       0  4139.1    0.05       0
  4662.0   0.035       0  4788.1    0.12       0  4955.0    0.07       0
  4968.9    0.12       0  5133.7    0.05       0  5373.1   0.035       0
  5498.8    0.05       0  5989.8    0.07       0  6145.3    0.05       0
  6685.0    0.07       0  7014.7    0.16       0  7112.4    0.07       0
Bank Sta=4955,4968.9
Exp/Cntr=0.3,0.1

Type RM Length L Ch R = 1,518,0,0,0
BEGIN DESCRIPTION:
Scruggs Creek 1.0
END DESCRIPTION:
XS GIS Cut Line= 5
      2453275.01     13810424.98      2453747.67     13809764.40
      2453875.00     13808925.00      2453721.66     13808198.46
      2452379.72     13807413.06
#Sta/Elev= 30
  3343.4  414.40  3808.7  409.49  3909.1  408.58  4157.9  406.72  4230.2  405.11
  4573.0  399.15  4731.6  400.32  4812.5  399.29  4901.6  401.18  4923.9  400.58
  4933.9  399.89  4954.1  395.66  4977.5  394.04  4978.0  393.54  4991.4  394.04
  5002.1  397.90  5014.9  400.87  5108.3  400.37  5710.9  398.01  6203.4  398.39
  6280.4  398.68  6328.0  400.33  6434.9  404.44  6499.4  405.54  6659.7  405.68
  6835.7  408.59  6968.7  411.93  7084.8  417.09  7187.6  422.45  7302.1  426.65
#Mann=11,-1,0
  3343.4    0.05       0  3808.7   0.035       0  3909.1    0.05       0
  4230.2    0.07       0  4923.9    0.16       0  4977.5    0.07       0
  4991.4    0.16       0  5108.3    0.05       0  6203.4    0.07       0
  6328.0    0.05       0  7084.8    0.07       0
Bank Sta=4977.5,4991.4
Exp/Cntr=0.3,0.1

Chan Stop Cuts=-1