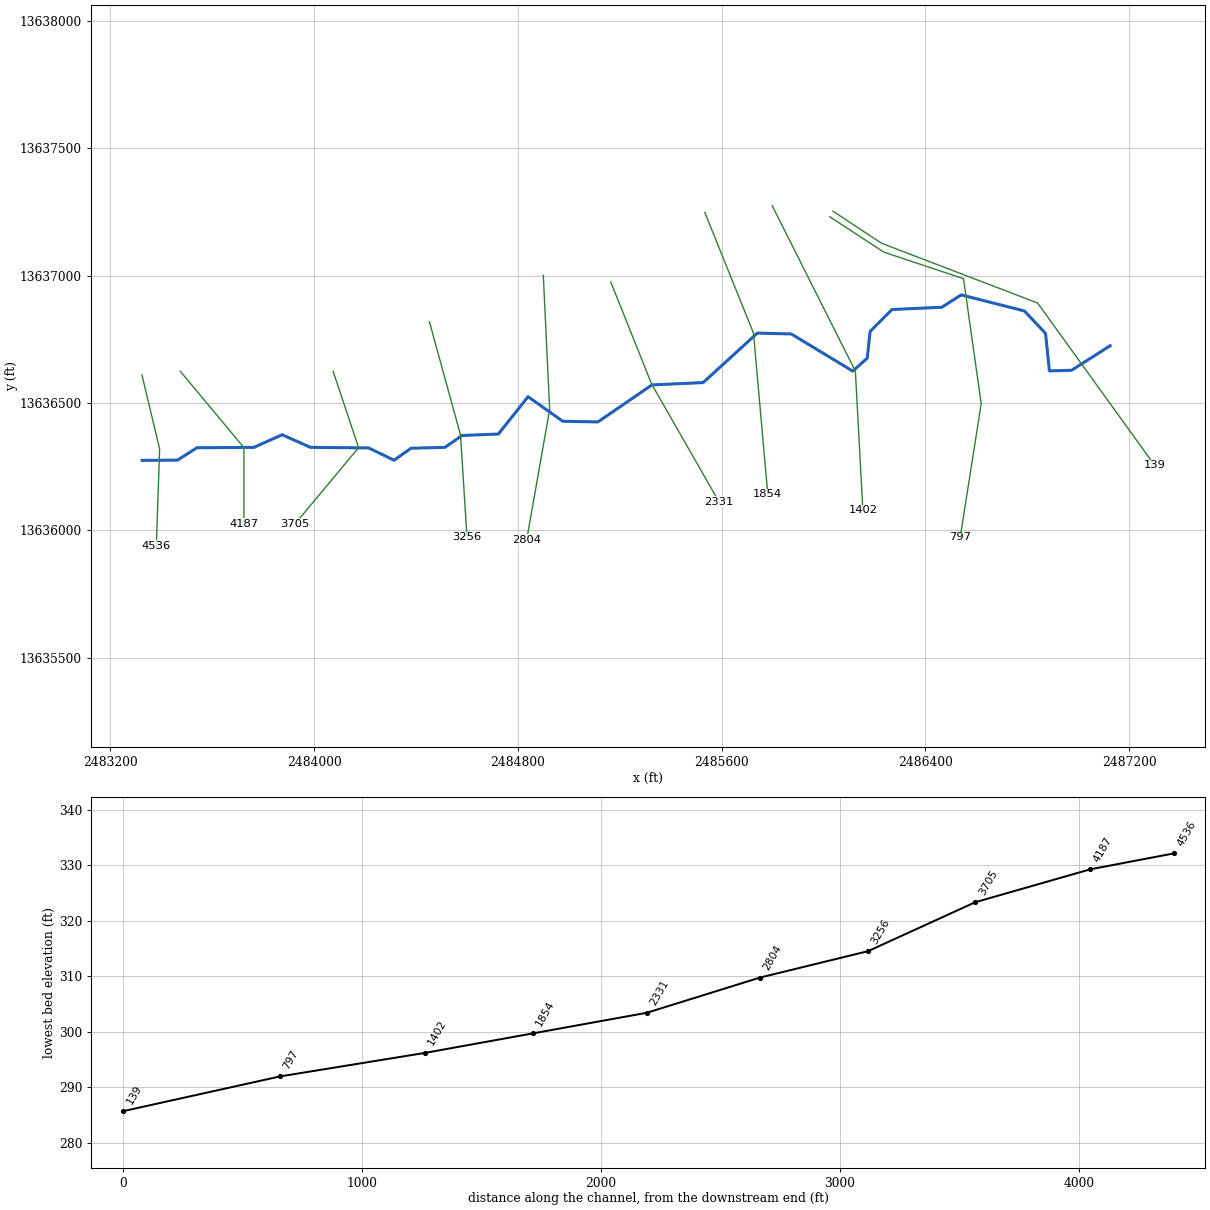
--- Stream0305.prj (project) ---

Proj Title=Stream0305 Base Level Engineering
Current Plan=p01
Default Exp/Contr=0.3,0.1
English Units
Geom File=g01
Flow File=f01
Plan File=p01
BEGIN DESCRIPTION:
Stream0305
END DESCRIPTION:

--- Stream0305.p01 (plan) ---

Plan Title=Multiple Run
Short Identifier=Multiple
Geom File=g01
Flow File=f01
Subcritical Flow
K Sum by GR= 0
Std Step Tol= 0.01
Critical Tol= 0.01
Num of Std Step Trials= 20
Max Error Tol= 0.3
Flow Tol Ratio= 0.001
Split Flow NTrial= 30
Split Flow Tol= 0.02
Split Flow Ratio= 0.02
Log Output Level= 0
Friction Slope Method= 1
Unsteady Friction Slope Method= 2
Unsteady Bridges Friction Slope Method= 1
Parabolic Critical Depth
Global Vel Dist=  1 , 1 , 1
Global Log Level= 0
CheckData=True
Encroach Param= -1, 0, 0, 0
BEGIN DESCRIPTION:
Multiple Run
END DESCRIPTION:

--- Stream0305.f01 (steady flow) ---

Flow Title=Multiple
Number of Profiles=7
Profile Names=10-year,25-year,50-year,1pct_min,100-year,1pct_plu,500-year
River Rch & RM= Stream0305,Reach-1,4536
     615     994    1337     873    1741    3474    2921
Boundary for River Rch & Prof#=Stream0305,Reach-1,1
Up Type=0
Dn Type=3
Dn Slope=0.005
Boundary for River Rch & Prof#=Stream0305,Reach-1,2
Up Type=0
Dn Type=3
Dn Slope=0.005
Boundary for River Rch & Prof#=Stream0305,Reach-1,3
Up Type=0
Dn Type=3
Dn Slope=0.005
Boundary for River Rch & Prof#=Stream0305,Reach-1,4
Up Type=0
Dn Type=3
Dn Slope=0.005
Boundary for River Rch & Prof#=Stream0305,Reach-1,5
Up Type=0
Dn Type=3
Dn Slope=0.005
Boundary for River Rch & Prof#=Stream0305,Reach-1,6
Up Type=0
Dn Type=3
Dn Slope=0.005
Boundary for River Rch & Prof#=Stream0305,Reach-1,7
Up Type=0
Dn Type=3
Dn Slope=0.005

--- Stream0305.g01 (geometry) ---

Geom Title=Existing Conditions

River Reach=Stream0305,Reach-1
Reach XY= 30
      2483325.00     13636275.00      2483464.52     13636276.17
      2483540.22     13636324.48      2483764.50     13636326.22
      2483875.00     13636375.82      2483985.50     13636326.22
      2484214.50     13636323.76      2484314.31     13636275.77
      2484380.93     13636322.70      2484514.49     13636326.23
      2484580.94     13636372.73      2484723.75     13636378.46
      2484840.24     13636525.16      2484976.47     13636428.54
      2485114.56     13636426.04      2485326.55     13636571.25
      2485527.45     13636580.46      2485740.16     13636774.64
      2485873.44     13636771.26      2486114.53     13636625.48
      2486171.47     13636676.22      2486182.86     13636781.19
      2486268.79     13636867.20      2486464.50     13636876.22
      2486540.27     13636924.62      2486788.33     13636861.61
      2486871.46     13636773.54      2486886.53     13636626.37
      2486973.34     13636628.63      2487125.00     13636725.00

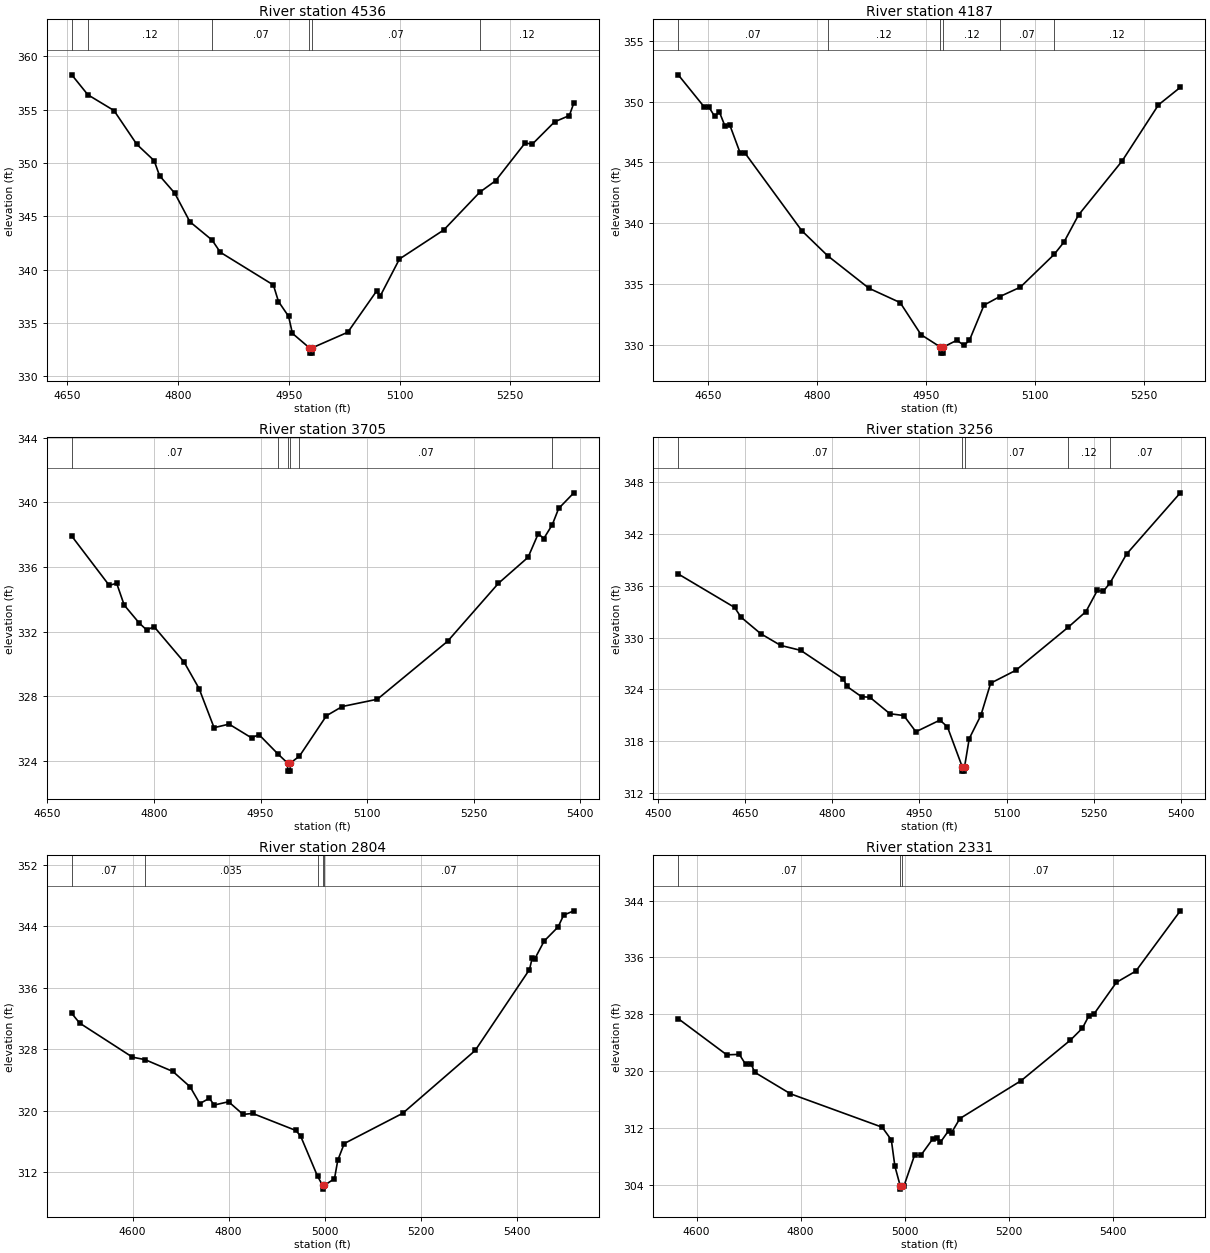
Type RM Length L Ch R = 1,4536,349,349,349
BEGIN DESCRIPTION:
XS6426
END DESCRIPTION:
XS GIS Cut Line= 3
      2483324.57     13636610.65      2483394.01     13636319.88
      2483381.02     13635938.95
#Sta/Elev= 30
  4655.9  358.26  4677.7  356.39  4713.1  354.91  4744.0  351.74  4767.5  350.21
  4774.8  348.80  4795.4  347.16  4815.9  344.48  4846.0  342.76  4857.1  341.62
  4929.0  338.55  4935.9  337.00  4949.6  335.61  4954.8  334.01  4977.7  332.66
  4978.0  332.16  4981.5  332.16  4981.7  332.66  5029.8  334.12  5068.7  337.97
  5073.7  337.51  5099.8  340.99  5159.8  343.71  5208.7  347.26  5229.9  348.32
  5269.9  351.86  5279.9  351.77  5309.9  353.85  5329.9  354.44  5336.0  355.62
#Mann=6,-1,0
  4655.9    0.07       0  4677.7    0.12       0  4846.0    0.07       0
  4977.7    0.05       0  4981.7    0.07       0  5208.7    0.12       0
Bank Sta=4977.7,4981.7
Exp/Cntr=0.3,0.1

Type RM Length L Ch R = 1,4187,482,482,482
BEGIN DESCRIPTION:
Stream0305 8.0
END DESCRIPTION:
XS GIS Cut Line= 3
      2483475.01     13636624.99      2483725.00     13636325.00
      2483725.00     13636025.00
#Sta/Elev= 30
  4609.1  352.21  4644.9  349.56  4651.4  349.54  4659.2  348.79  4665.7  349.15
  4673.5  347.97  4680.0  348.08  4694.3  345.77  4700.9  345.77  4779.0  339.38
  4814.7  337.31  4871.4  334.64  4914.3  333.46  4943.0  330.82  4969.6  329.80
  4969.9  329.30  4973.4  329.30  4973.6  329.80  4992.4  330.36  5002.1  329.93
  5009.6  330.36  5029.6  333.25  5051.2  333.95  5079.6  334.73  5126.0  337.42
  5139.6  338.44  5159.6  340.67  5219.6  345.12  5269.6  349.74  5299.6  351.18
#Mann=6,-1,0
  4609.1    0.07       0  4814.7    0.12       0  4969.6    0.05       0
  4973.6    0.12       0  5051.2    0.07       0  5126.0    0.12       0
Bank Sta=4969.6,4973.6
Exp/Cntr=0.3,0.1

Type RM Length L Ch R = 1,3705,449,449,449
BEGIN DESCRIPTION:
Stream0305 7.0
END DESCRIPTION:
XS GIS Cut Line= 3
      2484075.00     13636624.99      2484175.00     13636325.00
      2483925.02     13636025.02
#Sta/Elev= 30
  4684.2  337.91  4736.9  334.86  4747.4  334.99  4758.0  333.64  4779.1  332.53
  4789.6  332.10  4800.1  332.30  4842.3  330.11  4863.4  328.47  4884.5  326.05
  4905.6  326.27  4937.2  325.42  4947.7  325.62  4974.0  324.44  4987.9  323.86
  4988.1  323.36  4991.6  323.36  4991.9  323.86  5004.7  324.29  5042.7  326.79
  5064.9  327.36  5114.3  327.81  5213.2  331.40  5284.8  334.99  5326.5  336.60
  5340.8  338.06  5348.6  337.76  5360.6  338.62  5369.5  339.62  5390.9  340.59
#Mann=6,-1,0
  4684.2    0.07       0  4974.0    0.12       0  4987.9    0.05       0
  4991.9    0.12       0  5004.7    0.07       0  5360.6    0.12       0
Bank Sta=4987.9,4991.9
Exp/Cntr=0.3,0.1

Type RM Length L Ch R = 1,3256,452,452,452
BEGIN DESCRIPTION:
Stream0305 6.0
END DESCRIPTION:
XS GIS Cut Line= 3
      2484453.04     13636819.01      2484575.00     13636375.00
      2484600.61     13635972.67
#Sta/Elev= 30
  4535.1  337.37  4632.1  333.49  4643.0  332.37  4677.0  330.45  4711.4  329.09
  4745.8  328.52  4819.3  325.21  4825.1  324.35  4850.4  323.15  4864.7  323.09
  4899.1  321.18  4923.0  320.97  4943.9  319.09  4985.2  320.44  4998.1  319.66
  5023.6  315.03  5023.9  314.53  5027.4  314.53  5027.6  315.03  5035.6  318.29
  5055.7  321.00  5072.5  324.72  5115.8  326.21  5205.7  331.19  5236.4  333.01
  5256.1  335.48  5266.1  335.35  5277.9  336.34  5306.2  339.67  5398.7  346.77
#Mann=5,-1,0
  4535.1    0.07       0  5023.6    0.05       0  5027.6    0.07       0
  5205.7    0.12       0  5277.9    0.07       0
Bank Sta=5023.6,5027.6
Exp/Cntr=0.3,0.1

Type RM Length L Ch R = 1,2804,473,473,473
BEGIN DESCRIPTION:
Stream0305 5.0
END DESCRIPTION:
XS GIS Cut Line= 3
      2484900.09     13637001.26      2484925.00     13636475.00
      2484834.99     13635964.01
#Sta/Elev= 30
  4473.2  332.63  4489.5  331.38  4599.6  326.94  4625.7  326.62  4683.8  325.08
  4719.7  323.08  4739.8  320.90  4759.8  321.59  4769.8  320.71  4799.8  321.14
  4829.9  319.49  4849.9  319.62  4940.0  317.40  4950.0  316.65  4985.0  311.46
  4995.5  310.27  4995.8  309.77  4999.5  310.27  5020.4  311.13  5027.2  313.52
  5040.7  315.70  5162.5  319.64  5313.4  327.81  5426.5  338.34  5432.0  339.80
  5437.1  339.68  5457.0  342.04  5486.2  343.89  5497.6  345.42  5518.9  345.98
#Mann=5,-1,0
  4473.2    0.07       0  4625.7   0.035       0  4985.0    0.07       0
  4995.5    0.05       0  4999.5    0.07       0
Bank Sta=4995.5,4999.5
Exp/Cntr=0.3,0.1

Type RM Length L Ch R = 1,2331,477,477,477
BEGIN DESCRIPTION:
Stream0305 4.0
END DESCRIPTION:
XS GIS Cut Line= 3
      2485164.86     13636975.23      2485325.00     13636575.00
      2485590.07     13636111.75
#Sta/Elev= 30
  4564.8  327.39  4658.0  322.31  4682.2  322.37  4694.3  320.97  4705.1  320.99
  4711.8  319.85  4780.5  316.83  4956.8  312.13  4974.3  310.34  4981.1  306.66
  4991.2  303.93  4991.4  303.43  4995.2  303.93  4998.8  303.93  5018.9  308.20
  5031.1  308.19  5053.5  310.45  5062.8  310.66  5068.6  310.02  5084.4  311.65
  5090.1  311.38  5106.0  313.35  5224.0  318.69  5318.5  324.38  5341.5  326.06
  5353.5  327.74  5363.6  328.04  5406.8  332.49  5444.2  334.08  5529.6  342.55
#Mann=3,-1,0
  4564.8    0.07       0  4991.2    0.05       0  4995.2    0.07       0
Bank Sta=4991.2,4995.2
Exp/Cntr=0.3,0.1

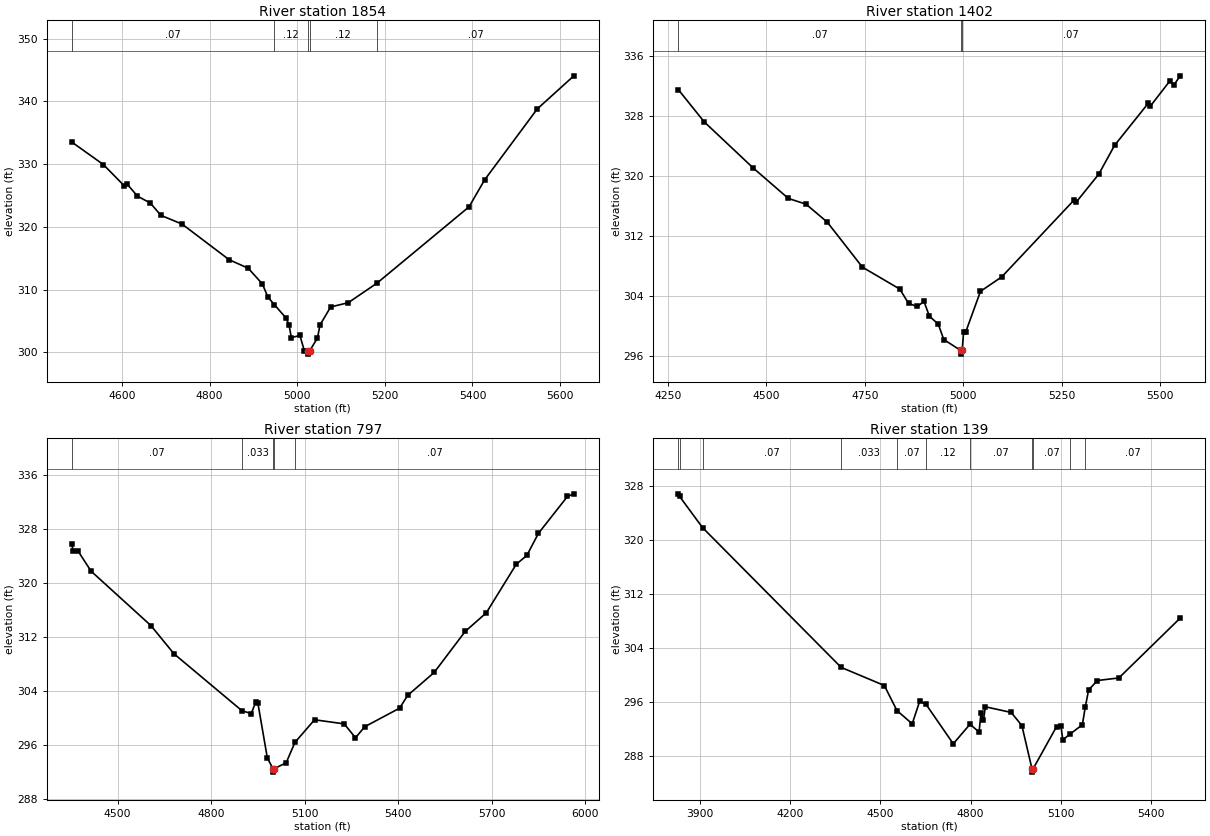
Type RM Length L Ch R = 1,1854,452,452,452
BEGIN DESCRIPTION:
Stream0305 3.0
END DESCRIPTION:
XS GIS Cut Line= 3
      2485533.78     13637248.67      2485725.00     13636775.00
      2485781.17     13636141.90
#Sta/Elev= 30
  4485.1  333.53  4557.2  329.94  4605.4  326.52  4610.8  326.88  4635.0  324.91
  4664.5  323.80  4688.6  321.84  4736.9  320.45  4844.3  314.77  4888.1  313.40
  4920.4  310.90  4932.9  308.80  4947.9  307.58  4974.3  305.47  4981.1  304.39
  4986.5  302.34  5006.0  302.69  5016.0  300.27  5024.0  300.21  5024.3  299.71
  5028.0  300.21  5046.1  302.27  5051.8  304.34  5076.2  307.23  5116.4  307.91
  5182.4  311.05  5392.2  323.20  5427.6  327.48  5548.1  338.82  5631.5  344.09
#Mann=5,-1,0
  4485.1    0.07       0  4947.9    0.12       0  5024.0    0.05       0
  5028.0    0.12       0  5182.4    0.07       0
Bank Sta=5024,5028
Exp/Cntr=0.3,0.1

Type RM Length L Ch R = 1,1402,605,605,605
BEGIN DESCRIPTION:
Stream0305 2.0
END DESCRIPTION:
XS GIS Cut Line= 3
      2485798.54     13637274.71      2486125.00     13636625.00
      2486154.34     13636078.41
#Sta/Elev= 30
  4276.2  331.56  4341.9  327.25  4466.1  321.09  4555.7  317.00  4600.4  316.24
  4654.4  313.84  4743.8  307.81  4838.7  304.88  4861.0  302.96  4883.3  302.56
  4900.0  303.24  4913.8  301.25  4936.2  300.21  4950.3  298.14  4993.0  296.69
  4993.2  296.19  4997.0  296.69  5000.5  299.12  5005.8  299.12  5043.4  304.58
  5097.5  306.52  5280.9  316.78  5285.9  316.47  5343.8  320.25  5383.9  324.10
  5469.3  329.72  5474.4  329.32  5524.1  332.70  5534.1  332.16  5550.7  333.39
#Mann=3,-1,0
  4276.2    0.07       0  4993.0    0.05       0  4997.0    0.07       0
Bank Sta=4993,4997
Exp/Cntr=0.3,0.1

Type RM Length L Ch R = 1,797,658,658,658
BEGIN DESCRIPTION:
XS6427
END DESCRIPTION:
XS GIS Cut Line= 5
      2486024.19     13637231.36      2486236.89     13637092.45
      2486549.39     13636988.28      2486618.84     13636497.83
      2486536.37     13635972.66
#Sta/Elev= 30
  4353.3  325.77  4358.0  324.73  4373.1  324.79  4415.3  321.78  4607.3  313.70
  4681.4  309.51  4899.2  301.07  4929.1  300.65  4943.1  302.35  4950.2  302.22
  4980.5  294.08  4998.7  292.46  4998.9  291.96  5002.7  292.46  5041.1  293.36
  5069.1  296.37  5132.0  299.73  5227.2  299.12  5263.3  297.06  5293.1  298.70
  5404.7  301.45  5431.0  303.36  5515.9  306.76  5615.0  312.83  5682.7  315.59
  5779.1  322.81  5813.0  324.12  5850.0  327.39  5943.2  332.87  5963.7  333.26
#Mann=5,-1,0
  4353.3    0.07       0  4899.2   0.033       0  4998.7   0.033       0
  5002.7   0.033       0  5069.1    0.07       0
Bank Sta=4998.7,5002.7
Exp/Cntr=0.3,0.1

Type RM Length L Ch R = 1,139,0,0,0
BEGIN DESCRIPTION:
Stream0305 1.0
END DESCRIPTION:
XS GIS Cut Line= 4
      2486037.26     13637253.02      2486228.21     13637127.17
      2486840.19     13636892.80      2487300.14     13636254.95
#Sta/Elev= 30
  3827.1  326.81  3831.7  326.42  3907.9  321.82  4369.1  301.16  4512.8  298.48
  4554.7  294.78  4605.5  292.82  4630.1  296.12  4651.0  295.73  4742.1  289.87
  4797.7  292.75  4828.0  291.61  4834.2  294.37  4842.7  293.39  4848.9  295.34
  4934.8  294.50  4970.4  292.56  5003.9  286.18  5004.2  285.68  5007.9  286.18
  5085.7  292.40  5100.4  292.47  5106.6  290.45  5129.1  291.25  5171.6  292.68
  5181.3  295.28  5192.4  297.83  5221.9  299.22  5293.1  299.60  5497.5  308.46
#Mann=11,-1,0
  3827.1    0.07       0  3831.7    0.12       0  3907.9    0.07       0
  4369.1   0.033       0  4554.7    0.07       0  4651.0    0.12       0
  4797.7    0.07       0  5003.9    0.05       0  5007.9    0.07       0
  5129.1    0.12       0  5181.3    0.07       0
Bank Sta=5003.9,5007.9
Exp/Cntr=0.3,0.1

Chan Stop Cuts=-1