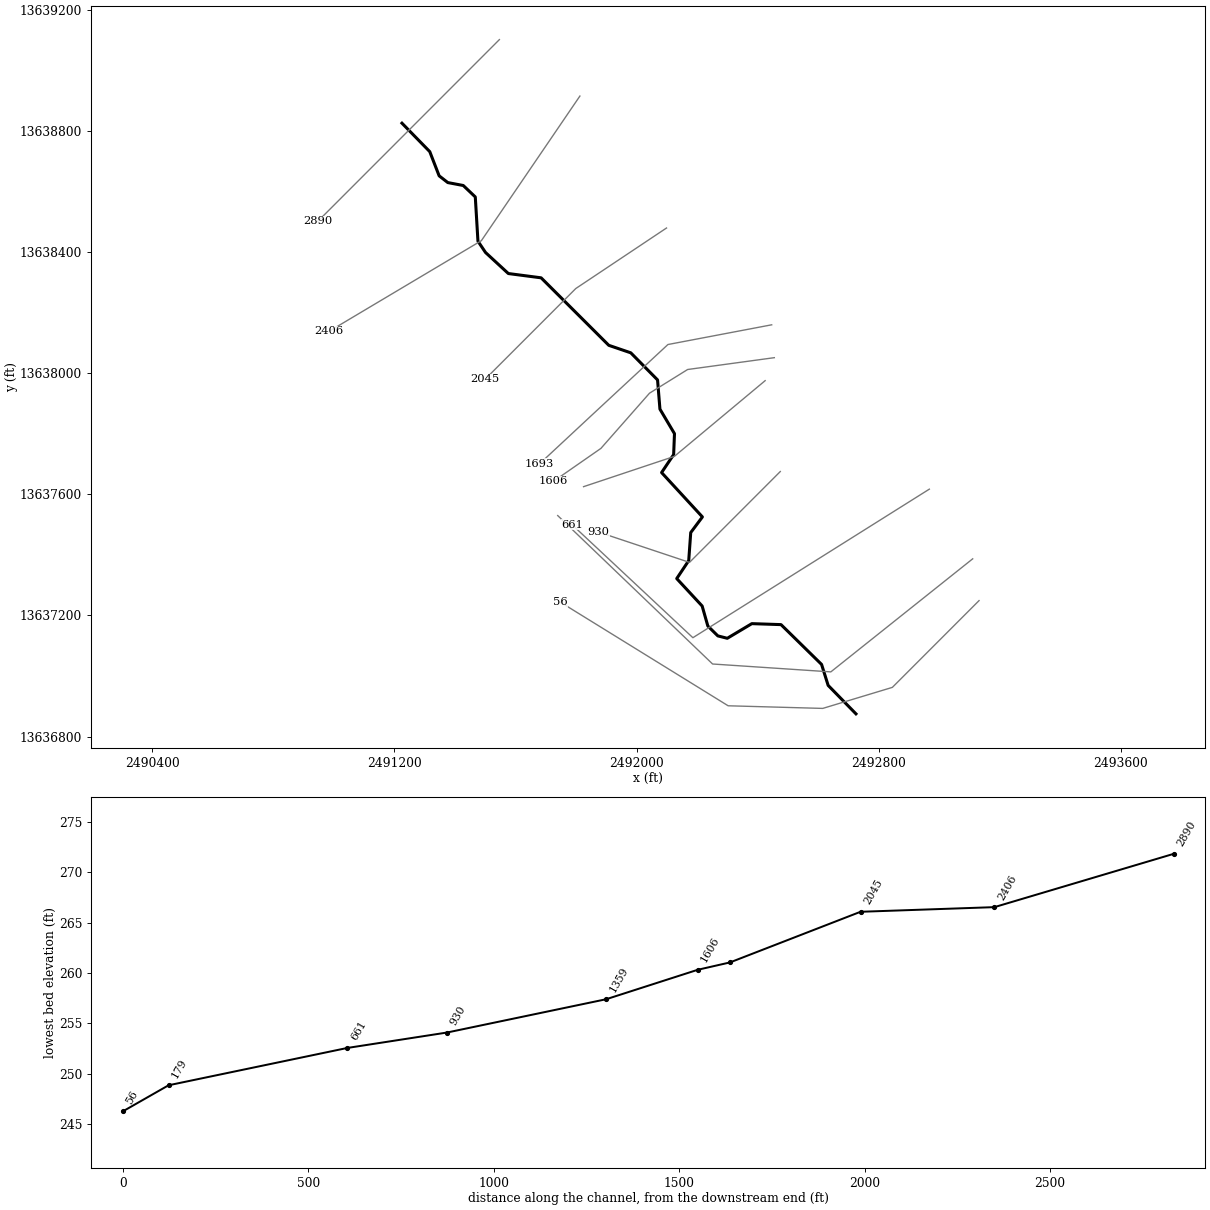
--- Stream0307.prj (project) ---

Proj Title=Stream0307 Base Level Engineering
Current Plan=p01
Default Exp/Contr=0.3,0.1
English Units
Geom File=g01
Flow File=f01
Plan File=p01
BEGIN DESCRIPTION:
Stream0307
END DESCRIPTION:

--- Stream0307.p01 (plan) ---

Plan Title=Multiple Run
Short Identifier=Multiple
Geom File=g01
Flow File=f01
Subcritical Flow
K Sum by GR= 0
Std Step Tol= 0.01
Critical Tol= 0.01
Num of Std Step Trials= 20
Max Error Tol= 0.3
Flow Tol Ratio= 0.001
Split Flow NTrial= 30
Split Flow Tol= 0.02
Split Flow Ratio= 0.02
Log Output Level= 0
Friction Slope Method= 1
Unsteady Friction Slope Method= 2
Unsteady Bridges Friction Slope Method= 1
Parabolic Critical Depth
Global Vel Dist=  1 , 1 , 1
Global Log Level= 0
CheckData=True
Encroach Param= -1, 0, 0, 0
BEGIN DESCRIPTION:
Multiple Run
END DESCRIPTION:

--- Stream0307.f01 (steady flow) ---

Flow Title=Multiple
Number of Profiles=7
Profile Names=10-year,25-year,50-year,1pct_min,100-year,1pct_plu,500-year
River Rch & RM= Stream0307,Reach-1,2890
     568     913    1225     798    1593    3178    2661
Boundary for River Rch & Prof#=Stream0307,Reach-1,1
Up Type=0
Dn Type=3
Dn Slope=0.005
Boundary for River Rch & Prof#=Stream0307,Reach-1,2
Up Type=0
Dn Type=3
Dn Slope=0.005
Boundary for River Rch & Prof#=Stream0307,Reach-1,3
Up Type=0
Dn Type=3
Dn Slope=0.005
Boundary for River Rch & Prof#=Stream0307,Reach-1,4
Up Type=0
Dn Type=3
Dn Slope=0.005
Boundary for River Rch & Prof#=Stream0307,Reach-1,5
Up Type=0
Dn Type=3
Dn Slope=0.005
Boundary for River Rch & Prof#=Stream0307,Reach-1,6
Up Type=0
Dn Type=3
Dn Slope=0.005
Boundary for River Rch & Prof#=Stream0307,Reach-1,7
Up Type=0
Dn Type=3
Dn Slope=0.005

--- Stream0307.g01 (geometry) ---

Geom Title=Existing Conditions

River Reach=Stream0307,Reach-1
Reach XY= 30
      2491225.00     13638825.00      2491316.88     13638731.05
      2491347.86     13638651.16      2491376.46     13638628.90
      2491427.55     13638619.25      2491467.30     13638581.47
      2491476.06     13638435.43      2491501.14     13638398.06
      2491576.48     13638328.61      2491684.79     13638314.48
      2491908.33     13638091.65      2491981.07     13638066.85
      2492069.48     13637977.44      2492077.36     13637880.98
      2492125.39     13637800.00      2492122.63     13637730.89
      2492082.80     13637671.58      2492217.69     13637525.10
      2492179.10     13637473.50      2492172.44     13637380.89
      2492132.81     13637321.59      2492216.80     13637231.03
      2492235.65     13637164.89      2492268.66     13637132.36
      2492299.88     13637124.47      2492380.97     13637172.81
      2492477.43     13637169.60      2492611.37     13637038.21
      2492633.11     13636968.93      2492725.00     13636875.00

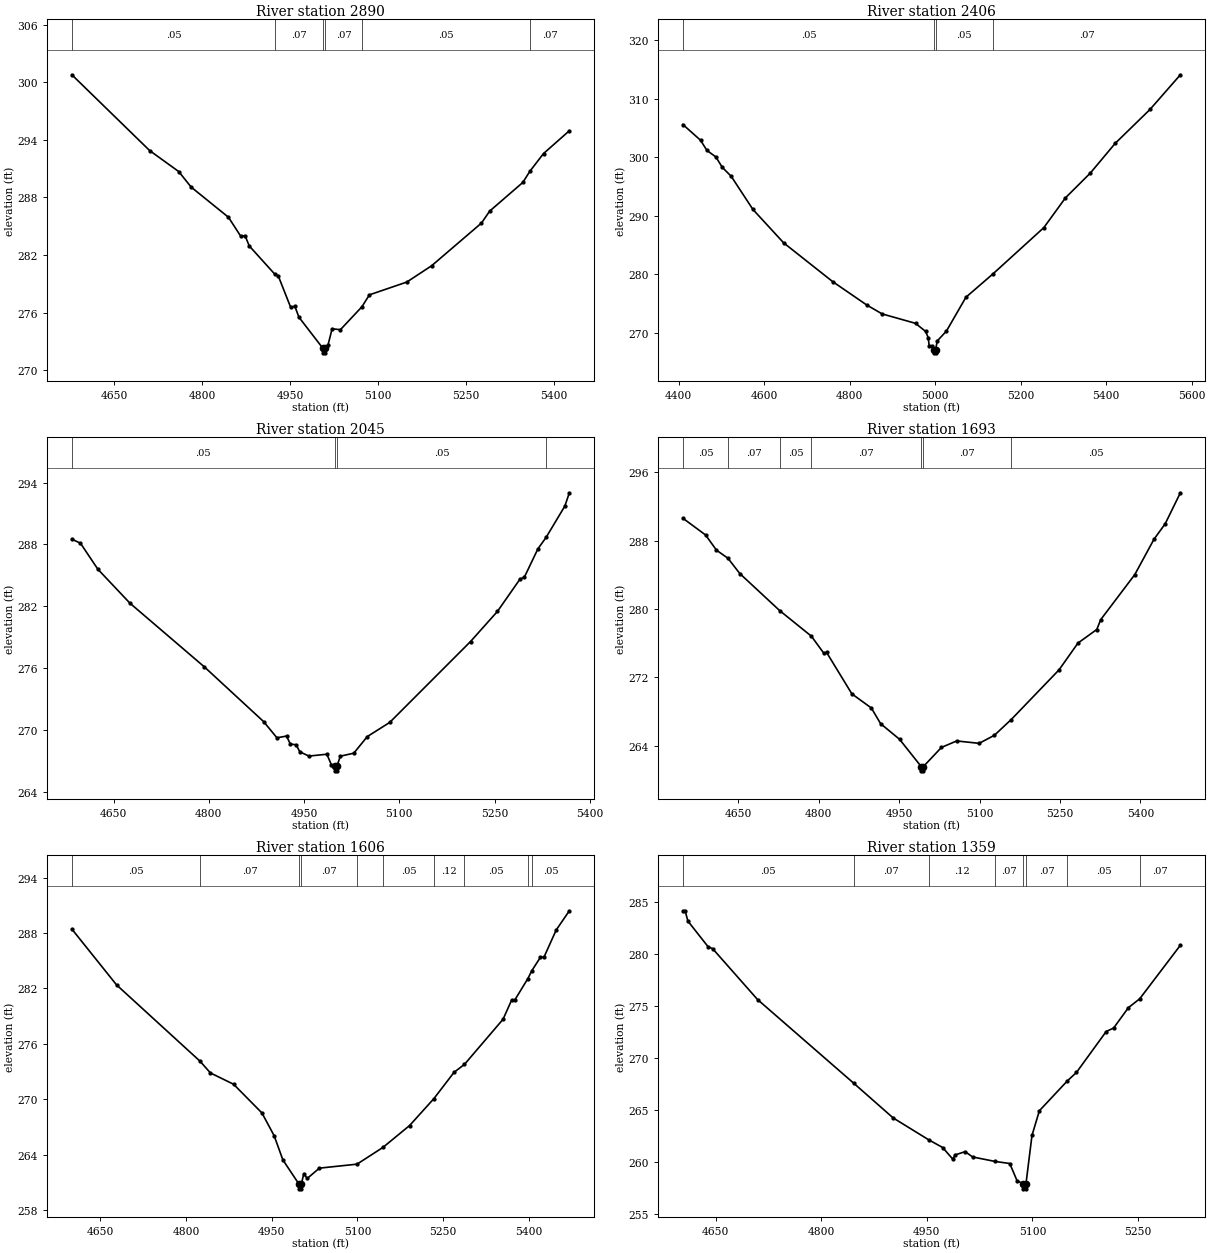
Type RM Length L Ch R = 1,2890,484,484,484
BEGIN DESCRIPTION:
Stream0307 5.0
END DESCRIPTION:
XS GIS Cut Line= 3
      2491546.89     13639100.88      2491246.88     13638800.87
      2490946.91     13638500.90
#Sta/Elev= 30
  4577.4  300.78  4710.2  292.88  4759.7  290.70  4780.9  289.08  4844.5  285.94
  4865.7  283.94  4872.8  284.03  4879.9  282.96  4923.7  280.00  4929.4  279.84
  4950.6  276.56  4957.7  276.67  4964.7  275.53  5005.2  272.32  5005.4  271.82
  5008.9  271.82  5009.2  272.32  5014.2  272.62  5021.3  274.33  5035.4  274.23
  5072.0  276.61  5084.9  277.86  5148.6  279.19  5191.0  280.89  5275.9  285.33
  5290.0  286.58  5346.6  289.57  5358.7  290.74  5381.9  292.58  5425.9  294.95
#Mann=6,-1,0
  4577.4    0.05       0  4923.7    0.07       0  5005.2    0.05       0
  5009.2    0.07       0  5072.0    0.05       0  5358.7    0.07       0
Bank Sta=5005.2,5009.2
Exp/Cntr=0.3,0.1

Type RM Length L Ch R = 1,2406,361,361,361
BEGIN DESCRIPTION:
Stream0307 4.0
END DESCRIPTION:
XS GIS Cut Line= 3
      2491812.92     13638914.57      2491487.41     13638437.15
      2490983.97     13638137.69
#Sta/Elev= 30
  4410.1  305.60  4451.4  302.91  4466.3  301.17  4487.3  300.05  4502.2  298.28
  4523.2  296.73  4574.0  291.06  4645.8  285.35  4760.6  278.71  4840.3  274.71
  4876.2  273.19  4954.2  271.58  4977.9  270.19  4983.9  269.13  4986.2  267.75
  4992.2  267.75  4997.2  267.03  4997.5  266.53  5001.0  266.53  5001.2  267.03
  5005.0  268.56  5026.5  270.25  5072.2  276.05  5135.4  280.04  5254.4  287.96
  5304.9  293.05  5363.1  297.29  5421.2  302.37  5502.7  308.18  5573.7  314.11
#Mann=4,-1,0
  4410.1    0.05       0  4997.2    0.05       0  5001.2    0.05       0
  5135.4    0.07       0
Bank Sta=4997.2,5001.2
Exp/Cntr=0.3,0.1

Type RM Length L Ch R = 1,2045,352,352,352
BEGIN DESCRIPTION:
Stream0307 3.0
END DESCRIPTION:
XS GIS Cut Line= 3
      2492099.10     13638478.97      2491799.13     13638278.99
      2491500.04     13637979.90
#Sta/Elev= 30
  4584.3  288.52  4597.9  288.12  4625.3  285.60  4676.0  282.30  4793.2  276.13
  4886.3  270.84  4907.3  269.27  4922.4  269.44  4928.4  268.66  4937.4  268.60
  4943.4  267.91  4957.6  267.50  4985.9  267.68  4993.0  266.66  4998.1  266.57
  4998.3  266.07  5001.8  266.07  5002.1  266.57  5007.1  267.49  5028.3  267.78
  5049.6  269.39  5084.9  270.76  5212.2  278.60  5254.6  281.52  5290.0  284.64
  5297.0  284.84  5318.3  287.58  5331.1  288.68  5360.7  291.72  5367.8  293.01
#Mann=4,-1,0
  4584.3    0.05       0  4998.1    0.05       0  5002.1    0.05       0
  5331.1    0.07       0
Bank Sta=4998.1,5002.1
Exp/Cntr=0.3,0.1

Type RM Length L Ch R = 1,1693,87,87,87
BEGIN DESCRIPTION:
XS6431
END DESCRIPTION:
XS GIS Cut Line= 4
      2492446.59     13638159.37      2492103.73     13638094.27
      2491865.02     13637872.92      2491679.58     13637700.41
#Sta/Elev= 30
  4546.8  290.63  4589.1  288.67  4609.5  286.89  4630.9  285.94  4653.0  284.15
  4727.4  279.81  4786.4  276.82  4809.7  274.82  4814.8  274.92  4862.0  270.06
  4898.3  268.41  4915.6  266.57  4950.8  264.75  4991.3  261.55  4991.6  261.05
  4995.1  261.05  4995.3  261.55  5029.0  263.79  5057.4  264.55  5099.3  264.27
  5127.7  265.21  5159.2  267.06  5248.4  272.88  5283.6  276.01  5318.7  277.60
  5326.1  278.76  5389.6  284.03  5425.3  288.16  5446.3  289.98  5474.6  293.61
#Mann=7,-1,0
  4546.8    0.05       0  4630.9    0.07       0  4727.4    0.05       0
  4786.4    0.07       0  4991.3    0.05       0  4995.3    0.07       0
  5159.2    0.05       0
Bank Sta=4991.3,4995.3
Exp/Cntr=0.3,0.1

Type RM Length L Ch R = 1,1606,247,247,247
BEGIN DESCRIPTION:
XS6430
END DESCRIPTION:
XS GIS Cut Line= 5
      2492455.27     13638050.86      2492168.84     13638011.81
      2492042.97     13637933.68      2491882.38     13637751.39
      2491726.13     13637642.88
#Sta/Elev= 30
  4600.4  288.43  4678.6  282.39  4824.5  274.14  4842.9  272.86  4883.3  271.64
  4933.0  268.53  4954.3  266.07  4969.6  263.45  4997.9  260.82  4998.2  260.32
  5001.7  260.32  5001.9  260.82  5006.2  261.96  5012.1  261.44  5033.5  262.56
  5099.3  262.99  5144.6  264.80  5191.3  267.17  5233.9  270.09  5269.1  272.93
  5287.3  273.79  5354.8  278.67  5369.7  280.73  5375.8  280.80  5398.3  283.08
  5404.8  283.89  5420.3  285.39  5426.4  285.39  5447.8  288.33  5470.8  290.41
#Mann=10,-1,0
  4600.4    0.05       0  4824.5    0.07       0  4997.9    0.05       0
  5001.9    0.07       0  5099.3    0.12       0  5144.6    0.05       0
  5233.9    0.12       0  5287.3    0.05       0  5398.3    0.07       0
  5404.8    0.05       0
Bank Sta=4997.9,5001.9
Exp/Cntr=0.3,0.1

Type RM Length L Ch R = 1,1359,429,429,429
BEGIN DESCRIPTION:
Stream0307 2.0
END DESCRIPTION:
XS GIS Cut Line= 3
      2492424.98     13637974.99      2492125.00     13637725.00
      2491825.02     13637625.01
#Sta/Elev= 30
  4603.5  284.18  4606.7  284.18  4610.6  283.19  4639.3  280.72  4645.8  280.53
  4709.6  275.63  4846.4  267.56  4902.2  264.23  4952.5  262.13  4972.5  261.38
  4986.8  260.27  4990.7  260.68  5004.5  260.98  5015.1  260.47  5046.9  260.04
  5067.8  259.84  5078.3  258.17  5086.9  257.90  5087.1  257.40  5090.6  257.40
  5090.9  257.90  5099.4  262.54  5109.9  264.92  5149.7  267.80  5162.6  268.61
  5204.8  272.55  5215.4  272.89  5236.4  274.85  5252.4  275.70  5310.2  280.86
#Mann=8,-1,0
  4603.5    0.05       0  4846.4    0.07       0  4952.5    0.12       0
  5046.9    0.07       0  5086.9    0.05       0  5090.9    0.07       0
  5149.7    0.05       0  5252.4    0.07       0
Bank Sta=5086.9,5090.9
Exp/Cntr=0.3,0.1

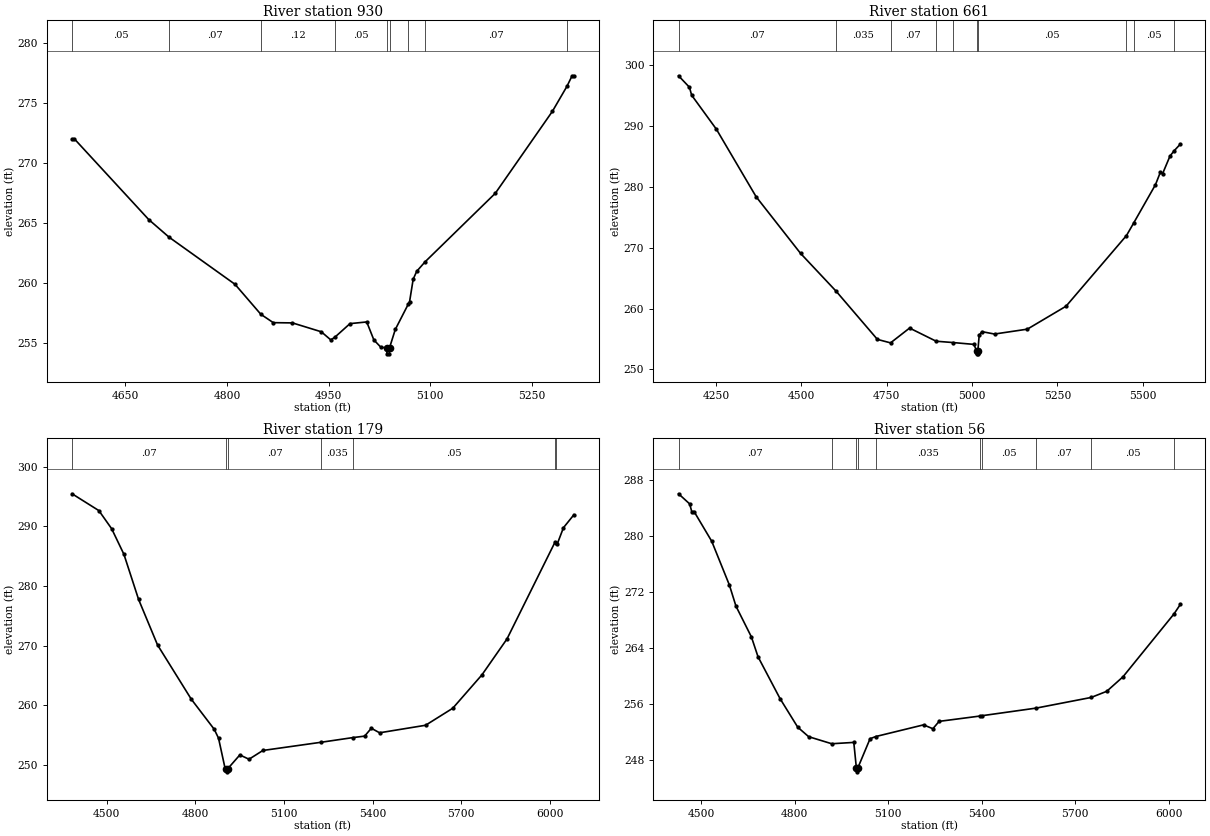
Type RM Length L Ch R = 1,930,269,269,269
BEGIN DESCRIPTION:
Stream0307 1.0
END DESCRIPTION:
XS GIS Cut Line= 3
      2492474.97     13637674.97      2492175.00     13637375.00
      2491875.04     13637474.99
#Sta/Elev= 30
  4571.4  272.02  4574.9  272.02  4684.5  265.30  4714.5  263.83  4811.8  259.90
  4849.9  257.40  4868.3  256.70  4896.6  256.68  4939.1  255.94  4953.2  255.26
  4959.6  255.51  4981.5  256.62  5006.2  256.76  5016.7  255.26  5027.2  254.64
  5035.8  254.60  5036.0  254.10  5039.5  254.10  5039.8  254.60  5048.3  256.13
  5067.8  258.28  5069.4  258.45  5074.7  260.32  5079.9  260.98  5092.2  261.77
  5195.9  267.49  5280.2  274.33  5301.6  276.41  5309.2  277.29  5311.8  277.29
#Mann=9,-1,0
  4571.4    0.05       0  4714.5    0.07       0  4849.9    0.12       0
  4959.6    0.05       0  5035.8    0.05       0  5039.8    0.05       0
  5067.8    0.12       0  5092.2    0.07       0  5301.6    0.05       0
Bank Sta=5035.8,5039.8
Exp/Cntr=0.3,0.1

Type RM Length L Ch R = 1,661,482,482,482
BEGIN DESCRIPTION:
XS6429
END DESCRIPTION:
XS GIS Cut Line= 3
      2492967.42     13637616.82      2492186.20     13637126.39
      2491786.90     13637499.65
#Sta/Elev= 30
  4140.7  298.21  4172.7  296.32  4179.0  295.03  4251.6  289.43  4367.9  278.35
  4497.9  269.06  4602.5  262.82  4722.9  254.94  4761.4  254.37  4817.1  256.80
  4894.9  254.64  4945.0  254.42  5005.6  254.12  5013.0  253.07  5013.3  252.57
  5016.8  252.57  5017.0  253.07  5020.9  255.63  5029.1  256.21  5065.7  255.82
  5161.8  256.62  5275.2  260.39  5452.1  271.99  5473.3  274.06  5537.0  280.34
  5551.2  282.37  5558.0  282.17  5579.5  285.04  5592.1  285.93  5609.7  286.99
#Mann=10,-1,0
  4140.7    0.07       0  4602.5   0.035       0  4761.4    0.07       0
  4894.9   0.035       0  4945.0    0.05       0  5013.0    0.05       0
  5017.0    0.05       0  5452.1    0.07       0  5473.3    0.05       0
  5592.1    0.07       0
Bank Sta=5013,5017
Exp/Cntr=0.3,0.1

Type RM Length L Ch R = 1,179,123,123,123
BEGIN DESCRIPTION:
XS6428
END DESCRIPTION:
XS GIS Cut Line= 4
      2493110.68     13637386.81      2492641.93     13637013.54
      2492251.30     13637039.58      2491739.60     13637529.61
#Sta/Elev= 30
  4382.2  295.44  4473.0  292.62  4516.2  289.59  4557.8  285.30  4607.5  277.74
  4671.6  270.12  4785.7  261.05  4863.7  255.99  4878.2  254.50  4900.6  249.39
  4905.0  249.37  4905.3  248.87  4909.0  249.37  4950.3  251.70  4981.4  250.98
  5028.4  252.45  5226.5  253.83  5333.6  254.61  5372.9  254.85  5395.5  256.17
  5423.5  255.41  5579.2  256.67  5671.3  259.52  5770.1  265.11  5855.0  271.13
  6017.6  287.34  6020.1  287.26  6024.8  286.99  6046.2  289.76  6081.4  291.92
#Mann=7,-1,0
  4382.2    0.07       0  4905.0    0.05       0  4909.0    0.07       0
  5226.5   0.035       0  5333.6    0.05       0  6017.6    0.12       0
  6020.1    0.05       0
Bank Sta=4905,4909
Exp/Cntr=0.3,0.1

Type RM Length L Ch R = 1,56,0,0,0
BEGIN DESCRIPTION:
E20883
END DESCRIPTION:
XS GIS Cut Line= 5
      2493131.65     13637248.84      2492845.23     13636962.41
      2492615.19     13636892.97      2492302.69     13636901.65
      2491748.60     13637243.63
#Sta/Elev= 30
  4428.1  286.07  4463.8  284.62  4470.9  283.46  4477.9  283.53  4534.5  279.28
  4591.1  273.02  4612.3  269.99  4661.8  265.59  4683.0  262.75  4753.7  256.76
  4810.3  252.68  4845.3  251.32  4919.3  250.31  4990.1  250.50  4998.5  246.79
  4998.8  246.29  5002.5  246.79  5042.3  251.03  5060.5  251.34  5213.7  253.01
  5243.7  252.46  5263.7  253.51  5396.0  254.28  5402.8  254.33  5575.1  255.41
  5751.1  256.93  5801.2  257.81  5853.2  259.88  6017.2  268.90  6037.2  270.24
#Mann=10,-1,0
  4428.1    0.07       0  4919.3     0.1       0  4998.5    0.05       0
  5002.5     0.1       0  5060.5   0.035       0  5396.0    0.07       0
  5402.8    0.05       0  5575.1    0.07       0  5751.1    0.05       0
  6017.2    0.12       0
Bank Sta=4998.5,5002.5
Exp/Cntr=0.3,0.1

Chan Stop Cuts=-1