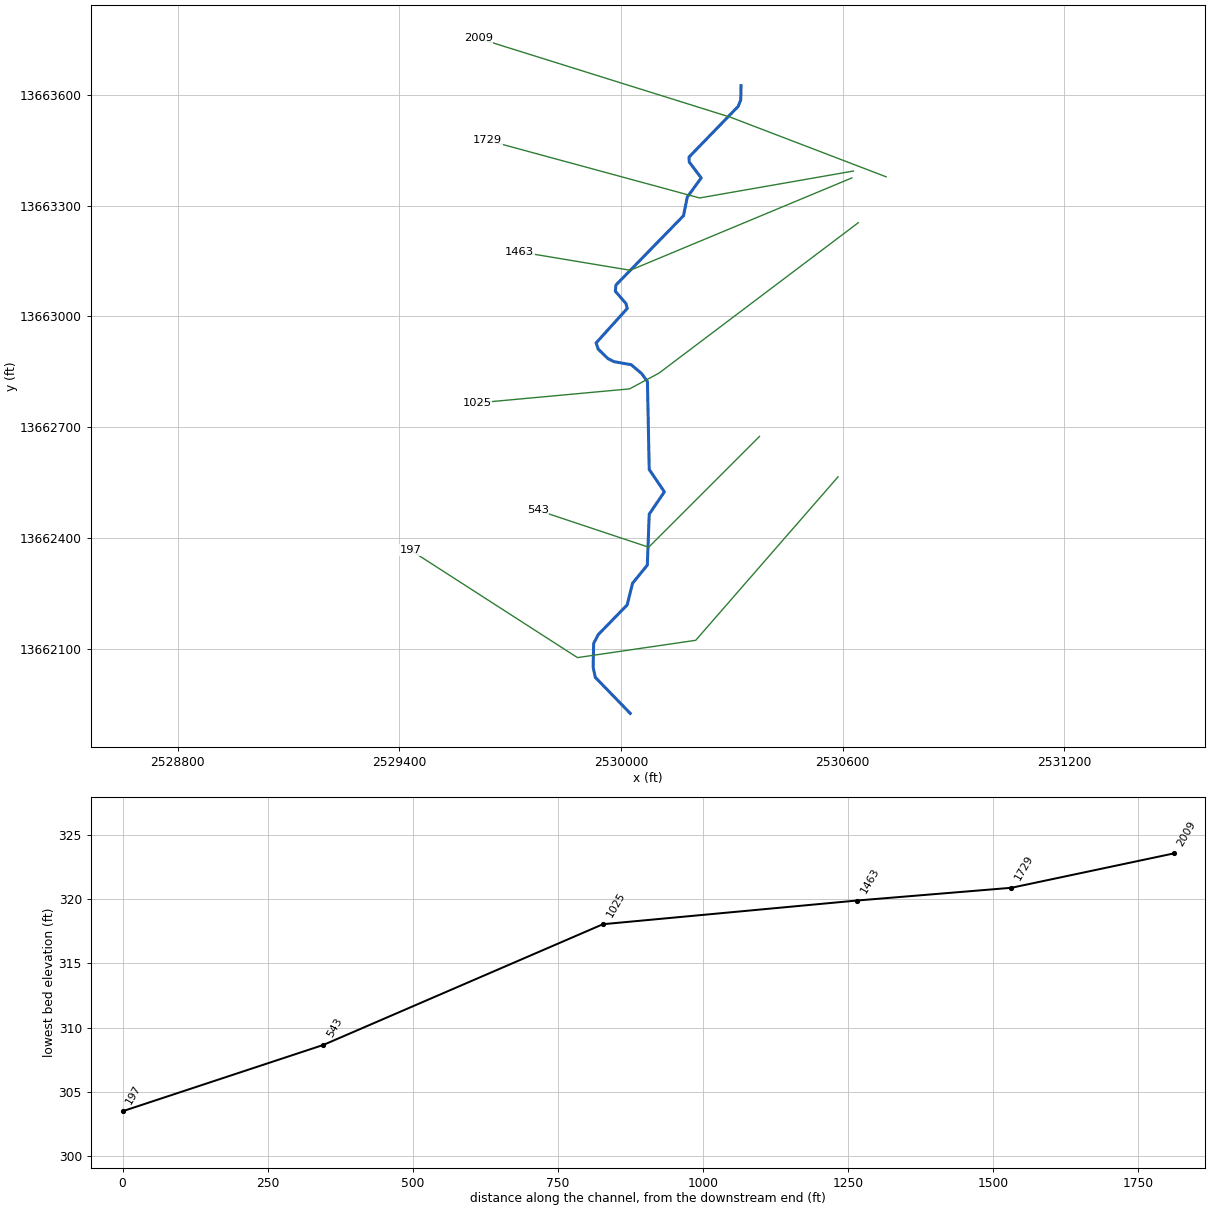
--- Stream0312.prj (project) ---

Proj Title=Stream0312 Base Level Engineering
Current Plan=p01
Default Exp/Contr=0.3,0.1
English Units
Geom File=g01
Flow File=f01
Plan File=p01
BEGIN DESCRIPTION:
Stream0312
END DESCRIPTION:

--- Stream0312.p01 (plan) ---

Plan Title=Multiple Run
Short Identifier=Multiple
Geom File=g01
Flow File=f01
Subcritical Flow
K Sum by GR= 0
Std Step Tol= 0.01
Critical Tol= 0.01
Num of Std Step Trials= 20
Max Error Tol= 0.3
Flow Tol Ratio= 0.001
Split Flow NTrial= 30
Split Flow Tol= 0.02
Split Flow Ratio= 0.02
Log Output Level= 0
Friction Slope Method= 1
Unsteady Friction Slope Method= 2
Unsteady Bridges Friction Slope Method= 1
Parabolic Critical Depth
Global Vel Dist=  1 , 1 , 1
Global Log Level= 0
CheckData=True
Encroach Param= -1, 0, 0, 0
BEGIN DESCRIPTION:
Multiple Run
END DESCRIPTION:

--- Stream0312.f01 (steady flow) ---

Flow Title=Multiple
Number of Profiles=7
Profile Names=10-year,25-year,50-year,1pct_min,100-year,1pct_plu,500-year
River Rch & RM= Stream0312,Reach-1,2009
     729    1175    1579    1029    2052    4095    3428
Boundary for River Rch & Prof#=Stream0312,Reach-1,1
Up Type=0
Dn Type=3
Dn Slope=0.005
Boundary for River Rch & Prof#=Stream0312,Reach-1,2
Up Type=0
Dn Type=3
Dn Slope=0.005
Boundary for River Rch & Prof#=Stream0312,Reach-1,3
Up Type=0
Dn Type=3
Dn Slope=0.005
Boundary for River Rch & Prof#=Stream0312,Reach-1,4
Up Type=0
Dn Type=3
Dn Slope=0.005
Boundary for River Rch & Prof#=Stream0312,Reach-1,5
Up Type=0
Dn Type=3
Dn Slope=0.005
Boundary for River Rch & Prof#=Stream0312,Reach-1,6
Up Type=0
Dn Type=3
Dn Slope=0.005
Boundary for River Rch & Prof#=Stream0312,Reach-1,7
Up Type=0
Dn Type=3
Dn Slope=0.005

--- Stream0312.g01 (geometry) ---

Geom Title=Existing Conditions

River Reach=Stream0312,Reach-1
Reach XY= 30
      2530325.00     13663625.00      2530324.41     13663586.84
      2530317.24     13663568.79      2530184.30     13663431.67
      2530184.60     13663418.34      2530217.22     13663375.09
      2530179.44     13663323.35      2530169.19     13663272.71
      2529986.24     13663085.00      2529984.62     13663068.33
      2530013.28     13663035.00      2530016.97     13663021.67
      2529932.54     13662928.15      2529938.27     13662911.32
      2529964.59     13662885.79      2529980.68     13662877.55
      2530027.52     13662869.26      2530055.55     13662845.55
      2530071.55     13662823.75      2530076.38     13662585.44
      2530117.44     13662525.00      2530076.40     13662464.56
      2530071.24     13662326.56      2530031.14     13662277.17
      2530016.84     13662218.95      2529938.36     13662138.29
      2529925.93     13662114.51      2529924.49     13662049.96
      2529930.33     13662022.55      2530025.00     13661925.00

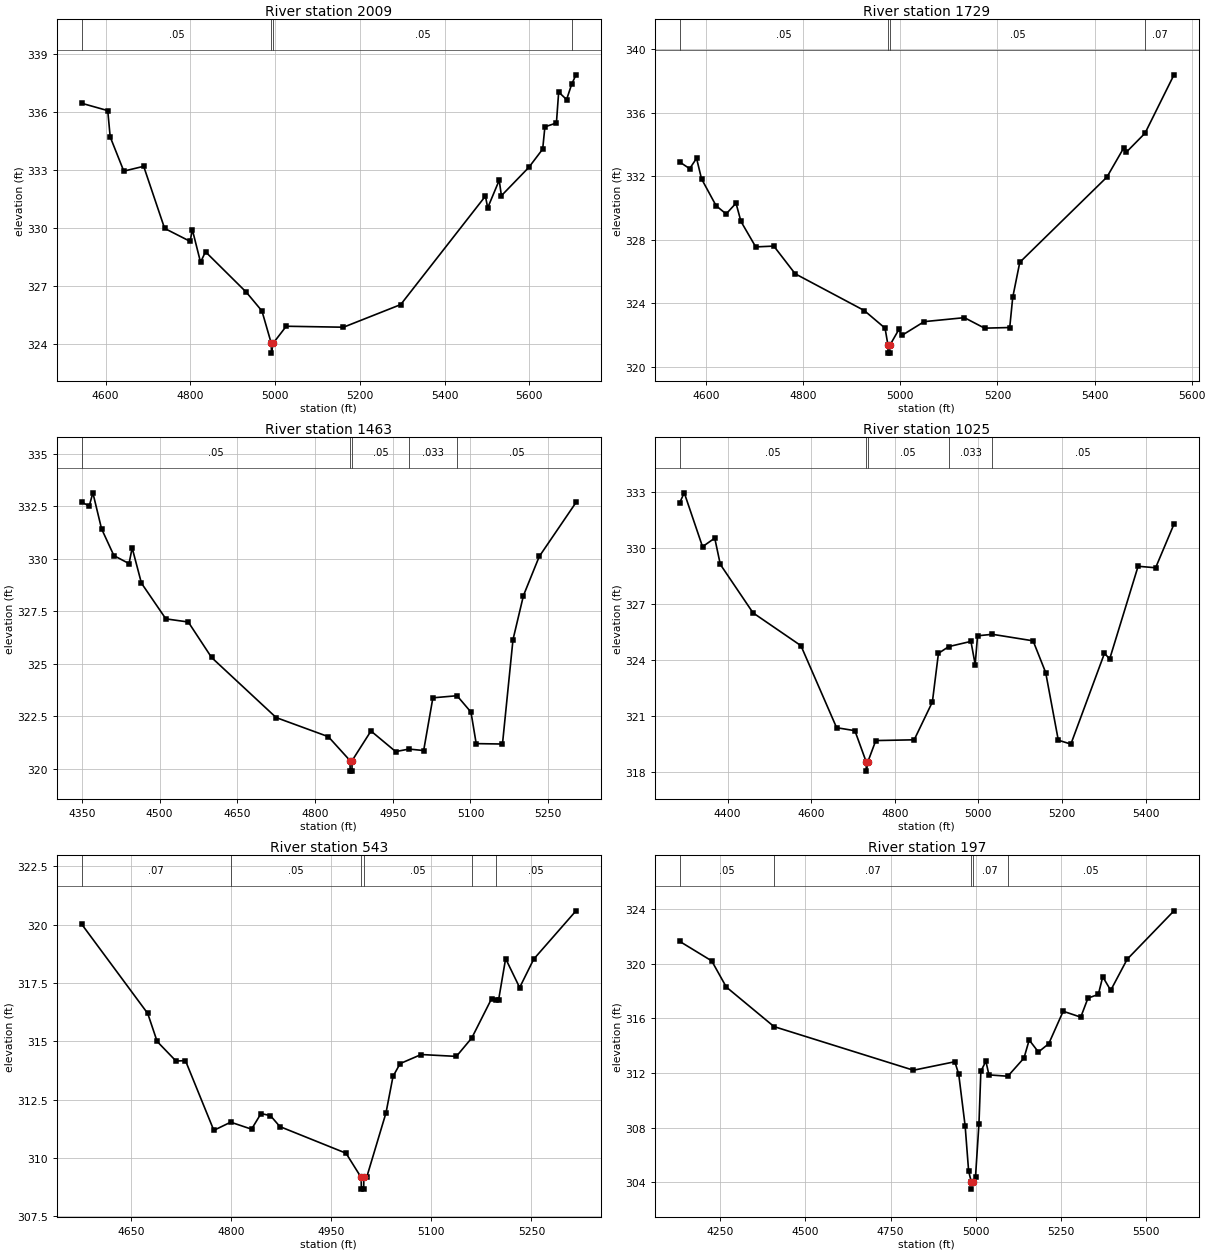
Type RM Length L Ch R = 1,2009,280,280,280
BEGIN DESCRIPTION:
Stream0312 4.0
END DESCRIPTION:
XS GIS Cut Line= 3
      2530717.95     13663378.13      2530296.09     13663539.58
      2529613.82     13663753.12
#Sta/Elev= 30
  4543.4  336.46  4605.0  336.08  4610.8  334.72  4642.9  332.95  4689.8  333.20
  4739.2  329.99  4799.3  329.32  4804.7  329.92  4824.0  328.24  4835.7  328.78
  4932.0  326.69  4968.9  325.72  4991.0  324.04  4991.3  323.54  4995.0  324.04
  5026.2  324.93  5161.3  324.88  5296.3  326.05  5496.3  331.66  5501.6  331.05
  5528.8  332.48  5534.0  331.68  5598.9  333.15  5631.4  334.09  5636.6  335.24
  5663.8  335.44  5669.1  337.04  5687.8  336.65  5699.9  337.45  5710.0  337.93
#Mann=4,-1,0
  4543.4    0.05       0  4991.0    0.05       0  4995.0    0.05       0
  5699.9    0.07       0
Bank Sta=4991,4995
Exp/Cntr=0.3,0.1

Type RM Length L Ch R = 1,1729,266,266,266
BEGIN DESCRIPTION:
XS6436
END DESCRIPTION:
XS GIS Cut Line= 3
      2530629.39     13663393.74      2530212.76     13663320.83
      2529638.60     13663476.71
#Sta/Elev= 30
  4545.7  332.89  4566.4  332.47  4580.6  333.12  4590.8  331.83  4620.8  330.14
  4641.5  329.62  4661.8  330.30  4672.0  329.15  4702.4  327.55  4739.7  327.60
  4783.6  325.86  4925.8  323.55  4968.7  322.44  4974.7  321.37  4974.9  320.87
  4978.4  320.87  4978.7  321.37  4997.4  322.37  5003.1  321.98  5049.2  322.85
  5132.1  323.10  5173.6  322.44  5225.4  322.48  5231.6  324.38  5246.1  326.58
  5425.5  331.94  5460.1  333.77  5465.3  333.50  5504.0  334.70  5563.6  338.37
#Mann=4,-1,0
  4545.7    0.05       0  4974.7    0.05       0  4978.7    0.05       0
  5504.0    0.07       0
Bank Sta=4974.7,4978.7
Exp/Cntr=0.3,0.1

Type RM Length L Ch R = 1,1463,438,438,438
BEGIN DESCRIPTION:
Stream0312 3.0
END DESCRIPTION:
XS GIS Cut Line= 3
      2530624.99     13663375.00      2530025.00     13663125.00
      2529725.03     13663175.00
#Sta/Elev= 30
  4349.6  332.69  4364.2  332.50  4371.3  333.13  4388.0  331.42  4411.9  330.14
  4441.1  329.76  4447.1  330.51  4465.0  328.83  4512.1  327.13  4555.4  326.98
  4600.4  325.29  4725.0  322.43  4825.7  321.52  4867.6  320.38  4867.8  319.88
  4871.3  319.88  4871.6  320.38  4908.0  321.79  4955.7  320.81  4981.4  320.93
  5009.7  320.86  5027.5  323.37  5074.1  323.47  5101.0  322.69  5111.1  321.19
  5161.8  321.17  5182.1  326.14  5202.3  328.24  5232.8  330.10  5303.7  332.67
#Mann=5,-1,0
  4349.6    0.05       0  4867.6   0.033       0  4871.6    0.05       0
  4981.4   0.033       0  5074.1    0.05       0
Bank Sta=4867.6,4871.6
Exp/Cntr=0.3,0.1

Type RM Length L Ch R = 1,1025,482,482,482
BEGIN DESCRIPTION:
Stream0312 2.0
END DESCRIPTION:
XS GIS Cut Line= 4
      2530642.69     13663253.85      2530102.83     13662846.43
      2530023.14     13662803.78      2529609.52     13662765.67
#Sta/Elev= 30
  4285.5  332.43  4296.6  332.97  4340.3  330.08  4369.5  330.54  4382.8  329.13
  4461.1  326.53  4575.6  324.77  4660.9  320.37  4704.6  320.21  4731.6  318.54
  4731.9  318.04  4735.6  318.54  4754.6  319.68  4846.4  319.72  4889.9  321.75
  4904.4  324.36  4929.0  324.72  4982.1  325.00  4992.2  323.76  4997.9  325.30
  5033.4  325.38  5130.7  325.03  5160.8  323.33  5191.0  319.70  5221.1  319.49
  5301.4  324.36  5313.9  324.06  5381.8  329.03  5423.7  328.95  5467.6  331.29
#Mann=5,-1,0
  4285.5    0.05       0  4731.6   0.033       0  4735.6    0.05       0
  4929.0   0.033       0  5033.4    0.05       0
Bank Sta=4731.6,4735.6
Exp/Cntr=0.3,0.1

Type RM Length L Ch R = 1,543,346,346,346
BEGIN DESCRIPTION:
Stream0312 1.0
END DESCRIPTION:
XS GIS Cut Line= 3
      2530374.99     13662674.99      2530075.00     13662375.00
      2529774.98     13662475.01
#Sta/Elev= 30
  4576.2  320.02  4675.2  316.19  4689.3  314.99  4717.6  314.15  4731.7  314.17
  4774.2  311.18  4799.5  311.53  4830.7  311.23  4844.9  311.90  4859.0  311.81
  4873.2  311.34  4972.2  310.20  4994.9  309.16  4995.2  308.66  4998.7  308.66
  4998.9  309.16  5003.1  309.16  5032.1  311.93  5042.6  313.49  5053.2  314.04
  5084.8  314.43  5137.5  314.35  5160.6  315.14  5190.2  316.82  5197.2  316.78
  5200.7  316.76  5211.3  318.54  5232.3  317.30  5253.4  318.52  5316.7  320.59
#Mann=6,-1,0
  4576.2    0.07       0  4799.5    0.05       0  4994.9    0.05       0
  4998.9    0.05       0  5160.6    0.07       0  5197.2    0.05       0
Bank Sta=4994.9,4998.9
Exp/Cntr=0.3,0.1

Type RM Length L Ch R = 1,197,0,0,0
BEGIN DESCRIPTION:
XS6437
END DESCRIPTION:
XS GIS Cut Line= 4
      2530587.74     13662565.60      2530202.34     13662122.92
      2529882.03     13662076.04      2529429.45     13662367.36
#Sta/Elev= 30
  4131.9  321.62  4226.0  320.19  4268.7  318.28  4408.5  315.39  4817.2  312.20
  4938.5  312.82  4949.9  311.91  4968.8  308.11  4978.9  304.84  4987.0  304.01
  4987.3  303.51  4991.0  304.01  4999.1  304.41  5009.2  308.28  5014.8  312.12
  5029.5  312.86  5038.5  311.86  5093.8  311.76  5141.2  313.09  5156.4  314.41
  5183.5  313.53  5213.8  314.14  5256.1  316.51  5307.6  316.08  5328.7  317.47
  5359.1  317.74  5372.0  319.03  5395.4  318.04  5443.6  320.31  5580.8  323.85
#Mann=5,-1,0
  4131.9    0.05       0  4408.5    0.07       0  4987.0    0.05       0
  4991.0    0.07       0  5093.8    0.05       0
Bank Sta=4987,4991
Exp/Cntr=0.3,0.1

Chan Stop Cuts=-1