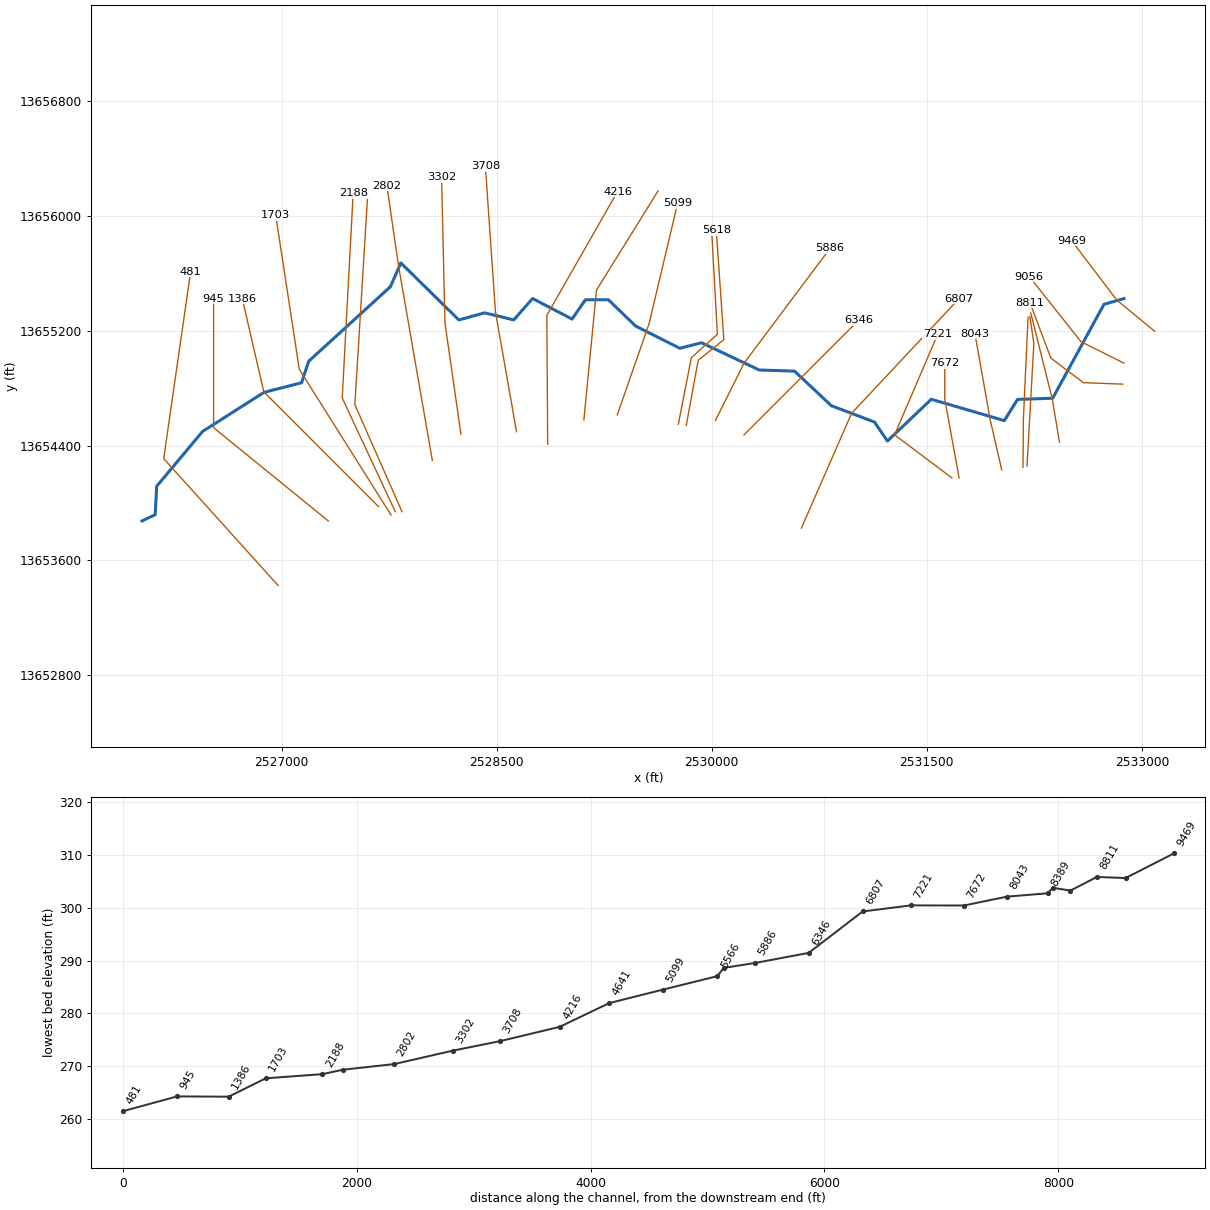
--- Stream0313.prj (project) ---

Proj Title=Stream0313 Base Level Engineering
Current Plan=p01
Default Exp/Contr=0.3,0.1
English Units
Geom File=g01
Flow File=f01
Plan File=p01
BEGIN DESCRIPTION:
Stream0313
END DESCRIPTION:

--- Stream0313.p01 (plan) ---

Plan Title=Multiple Run
Short Identifier=Multiple
Geom File=g01
Flow File=f01
Subcritical Flow
K Sum by GR= 0
Std Step Tol= 0.01
Critical Tol= 0.01
Num of Std Step Trials= 20
Max Error Tol= 0.3
Flow Tol Ratio= 0.001
Split Flow NTrial= 30
Split Flow Tol= 0.02
Split Flow Ratio= 0.02
Log Output Level= 0
Friction Slope Method= 1
Unsteady Friction Slope Method= 2
Unsteady Bridges Friction Slope Method= 1
Parabolic Critical Depth
Global Vel Dist=  1 , 1 , 1
Global Log Level= 0
CheckData=True
Encroach Param= -1, 0, 0, 0
BEGIN DESCRIPTION:
Multiple Run
END DESCRIPTION:

--- Stream0313.f01 (steady flow) ---

Flow Title=Multiple
Number of Profiles=7
Profile Names=10-year,25-year,50-year,1pct_min,100-year,1pct_plu,500-year
River Rch & RM= Stream0313,Reach-1,9469
     700    1119    1496     968    1932    3854    3187
River Rch & RM= Stream0313,Reach-1,7221
     923    1498    2020    1319    2632    5251    4417
River Rch & RM= Stream0313,Reach-1,2802
    1162    1915    2610    1719    3431    6845    5869
Boundary for River Rch & Prof#=Stream0313,Reach-1,1
Up Type=0
Dn Type=3
Dn Slope=0.005
Boundary for River Rch & Prof#=Stream0313,Reach-1,2
Up Type=0
Dn Type=3
Dn Slope=0.005
Boundary for River Rch & Prof#=Stream0313,Reach-1,3
Up Type=0
Dn Type=3
Dn Slope=0.005
Boundary for River Rch & Prof#=Stream0313,Reach-1,4
Up Type=0
Dn Type=3
Dn Slope=0.005
Boundary for River Rch & Prof#=Stream0313,Reach-1,5
Up Type=0
Dn Type=3
Dn Slope=0.005
Boundary for River Rch & Prof#=Stream0313,Reach-1,6
Up Type=0
Dn Type=3
Dn Slope=0.005
Boundary for River Rch & Prof#=Stream0313,Reach-1,7
Up Type=0
Dn Type=3
Dn Slope=0.005

--- Stream0313.g01 (geometry) ---

Geom Title=Existing Conditions

River Reach=Stream0313,Reach-1
Reach XY= 30
      2532875.00     13655425.00      2532735.61     13655385.05
      2532377.70     13654730.36      2532132.97     13654722.06
      2532040.26     13654574.48      2531530.86     13654722.95
      2531224.79     13654431.98      2531135.00     13654564.36
      2530833.48     13654678.51      2530577.28     13654919.18
      2530330.97     13654927.15      2529928.41     13655117.19
      2529776.59     13655078.68      2529468.94     13655233.14
      2529278.41     13655417.18      2529117.99     13655415.97
      2529025.30     13655282.20      2528749.88     13655425.54
      2528619.15     13655276.54      2528414.83     13655325.50
      2528235.48     13655275.94      2527830.84     13655673.52
      2527758.56     13655508.21      2527188.41     13654988.30
      2527138.63     13654838.45      2526876.56     13654771.24
      2526447.86     13654498.83      2526128.07     13654116.70
      2526117.42     13653918.53      2526025.00     13653875.00

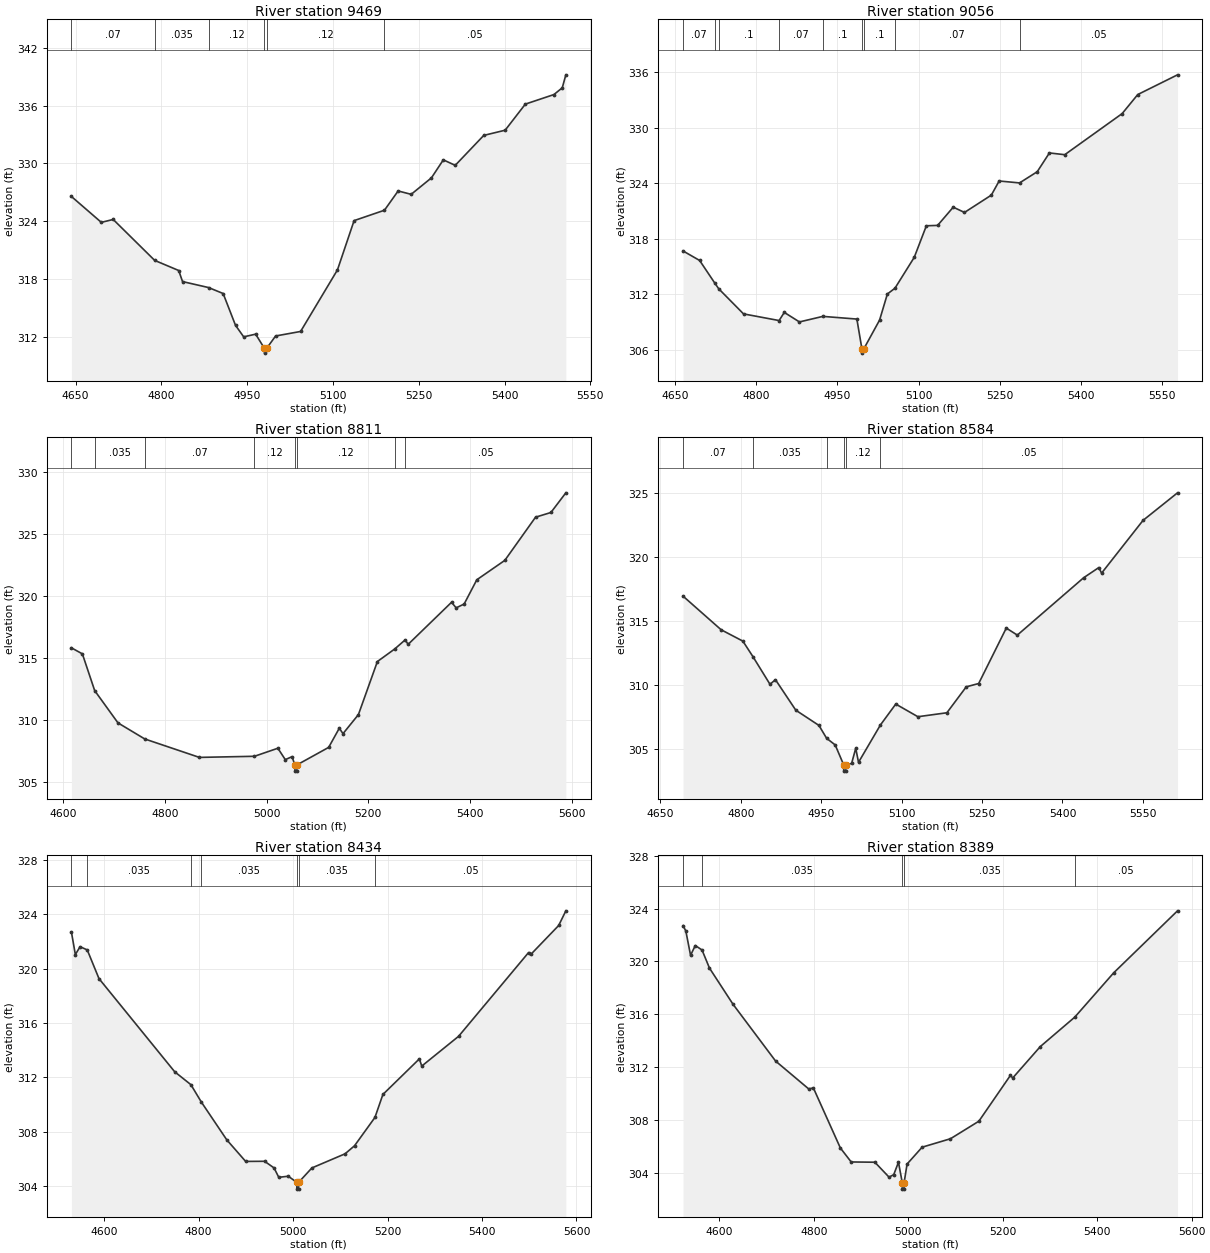
Type RM Length L Ch R = 1,9469,413,413,413
BEGIN DESCRIPTION:
XS6439
END DESCRIPTION:
XS GIS Cut Line= 3
      2533089.94     13655196.43      2532825.61     13655413.77
      2532509.49     13655829.40
#Sta/Elev= 30
  4642.7  326.57  4695.0  323.88  4715.8  324.18  4788.3  319.93  4830.3  318.88
  4837.0  317.73  4882.5  317.11  4908.0  316.49  4929.6  313.19  4943.9  311.99
  4964.8  312.27  4980.1  310.80  4980.3  310.30  4984.1  310.80  4999.7  312.08
  5043.4  312.55  5107.8  318.94  5136.9  324.06  5190.0  325.14  5213.9  327.14
  5236.7  326.79  5272.1  328.50  5292.9  330.37  5313.7  329.80  5363.6  332.91
  5401.0  333.45  5436.3  336.16  5486.2  337.15  5500.8  337.85  5507.1  339.20
#Mann=6,-1,0
  4642.7    0.07       0  4788.3   0.035       0  4882.5    0.12       0
  4980.1    0.05       0  4984.1    0.12       0  5190.0    0.05       0
Bank Sta=4980.1,4984.1
Exp/Cntr=0.3,0.1

Type RM Length L Ch R = 1,9056,245,245,245
BEGIN DESCRIPTION:
Stream0313 20.0
END DESCRIPTION:
XS GIS Cut Line= 3
      2532874.96     13654975.02      2532575.00     13655125.00
      2532214.78     13655578.22
#Sta/Elev= 30
  4664.6  316.67  4695.3  315.64  4723.6  313.17  4730.6  312.58  4776.4  309.87
  4842.2  309.15  4851.8  310.03  4879.8  309.00  4923.1  309.60  4986.0  309.31
  4995.2  306.13  4995.4  305.63  4999.2  306.13  5028.0  309.20  5042.4  312.02
  5056.4  312.64  5092.1  315.98  5114.5  319.39  5135.3  319.43  5164.2  321.40
  5185.0  320.83  5234.6  322.70  5249.1  324.23  5286.8  324.02  5319.5  325.23
  5342.0  327.26  5370.4  327.07  5476.5  331.51  5505.4  333.57  5578.9  335.70
#Mann=9,-1,0
  4664.6    0.07       0  4723.6   0.035       0  4730.6     0.1       0
  4842.2    0.07       0  4923.1     0.1       0  4995.2    0.05       0
  4999.2     0.1       0  5056.4    0.07       0  5286.8    0.05       0
Bank Sta=4995.2,4999.2
Exp/Cntr=0.3,0.1

Type RM Length L Ch R = 1,8811,227,227,227
BEGIN DESCRIPTION:
XS6443
END DESCRIPTION:
XS GIS Cut Line= 4
      2532866.55     13654828.77      2532591.82     13654838.85
      2532365.00     13655010.23      2532219.40     13655396.81
#Sta/Elev= 30
  4616.2  315.81  4637.8  315.32  4662.0  312.35  4707.8  309.74  4760.5  308.44
  4867.9  306.95  4976.2  307.04  5022.2  307.69  5036.8  306.77  5050.1  307.01
  5055.6  306.34  5055.9  305.84  5059.4  305.84  5059.6  306.34  5122.1  307.76
  5143.0  309.31  5150.3  308.87  5180.6  310.41  5217.9  314.70  5252.1  315.72
  5272.5  316.45  5278.4  316.09  5363.7  319.49  5372.8  319.04  5388.5  319.35
  5413.4  321.31  5468.5  322.88  5528.9  326.37  5559.1  326.75  5588.5  328.34
#Mann=8,-1,0
  4616.2    0.07       0  4662.0   0.035       0  4760.5    0.07       0
  4976.2    0.12       0  5055.6    0.05       0  5059.6    0.12       0
  5252.1    0.07       0  5272.5    0.05       0
Bank Sta=5055.6,5059.6
Exp/Cntr=0.3,0.1

Type RM Length L Ch R = 1,8584,150,150,150
BEGIN DESCRIPTION:
Stream0313 19.0
END DESCRIPTION:
XS GIS Cut Line= 3
      2532425.01     13654424.96      2532375.00     13654725.00
      2532225.01     13655324.96
#Sta/Elev= 30
  4692.1  316.95  4763.1  314.32  4803.7  313.43  4822.4  312.22  4854.3  310.05
  4864.5  310.41  4902.5  308.02  4945.6  306.83  4960.0  305.82  4976.0  305.30
  4991.7  303.75  4992.0  303.25  4995.5  303.25  4995.7  303.75  5006.6  303.85
  5014.3  305.04  5019.5  303.94  5060.3  306.86  5089.0  308.50  5130.3  307.51
  5184.4  307.82  5220.5  309.85  5243.7  310.11  5295.2  314.45  5315.8  313.90
  5439.5  318.39  5467.9  319.19  5473.0  318.75  5550.3  322.88  5614.7  325.04
#Mann=6,-1,0
  4692.1    0.07       0  4822.4   0.035       0  4960.0    0.12       0
  4991.7    0.05       0  4995.7    0.12       0  5060.3    0.05       0
Bank Sta=4991.7,4995.7
Exp/Cntr=0.3,0.1

Type RM Length L Ch R = 1,8434,45,45,45
BEGIN DESCRIPTION:
XS6442
END DESCRIPTION:
XS GIS Cut Line= 3
      2532198.66     13654256.66      2532246.54     13655111.04
      2532218.83     13655299.99
#Sta/Elev= 30
  4530.8  322.72  4539.2  321.05  4549.2  321.63  4564.4  321.39  4589.2  319.28
  4749.5  312.42  4783.8  311.47  4805.9  310.19  4859.7  307.41  4899.7  305.82
  4939.8  305.83  4959.8  305.34  4969.8  304.65  4989.9  304.73  5007.9  304.28
  5008.1  303.78  5011.6  303.78  5011.9  304.28  5039.9  305.34  5110.1  306.38
  5130.1  306.97  5173.4  309.06  5190.2  310.75  5267.4  313.37  5272.5  312.84
  5350.4  315.03  5498.6  321.20  5503.6  321.07  5562.3  323.19  5577.5  324.27
#Mann=7,-1,0
  4530.8    0.12       0  4564.4   0.035       0  4783.8    0.07       0
  4805.9   0.035       0  5007.9   0.035       0  5011.9   0.035       0
  5173.4    0.05       0
Bank Sta=5007.9,5011.9
Exp/Cntr=0.3,0.1

Type RM Length L Ch R = 1,8389,346,346,346
BEGIN DESCRIPTION:
XS6441
END DESCRIPTION:
XS GIS Cut Line= 3
      2532170.93     13654249.11      2532173.46     13654584.30
      2532206.22     13655295.05
#Sta/Elev= 30
  4523.4  322.72  4529.3  322.31  4539.3  320.47  4549.3  321.21  4563.6  320.87
  4579.3  319.50  4629.3  316.75  4719.3  312.45  4789.3  310.34  4799.3  310.41
  4856.4  305.86  4879.3  304.80  4929.4  304.78  4959.4  303.65  4969.4  303.84
  4979.4  304.78  4987.4  303.24  4987.7  302.74  4991.2  302.74  4991.4  303.24
  4997.6  304.64  5029.5  305.92  5089.5  306.56  5149.6  307.89  5216.3  311.36
  5221.3  311.17  5279.7  313.55  5352.6  315.78  5435.0  319.14  5570.1  323.84
#Mann=5,-1,0
  4523.4    0.12       0  4563.6   0.035       0  4987.4   0.035       0
  4991.4   0.035       0  5352.6    0.05       0
Bank Sta=4987.4,4991.4
Exp/Cntr=0.3,0.1

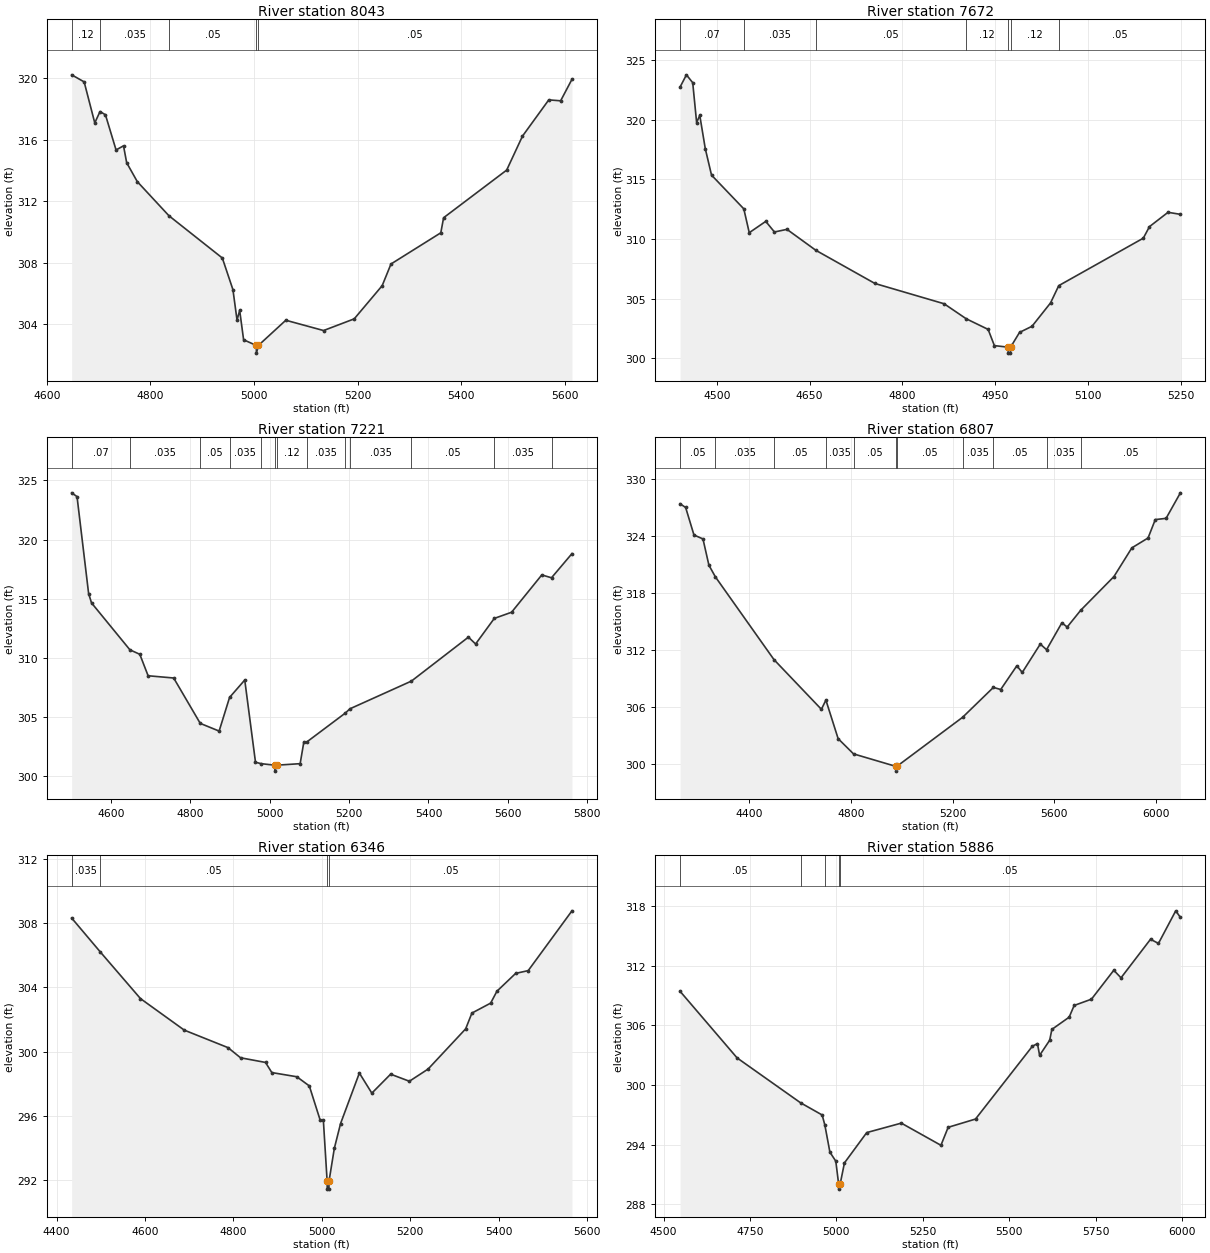
Type RM Length L Ch R = 1,8043,371,371,371
BEGIN DESCRIPTION:
Stream0313 18.0
END DESCRIPTION:
XS GIS Cut Line= 3
      2532022.23     13654231.49      2531941.59     13654581.78
      2531835.73     13655179.12
#Sta/Elev= 30
  4647.8  320.22  4671.9  319.76  4692.4  317.09  4702.5  317.83  4713.0  317.62
  4733.5  315.33  4747.9  315.60  4754.0  314.50  4774.5  313.27  4835.6  311.05
  4938.7  308.30  4959.2  306.24  4967.1  304.26  4972.2  304.89  4979.8  302.98
  5004.3  302.61  5004.6  302.11  5008.3  302.61  5061.3  304.25  5134.2  303.58
  5193.4  304.34  5247.4  306.50  5264.4  307.91  5360.6  309.94  5366.0  310.92
  5487.8  314.02  5518.3  316.23  5569.1  318.59  5592.0  318.53  5613.9  319.93
#Mann=5,-1,0
  4647.8    0.12       0  4702.5   0.035       0  4835.6    0.05       0
  5004.3    0.05       0  5008.3    0.05       0
Bank Sta=5004.3,5008.3
Exp/Cntr=0.3,0.1

Type RM Length L Ch R = 1,7672,451,451,451
BEGIN DESCRIPTION:
Stream0313 17.0
END DESCRIPTION:
XS GIS Cut Line= 3
      2531725.01     13654174.97      2531625.00     13654725.00
      2531625.00     13654974.95
#Sta/Elev= 30
  4440.5  322.74  4450.7  323.76  4460.9  323.10  4467.2  319.76  4472.3  320.36
  4481.2  317.57  4491.3  315.35  4543.5  312.52  4552.3  310.52  4579.0  311.47
  4593.0  310.58  4613.3  310.80  4660.1  309.04  4755.6  306.26  4867.4  304.56
  4903.2  303.30  4938.6  302.41  4948.7  301.05  4970.9  300.92  4971.1  300.42
  4974.6  300.42  4974.9  300.92  4989.4  302.16  5009.5  302.67  5039.5  304.63
  5052.8  306.08  5189.5  310.06  5199.5  311.03  5229.5  312.23  5249.5  312.06
#Mann=7,-1,0
  4440.5    0.07       0  4543.5   0.035       0  4660.1    0.05       0
  4903.2    0.12       0  4970.9    0.05       0  4974.9    0.12       0
  5052.8    0.05       0
Bank Sta=4970.9,4974.9
Exp/Cntr=0.3,0.1

Type RM Length L Ch R = 1,7221,414,414,414
BEGIN DESCRIPTION:
Stream0313 16.0
END DESCRIPTION:
XS GIS Cut Line= 3
      2531674.96     13654175.03      2531275.00     13654475.00
      2531574.99     13655174.97
#Sta/Elev= 30
  4500.4  323.94  4513.9  323.62  4543.1  315.44  4550.4  314.65  4647.2  310.69
  4672.2  310.31  4693.1  308.50  4757.6  308.31  4824.6  304.48  4872.2  303.83
  4898.5  306.67  4936.8  308.14  4963.9  301.20  4978.1  301.08  5012.8  300.95
  5013.1  300.45  5016.9  300.95  5076.5  301.08  5085.6  302.87  5093.6  302.92
  5190.4  305.35  5202.0  305.71  5357.1  308.05  5500.8  311.76  5518.9  311.18
  5566.0  313.34  5609.6  313.86  5685.8  317.01  5710.3  316.77  5761.9  318.81
#Mann=13,-1,0
  4500.4    0.07       0  4647.2   0.035       0  4824.6    0.05       0
  4898.5   0.035       0  4978.1    0.12       0  5012.8    0.05       0
  5016.9    0.12       0  5093.6   0.035       0  5190.4    0.05       0
  5202.0   0.035       0  5357.1    0.05       0  5566.0   0.035       0
  5710.3    0.05       0
Bank Sta=5012.8,5016.9
Exp/Cntr=0.3,0.1

Type RM Length L Ch R = 1,6807,461,461,461
BEGIN DESCRIPTION:
Stream0313 15.0
END DESCRIPTION:
XS GIS Cut Line= 3
      2530625.00     13653825.01      2530975.00     13654625.00
      2531725.01     13655425.01
#Sta/Elev= 30
  4126.8  327.36  4148.6  326.97  4181.4  324.08  4216.8  323.67  4240.2  320.91
  4265.6  319.69  4496.3  311.00  4683.1  305.78  4700.8  306.75  4749.0  302.70
  4809.6  301.10  4976.1  299.79  4976.4  299.29  4980.2  299.79  5239.0  304.94
  5360.3  308.08  5389.1  307.86  5452.6  310.35  5474.0  309.65  5544.9  312.63
  5569.6  312.04  5629.9  314.86  5650.9  314.42  5704.1  316.18  5835.0  319.72
  5905.4  322.73  5969.3  323.77  5997.7  325.70  6040.2  325.83  6096.6  328.51
#Mann=11,-1,0
  4126.8    0.05       0  4265.6   0.035       0  4496.3    0.05       0
  4700.8   0.035       0  4809.6    0.05       0  4976.1    0.05       0
  4980.2    0.05       0  5239.0   0.035       0  5360.3    0.05       0
  5569.6   0.035       0  5704.1    0.05       0
Bank Sta=4976.1,4980.2
Exp/Cntr=0.3,0.1

Type RM Length L Ch R = 1,6346,460,460,460
BEGIN DESCRIPTION:
Stream0313 14.0
END DESCRIPTION:
XS GIS Cut Line= 3
      2530224.98     13654474.98      2530625.00     13654875.00
      2531025.00     13655275.00
#Sta/Elev= 30
  4434.3  308.30  4499.4  306.18  4589.9  303.29  4688.9  301.33  4787.9  300.24
  4816.2  299.61  4872.7  299.32  4886.9  298.69  4943.4  298.43  4971.7  297.86
  4996.5  295.71  5003.5  295.71  5012.0  291.94  5012.3  291.44  5016.0  291.44
  5016.3  291.94  5028.3  293.98  5042.4  295.52  5084.9  298.66  5113.1  297.41
  5155.6  298.59  5198.0  298.15  5240.4  298.91  5325.3  301.41  5339.4  302.39
  5381.8  303.01  5396.0  303.75  5438.4  304.86  5466.7  305.03  5565.7  308.75
#Mann=4,-1,0
  4434.3   0.035       0  4499.4    0.05       0  5012.0    0.05       0
  5016.3    0.05       0
Bank Sta=5012,5016.3
Exp/Cntr=0.3,0.1

Type RM Length L Ch R = 1,5886,268,268,268
BEGIN DESCRIPTION:
Stream0313 13.0
END DESCRIPTION:
XS GIS Cut Line= 3
      2530024.99     13654574.98      2530225.00     13654975.00
      2530824.98     13655774.97
#Sta/Elev= 30
  4548.0  309.43  4712.9  302.73  4896.3  298.22  4958.9  296.99  4966.7  295.98
  4981.3  293.25  4998.4  292.34  5006.6  290.03  5006.9  289.53  5010.9  290.03
  5023.4  292.17  5087.9  295.22  5187.9  296.17  5302.5  293.94  5323.4  295.75
  5402.5  296.58  5567.1  303.91  5581.7  304.17  5587.9  302.99  5617.1  304.51
  5623.4  305.60  5673.4  306.83  5687.9  308.01  5737.9  308.64  5802.5  311.55
  5823.4  310.79  5908.8  314.67  5931.7  314.25  5981.7  317.53  5995.2  316.87
#Mann=5,-1,0
  4548.0    0.05       0  4896.3     0.1       0  4966.7    0.05       0
  5006.6    0.05       0  5010.9    0.05       0
Bank Sta=5006.6,5010.9
Exp/Cntr=0.3,0.1

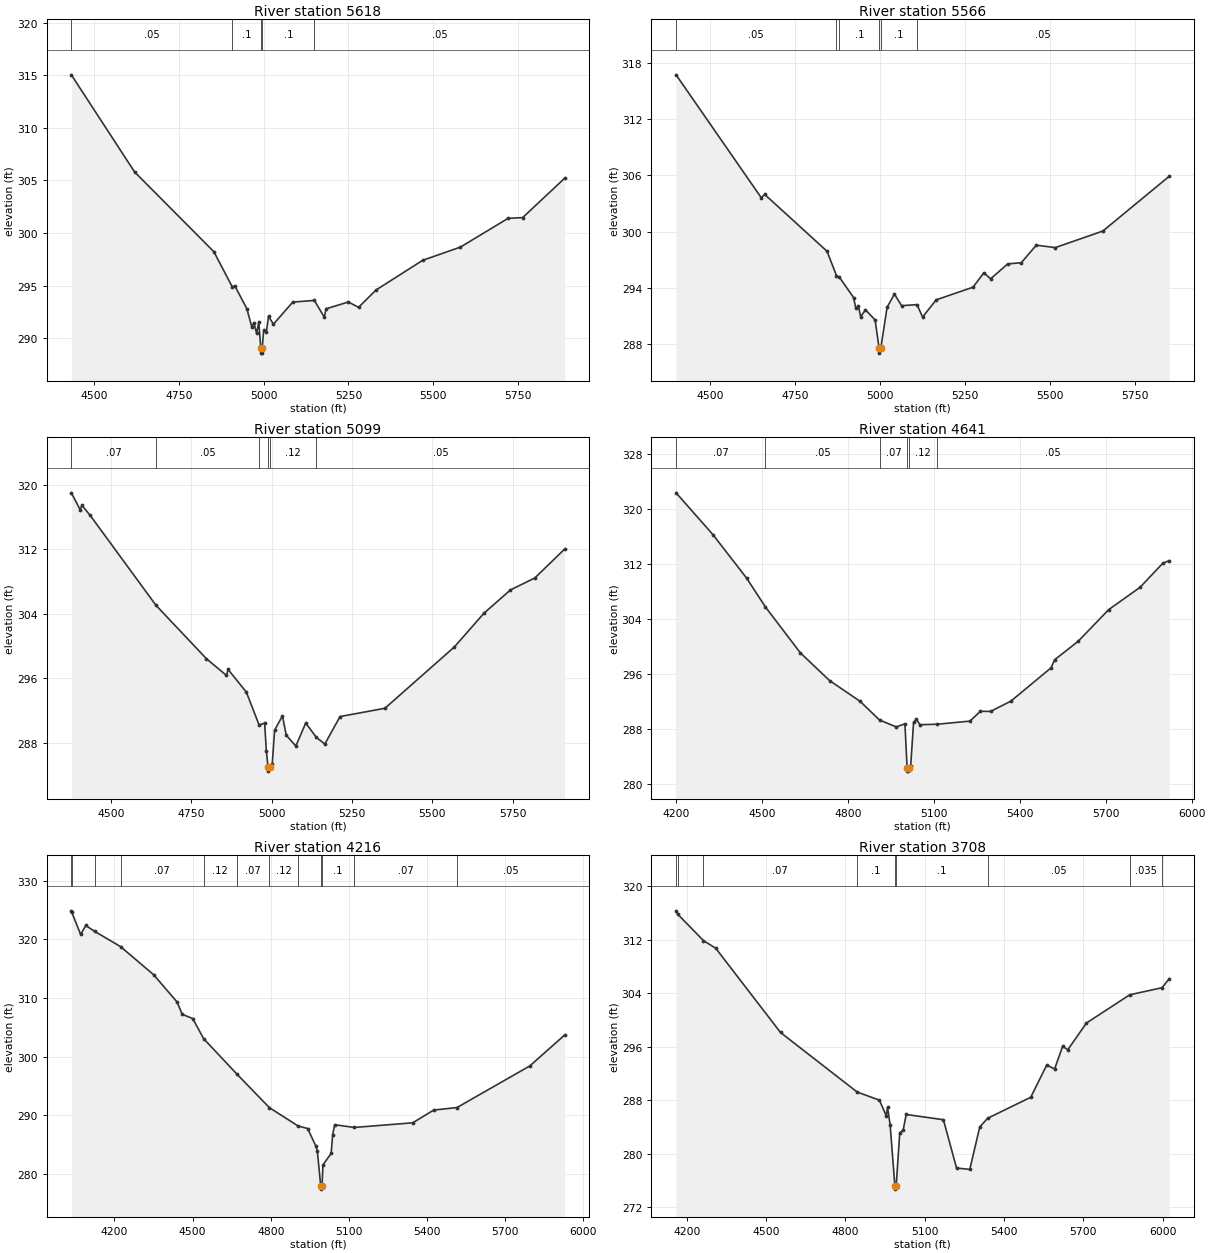
Type RM Length L Ch R = 1,5618,52,52,52
BEGIN DESCRIPTION:
XS6440
END DESCRIPTION:
XS GIS Cut Line= 4
      2529822.04     13654541.43      2529905.22     13654995.11
      2530084.15     13655138.76      2530031.31     13655901.22
#Sta/Elev= 30
  4432.5  315.04  4619.1  305.81  4853.0  298.23  4907.1  294.90  4915.1  294.97
  4950.3  292.81  4964.7  291.11  4971.1  291.46  4979.1  290.47  4985.5  291.54
  4991.4  289.09  4991.6  288.59  4995.4  288.59  4995.7  289.09  4999.9  290.75
  5007.9  290.58  5014.3  292.10  5028.7  291.34  5085.8  293.44  5149.4  293.60
  5178.9  292.00  5183.9  292.80  5249.7  293.45  5279.8  292.94  5331.4  294.59
  5468.9  297.41  5580.5  298.67  5720.9  301.40  5763.9  301.47  5887.5  305.20
#Mann=5,-1,0
  4432.5    0.05       0  4907.1     0.1       0  4991.4    0.05       0
  4995.7     0.1       0  5149.4    0.05       0
Bank Sta=4991.4,4995.7
Exp/Cntr=0.3,0.1

Type RM Length L Ch R = 1,5566,467,467,467
BEGIN DESCRIPTION:
Stream0313 12.0
END DESCRIPTION:
XS GIS Cut Line= 4
      2529766.60     13654549.04      2529857.33     13655012.75
      2530038.79     13655176.57      2529998.46     13655909.99
#Sta/Elev= 30
  4399.5  316.71  4650.1  303.61  4660.3  303.96  4843.7  297.90  4871.5  295.31
  4880.3  295.12  4921.8  292.97  4928.5  291.81  4936.0  292.04  4942.7  290.92
  4956.9  291.66  4985.3  290.57  4997.1  287.54  4997.5  287.04  5001.9  287.54
  5020.5  291.93  5042.1  293.34  5063.1  292.10  5108.6  292.21  5124.9  290.89
  5165.0  292.72  5273.4  294.07  5305.2  295.60  5325.2  294.96  5375.3  296.55
  5415.4  296.68  5459.6  298.55  5515.5  298.29  5655.7  300.06  5851.0  305.90
#Mann=6,-1,0
  4399.5    0.05       0  4871.5   0.035       0  4880.3     0.1       0
  4997.1    0.05       0  5001.9     0.1       0  5108.6    0.05       0
Bank Sta=4997.1,5001.9
Exp/Cntr=0.3,0.1

Type RM Length L Ch R = 1,5099,458,458,458
BEGIN DESCRIPTION:
Stream0313 11.0
END DESCRIPTION:
XS GIS Cut Line= 3
      2529340.68     13654614.56      2529562.46     13655249.65
      2529761.55     13656088.86
#Sta/Elev= 30
  4376.2  319.01  4403.8  316.91  4409.1  317.47  4434.9  316.21  4639.4  305.07
  4796.9  298.42  4859.0  296.36  4864.3  297.09  4921.1  294.28  4960.6  290.21
  4978.0  290.43  4983.2  286.97  4988.6  284.98  4989.0  284.48  4993.5  284.98
  5001.6  285.40  5009.0  289.57  5033.4  291.34  5045.2  288.93  5075.0  287.59
  5105.8  290.45  5138.8  288.67  5165.3  287.84  5212.6  291.25  5352.4  292.28
  5568.3  299.88  5660.8  304.08  5743.0  306.96  5819.1  308.45  5911.4  312.02
#Mann=6,-1,0
  4376.2    0.07       0  4639.4    0.05       0  4960.6    0.12       0
  4988.6    0.05       0  4993.5    0.12       0  5138.8    0.05       0
Bank Sta=4988.6,4993.5
Exp/Cntr=0.3,0.1

Type RM Length L Ch R = 1,4641,425,425,425
BEGIN DESCRIPTION:
Stream0313 10.0
END DESCRIPTION:
XS GIS Cut Line= 3
      2529107.76     13654579.73      2529195.86     13655484.25
      2529625.00     13656175.00
#Sta/Elev= 30
  4199.9  322.34  4328.5  316.27  4446.3  309.95  4511.8  305.77  4633.9  299.10
  4735.7  295.08  4842.6  292.06  4910.2  289.35  4968.8  288.35  4998.9  288.80
  5006.5  282.43  5006.9  281.93  5011.1  281.93  5011.4  282.43  5019.0  282.72
  5029.1  289.01  5039.1  289.47  5051.2  288.67  5111.0  288.74  5225.8  289.19
  5262.4  290.62  5297.9  290.60  5368.7  292.09  5509.2  296.93  5521.6  298.10
  5603.7  300.78  5710.0  305.37  5819.8  308.62  5898.9  312.10  5921.9  312.50
#Mann=6,-1,0
  4199.9    0.07       0  4511.8    0.05       0  4910.2    0.07       0
  5006.5    0.05       0  5011.4    0.12       0  5111.0    0.05       0
Bank Sta=5006.5,5011.4
Exp/Cntr=0.3,0.1

Type RM Length L Ch R = 1,4216,508,508,508
BEGIN DESCRIPTION:
Stream0313 9.0
END DESCRIPTION:
XS GIS Cut Line= 3
      2528855.21     13654409.38      2528849.33     13655308.05
      2529342.30     13656170.75
#Sta/Elev= 30
  4035.0  324.84  4036.2  324.67  4070.6  320.82  4090.6  322.34  4124.1  321.35
  4223.7  318.75  4350.6  313.96  4440.6  309.31  4460.6  307.20  4500.6  306.49
  4542.8  303.05  4670.5  297.01  4795.0  291.30  4905.1  288.18  4941.7  287.75
  4972.9  284.78  4978.7  284.00  4992.0  277.92  4992.4  277.42  4997.0  277.92
  5000.3  281.54  5031.9  283.51  5037.7  286.71  5045.4  288.39  5120.7  287.93
  5344.8  288.72  5425.4  290.89  5514.7  291.32  5794.0  298.41  5927.3  303.66
#Mann=12,-1,0
  4035.0    0.05       0  4036.2    0.07       0  4124.1   0.035       0
  4223.7    0.07       0  4542.8    0.12       0  4670.5    0.07       0
  4795.0    0.12       0  4905.1     0.1       0  4992.0    0.05       0
  4997.0     0.1       0  5120.7    0.07       0  5514.7    0.05       0
Bank Sta=4992,4997
Exp/Cntr=0.3,0.1

Type RM Length L Ch R = 1,3708,406,406,406
BEGIN DESCRIPTION:
Stream0313 8.0
END DESCRIPTION:
XS GIS Cut Line= 3
      2528637.89     13654497.55      2528491.06     13655331.54
      2528420.57     13656347.68
#Sta/Elev= 30
  4159.4  316.31  4165.1  315.82  4263.0  311.86  4309.1  310.73  4554.4  298.13
  4843.9  289.24  4928.5  288.01  4954.3  285.69  4959.3  286.97  4969.1  284.27
  4986.9  275.22  4987.3  274.72  4991.9  275.22  5005.4  283.16  5018.1  283.51
  5029.7  285.88  5170.5  285.09  5220.2  277.87  5270.3  277.67  5308.0  284.02
  5338.2  285.32  5500.9  288.45  5561.0  293.25  5591.1  292.68  5621.2  296.05
  5641.2  295.56  5711.4  299.54  5875.2  303.76  5997.3  304.82  6024.8  306.18
#Mann=9,-1,0
  4159.4    0.07       0  4165.1   0.035       0  4263.0    0.07       0
  4843.9     0.1       0  4986.9    0.05       0  4991.9     0.1       0
  5338.2    0.05       0  5875.2   0.035       0  5997.3    0.05       0
Bank Sta=4986.9,4991.9
Exp/Cntr=0.3,0.1

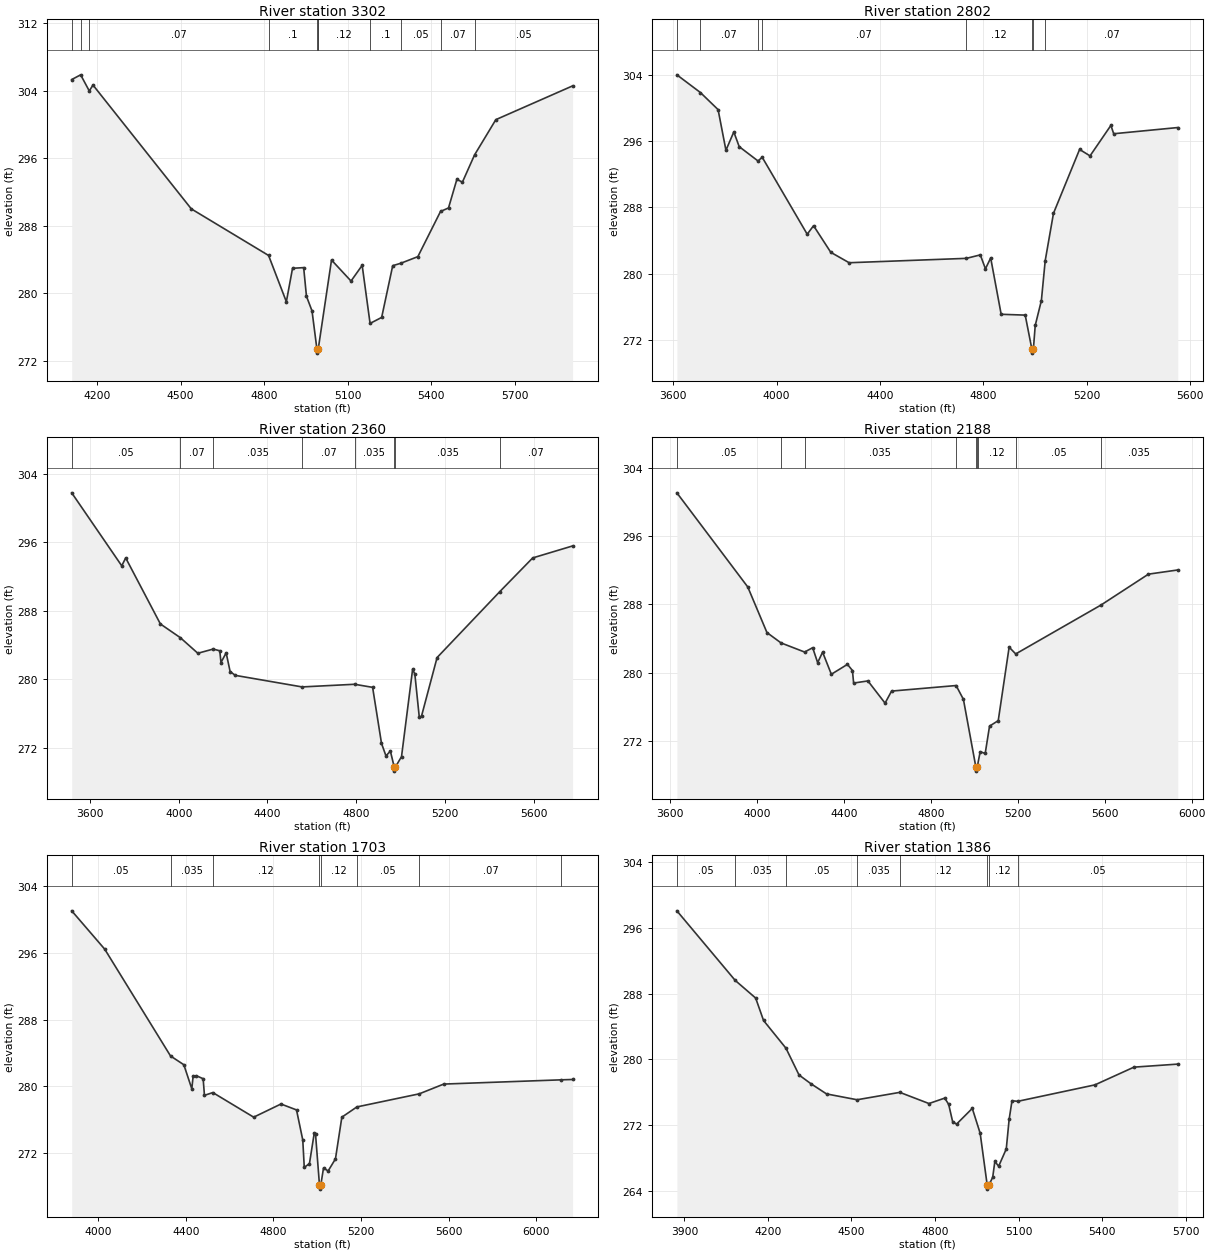
Type RM Length L Ch R = 1,3302,500,500,500
BEGIN DESCRIPTION:
Stream0313 7.0
END DESCRIPTION:
XS GIS Cut Line= 3
      2528250.25     13654479.89      2528138.65     13655255.19
      2528115.18     13656270.63
#Sta/Elev= 30
  4108.9  305.32  4141.0  305.88  4172.0  303.97  4185.3  304.67  4538.4  290.00
  4816.0  284.48  4879.8  279.00  4902.0  282.96  4942.0  283.04  4952.0  279.65
  4972.0  277.91  4989.5  273.41  4989.9  272.91  4994.5  273.41  4994.9  273.52
  5042.0  283.94  5112.1  281.45  5152.1  283.31  5180.5  276.43  5222.1  277.14
  5261.8  283.27  5290.3  283.55  5352.1  284.34  5433.5  289.69  5462.2  290.11
  5492.2  293.49  5512.2  293.17  5555.7  296.39  5632.2  300.57  5907.9  304.57
#Mann=11,-1,0
  4108.9    0.07       0  4141.0   0.035       0  4172.0    0.07       0
  4816.0     0.1       0  4989.5    0.05       0  4994.5     0.1       0
  4994.9    0.12       0  5180.5     0.1       0  5290.3    0.05       0
  5433.5    0.07       0  5555.7    0.05       0
Bank Sta=4989.5,4994.5
Exp/Cntr=0.3,0.1

Type RM Length L Ch R = 1,2802,442,442,442
BEGIN DESCRIPTION:
Stream0313 6.0
END DESCRIPTION:
XS GIS Cut Line= 3
      2528050.56     13654297.78      2527815.62     13655648.70
      2527733.58     13656211.25
#Sta/Elev= 30
  3613.6  304.05  3704.6  301.91  3773.2  299.84  3803.6  294.92  3834.1  297.14
  3854.9  295.36  3928.0  293.62  3943.9  294.08  4118.3  284.76  4142.9  285.79
  4209.6  282.57  4280.7  281.31  4734.8  281.84  4788.7  282.26  4808.5  280.57
  4828.8  281.89  4869.4  275.07  4962.5  274.97  4988.2  270.87  4988.7  270.37
  4994.2  270.87  5001.3  273.72  5025.1  276.73  5040.0  281.57  5072.0  287.29
  5173.1  295.02  5213.5  294.24  5294.3  297.93  5305.2  296.92  5553.3  297.67
#Mann=8,-1,0
  3613.6    0.05       0  3704.6    0.07       0  3928.0   0.035       0
  3943.9    0.07       0  4734.8    0.12       0  4988.2    0.05       0
  4994.2    0.12       0  5040.0    0.07       0
Bank Sta=4988.2,4994.2
Exp/Cntr=0.3,0.1

Type RM Length L Ch R = 1,2360,172,172,172
BEGIN DESCRIPTION:
XS6438
END DESCRIPTION:
XS GIS Cut Line= 3
      2527839.11     13653939.55      2527510.20     13654685.47
      2527598.30     13656124.46
#Sta/Elev= 30
  3517.9  301.78  3743.3  293.26  3761.2  294.18  3917.5  286.47  4007.3  284.87
  4086.2  283.05  4155.4  283.54  4185.0  283.34  4190.5  281.97  4213.8  283.10
  4231.6  280.92  4254.9  280.47  4556.0  279.12  4792.6  279.43  4873.7  279.07
  4913.7  272.54  4933.8  271.07  4953.8  271.63  4970.8  269.79  4971.3  269.29
  4976.8  269.79  5003.9  270.98  5054.0  281.19  5064.0  280.62  5084.0  275.58
  5094.1  275.72  5164.2  282.55  5447.3  290.26  5595.0  294.18  5774.8  295.58
#Mann=8,-1,0
  3517.9    0.05       0  4007.3    0.07       0  4155.4   0.035       0
  4556.0    0.07       0  4792.6   0.035       0  4970.8   0.035       0
  4976.8   0.035       0  5447.3    0.07       0
Bank Sta=4970.8,4976.8
Exp/Cntr=0.3,0.1

Type RM Length L Ch R = 1,2188,485,485,485
BEGIN DESCRIPTION:
Stream0313 5.0
END DESCRIPTION:
XS GIS Cut Line= 3
      2527792.14     13653939.51      2527422.10     13654732.46
      2527498.45     13656159.68
#Sta/Elev= 30
  3631.9  301.04  3958.0  290.02  4046.3  284.68  4111.0  283.47  4219.6  282.40
  4256.6  282.91  4279.5  281.16  4302.3  282.39  4342.5  279.80  4416.6  280.96
  4439.5  280.24  4445.0  278.77  4510.7  279.02  4589.6  276.42  4619.6  277.83
  4916.5  278.48  4950.1  276.86  5007.2  268.96  5007.7  268.46  5013.2  268.96
  5015.3  269.17  5027.2  270.73  5050.3  270.53  5070.3  273.73  5110.3  274.37
  5160.4  282.97  5190.7  282.18  5583.4  287.91  5801.3  291.52  5936.2  292.01
#Mann=9,-1,0
  3631.9    0.05       0  4111.0    0.07       0  4219.6   0.035       0
  4916.5    0.07       0  5007.2    0.05       0  5013.2    0.07       0
  5015.3    0.12       0  5190.7    0.05       0  5583.4   0.035       0
Bank Sta=5007.2,5013.2
Exp/Cntr=0.3,0.1

Type RM Length L Ch R = 1,1703,317,317,317
BEGIN DESCRIPTION:
Stream0313 4.0
END DESCRIPTION:
XS GIS Cut Line= 3
      2527762.73     13653916.09      2527122.56     13654932.15
      2526958.10     13656007.03
#Sta/Elev= 30
  3878.3  301.05  4029.1  296.45  4329.8  283.64  4390.5  282.59  4427.0  279.70
  4432.9  281.21  4448.2  281.27  4478.8  280.91  4484.7  278.92  4523.1  279.25
  4709.6  276.30  4834.3  277.88  4905.3  277.17  4933.9  273.56  4940.7  270.28
  4964.4  270.73  4986.2  274.37  4992.1  274.29  5010.2  268.17  5010.7  267.67
  5016.3  268.17  5028.6  270.20  5049.8  269.85  5083.2  271.30  5112.4  276.30
  5181.2  277.53  5466.1  279.10  5577.8  280.27  6115.4  280.78  6166.6  280.82
#Mann=8,-1,0
  3878.3    0.05       0  4329.8   0.035       0  4523.1    0.12       0
  5010.2    0.05       0  5016.3    0.12       0  5181.2    0.05       0
  5466.1    0.07       0  6115.4    0.05       0
Bank Sta=5010.2,5016.3
Exp/Cntr=0.3,0.1

Type RM Length L Ch R = 1,1386,441,441,441
BEGIN DESCRIPTION:
Stream0313 3.0
END DESCRIPTION:
XS GIS Cut Line= 3
      2527675.03     13653974.97      2526875.00     13654775.00
      2526725.00     13655425.00
#Sta/Elev= 30
  3873.1  298.07  4082.5  289.60  4156.0  287.45  4184.3  284.72  4264.9  281.34
  4311.6  278.09  4354.0  277.03  4410.5  275.78  4520.1  275.07  4673.6  275.97
  4778.2  274.61  4834.8  275.27  4849.0  274.51  4863.1  272.42  4877.2  272.10
  4933.8  274.02  4962.1  270.99  4987.3  264.69  4987.8  264.19  4993.5  264.69
  5007.1  265.63  5014.8  267.56  5028.5  266.98  5055.8  269.08  5066.1  272.68
  5076.4  274.95  5097.1  274.88  5374.0  276.88  5514.2  279.04  5671.6  279.41
#Mann=8,-1,0
  3873.1    0.05       0  4082.5   0.035       0  4264.9    0.05       0
  4520.1   0.035       0  4673.6    0.12       0  4987.3    0.05       0
  4993.5    0.12       0  5097.1    0.05       0
Bank Sta=4987.3,4993.5
Exp/Cntr=0.3,0.1

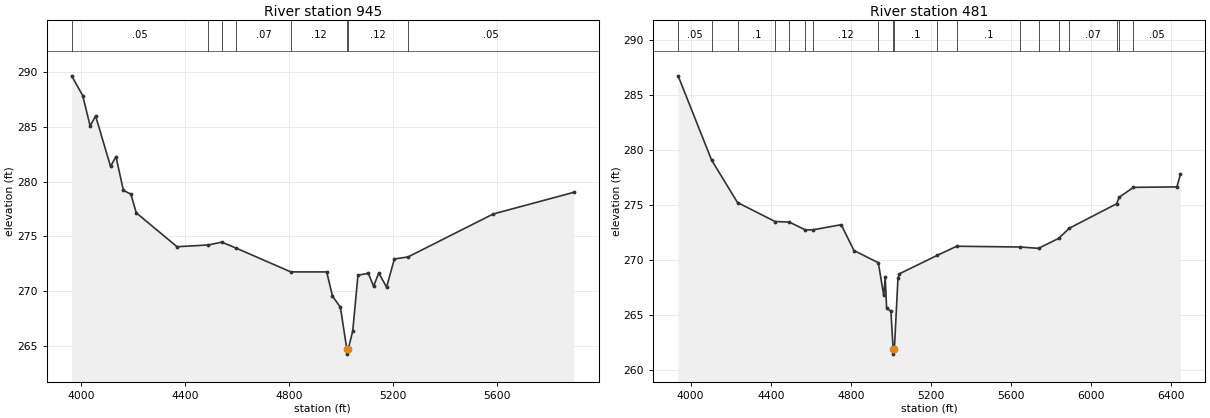
Type RM Length L Ch R = 1,945,464,464,464
BEGIN DESCRIPTION:
Stream0313 2.0
END DESCRIPTION:
XS GIS Cut Line= 3
      2527325.03     13653874.98      2526525.00     13654525.00
      2526525.00     13655424.99
#Sta/Elev= 30
  3964.4  289.66  4006.8  287.86  4035.6  285.07  4056.4  286.00  4113.9  281.39
  4134.7  282.28  4163.4  279.20  4192.1  278.85  4213.0  277.14  4369.6  274.05
  4489.9  274.21  4541.6  274.47  4597.2  273.92  4807.0  271.75  4944.9  271.75
  4967.2  269.54  4997.7  268.52  5022.1  264.74  5022.6  264.24  5028.3  264.74
  5045.2  266.37  5065.2  271.45  5105.2  271.62  5125.2  270.44  5145.2  271.65
  5175.2  270.36  5205.2  272.93  5257.9  273.12  5585.2  277.04  5895.2  279.02
#Mann=8,-1,0
  3964.4    0.05       0  4489.9    0.12       0  4541.6   0.035       0
  4597.2    0.07       0  4807.0    0.12       0  5022.1    0.05       0
  5028.3    0.12       0  5257.9    0.05       0
Bank Sta=5022.1,5028.3
Exp/Cntr=0.3,0.1

Type RM Length L Ch R = 1,481,0,0,0
BEGIN DESCRIPTION:
Stream0313 1.0
END DESCRIPTION:
XS GIS Cut Line= 3
      2526975.01     13653424.99      2526176.95     13654309.57
      2526364.64     13655611.73
#Sta/Elev= 30
  3937.6  286.76  4104.8  279.09  4234.1  275.23  4421.5  273.50  4492.9  273.45
  4573.2  272.73  4610.0  272.74  4751.8  273.21  4815.4  270.86  4937.1  269.75
  4964.1  266.78  4971.5  268.41  4978.3  265.66  4999.9  265.31  5010.9  261.93
  5011.4  261.43  5017.3  261.93  5035.1  268.32  5042.0  268.74  5230.1  270.41
  5328.2  271.25  5644.4  271.18  5736.8  271.06  5836.8  271.96  5890.8  272.89
  6127.0  275.12  6138.9  275.70  6210.6  276.61  6427.7  276.65  6444.6  277.78
#Mann=19,-1,0
  3937.6    0.05       0  4104.8    0.07       0  4234.1     0.1       0
  4421.5    0.05       0  4492.9    0.12       0  4573.2    0.05       0
  4610.0    0.12       0  4937.1     0.1       0  5010.9    0.05       0
  5017.3     0.1       0  5230.1    0.12       0  5328.2     0.1       0
  5644.4    0.12       0  5736.8     0.1       0  5836.8    0.12       0
  5890.8    0.07       0  6127.0    0.05       0  6138.9    0.07       0
  6210.6    0.05       0
Bank Sta=5010.9,5017.3
Exp/Cntr=0.3,0.1

Chan Stop Cuts=-1