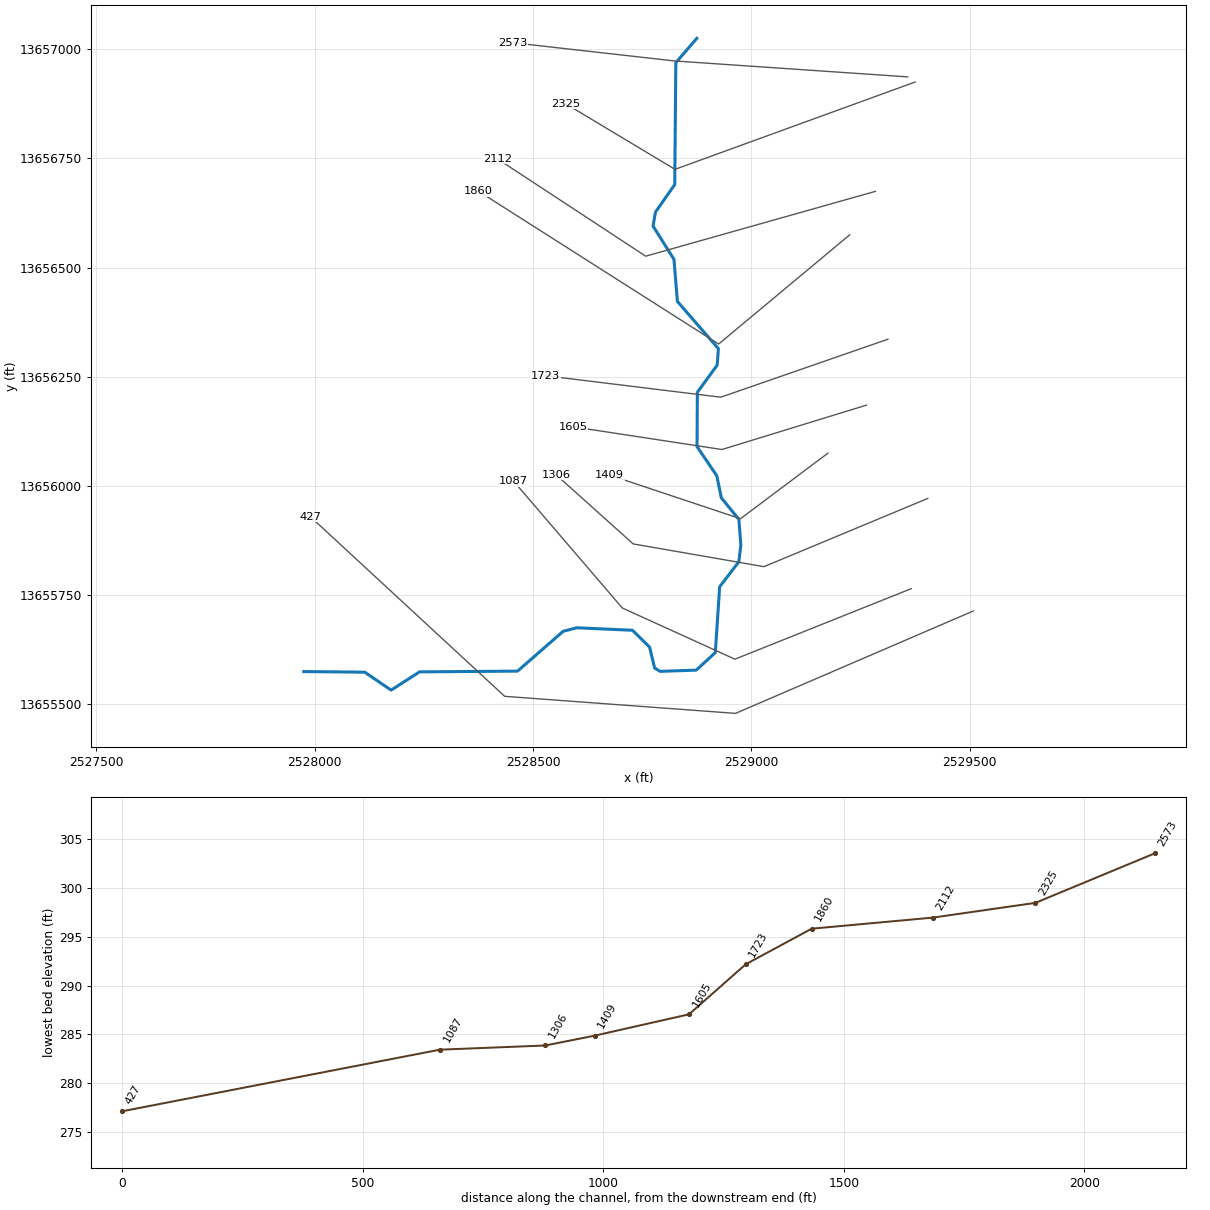
--- Stream0314.prj (project) ---

Proj Title=Stream0314 Base Level Engineering
Current Plan=p01
Default Exp/Contr=0.3,0.1
English Units
Geom File=g01
Flow File=f01
Plan File=p01
BEGIN DESCRIPTION:
Stream0314
END DESCRIPTION:

--- Stream0314.p01 (plan) ---

Plan Title=Multiple Run
Short Identifier=Multiple
Geom File=g01
Flow File=f01
Subcritical Flow
K Sum by GR= 0
Std Step Tol= 0.01
Critical Tol= 0.01
Num of Std Step Trials= 20
Max Error Tol= 0.3
Flow Tol Ratio= 0.001
Split Flow NTrial= 30
Split Flow Tol= 0.02
Split Flow Ratio= 0.02
Log Output Level= 0
Friction Slope Method= 1
Unsteady Friction Slope Method= 2
Unsteady Bridges Friction Slope Method= 1
Parabolic Critical Depth
Global Vel Dist=  1 , 1 , 1
Global Log Level= 0
CheckData=True
Encroach Param= -1, 0, 0, 0
BEGIN DESCRIPTION:
Multiple Run
END DESCRIPTION:

--- Stream0314.f01 (steady flow) ---

Flow Title=Multiple
Number of Profiles=7
Profile Names=10-year,25-year,50-year,1pct_min,100-year,1pct_plu,500-year
River Rch & RM= Stream0314,Reach-1,2573
     448     701     923     590    1177    2348    1891
Boundary for River Rch & Prof#=Stream0314,Reach-1,1
Up Type=0
Dn Type=3
Dn Slope=0.005
Boundary for River Rch & Prof#=Stream0314,Reach-1,2
Up Type=0
Dn Type=3
Dn Slope=0.005
Boundary for River Rch & Prof#=Stream0314,Reach-1,3
Up Type=0
Dn Type=3
Dn Slope=0.005
Boundary for River Rch & Prof#=Stream0314,Reach-1,4
Up Type=0
Dn Type=3
Dn Slope=0.005
Boundary for River Rch & Prof#=Stream0314,Reach-1,5
Up Type=0
Dn Type=3
Dn Slope=0.005
Boundary for River Rch & Prof#=Stream0314,Reach-1,6
Up Type=0
Dn Type=3
Dn Slope=0.005
Boundary for River Rch & Prof#=Stream0314,Reach-1,7
Up Type=0
Dn Type=3
Dn Slope=0.005

--- Stream0314.g01 (geometry) ---

Geom Title=Existing Conditions

River Reach=Stream0314,Reach-1
Reach XY= 30
      2528875.00     13657025.00      2528826.89     13656969.22
      2528824.46     13656690.21      2528780.38     13656627.18
      2528774.72     13656595.18      2528822.62     13656519.03
      2528830.54     13656422.58      2528924.40     13656314.38
      2528921.66     13656276.75      2528876.23     13656214.50
      2528875.49     13656090.22      2528920.81     13656023.26
      2528931.12     13655972.82      2528971.33     13655923.42
      2528975.78     13655864.95      2528971.30     13655826.60
      2528927.27     13655769.06      2528917.32     13655618.47
      2528873.68     13655578.33      2528790.91     13655575.53
      2528778.43     13655583.08      2528766.83     13655631.03
      2528727.68     13655669.61      2528599.89     13655675.32
      2528568.82     13655667.18      2528464.56     13655576.06
      2528240.16     13655574.34      2528175.00     13655532.56
      2528114.59     13655573.66      2527975.00     13655575.00

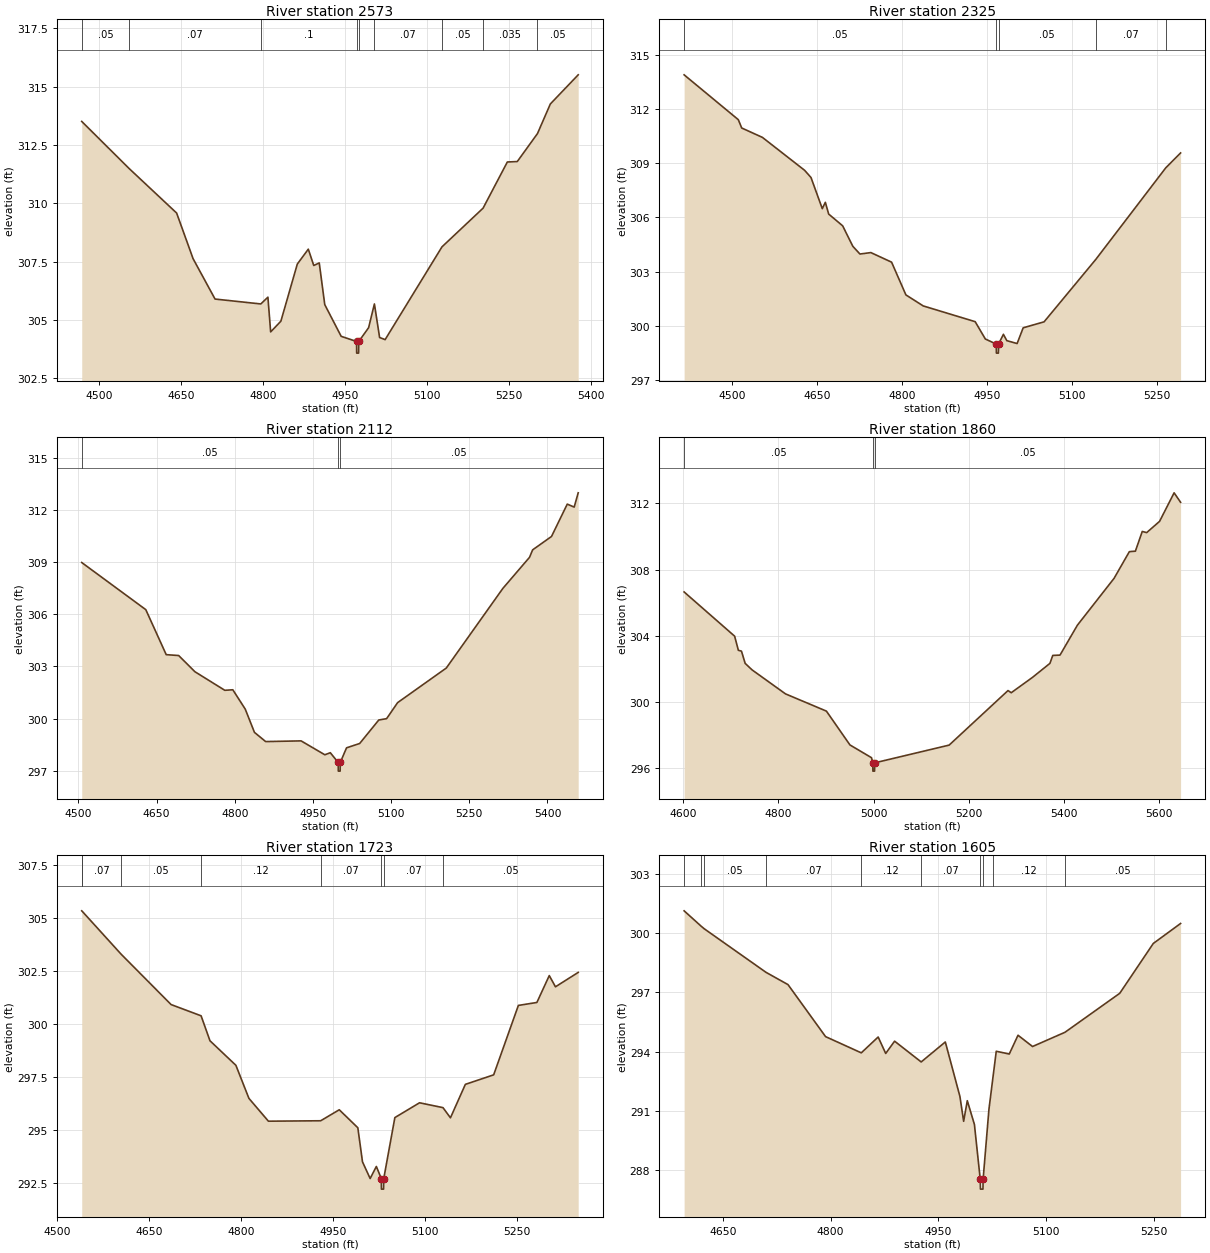
Type RM Length L Ch R = 1,2573,248,248,248
BEGIN DESCRIPTION:
XS6445
END DESCRIPTION:
XS GIS Cut Line= 3
      2529358.02     13656936.72      2528824.22     13656973.18
      2528454.41     13657014.85
#Sta/Elev= 30
  4468.8  313.51  4555.4  311.49  4642.2  309.58  4672.3  307.62  4712.4  305.89
  4796.0  305.68  4809.0  305.97  4814.0  304.48  4832.7  304.94  4862.7  307.39
  4882.8  308.03  4892.8  307.33  4902.8  307.44  4912.9  305.65  4942.9  304.29
  4971.0  304.07  4971.2  303.57  4974.7  303.57  4975.0  304.07  4993.0  304.66
  5003.6  305.68  5013.1  304.24  5023.2  304.15  5127.1  308.13  5202.2  309.79
  5246.5  311.77  5264.7  311.79  5301.6  312.99  5325.1  314.26  5376.0  315.51
#Mann=9,-1,0
  4468.8    0.05       0  4555.4    0.07       0  4796.0     0.1       0
  4971.0    0.05       0  4975.0     0.1       0  5003.6    0.07       0
  5127.1    0.05       0  5202.2   0.035       0  5301.6    0.05       0
Bank Sta=4971,4975
Exp/Cntr=0.3,0.1

Type RM Length L Ch R = 1,2325,213,213,213
BEGIN DESCRIPTION:
Stream0314 3.0
END DESCRIPTION:
XS GIS Cut Line= 3
      2529374.97     13656924.99      2528825.00     13656725.00
      2528574.96     13656875.02
#Sta/Elev= 30
  4415.2  313.88  4510.9  311.40  4516.9  310.94  4553.5  310.42  4628.0  308.60
  4639.3  308.20  4659.2  306.48  4664.6  306.83  4670.5  306.18  4695.2  305.53
  4713.1  304.40  4725.7  303.97  4745.0  304.05  4781.6  303.52  4806.9  301.71
  4837.5  301.10  4929.2  300.23  4947.2  299.27  4966.5  298.99  4966.7  298.49
  4970.2  298.49  4970.5  298.99  4979.1  299.53  4985.1  299.18  5003.3  299.02
  5014.0  299.89  5050.9  300.22  5142.2  303.67  5265.9  308.74  5292.0  309.56
#Mann=5,-1,0
  4415.2    0.05       0  4966.5    0.05       0  4970.5    0.05       0
  5142.2    0.07       0  5265.9    0.05       0
Bank Sta=4966.5,4970.5
Exp/Cntr=0.3,0.1

Type RM Length L Ch R = 1,2112,252,252,252
BEGIN DESCRIPTION:
E20888
END DESCRIPTION:
XS GIS Cut Line= 3
      2529283.98     13656674.61      2528757.96     13656526.17
      2528418.53     13656749.00
#Sta/Elev= 30
  4506.4  308.98  4629.3  306.27  4668.5  303.68  4692.4  303.63  4723.5  302.70
  4780.9  301.63  4796.3  301.66  4820.1  300.55  4837.8  299.21  4859.3  298.68
  4927.3  298.72  4972.9  297.92  4983.3  298.04  4998.5  297.48  4998.7  296.98
  5002.2  296.98  5002.5  297.48  5014.5  298.32  5039.7  298.57  5076.3  299.92
  5091.4  300.00  5112.5  300.92  5205.9  302.91  5314.4  307.49  5365.6  309.28
  5371.6  309.71  5407.8  310.48  5438.0  312.34  5451.3  312.17  5459.0  312.99
#Mann=3,-1,0
  4506.4    0.05       0  4998.5    0.05       0  5002.5    0.05       0
Bank Sta=4998.5,5002.5
Exp/Cntr=0.3,0.1

Type RM Length L Ch R = 1,1860,137,137,137
BEGIN DESCRIPTION:
Stream0314 2.0
END DESCRIPTION:
XS GIS Cut Line= 3
      2529225.02     13656575.01      2528925.00     13656325.00
      2528374.96     13656675.02
#Sta/Elev= 30
  4602.2  306.65  4708.3  303.98  4716.1  303.13  4722.6  303.08  4730.4  302.34
  4744.8  301.95  4815.1  300.50  4901.0  299.46  4950.4  297.42  4995.7  296.65
  4998.4  296.34  4998.6  295.84  5002.1  295.84  5002.4  296.34  5158.7  297.41
  5282.3  300.70  5289.1  300.57  5333.9  301.50  5370.3  302.34  5376.3  302.82
  5391.5  302.84  5427.9  304.64  5505.0  307.47  5537.1  309.08  5549.8  309.11
  5564.2  310.30  5573.5  310.23  5600.6  310.91  5631.1  312.63  5644.7  312.06
#Mann=3,-1,0
  4602.2    0.05       0  4998.4    0.05       0  5002.4    0.05       0
Bank Sta=4998.4,5002.4
Exp/Cntr=0.3,0.1

Type RM Length L Ch R = 1,1723,118,118,118
BEGIN DESCRIPTION:
E20887
END DESCRIPTION:
XS GIS Cut Line= 3
      2529312.65     13656336.07      2528929.83     13656203.26
      2528528.14     13656252.50
#Sta/Elev= 30
  4540.1  305.34  4541.1  305.31  4604.4  303.29  4685.9  300.91  4734.8  300.38
  4749.3  299.20  4791.6  298.04  4812.8  296.48  4844.6  295.40  4929.9  295.42
  4960.2  295.94  4990.5  295.09  4998.1  293.48  5010.6  292.69  5020.7  293.26
  5028.8  292.69  5029.0  292.19  5032.5  292.19  5032.8  292.69  5050.9  295.57
  5091.2  296.27  5129.4  296.04  5141.6  295.56  5165.9  297.14  5212.1  297.59
  5252.4  300.87  5282.6  301.01  5302.8  302.28  5312.9  301.75  5350.0  302.43
#Mann=8,-1,0
  4540.1    0.05       0  4541.1    0.07       0  4604.4    0.05       0
  4734.8    0.12       0  4929.9    0.07       0  5028.8    0.05       0
  5032.8    0.07       0  5129.4    0.05       0
Bank Sta=5028.8,5032.8
Exp/Cntr=0.3,0.1

Type RM Length L Ch R = 1,1605,196,196,196
BEGIN DESCRIPTION:
E20886
END DESCRIPTION:
XS GIS Cut Line= 3
      2529263.20     13656185.04      2528932.44     13656083.47
      2528591.30     13656135.55
#Sta/Elev= 30
  4596.2  301.12  4620.0  300.34  4624.3  300.21  4710.2  298.01  4740.8  297.39
  4793.1  294.76  4842.8  293.94  4866.3  294.74  4876.8  293.91  4889.2  294.53
  4926.2  293.48  4959.8  294.49  4980.1  291.74  4985.3  290.48  4990.4  291.52
  5000.3  290.32  5008.4  287.55  5008.7  287.05  5012.2  287.05  5012.4  287.55
  5020.5  291.08  5026.5  292.81  5030.7  294.02  5048.8  293.88  5061.0  294.83
  5081.2  294.26  5126.4  294.98  5202.6  296.95  5249.3  299.47  5287.3  300.48
#Mann=10,-1,0
  4596.2    0.05       0  4620.0    0.07       0  4624.3    0.05       0
  4710.2    0.07       0  4842.8    0.12       0  4926.2    0.07       0
  5008.4    0.05       0  5012.4    0.07       0  5026.5    0.12       0
  5126.4    0.05       0
Bank Sta=5008.4,5012.4
Exp/Cntr=0.3,0.1

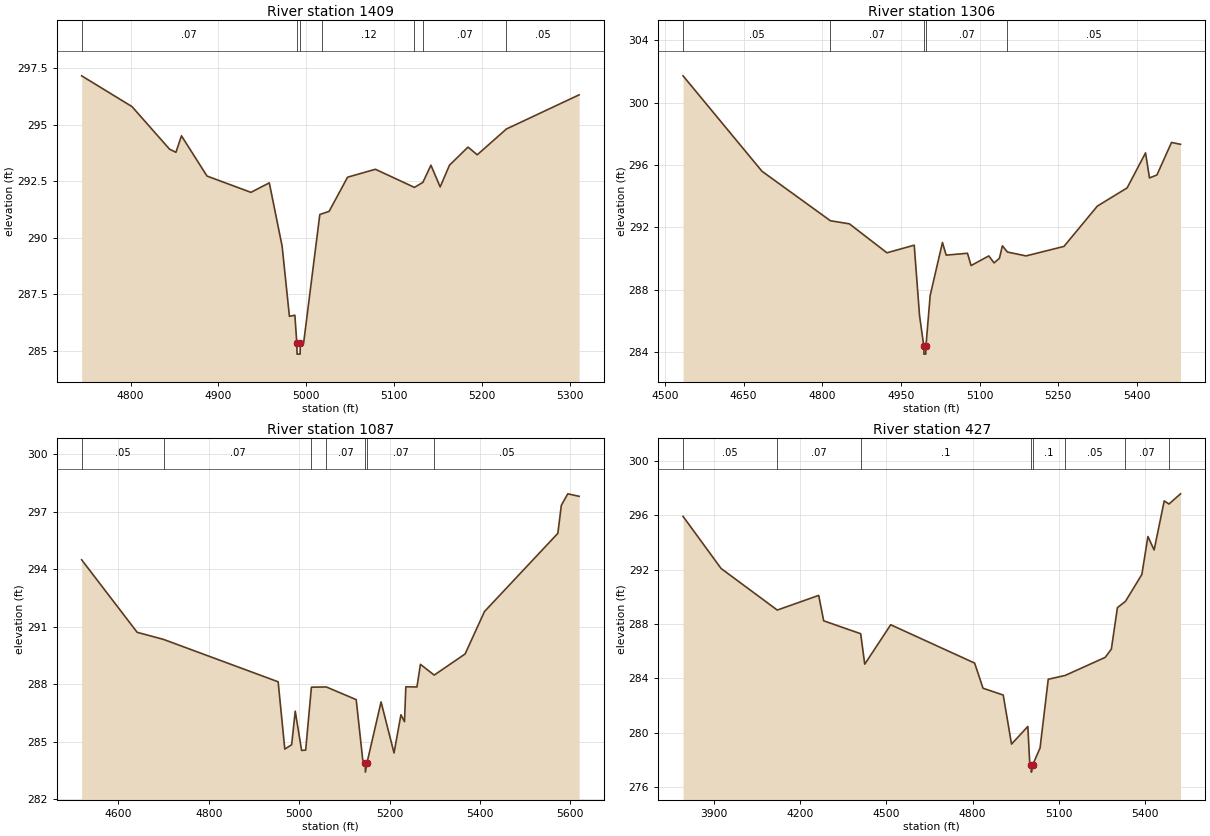
Type RM Length L Ch R = 1,1409,103,103,103
BEGIN DESCRIPTION:
Stream0314 1.0
END DESCRIPTION:
XS GIS Cut Line= 3
      2529175.02     13656075.02      2528975.00     13655925.00
      2528674.96     13656025.01
#Sta/Elev= 30
  4744.3  297.16  4801.6  295.80  4844.3  293.92  4851.6  293.78  4857.9  294.51
  4887.0  292.73  4937.0  292.01  4957.9  292.43  4972.5  289.63  4980.8  286.53
  4987.0  286.58  4989.2  285.36  4989.5  284.86  4993.0  284.86  4993.2  285.36
  4997.0  285.36  5015.4  291.03  5018.4  291.07  5026.0  291.17  5047.0  292.68
  5078.7  293.03  5123.1  292.23  5132.7  292.45  5141.9  293.21  5152.4  292.25
  5163.0  293.21  5184.1  294.01  5194.6  293.67  5227.8  294.81  5310.6  296.32
#Mann=7,-1,0
  4744.3    0.07       0  4989.2    0.05       0  4993.2    0.07       0
  5018.4    0.12       0  5123.1    0.05       0  5132.7    0.07       0
  5227.8    0.05       0
Bank Sta=4989.2,4993.2
Exp/Cntr=0.3,0.1

Type RM Length L Ch R = 1,1306,219,219,219
BEGIN DESCRIPTION:
E20885
END DESCRIPTION:
XS GIS Cut Line= 4
      2529403.83     13655971.50      2529028.79     13655815.24
      2528729.31     13655867.32      2528552.20     13656026.20
#Sta/Elev= 30
  4534.7  301.73  4685.1  295.60  4815.5  292.42  4851.8  292.22  4923.3  290.36
  4975.3  290.85  4985.4  286.34  4993.6  284.35  4993.8  283.85  4997.3  283.85
  4997.6  284.35  5005.7  287.62  5029.1  291.02  5036.2  290.21  5076.8  290.33
  5083.7  289.54  5117.4  290.16  5127.5  289.71  5137.7  290.01  5143.3  290.81
  5152.9  290.41  5188.4  290.16  5260.7  290.77  5324.3  293.36  5381.1  294.53
  5416.2  296.78  5423.7  295.17  5437.9  295.36  5465.7  297.45  5482.9  297.33
#Mann=5,-1,0
  4534.7    0.05       0  4815.5    0.07       0  4993.6    0.05       0
  4997.6    0.07       0  5152.9    0.05       0
Bank Sta=4993.6,4997.6
Exp/Cntr=0.3,0.1

Type RM Length L Ch R = 1,1087,660,660,660
BEGIN DESCRIPTION:
XS6444
END DESCRIPTION:
XS GIS Cut Line= 4
      2529365.87     13655764.84      2528962.24     13655603.39
      2528704.43     13655720.57      2528455.38     13656011.12
#Sta/Elev= 30
  4518.7  294.49  4641.5  290.71  4699.8  290.34  4953.4  288.13  4968.1  284.62
  4983.3  284.85  4991.2  286.60  5005.3  284.55  5014.3  284.57  5027.0  287.85
  5060.0  287.86  5126.1  287.20  5140.6  284.05  5146.1  283.92  5146.4  283.42
  5150.1  283.92  5181.1  287.08  5209.8  284.42  5225.0  286.41  5232.9  286.05
  5235.9  287.87  5260.5  287.86  5268.2  289.04  5298.7  288.48  5367.0  289.58
  5409.8  291.79  5572.2  295.87  5579.9  297.33  5594.2  297.93  5619.3  297.80
#Mann=7,-1,0
  4518.7    0.05       0  4699.8    0.07       0  5027.0     0.1       0
  5060.0    0.07       0  5146.1    0.05       0  5150.1    0.07       0
  5298.7    0.05       0
Bank Sta=5146.1,5150.1
Exp/Cntr=0.3,0.1

Type RM Length L Ch R = 1,427,0,0,0
BEGIN DESCRIPTION:
E20884
END DESCRIPTION:
XS GIS Cut Line= 4
      2529507.96     13655713.67      2528963.69     13655479.30
      2528435.04     13655518.36      2527989.88     13655929.87
#Sta/Elev= 30
  3794.0  295.91  3926.1  292.08  4121.4  289.02  4265.4  290.10  4282.7  288.23
  4411.3  287.28  4425.4  285.04  4515.6  287.94  4807.3  285.12  4836.5  283.27
  4906.7  282.77  4935.5  279.16  4992.2  280.46  4999.0  277.67  5004.4  277.60
  5004.6  277.10  5008.4  277.60  5034.7  278.88  5063.1  283.93  5121.7  284.21
  5261.0  285.54  5282.5  286.15  5303.5  289.20  5331.5  289.66  5388.5  291.64
  5409.5  294.43  5431.1  293.44  5466.2  297.05  5482.7  296.82  5522.9  297.57
#Mann=8,-1,0
  3794.0    0.05       0  4121.4    0.07       0  4411.3     0.1       0
  5004.4    0.05       0  5008.4     0.1       0  5121.7    0.05       0
  5331.5    0.07       0  5482.7    0.05       0
Bank Sta=5004.4,5008.4
Exp/Cntr=0.3,0.1

Chan Stop Cuts=-1