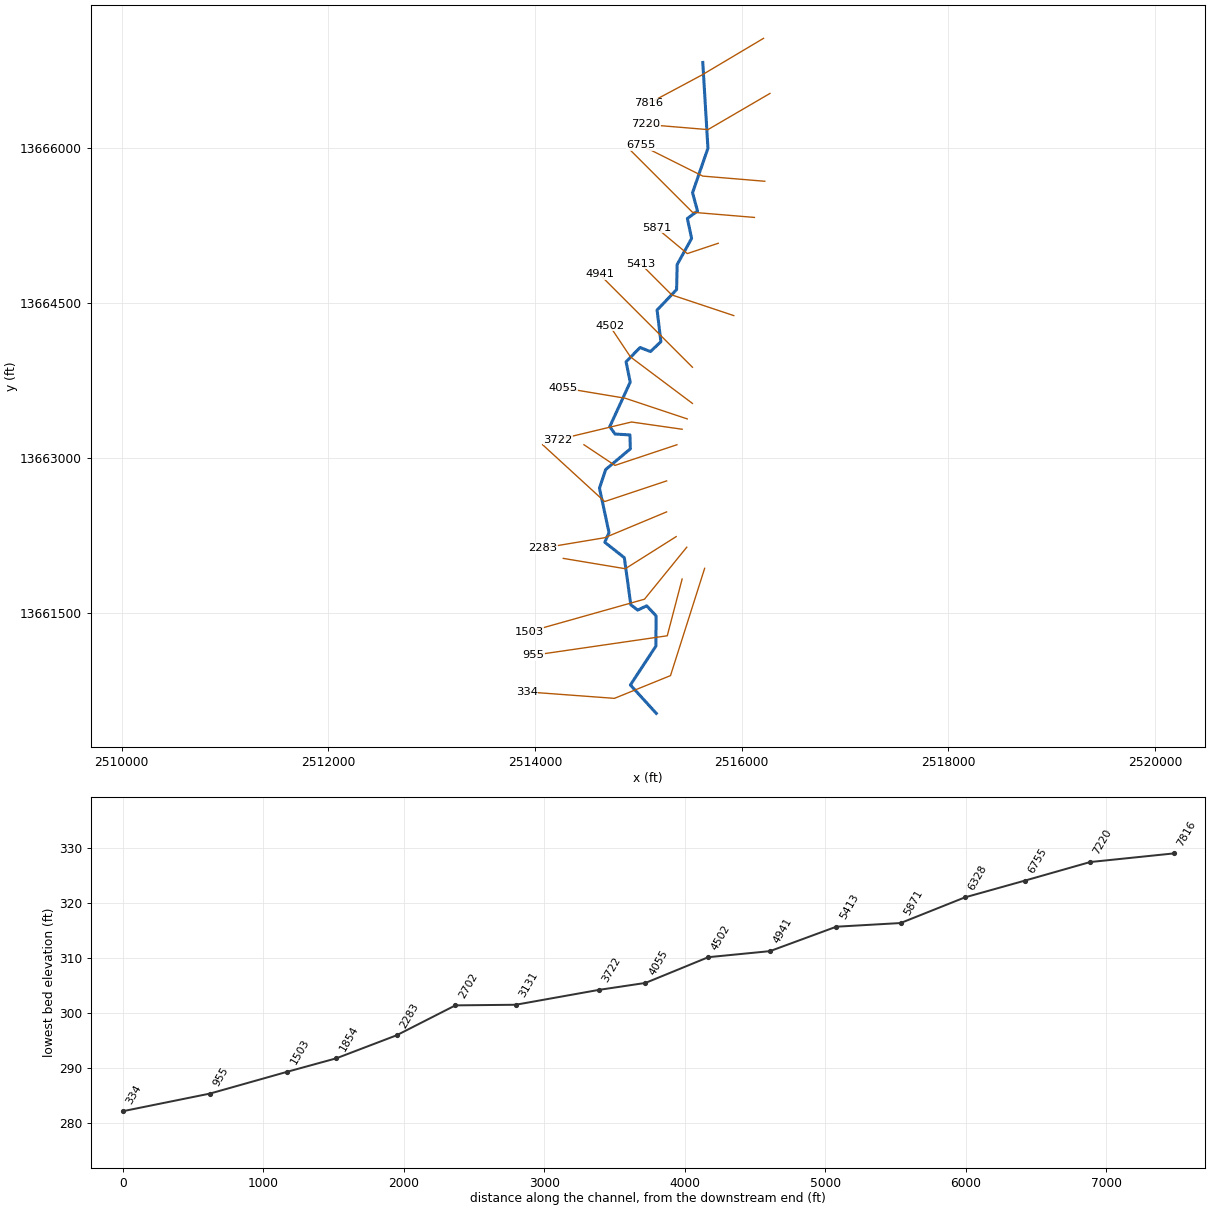
--- Stream0318.prj (project) ---

Proj Title=Stream0318 Base Level Engineering
Current Plan=p01
Default Exp/Contr=0.3,0.1
English Units
Geom File=g01
Flow File=f01
Plan File=p01
BEGIN DESCRIPTION:
Stream0318
END DESCRIPTION:

--- Stream0318.p01 (plan) ---

Plan Title=Multiple Run
Short Identifier=Multiple
Geom File=g01
Flow File=f01
Subcritical Flow
K Sum by GR= 0
Std Step Tol= 0.01
Critical Tol= 0.01
Num of Std Step Trials= 20
Max Error Tol= 0.3
Flow Tol Ratio= 0.001
Split Flow NTrial= 30
Split Flow Tol= 0.02
Split Flow Ratio= 0.02
Log Output Level= 0
Friction Slope Method= 1
Unsteady Friction Slope Method= 2
Unsteady Bridges Friction Slope Method= 1
Parabolic Critical Depth
Global Vel Dist=  1 , 1 , 1
Global Log Level= 0
CheckData=True
Encroach Param= -1, 0, 0, 0
BEGIN DESCRIPTION:
Multiple Run
END DESCRIPTION:

--- Stream0318.f01 (steady flow) ---

Flow Title=Multiple
Number of Profiles=7
Profile Names=10-year,25-year,50-year,1pct_min,100-year,1pct_plu,500-year
River Rch & RM= Stream0318,Reach-1,7816
     722    1163    1560    1014    2023    4037    3366
Boundary for River Rch & Prof#=Stream0318,Reach-1,1
Up Type=0
Dn Type=3
Dn Slope=0.005
Boundary for River Rch & Prof#=Stream0318,Reach-1,2
Up Type=0
Dn Type=3
Dn Slope=0.005
Boundary for River Rch & Prof#=Stream0318,Reach-1,3
Up Type=0
Dn Type=3
Dn Slope=0.005
Boundary for River Rch & Prof#=Stream0318,Reach-1,4
Up Type=0
Dn Type=3
Dn Slope=0.005
Boundary for River Rch & Prof#=Stream0318,Reach-1,5
Up Type=0
Dn Type=3
Dn Slope=0.005
Boundary for River Rch & Prof#=Stream0318,Reach-1,6
Up Type=0
Dn Type=3
Dn Slope=0.005
Boundary for River Rch & Prof#=Stream0318,Reach-1,7
Up Type=0
Dn Type=3
Dn Slope=0.005

--- Stream0318.g01 (geometry) ---

Geom Title=Existing Conditions

River Reach=Stream0318,Reach-1
Reach XY= 30
      2515625.00     13666825.00      2515674.93     13665995.03
      2515526.09     13665564.46      2515573.81     13665387.02
      2515475.99     13665314.70      2515516.92     13665121.70
      2515377.07     13664869.14      2515371.46     13664626.46
      2515182.79     13664428.42      2515219.55     13664122.53
      2515118.96     13664026.65      2515018.27     13664065.85
      2514882.79     13663928.42      2514922.75     13663730.94
      2514724.46     13663299.87      2514776.23     13663228.45
      2514920.00     13663219.99      2514923.97     13663085.45
      2514685.39     13662885.10      2514624.91     13662704.90
      2514717.41     13662274.99      2514676.58     13662180.87
      2514865.71     13662031.69      2514928.52     13661576.22
      2514995.05     13661524.63      2515081.75     13661565.86
      2515172.94     13661469.17      2515171.45     13661176.47
      2514924.41     13660800.00      2515175.00     13660525.00

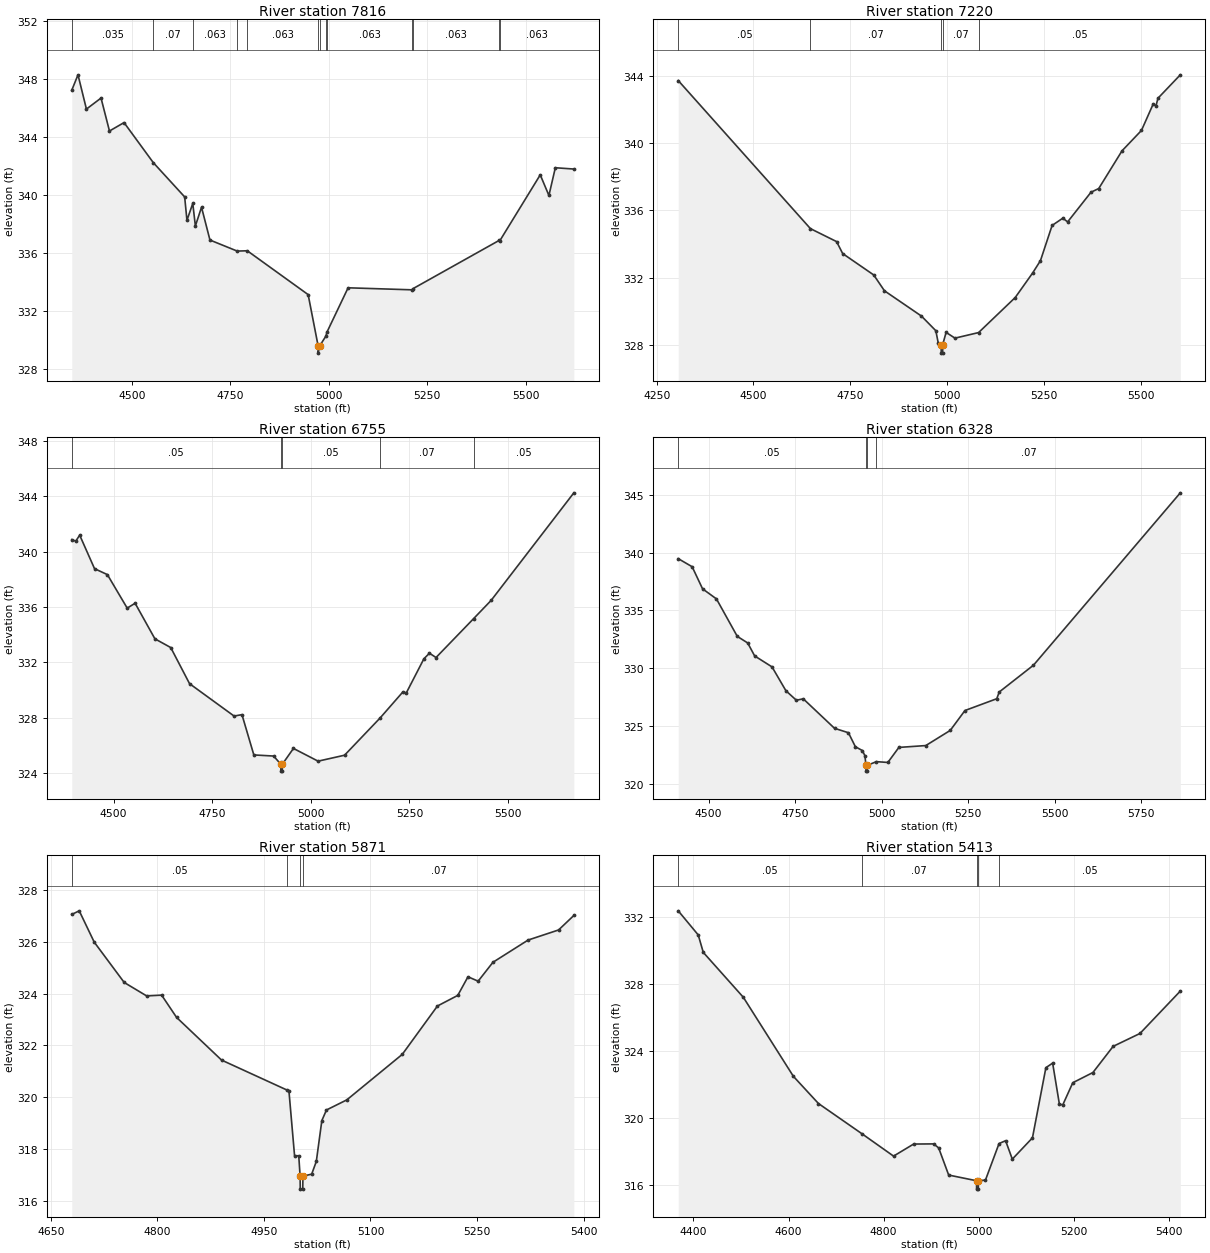
Type RM Length L Ch R = 1,7816,596,596,596
BEGIN DESCRIPTION:
Stream0318 16.0
END DESCRIPTION:
XS GIS Cut Line= 3
      2516213.09     13667058.39      2515614.23     13666702.22
      2515104.57     13666429.94
#Sta/Elev= 30
  4347.6  347.21  4363.4  348.27  4384.8  345.91  4421.9  346.67  4443.3  344.40
  4480.3  344.98  4554.6  342.22  4634.2  339.86  4640.0  338.25  4654.8  339.41
  4661.4  337.86  4677.0  339.15  4698.4  336.89  4767.5  336.13  4793.2  336.15
  4947.7  333.13  4973.0  329.60  4973.2  329.10  4977.0  329.60  4992.7  330.27
  4995.5  330.55  5049.1  333.60  5211.7  333.46  5213.8  333.54  5432.3  336.86
  5433.6  336.81  5536.9  341.38  5558.9  339.96  5575.2  341.87  5622.2  341.78
#Mann=13,-1,0
  4347.6   0.035       0  4554.6    0.07       0  4654.8   0.063       0
  4767.5   0.035       0  4793.2   0.063       0  4973.0    0.05       0
  4977.0   0.063       0  4992.7   0.035       0  4995.5   0.063       0
  5211.7    0.07       0  5213.8   0.063       0  5432.3    0.05       0
  5433.6   0.063       0
Bank Sta=4973,4977
Exp/Cntr=0.3,0.1

Type RM Length L Ch R = 1,7220,465,465,465
BEGIN DESCRIPTION:
Stream0318 15.0
END DESCRIPTION:
XS GIS Cut Line= 3
      2516275.04     13666525.02      2515675.00     13666175.00
      2515075.05     13666225.00
#Sta/Elev= 30
  4305.8  343.71  4647.2  334.92  4714.8  334.15  4730.5  333.44  4810.7  332.17
  4838.4  331.23  4933.9  329.73  4971.1  328.86  4977.3  328.13  4984.8  328.03
  4985.1  327.53  4988.6  327.53  4988.8  328.03  4997.6  328.76  5020.5  328.42
  5081.5  328.75  5176.1  330.83  5221.2  332.29  5241.3  333.02  5271.4  335.11
  5299.0  335.54  5311.5  335.32  5371.8  337.08  5391.8  337.30  5452.0  339.54
  5502.2  340.75  5532.3  342.31  5539.8  342.22  5544.8  342.66  5602.5  344.05
#Mann=5,-1,0
  4305.8    0.05       0  4647.2    0.07       0  4984.8    0.05       0
  4988.8    0.07       0  5081.5    0.05       0
Bank Sta=4984.8,4988.8
Exp/Cntr=0.3,0.1

Type RM Length L Ch R = 1,6755,427,427,427
BEGIN DESCRIPTION:
Stream0318 14.0
END DESCRIPTION:
XS GIS Cut Line= 3
      2516225.03     13665675.00      2515625.00     13665725.00
      2515025.03     13666024.99
#Sta/Elev= 30
  4393.8  340.88  4403.9  340.77  4413.9  341.20  4451.5  338.78  4484.1  338.35
  4534.3  335.93  4554.4  336.28  4604.6  333.71  4644.7  333.08  4692.4  330.47
  4805.3  328.13  4825.3  328.23  4855.4  325.32  4905.6  325.24  4923.7  324.65
  4923.9  324.15  4927.4  324.15  4927.7  324.65  4955.8  325.79  5018.3  324.87
  5085.4  325.30  5175.8  328.00  5233.5  329.88  5241.9  329.80  5286.6  332.27
  5300.6  332.67  5317.3  332.36  5412.6  335.17  5457.1  336.49  5666.7  344.26
#Mann=5,-1,0
  4393.8    0.05       0  4923.7    0.05       0  4927.7    0.05       0
  5175.8    0.07       0  5412.6    0.05       0
Bank Sta=4923.7,4927.7
Exp/Cntr=0.3,0.1

Type RM Length L Ch R = 1,6328,457,457,457
BEGIN DESCRIPTION:
Stream0318 13.0
END DESCRIPTION:
XS GIS Cut Line= 3
      2516125.02     13665325.00      2515525.00     13665375.00
      2514925.02     13665974.98
#Sta/Elev= 30
  4412.2  339.47  4452.4  338.77  4482.5  336.86  4522.6  335.99  4582.8  332.75
  4612.9  332.18  4633.0  331.06  4683.2  330.11  4723.3  328.05  4753.4  327.23
  4773.5  327.35  4863.8  324.80  4903.9  324.42  4924.0  323.21  4944.1  322.88
  4951.6  322.43  4954.6  321.60  4954.8  321.10  4958.3  321.10  4958.6  321.60
  4984.6  321.92  5017.8  321.85  5049.7  323.15  5127.4  323.31  5198.1  324.62
  5240.6  326.34  5332.5  327.36  5339.6  327.94  5438.6  330.26  5862.8  345.16
#Mann=4,-1,0
  4412.2    0.05       0  4954.6    0.05       0  4958.6    0.05       0
  4984.6    0.07       0
Bank Sta=4954.6,4958.6
Exp/Cntr=0.3,0.1

Type RM Length L Ch R = 1,5871,458,458,458
BEGIN DESCRIPTION:
Stream0318 12.0
END DESCRIPTION:
XS GIS Cut Line= 3
      2515774.98     13665074.99      2515475.00     13664975.00
      2515175.01     13665224.99
#Sta/Elev= 30
  4679.6  327.06  4690.1  327.20  4711.2  325.99  4753.4  324.43  4785.0  323.91
  4806.1  323.94  4827.1  323.08  4890.4  321.43  4982.6  320.27  4985.3  320.23
  4993.2  317.73  4999.1  317.73  5001.0  316.94  5001.2  316.44  5004.7  316.44
  5005.0  316.94  5017.3  317.02  5023.8  317.51  5031.6  319.09  5038.1  319.50
  5066.7  319.89  5144.8  321.65  5194.3  323.52  5222.9  323.93  5237.3  324.65
  5251.6  324.48  5272.4  325.21  5321.9  326.07  5364.8  326.46  5386.3  327.02
#Mann=4,-1,0
  4679.6    0.05       0  4982.6    0.07       0  5001.0    0.05       0
  5005.0    0.07       0
Bank Sta=5001,5005
Exp/Cntr=0.3,0.1

Type RM Length L Ch R = 1,5413,472,472,472
BEGIN DESCRIPTION:
Stream0318 11.0
END DESCRIPTION:
XS GIS Cut Line= 3
      2515924.96     13664375.01      2515325.00     13664575.00
      2515024.98     13664875.02
#Sta/Elev= 30
  4367.9  332.38  4410.0  330.94  4420.6  329.90  4504.9  327.22  4610.3  322.50
  4663.0  320.88  4754.8  319.07  4821.1  317.74  4863.3  318.46  4905.4  318.47
  4916.0  318.23  4937.1  316.61  4995.7  316.27  4995.9  315.77  4999.4  315.77
  4999.7  316.27  5014.5  316.31  5043.1  318.49  5056.9  318.66  5071.0  317.56
  5113.4  318.83  5141.7  323.02  5155.9  323.29  5170.0  320.86  5177.1  320.79
  5198.3  322.12  5240.7  322.73  5283.2  324.29  5339.7  325.06  5424.6  327.59
#Mann=5,-1,0
  4367.9    0.05       0  4754.8    0.07       0  4995.7    0.05       0
  4999.7    0.07       0  5043.1    0.05       0
Bank Sta=4995.7,4999.7
Exp/Cntr=0.3,0.1

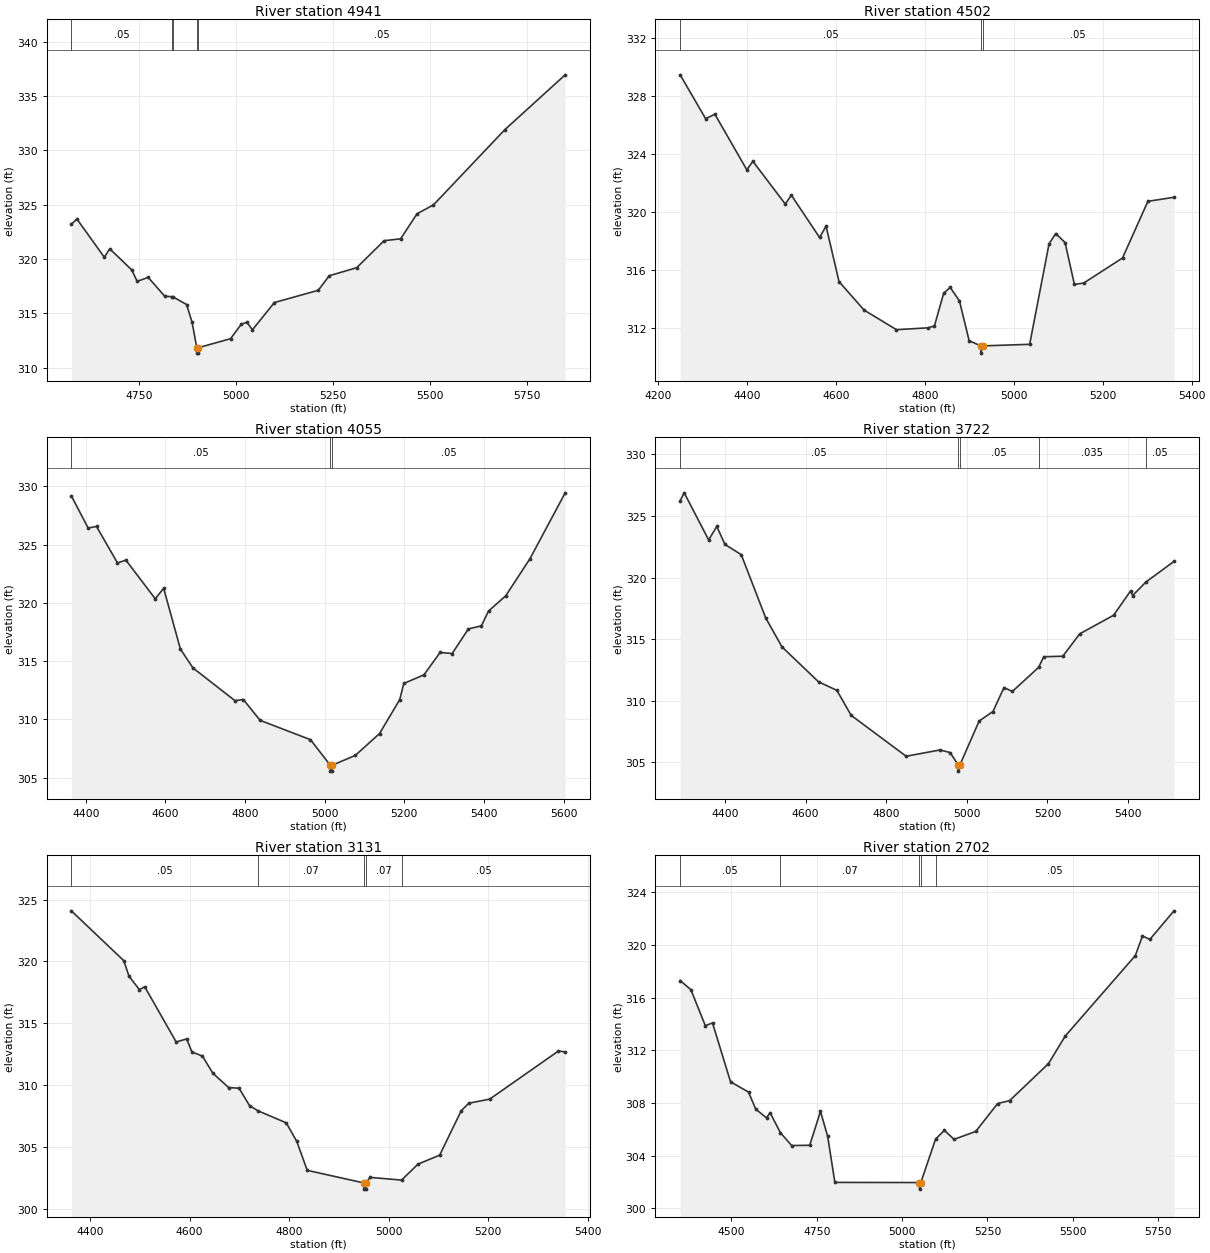
Type RM Length L Ch R = 1,4941,439,439,439
BEGIN DESCRIPTION:
Stream0318 10.0
END DESCRIPTION:
XS GIS Cut Line= 3
      2515525.03     13663874.97      2515225.00     13664175.00
      2514625.02     13664774.98
#Sta/Elev= 30
  4576.3  323.20  4590.5  323.69  4661.2  320.17  4675.3  320.94  4731.9  319.00
  4746.0  317.94  4774.3  318.31  4816.8  316.58  4836.8  316.52  4837.4  316.53
  4873.3  315.81  4887.5  314.17  4899.6  311.83  4899.9  311.33  4903.4  311.33
  4903.6  311.83  4986.5  312.66  5014.7  314.01  5028.9  314.16  5043.0  313.48
  5099.6  315.99  5212.7  317.12  5241.0  318.46  5311.7  319.20  5382.4  321.69
  5424.9  321.86  5467.3  324.17  5509.7  324.99  5693.6  331.92  5849.1  336.97
#Mann=5,-1,0
  4576.3    0.05       0  4836.8    0.07       0  4837.4    0.05       0
  4899.6    0.05       0  4903.6    0.05       0
Bank Sta=4899.6,4903.6
Exp/Cntr=0.3,0.1

Type RM Length L Ch R = 1,4502,447,447,447
BEGIN DESCRIPTION:
Stream0318 9.0
END DESCRIPTION:
XS GIS Cut Line= 3
      2515525.03     13663524.98      2514925.00     13663975.00
      2514724.99     13664275.01
#Sta/Elev= 30
  4249.6  329.48  4306.9  326.45  4327.8  326.75  4399.6  322.91  4413.2  323.50
  4486.1  320.54  4499.6  321.16  4563.2  318.23  4577.8  319.01  4606.9  315.18
  4663.2  313.21  4736.1  311.85  4806.9  311.98  4821.5  312.11  4842.3  314.37
  4856.9  314.78  4877.8  313.84  4899.6  311.09  4925.8  310.73  4926.0  310.23
  4929.8  310.73  5035.7  310.84  5079.3  317.79  5094.3  318.50  5115.3  317.88
  5136.3  314.98  5157.4  315.08  5244.5  316.81  5301.6  320.73  5360.2  321.01
#Mann=3,-1,0
  4249.6    0.05       0  4925.8    0.05       0  4929.8    0.05       0
Bank Sta=4925.8,4929.8
Exp/Cntr=0.3,0.1

Type RM Length L Ch R = 1,4055,333,333,333
BEGIN DESCRIPTION:
Stream0318 8.0
END DESCRIPTION:
XS GIS Cut Line= 3
      2515474.96     13663375.01      2514875.00     13663575.00
      2514274.99     13663675.00
#Sta/Elev= 30
  4363.5  329.19  4405.6  326.43  4426.7  326.56  4479.4  323.43  4500.5  323.67
  4574.3  320.35  4595.4  321.25  4637.5  316.03  4669.1  314.41  4774.6  311.60
  4795.6  311.70  4837.8  309.91  4964.3  308.25  5014.2  306.05  5014.4  305.55
  5017.9  305.55  5018.2  306.05  5077.0  306.90  5137.8  308.78  5188.5  311.69
  5198.7  313.08  5249.4  313.82  5289.9  315.74  5320.3  315.65  5360.9  317.76
  5393.8  318.03  5411.6  319.30  5454.7  320.60  5515.5  323.78  5604.2  329.45
#Mann=3,-1,0
  4363.5    0.05       0  5014.2    0.05       0  5018.2    0.05       0
Bank Sta=5014.2,5018.2
Exp/Cntr=0.3,0.1

Type RM Length L Ch R = 1,3722,591,591,591
BEGIN DESCRIPTION:
Stream0318 7.0
END DESCRIPTION:
XS GIS Cut Line= 3
      2515425.03     13663275.00      2514935.06     13663345.05
      2514225.00     13663175.00
#Sta/Elev= 30
  4288.8  326.24  4298.9  326.88  4359.5  323.06  4379.8  324.15  4400.0  322.69
  4440.4  321.86  4501.0  316.73  4541.4  314.37  4632.3  311.53  4677.6  310.84
  4713.1  308.81  4849.5  305.49  4933.6  306.00  4958.6  305.79  4978.8  304.78
  4979.0  304.28  4982.8  304.78  5030.6  308.35  5064.8  309.12  5092.3  311.07
  5112.9  310.75  5178.0  312.70  5190.9  313.57  5238.1  313.61  5280.1  315.43
  5364.2  316.94  5406.2  318.91  5411.4  318.54  5444.1  319.63  5513.9  321.31
#Mann=5,-1,0
  4288.8    0.05       0  4978.8    0.05       0  4982.8    0.05       0
  5178.0   0.035       0  5444.1    0.05       0
Bank Sta=4978.8,4982.8
Exp/Cntr=0.3,0.1

Type RM Length L Ch R = 1,3131,429,429,429
BEGIN DESCRIPTION:
Stream0318 6.0
END DESCRIPTION:
XS GIS Cut Line= 3
      2515374.96     13663124.99      2514775.00     13662925.00
      2514474.97     13663125.02
#Sta/Elev= 30
  4362.1  324.09  4467.5  320.06  4478.0  318.80  4499.1  317.71  4509.6  317.95
  4572.9  313.48  4594.0  313.73  4604.5  312.67  4625.6  312.35  4646.7  310.95
  4678.3  309.80  4699.4  309.74  4720.4  308.33  4737.4  307.92  4794.2  306.94
  4815.3  305.45  4836.4  303.10  4950.3  302.08  4950.6  301.58  4954.1  301.58
  4954.3  302.08  4962.9  302.53  5026.0  302.31  5059.1  303.60  5102.7  304.33
  5146.2  307.93  5161.3  308.53  5203.3  308.86  5341.5  312.75  5355.1  312.68
#Mann=5,-1,0
  4362.1    0.05       0  4737.4    0.07       0  4950.3    0.05       0
  4954.3    0.07       0  5026.0    0.05       0
Bank Sta=4950.3,4954.3
Exp/Cntr=0.3,0.1

Type RM Length L Ch R = 1,2702,419,419,419
BEGIN DESCRIPTION:
Stream0318 5.0
END DESCRIPTION:
XS GIS Cut Line= 3
      2515274.98     13662774.99      2514675.00     13662575.00
      2514074.98     13663125.02
#Sta/Elev= 30
  4349.9  317.31  4381.5  316.61  4423.7  313.88  4444.7  314.09  4497.5  309.62
  4550.2  308.84  4571.2  307.55  4602.9  306.88  4613.4  307.27  4643.7  305.75
  4676.6  304.78  4729.4  304.80  4761.0  307.37  4782.1  305.47  4803.1  301.98
  5050.9  301.97  5051.2  301.47  5054.9  301.97  5098.1  305.27  5123.9  305.93
  5152.2  305.25  5215.7  305.85  5279.9  307.97  5315.0  308.19  5428.5  310.99
  5477.8  313.09  5683.1  319.20  5704.1  320.69  5725.7  320.43  5796.3  322.60
#Mann=5,-1,0
  4349.9    0.05       0  4643.7    0.07       0  5050.9    0.05       0
  5054.9    0.07       0  5098.1    0.05       0
Bank Sta=5050.9,5054.9
Exp/Cntr=0.3,0.1

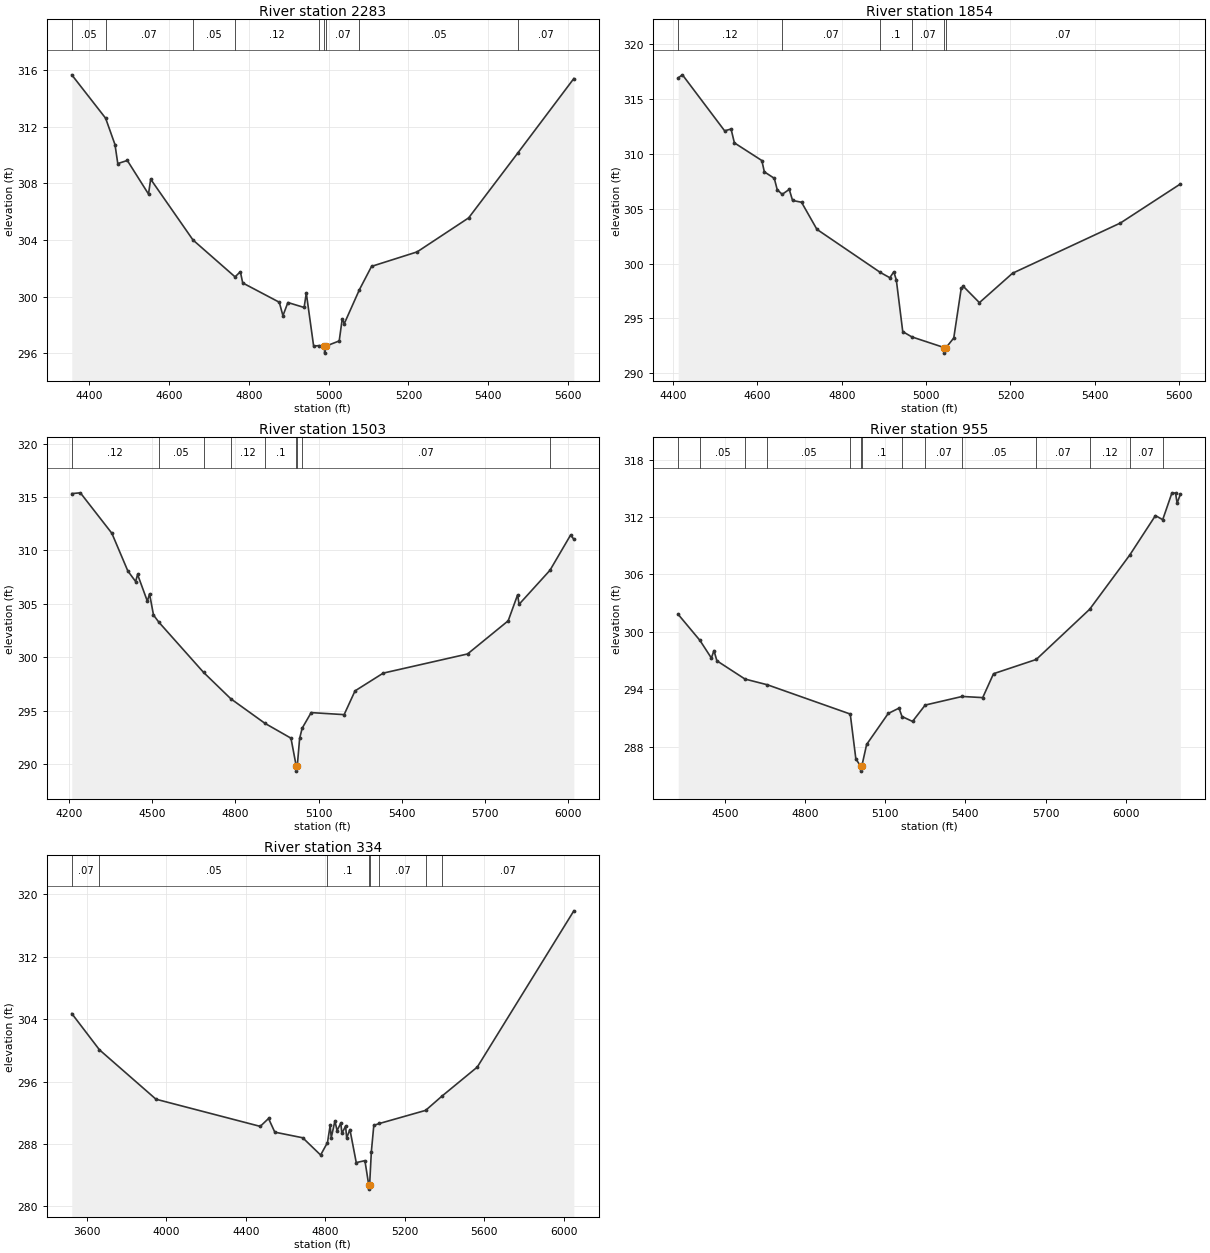
Type RM Length L Ch R = 1,2283,429,429,429
BEGIN DESCRIPTION:
Stream0318 4.0
END DESCRIPTION:
XS GIS Cut Line= 3
      2515274.96     13662474.98      2514675.00     13662225.00
      2514075.03     13662125.01
#Sta/Elev= 30
  4356.2  315.65  4441.0  312.59  4464.5  310.73  4471.5  309.39  4495.4  309.61
  4548.5  307.24  4553.9  308.29  4660.0  304.00  4765.4  301.40  4778.7  301.76
  4784.6  300.97  4876.2  299.61  4885.4  298.66  4897.8  299.59  4938.5  299.24
  4943.9  300.26  4962.3  296.52  4976.1  296.55  4989.5  296.52  4989.8  296.02
  4993.5  296.52  5026.4  296.88  5034.0  298.44  5039.1  298.10  5077.1  300.50
  5107.5  302.14  5221.6  303.16  5350.8  305.56  5474.3  310.15  5614.4  315.39
#Mann=9,-1,0
  4356.2    0.05       0  4441.0    0.07       0  4660.0    0.05       0
  4765.4    0.12       0  4976.1    0.07       0  4989.5    0.05       0
  4993.5    0.07       0  5077.1    0.05       0  5474.3    0.07       0
Bank Sta=4989.5,4993.5
Exp/Cntr=0.3,0.1

Type RM Length L Ch R = 1,1854,351,351,351
BEGIN DESCRIPTION:
Stream0318 3.0
END DESCRIPTION:
XS GIS Cut Line= 3
      2515367.70     13662235.80      2514875.00     13661925.00
      2514275.01     13662025.00
#Sta/Elev= 30
  4412.2  316.93  4422.2  317.20  4522.2  312.10  4537.5  312.26  4545.4  311.00
  4610.5  309.39  4616.4  308.36  4640.0  307.77  4647.0  306.73  4658.8  306.31
  4675.5  306.76  4683.4  305.75  4704.6  305.59  4741.1  303.12  4891.6  299.19
  4914.1  298.71  4923.5  299.25  4929.4  298.52  4944.7  293.80  4966.2  293.32
  5043.4  292.34  5043.7  291.84  5047.4  292.34  5065.7  293.22  5083.4  297.74
  5088.5  297.92  5126.5  296.44  5205.1  299.12  5461.1  303.70  5603.0  307.25
#Mann=6,-1,0
  4412.2    0.12       0  4658.8    0.07       0  4891.6     0.1       0
  4966.2    0.07       0  5043.4    0.05       0  5047.4    0.07       0
Bank Sta=5043.4,5047.4
Exp/Cntr=0.3,0.1

Type RM Length L Ch R = 1,1503,548,548,548
BEGIN DESCRIPTION:
Stream0318 2.0
END DESCRIPTION:
XS GIS Cut Line= 3
      2515470.01     13662133.56      2515060.93     13661630.08
      2513943.82     13661315.40
#Sta/Elev= 30
  4210.4  315.32  4241.4  315.39  4354.9  311.61  4412.4  308.09  4440.5  307.10
  4447.6  307.76  4482.8  305.26  4490.7  305.95  4504.9  303.97  4523.9  303.31
  4685.3  298.61  4783.6  296.14  4906.4  293.85  5000.3  292.46  5019.1  289.88
  5019.4  289.38  5023.1  289.88  5031.5  292.43  5040.6  293.39  5073.1  294.85
  5191.9  294.66  5231.2  296.88  5332.8  298.54  5636.6  300.33  5783.1  303.43
  5817.1  305.86  5822.3  304.97  5933.6  308.15  6008.1  311.45  6019.7  311.05
#Mann=9,-1,0
  4210.4    0.12       0  4523.9    0.05       0  4685.3    0.07       0
  4783.6    0.12       0  4906.4     0.1       0  5019.1    0.05       0
  5023.1     0.1       0  5040.6    0.07       0  5933.6    0.12       0
Bank Sta=5019.1,5023.1
Exp/Cntr=0.3,0.1

Type RM Length L Ch R = 1,955,621,621,621
BEGIN DESCRIPTION:
Stream0318 1.0
END DESCRIPTION:
XS GIS Cut Line= 3
      2515425.00     13661825.00      2515281.20     13661276.07
      2513983.21     13661087.27
#Sta/Elev= 30
  4325.4  301.82  4406.7  299.10  4449.4  297.26  4459.1  298.04  4470.1  296.97
  4575.3  295.06  4659.2  294.46  4969.2  291.40  4990.1  286.72  5008.3  285.93
  5008.5  285.43  5012.3  285.93  5030.5  288.22  5111.3  291.46  5151.7  292.02
  5162.9  291.14  5202.3  290.63  5249.7  292.34  5388.1  293.24  5465.0  293.12
  5505.4  295.62  5665.3  297.11  5865.2  302.36  6015.2  308.03  6111.4  312.16
  6138.6  311.73  6172.4  314.47  6186.5  314.54  6192.6  313.46  6204.5  314.38
#Mann=14,-1,0
  4325.4    0.07       0  4406.7    0.05       0  4575.3    0.07       0
  4659.2    0.05       0  4969.2     0.1       0  5008.3    0.05       0
  5012.3     0.1       0  5162.9    0.12       0  5249.7    0.07       0
  5388.1    0.05       0  5665.3    0.07       0  5865.2    0.12       0
  6015.2    0.07       0  6138.6    0.12       0
Bank Sta=5008.3,5012.3
Exp/Cntr=0.3,0.1

Type RM Length L Ch R = 1,334,0,0,0
BEGIN DESCRIPTION:
XS6448
END DESCRIPTION:
XS GIS Cut Line= 4
      2515643.07     13661929.01      2515312.67     13660890.60
      2514769.86     13660670.33      2513920.19     13660733.26
#Sta/Elev= 30
  3523.3  304.72  3662.7  300.07  3947.3  293.74  4472.0  290.26  4513.9  291.27
  4545.4  289.52  4686.0  288.80  4776.0  286.59  4810.6  288.19  4824.1  290.39
  4829.5  288.80  4847.9  290.95  4859.0  289.73  4877.7  290.68  4883.1  289.37
  4901.8  290.29  4907.2  288.78  4923.5  289.86  4955.4  285.62  4999.0  285.87
  5018.5  282.72  5018.8  282.22  5022.6  282.72  5031.4  287.01  5043.8  290.39
  5072.1  290.63  5304.6  292.31  5386.5  294.13  5564.7  297.86  6050.8  317.88
#Mann=8,-1,0
  3523.3    0.07       0  3662.7    0.05       0  4810.6     0.1       0
  5018.5    0.05       0  5022.6     0.1       0  5072.1    0.07       0
  5304.6    0.05       0  5386.5    0.07       0
Bank Sta=5018.5,5022.6
Exp/Cntr=0.3,0.1

Chan Stop Cuts=-1