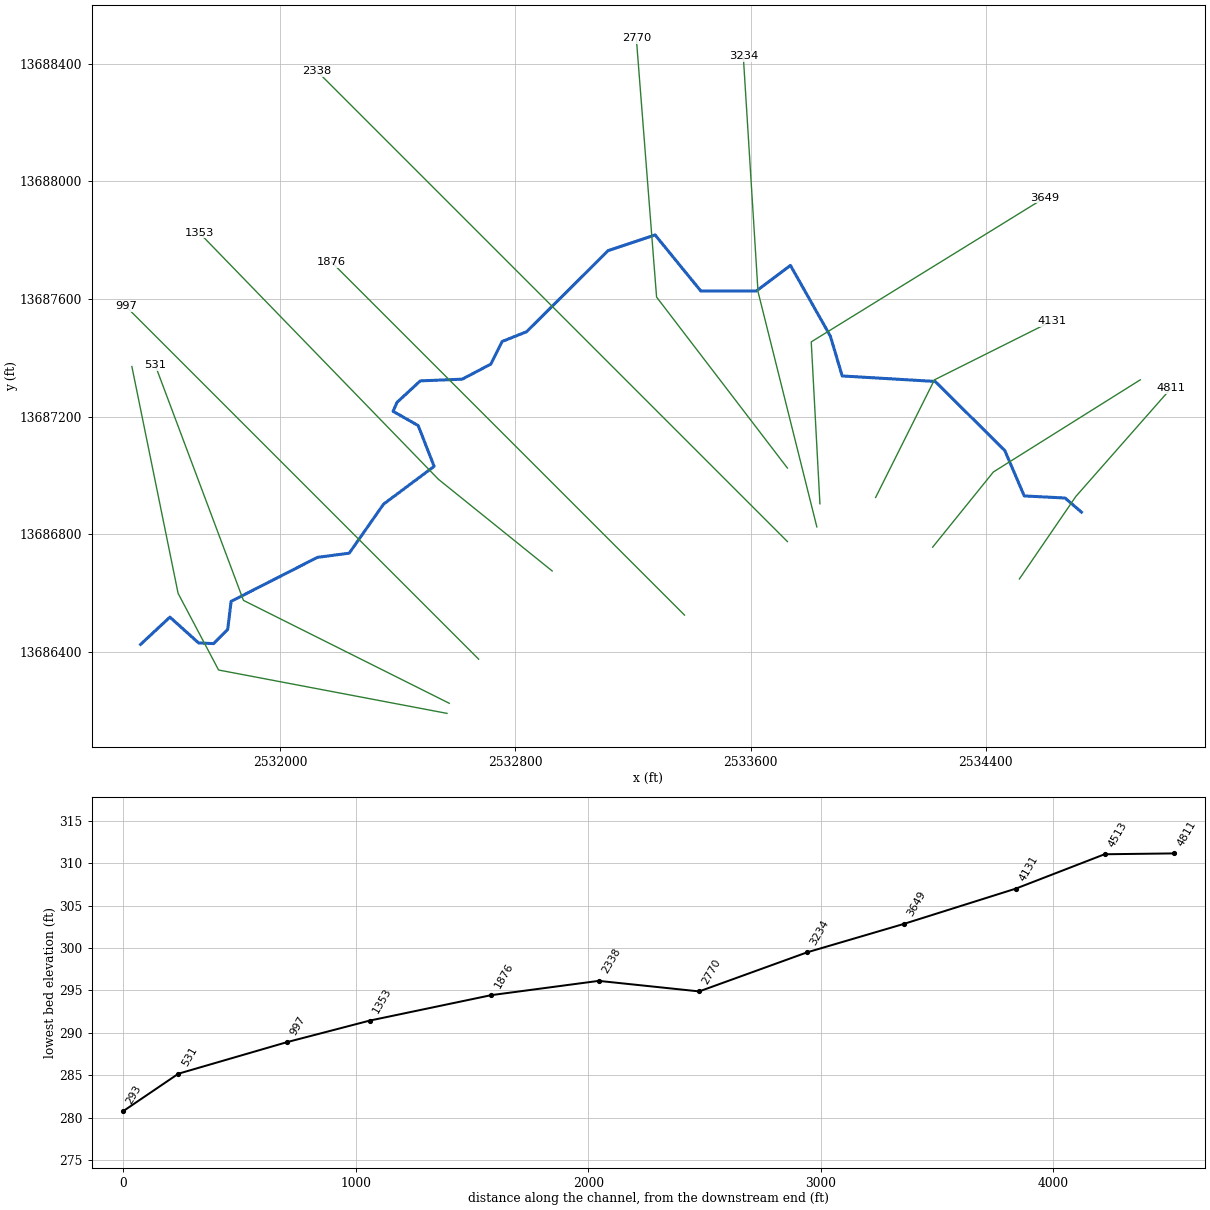
--- Stream0325.prj (project) ---

Proj Title=Stream0325 Base Level Engineering
Current Plan=p01
Default Exp/Contr=0.3,0.1
English Units
Geom File=g01
Flow File=f01
Plan File=p01
BEGIN DESCRIPTION:
Stream0325
END DESCRIPTION:

--- Stream0325.p01 (plan) ---

Plan Title=Multiple Run
Short Identifier=Multiple
Geom File=g01
Flow File=f01
Subcritical Flow
K Sum by GR= 0
Std Step Tol= 0.01
Critical Tol= 0.01
Num of Std Step Trials= 20
Max Error Tol= 0.3
Flow Tol Ratio= 0.001
Split Flow NTrial= 30
Split Flow Tol= 0.02
Split Flow Ratio= 0.02
Log Output Level= 0
Friction Slope Method= 1
Unsteady Friction Slope Method= 2
Unsteady Bridges Friction Slope Method= 1
Parabolic Critical Depth
Global Vel Dist=  1 , 1 , 1
Global Log Level= 0
CheckData=True
Encroach Param= -1, 0, 0, 0
BEGIN DESCRIPTION:
Multiple Run
END DESCRIPTION:

--- Stream0325.f01 (steady flow) ---

Flow Title=Multiple
Number of Profiles=7
Profile Names=10-year,25-year,50-year,1pct_min,100-year,1pct_plu,500-year
River Rch & RM= Stream0325,Reach-1,4811
     994    1647    2255    1497    2987    5959    5180
River Rch & RM= Stream0325,Reach-1,3234
    1437    2430    3371    2263    4515    9008    8019
River Rch & RM= Stream0325,Reach-1,531
    1449    2448    3394    2277    4543    9065    8060
Boundary for River Rch & Prof#=Stream0325,Reach-1,1
Up Type=0
Dn Type=3
Dn Slope=0.005
Boundary for River Rch & Prof#=Stream0325,Reach-1,2
Up Type=0
Dn Type=3
Dn Slope=0.005
Boundary for River Rch & Prof#=Stream0325,Reach-1,3
Up Type=0
Dn Type=3
Dn Slope=0.005
Boundary for River Rch & Prof#=Stream0325,Reach-1,4
Up Type=0
Dn Type=3
Dn Slope=0.005
Boundary for River Rch & Prof#=Stream0325,Reach-1,5
Up Type=0
Dn Type=3
Dn Slope=0.005
Boundary for River Rch & Prof#=Stream0325,Reach-1,6
Up Type=0
Dn Type=3
Dn Slope=0.005
Boundary for River Rch & Prof#=Stream0325,Reach-1,7
Up Type=0
Dn Type=3
Dn Slope=0.005

--- Stream0325.g01 (geometry) ---

Geom Title=Existing Conditions

River Reach=Stream0325,Reach-1
Reach XY= 30
      2534725.00     13686875.00      2534669.20     13686923.09
      2534530.41     13686930.17      2534464.23     13687084.68
      2534227.45     13687319.54      2533911.27     13687338.20
      2533871.17     13687473.41      2533735.32     13687714.18
      2533619.15     13687627.07      2533430.67     13687626.98
      2533275.11     13687817.69      2533115.21     13687764.48
      2532838.20     13687488.64      2532754.57     13687455.27
      2532716.51     13687378.53      2532619.09     13687327.24
      2532476.44     13687321.46      2532397.34     13687248.33
      2532383.88     13687218.08      2532469.35     13687169.39
      2532523.46     13687030.86      2532351.27     13686901.88
      2532234.81     13686735.51      2532126.59     13686721.17
      2531833.16     13686571.62      2531821.44     13686476.29
      2531773.59     13686428.00      2531722.74     13686430.08
      2531625.00     13686518.02      2531525.00     13686425.00

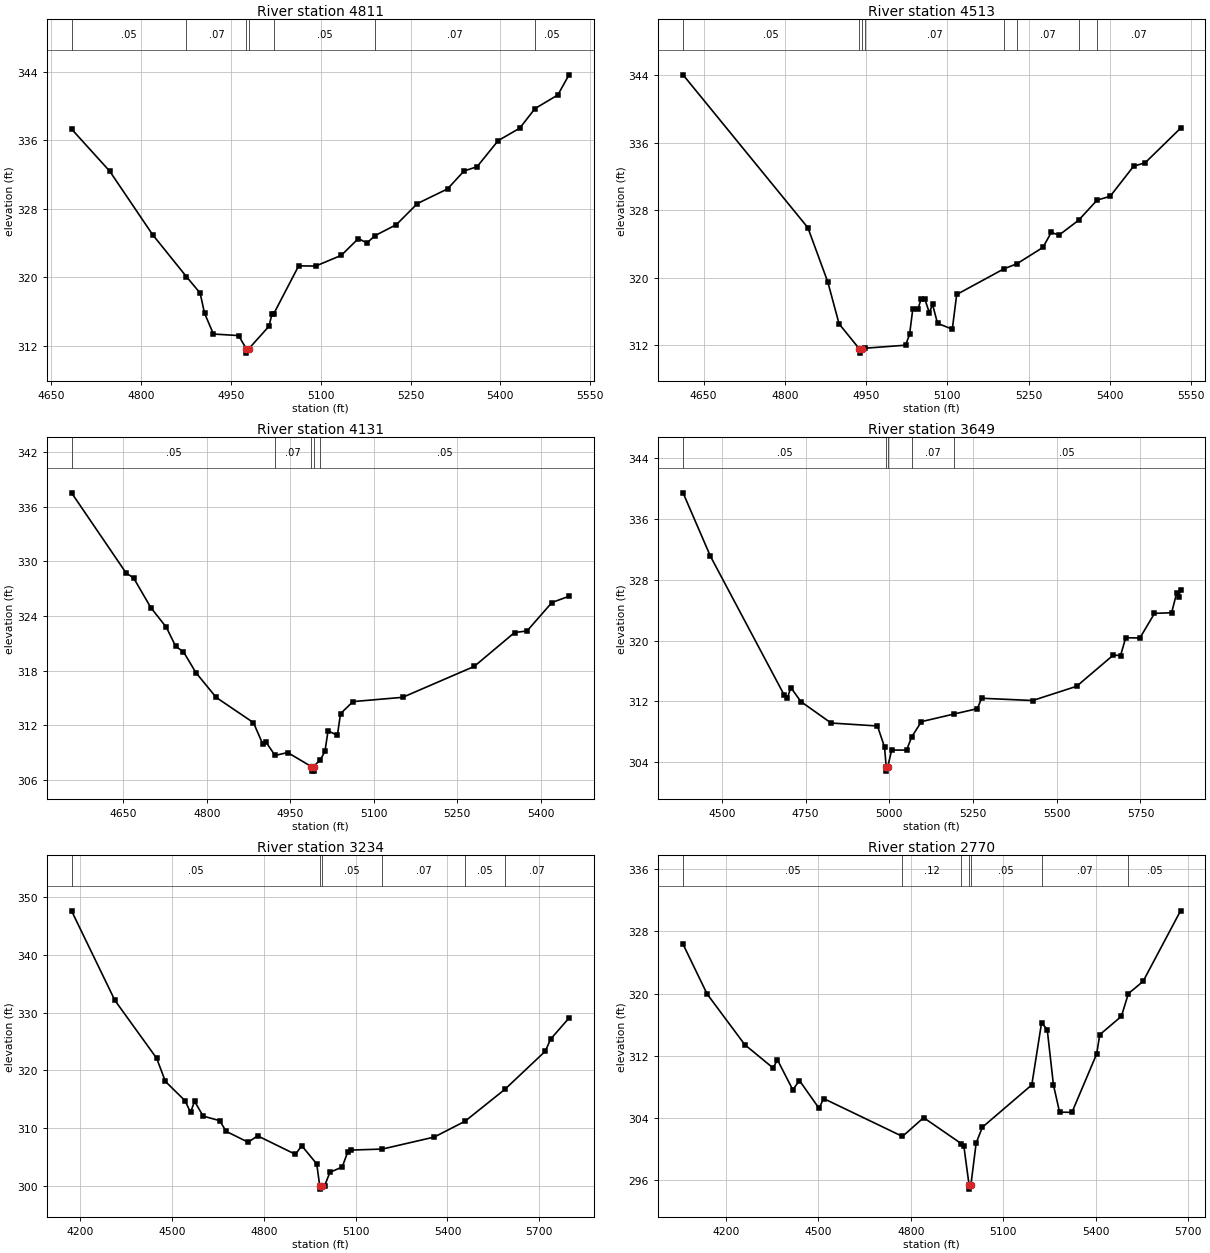
Type RM Length L Ch R = 1,4811,298,298,298
BEGIN DESCRIPTION:
XS6477
END DESCRIPTION:
XS GIS Cut Line= 3
      2534513.91     13686647.84      2534705.65     13686928.08
      2535030.04     13687296.71
#Sta/Elev= 30
  4684.0  337.31  4747.6  332.40  4819.3  324.98  4875.7  320.08  4898.7  318.15
  4906.0  315.81  4920.9  313.37  4962.9  313.19  4975.8  311.64  4976.0  311.14
  4979.8  311.64  5013.7  314.28  5018.7  315.75  5021.7  315.75  5063.2  321.33
  5091.7  321.31  5134.4  322.56  5162.9  324.52  5177.1  324.00  5190.7  324.86
  5226.4  326.15  5261.5  328.61  5311.8  330.32  5339.3  332.41  5361.1  332.91
  5396.3  335.96  5432.3  337.41  5457.8  339.70  5495.9  341.29  5514.6  343.64
#Mann=7,-1,0
  4684.0    0.05       0  4875.7    0.07       0  4975.8    0.05       0
  4979.8    0.07       0  5021.7    0.05       0  5190.7    0.07       0
  5457.8    0.05       0
Bank Sta=4975.8,4979.8
Exp/Cntr=0.3,0.1

Type RM Length L Ch R = 1,4513,382,382,382
BEGIN DESCRIPTION:
Stream0325 10.0
END DESCRIPTION:
XS GIS Cut Line= 3
      2534218.99     13686756.04      2534425.45     13687011.66
      2534925.02     13687325.01
#Sta/Elev= 30
  4612.1  344.03  4842.5  325.91  4879.3  319.47  4900.1  314.51  4937.6  311.54
  4937.9  311.04  4941.6  311.54  4947.7  311.62  5022.8  311.98  5030.2  313.25
  5036.1  316.23  5045.5  316.23  5051.4  317.43  5058.2  317.50  5066.7  315.82
  5072.6  316.83  5081.8  314.57  5109.1  313.88  5117.2  317.99  5204.9  321.05
  5228.0  321.62  5276.4  323.57  5291.8  325.35  5306.1  325.03  5342.2  326.79
  5376.4  329.18  5400.5  329.63  5443.8  333.20  5465.0  333.60  5530.4  337.70
#Mann=8,-1,0
  4612.1    0.05       0  4937.6    0.05       0  4941.6    0.05       0
  4947.7    0.07       0  5204.9    0.05       0  5228.0    0.07       0
  5342.2    0.05       0  5376.4    0.07       0
Bank Sta=4937.6,4941.6
Exp/Cntr=0.3,0.1

Type RM Length L Ch R = 1,4131,482,482,482
BEGIN DESCRIPTION:
Stream0325 9.0
END DESCRIPTION:
XS GIS Cut Line= 3
      2534024.98     13686924.96      2534225.00     13687325.00
      2534625.03     13687525.01
#Sta/Elev= 30
  4556.6  337.53  4654.5  328.75  4668.4  328.17  4699.2  324.93  4727.1  322.77
  4743.9  320.68  4757.9  320.08  4780.2  317.80  4816.6  315.08  4883.7  312.31
  4900.4  309.96  4906.0  310.19  4922.6  308.71  4945.2  309.03  4987.8  307.49
  4988.1  306.99  4991.7  306.99  4991.9  307.49  5004.1  308.26  5012.2  309.15
  5017.8  311.41  5034.6  310.92  5040.2  313.29  5062.6  314.62  5152.0  315.09
  5280.6  318.48  5353.2  322.20  5375.6  322.37  5420.3  325.49  5451.1  326.18
#Mann=5,-1,0
  4556.6    0.05       0  4922.6    0.07       0  4987.8    0.05       0
  4991.9    0.07       0  5004.1    0.05       0
Bank Sta=4987.8,4991.9
Exp/Cntr=0.3,0.1

Type RM Length L Ch R = 1,3649,415,415,415
BEGIN DESCRIPTION:
Stream0325 8.0
END DESCRIPTION:
XS GIS Cut Line= 3
      2533835.54     13686903.54      2533806.04     13687454.09
      2534601.21     13687944.93
#Sta/Elev= 30
  4383.8  339.45  4465.4  331.12  4685.7  312.86  4695.7  312.51  4705.7  313.82
  4735.8  311.98  4825.9  309.16  4964.4  308.77  4985.6  305.99  4990.6  303.33
  4990.9  302.83  4994.7  303.33  5006.9  305.60  5051.4  305.60  5066.7  307.33
  5095.6  309.34  5191.6  310.33  5263.0  311.05  5275.3  312.42  5427.8  312.12
  5559.1  313.99  5669.1  318.11  5690.4  318.03  5705.8  320.38  5748.3  320.35
  5791.8  323.59  5842.9  323.67  5858.3  326.31  5864.2  325.80  5869.6  326.67
#Mann=5,-1,0
  4383.8    0.05       0  4990.6    0.05       0  4994.7    0.05       0
  5066.7    0.07       0  5191.6    0.05       0
Bank Sta=4990.6,4994.7
Exp/Cntr=0.3,0.1

Type RM Length L Ch R = 1,3234,464,464,464
BEGIN DESCRIPTION:
Stream0325 7.0
END DESCRIPTION:
XS GIS Cut Line= 3
      2533825.00     13686824.98      2533625.00     13687625.00
      2533575.00     13688425.00
#Sta/Elev= 30
  4171.2  347.57  4312.9  332.10  4449.5  322.09  4477.9  318.10  4542.3  314.76
  4560.3  312.74  4573.2  314.66  4601.6  312.10  4655.7  311.32  4676.3  309.48
  4748.5  307.59  4779.4  308.70  4903.1  305.50  4923.7  306.99  4972.6  303.85
  4982.7  299.99  4983.1  299.49  4988.4  299.99  4998.3  300.07  5015.9  302.39
  5056.0  303.32  5073.5  305.83  5086.0  306.24  5187.0  306.41  5356.5  308.48
  5457.0  311.20  5587.7  316.73  5719.7  323.31  5737.3  325.41  5797.4  329.05
#Mann=6,-1,0
  4171.2    0.05       0  4982.7    0.05       0  4988.4    0.05       0
  5187.0    0.07       0  5457.0    0.05       0  5587.7    0.07       0
Bank Sta=4982.7,4988.4
Exp/Cntr=0.3,0.1

Type RM Length L Ch R = 1,2770,432,432,432
BEGIN DESCRIPTION:
Stream0325 6.0
END DESCRIPTION:
XS GIS Cut Line= 3
      2533725.01     13687024.98      2533280.04     13687606.48
      2533211.22     13688486.38
#Sta/Elev= 30
  4060.9  326.35  4138.9  319.96  4261.4  313.44  4352.9  310.46  4367.4  311.49
  4417.2  307.64  4438.7  308.84  4502.5  305.26  4517.0  306.53  4773.1  301.66
  4841.8  304.07  4964.5  300.72  4972.2  300.47  4989.4  295.39  4989.8  294.89
  4995.1  295.39  5012.3  300.82  5032.4  302.84  5192.9  308.28  5224.6  316.26
  5243.0  315.39  5263.1  308.29  5283.1  304.78  5323.2  304.75  5403.5  312.26
  5413.5  314.73  5483.7  317.09  5506.4  320.01  5554.0  321.57  5675.7  330.64
#Mann=7,-1,0
  4060.9    0.05       0  4773.1    0.12       0  4964.5    0.05       0
  4989.4    0.05       0  4995.1    0.05       0  5224.6    0.07       0
  5506.4    0.05       0
Bank Sta=4989.4,4995.1
Exp/Cntr=0.3,0.1

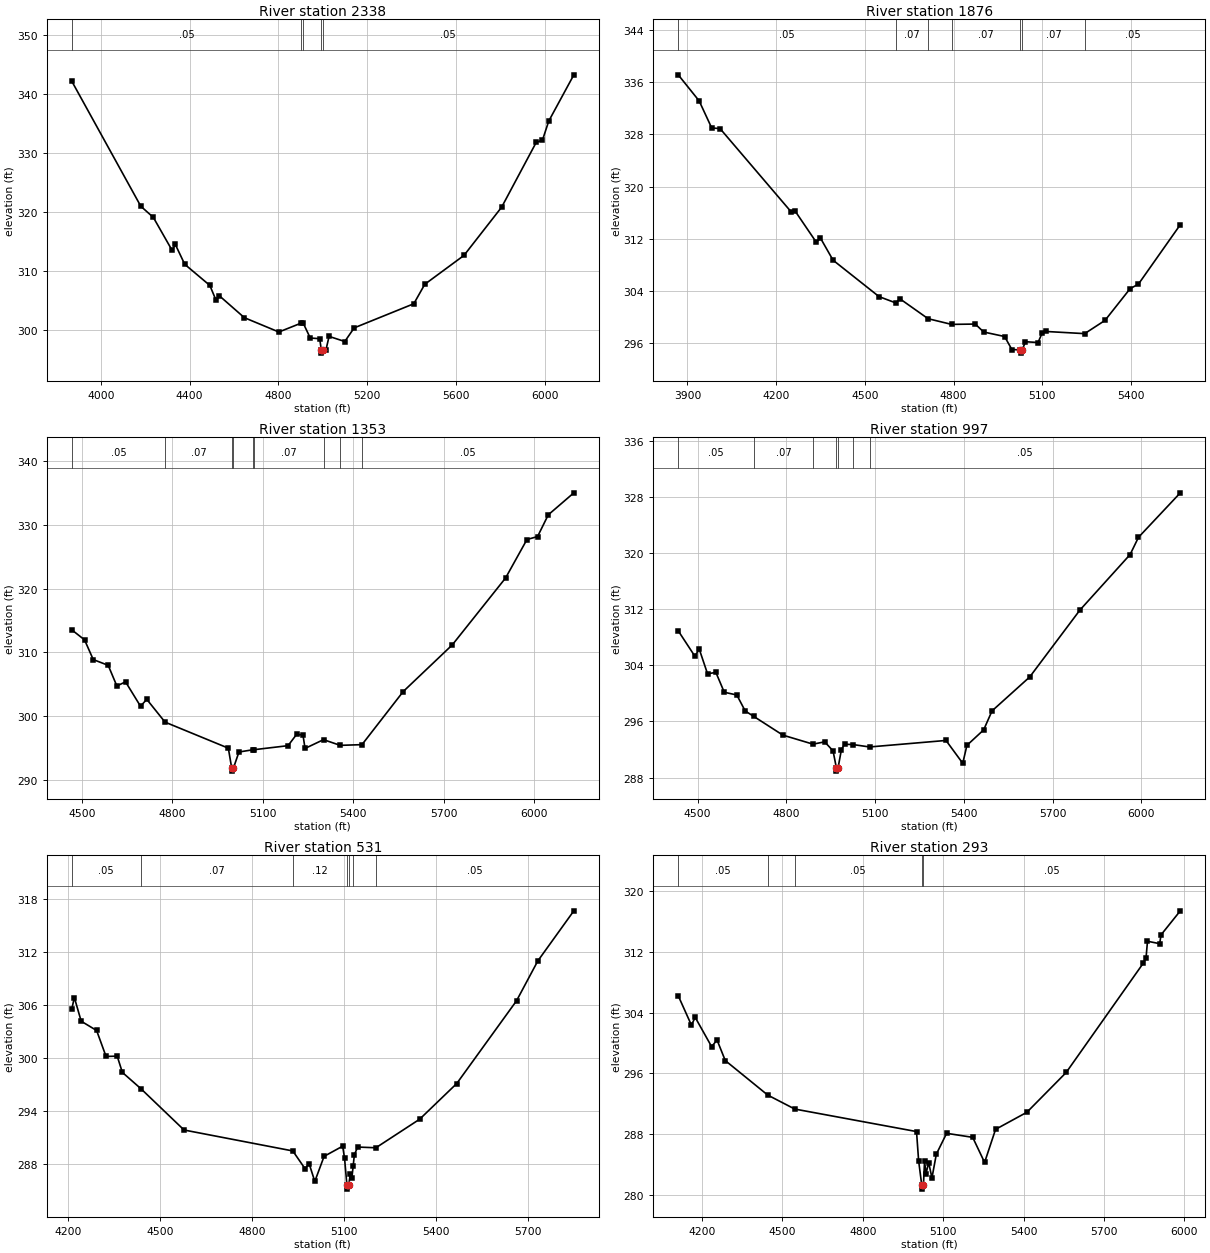
Type RM Length L Ch R = 1,2338,462,462,462
BEGIN DESCRIPTION:
Stream0325 5.0
END DESCRIPTION:
XS GIS Cut Line= 3
      2533724.97     13686775.03      2532925.00     13687575.00
      2532125.00     13688375.00
#Sta/Elev= 30
  3868.7  342.23  4179.8  321.03  4236.3  319.14  4321.2  313.53  4335.3  314.56
  4377.8  311.19  4490.9  307.61  4519.2  305.06  4533.3  305.87  4646.5  302.14
  4802.0  299.71  4901.3  301.20  4910.6  301.31  4943.5  298.69  4985.9  298.58
  4993.6  296.63  4994.1  296.13  4999.4  296.63  5014.2  296.67  5028.3  298.97
  5099.0  298.10  5141.4  300.41  5410.1  304.50  5459.6  307.80  5636.4  312.70
  5806.1  320.88  5961.7  331.85  5990.0  332.24  6018.3  335.47  6131.4  343.31
#Mann=5,-1,0
  3868.7    0.05       0  4901.3    0.12       0  4910.6    0.05       0
  4993.6    0.05       0  4999.4    0.05       0
Bank Sta=4993.6,4999.4
Exp/Cntr=0.3,0.1

Type RM Length L Ch R = 1,1876,523,523,523
BEGIN DESCRIPTION:
Stream0325 4.0
END DESCRIPTION:
XS GIS Cut Line= 3
      2533375.00     13686525.00      2532575.00     13687325.00
      2532174.97     13687725.03
#Sta/Elev= 30
  3869.1  337.15  3939.8  333.15  3982.2  329.00  4010.5  328.90  4250.9  316.12
  4265.1  316.19  4335.8  311.46  4349.9  312.10  4392.4  308.71  4547.9  303.12
  4604.1  302.16  4618.6  302.78  4713.7  299.73  4793.0  298.86  4873.2  298.91
  4901.5  297.69  4972.2  297.00  4996.9  295.00  5025.8  294.95  5026.3  294.45
  5031.7  294.95  5042.9  296.20  5085.3  296.08  5099.5  297.57  5113.6  297.77
  5242.9  297.44  5311.6  299.47  5396.5  304.34  5424.7  305.04  5566.2  314.16
#Mann=7,-1,0
  3869.1    0.05       0  4604.1    0.07       0  4713.7    0.05       0
  4793.0    0.07       0  5025.8    0.05       0  5031.7    0.07       0
  5242.9    0.05       0
Bank Sta=5025.8,5031.7
Exp/Cntr=0.3,0.1

Type RM Length L Ch R = 1,1353,356,356,356
BEGIN DESCRIPTION:
Stream0325 3.0
END DESCRIPTION:
XS GIS Cut Line= 3
      2532924.99     13686675.01      2532537.74     13686987.08
      2531724.98     13687825.02
#Sta/Elev= 30
  4467.1  313.54  4509.5  311.97  4538.3  308.89  4587.9  307.99  4616.6  304.76
  4645.4  305.41  4695.0  301.60  4715.8  302.67  4776.4  299.11  4986.2  295.04
  4997.3  291.95  4997.8  291.45  5003.3  291.95  5021.4  294.44  5069.0  294.80
  5071.4  294.80  5184.2  295.43  5212.3  297.18  5233.6  297.11  5240.6  295.00
  5301.8  296.37  5357.1  295.48  5429.3  295.59  5566.0  303.89  5728.6  311.18
  5905.5  321.65  5976.3  327.66  6011.5  328.12  6047.0  331.52  6131.8  334.96
#Mann=9,-1,0
  4467.1    0.05       0  4776.4    0.07       0  4997.3    0.05       0
  5003.3    0.07       0  5069.0    0.12       0  5071.4    0.07       0
  5301.8    0.05       0  5357.1    0.07       0  5429.3    0.05       0
Bank Sta=4997.3,5003.3
Exp/Cntr=0.3,0.1

Type RM Length L Ch R = 1,997,466,466,466
BEGIN DESCRIPTION:
Stream0325 2.0
END DESCRIPTION:
XS GIS Cut Line= 3
      2532675.01     13686374.99      2532275.00     13686775.00
      2531474.98     13687575.02
#Sta/Elev= 30
  4434.8  308.94  4491.4  305.29  4505.5  306.37  4533.8  302.81  4562.1  303.00
  4590.4  300.17  4632.8  299.78  4661.1  297.50  4689.8  296.73  4788.4  294.05
  4890.4  292.76  4929.8  293.09  4958.1  291.80  4969.2  289.41  4969.7  288.91
  4975.2  289.41  4986.4  291.99  4997.0  292.75  5025.8  292.70  5081.6  292.36
  5339.9  293.29  5396.5  290.03  5410.6  292.59  5467.2  294.80  5495.5  297.51
  5622.8  302.35  5792.5  311.90  5962.2  319.83  5990.5  322.29  6131.9  328.64
#Mann=7,-1,0
  4434.8    0.05       0  4689.8    0.07       0  4890.4    0.05       0
  4969.2    0.05       0  4975.2    0.05       0  5025.8    0.12       0
  5081.6    0.05       0
Bank Sta=4969.2,4975.2
Exp/Cntr=0.3,0.1

Type RM Length L Ch R = 1,531,238,238,238
BEGIN DESCRIPTION:
Stream0325 1.0
END DESCRIPTION:
XS GIS Cut Line= 3
      2532574.98     13686225.01      2531875.00     13686575.00
      2531575.00     13687375.00
#Sta/Elev= 30
  4212.5  305.57  4220.9  306.88  4243.2  304.20  4293.5  303.15  4324.3  300.21
  4360.6  300.25  4377.4  298.41  4437.7  296.57  4578.6  291.89  4933.2  289.52
  4972.7  287.53  4986.7  288.05  5004.9  286.07  5035.2  288.91  5095.7  290.06
  5101.9  288.70  5109.5  285.70  5110.0  285.20  5115.6  285.70  5120.6  286.89
  5125.9  286.51  5130.1  287.86  5133.9  289.09  5144.6  289.96  5204.1  289.88
  5346.7  293.11  5467.7  297.15  5662.6  306.51  5732.0  311.02  5849.5  316.69
#Mann=7,-1,0
  4212.5    0.05       0  4437.7    0.07       0  4933.2    0.12       0
  5109.5    0.05       0  5115.6    0.12       0  5130.1    0.12       0
  5204.1    0.05       0
Bank Sta=5109.5,5115.6
Exp/Cntr=0.3,0.1

Type RM Length L Ch R = 1,293,0,0,0
BEGIN DESCRIPTION:
XS6476
END DESCRIPTION:
XS GIS Cut Line= 4
      2532567.28     13686190.69      2531790.52     13686338.18
      2531652.87     13686598.72      2531495.62     13687370.25
#Sta/Elev= 30
  4111.7  306.21  4160.7  302.36  4175.1  303.36  4236.2  299.52  4256.5  300.39
  4287.1  297.69  4445.5  293.15  4546.4  291.31  5000.5  288.35  5008.3  284.52
  5020.1  281.28  5020.6  280.78  5026.3  281.28  5030.4  284.44  5036.0  282.83
  5045.8  284.28  5058.0  282.25  5074.4  285.38  5112.8  288.12  5210.0  287.59
  5254.4  284.29  5295.3  288.64  5412.2  290.89  5558.7  296.12  5846.4  310.50
  5856.6  311.22  5862.0  313.38  5907.4  313.06  5912.5  314.22  5984.4  317.38
#Mann=5,-1,0
  4111.7    0.05       0  4445.5    0.07       0  4546.4    0.05       0
  5020.1    0.05       0  5026.3    0.05       0
Bank Sta=5020.1,5026.3
Exp/Cntr=0.3,0.1

Chan Stop Cuts=-1