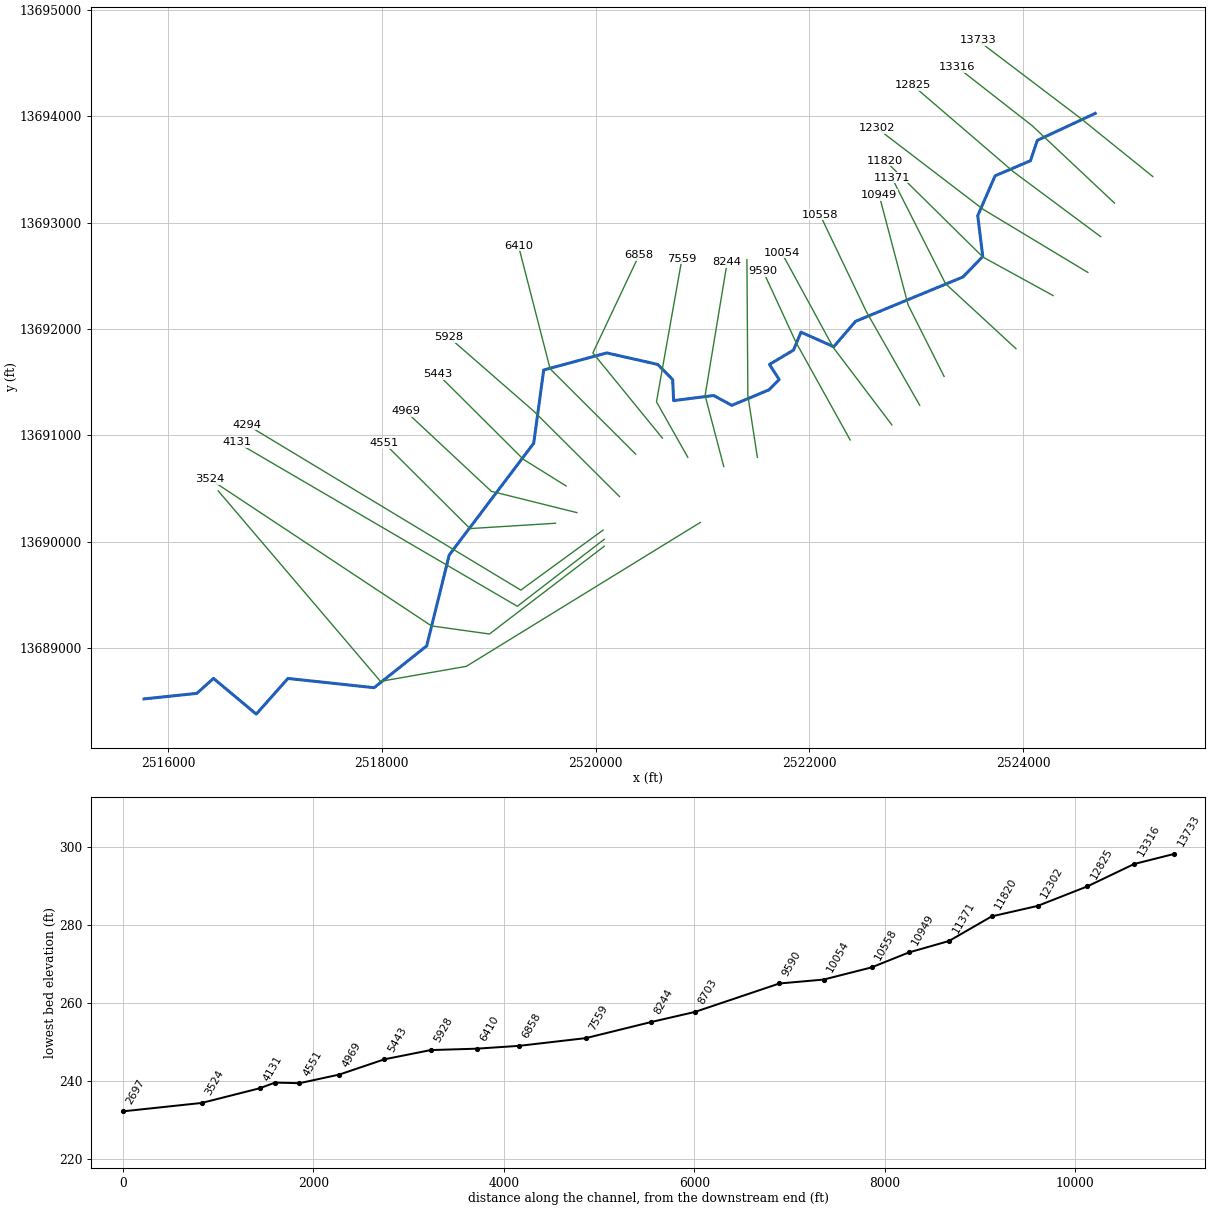
--- Stream0330.prj (project) ---

Proj Title=Stream0330 Base Level Engineering
Current Plan=p01
Default Exp/Contr=0.3,0.1
English Units
Geom File=g01
Flow File=f01
Plan File=p01
Y Axis Title=Elevation
X Axis Title(PF)=Main Channel Distance
X Axis Title(XS)=Station
BEGIN DESCRIPTION:
Stream0330
END DESCRIPTION:
DSS Export Rating Curves= 0
DSS Export Rating Curve Sorted= 0
DSS Export Volume Flow Curves= 0
DXF OffsetX= 0
DXF OffsetY= 0
DXF ScaleX= 1
DXF ScaleY= 10

--- Stream0330.p01 (plan) ---

Plan Title=Multiple Run
Short Identifier=Multiple
Geom File=g01
Flow File=f01
Subcritical Flow
K Sum by GR= 0
Std Step Tol= 0.01
Critical Tol= 0.01
Num of Std Step Trials= 20
Max Error Tol= 0.3
Flow Tol Ratio= 0.001
Split Flow NTrial= 30
Split Flow Tol= 0.02
Split Flow Ratio= 0.02
Log Output Level= 0
Friction Slope Method= 1
Unsteady Friction Slope Method= 2
Unsteady Bridges Friction Slope Method= 1
Parabolic Critical Depth
Global Vel Dist=  1 , 1 , 1
Global Log Level= 0
CheckData=True
Encroach Param= -1, 0, 0, 0
BEGIN DESCRIPTION:
Multiple Run
END DESCRIPTION:

--- Stream0330.f01 (steady flow) ---

Flow Title=Multiple
Number of Profiles=7
Profile Names=10-year,25-year,50-year,1pct_min,100-year,1pct_plu,500-year
River Rch & RM= Stream0330,Reach-1,13733
     885    1451    1973    1300    2594    5175    4434
River Rch & RM= Stream0330,Reach-1,13316
    1188    1979    2717    1805    3601    7186    6265
River Rch & RM= Stream0330,Reach-1,6410
    1622    2744    3808    2554    5095   10166    9034
River Rch & RM= Stream0330,Reach-1,4551
    1680    2837    3930    2630    5248   10471    9269
Boundary for River Rch & Prof#=Stream0330,Reach-1,1
Up Type=0
Dn Type=3
Dn Slope=0.005
Boundary for River Rch & Prof#=Stream0330,Reach-1,2
Up Type=0
Dn Type=3
Dn Slope=0.005
Boundary for River Rch & Prof#=Stream0330,Reach-1,3
Up Type=0
Dn Type=3
Dn Slope=0.005
Boundary for River Rch & Prof#=Stream0330,Reach-1,4
Up Type=0
Dn Type=3
Dn Slope=0.005
Boundary for River Rch & Prof#=Stream0330,Reach-1,5
Up Type=0
Dn Type=3
Dn Slope=0.005
Boundary for River Rch & Prof#=Stream0330,Reach-1,6
Up Type=0
Dn Type=3
Dn Slope=0.005
Boundary for River Rch & Prof#=Stream0330,Reach-1,7
Up Type=0
Dn Type=3
Dn Slope=0.005

--- Stream0330.g01 (geometry) ---

Geom Title=Existing Conditions
Program Version=4.10

River Reach=Stream0330      ,Reach-1
Reach XY= 30
        2524675.       13694025.      2524133.46      13693771.5
      2524069.75     13693580.44      2523738.45     13693438.63
      2523576.06     13693064.56      2523623.04     13692680.89
       2523438.3      13692488.4      2522432.98     13692072.05
      2522228.41     13691832.81      2521922.43     13691970.05
      2521852.12     13691801.48      2521627.46     13691666.83
      2521717.92     13691524.98      2521623.53     13691428.61
        2521275.      13691282.5      2521104.97     13691374.96
      2520730.45     13691327.05      2520721.54      13691523.5
      2520581.19     13691667.19      2520104.97     13691774.93
      2519514.84     13691614.64      2519421.25     13690926.55
      2518630.84     13689877.29      2518419.89     13689022.71
       2517927.7     13688630.35      2517121.58     13688717.21
      2516825.02     13688382.08      2516424.91     13688717.72
      2516269.15     13688577.06        2515775.       13688525.

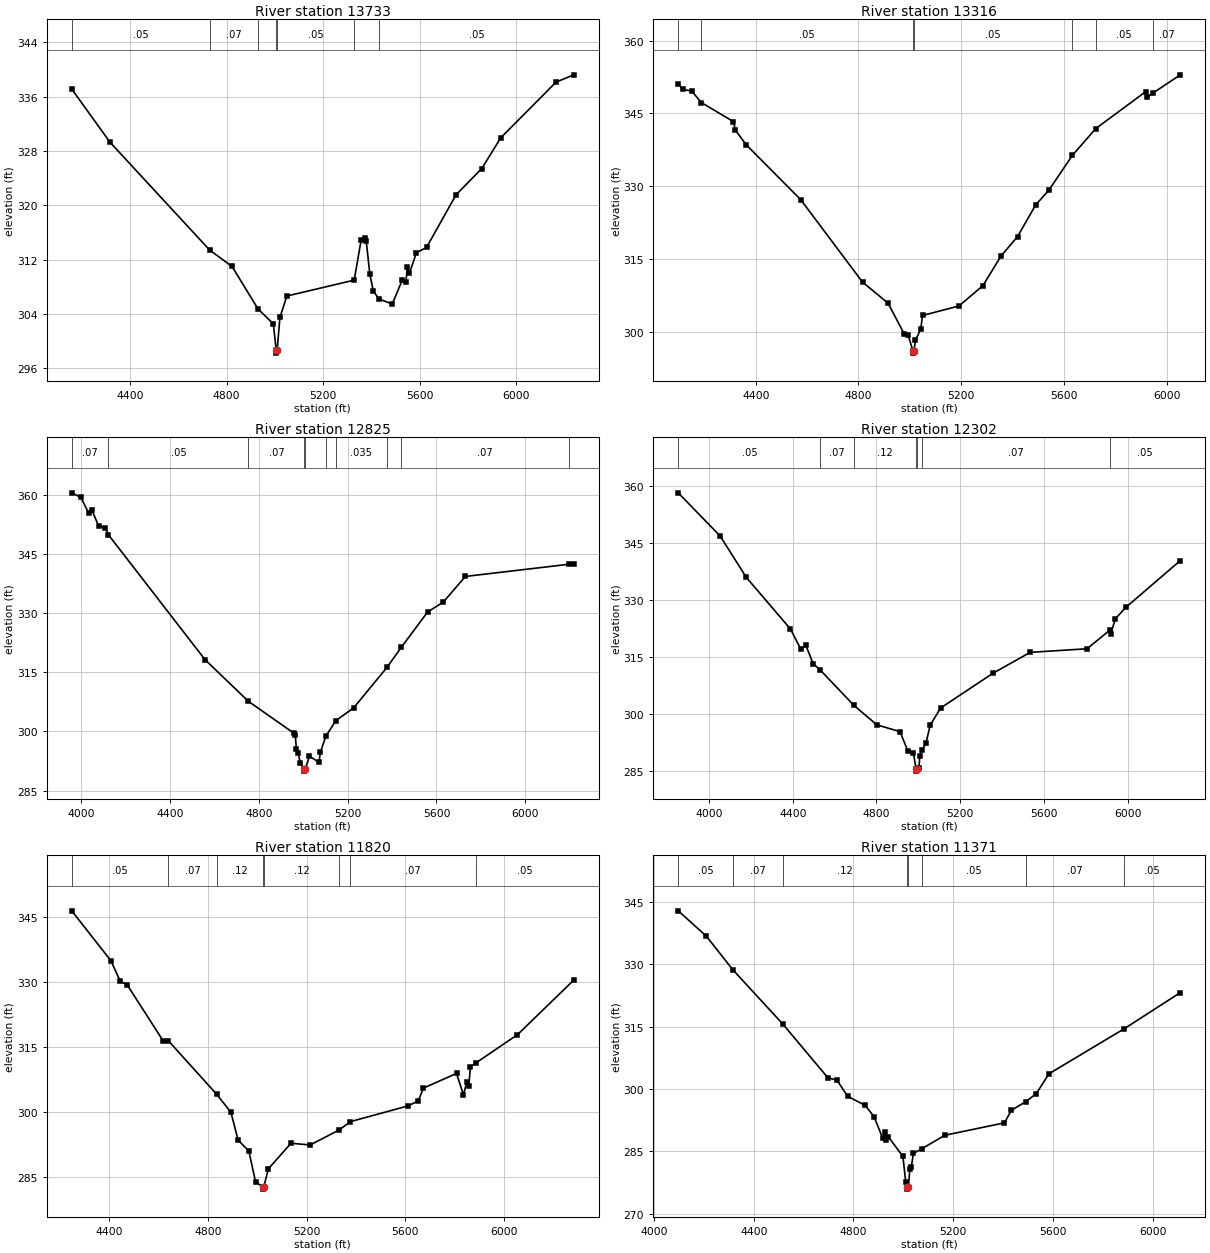
Type RM Length L Ch R = 1 ,13733   ,417,417,417
BEGIN DESCRIPTION:
Stream0330 20.0
END DESCRIPTION:
XS GIS Cut Line= 3
      2525214.14     13693431.62      2524530.51     13693985.03
      2523576.98     13694711.01
#Sta/Elev= 30
  4159.4   337.1  4317.4  329.28  4730.4  313.38  4822.6  310.98  4930.4  304.71
  4993.7  302.52  5005.3  298.71  5005.6  298.21  5009.6  298.71  5020.9  303.47
  5049.7  306.62  5328.2  308.96  5357.3   314.9  5371.8  315.21  5378.1  314.75
  5392.7  309.93  5407.2  307.38  5430.8  306.19  5485.8  305.44  5527.8  309.02
  5542.4  308.73  5548.6  310.91  5556.9  309.98    5586  313.01  5627.6  313.77
  5749.7  321.52  5856.3   325.4  5935.3  329.94  6163.9  338.13  6237.4   339.2
#Mann= 7 ,-1 , 0
  4159.4     .05       0  4730.4     .07       0  4930.4     .05       0
  5005.3     .05       0  5009.6     .05       0  5328.2     .07       0
  5430.8     .05       0
Bank Sta=5005.3,5009.6
XS Rating Curve= 0 ,0
Exp/Cntr=0.3,0.1

Type RM Length L Ch R = 1 ,13316   ,491,491,491
BEGIN DESCRIPTION:
Stream0330 19.0
END DESCRIPTION:
XS GIS Cut Line= 3
      2524856.02     13693182.09      2524085.63     13693909.07
      2523381.93     13694461.21
#Sta/Elev= 30
  4098.6  351.09  4115.4  349.97    4151   349.6  4188.7  347.23  4313.6  343.31
  4320.5  341.62    4363  338.55  4575.4  327.24  4815.7  310.27  4914.8  305.95
  4978.7  299.54  4992.9  299.43  5011.6  296.15  5011.9  295.65  5016.2  296.15
  5021.2  298.25  5042.2   300.6  5049.1   303.4  5191.1  305.36  5284.2  309.55
  5354.7  315.65  5418.9  319.64  5489.4  326.16    5540  329.14  5632.6  336.39
  5723.3  341.88  5917.8  349.49  5924.2   348.3  5944.8  349.16  6052.3  352.95
#Mann= 7 ,-1 , 0
  4098.6    .035       0  4188.7     .05       0  5011.6     .05       0
  5016.2     .05       0  5632.6    .035       0  5723.3     .05       0
  5944.8     .07       0
Bank Sta=5011.6,5016.2
XS Rating Curve= 0 ,0
Exp/Cntr=0.3,0.1

Type RM Length L Ch R = 1 ,12825   ,523,523,523
BEGIN DESCRIPTION:
Stream0330 18.0
END DESCRIPTION:
XS GIS Cut Line= 3
      2524725.82     13692867.41      2523912.02     13693475.04
      2522968.99       13694288.
#Sta/Elev= 30
    3958  360.51  3999.2  359.35  4034.7  355.28  4049.3  356.04  4078.5  352.17
  4107.7  351.71  4123.3  349.85  4557.9   318.2  4753.3  307.63  4957.4  299.57
  4964.4  299.02  4969.4  295.43  4978.8  294.56  4985.4  292.07    5005  290.42
  5005.3  289.92  5009.6  290.42  5028.1  293.72  5070.9  292.14  5077.5  294.71
    5102  298.75  5146.7  302.73  5226.7  305.93    5377  316.21  5441.2  321.28
  5560.2  330.29  5630.5  332.77  5730.3   339.3    6195  342.38  6218.7  342.57
#Mann= 10 ,-1 , 0
    3958     .07       0  4123.3     .05       0  4753.3     .07       0
    5005     .05       0  5009.6     .07       0    5102     .05       0
  5146.7    .035       0    5377     .05       0  5441.2     .07       0
    6195    .035       0
Bank Sta=5005,5009.6
XS Rating Curve= 0 ,0
Exp/Cntr=0.3,0.1

Type RM Length L Ch R = 1 ,12302   ,482,482,482
BEGIN DESCRIPTION:
Stream0330 17.0
END DESCRIPTION:
XS GIS Cut Line= 3
      2524606.46     13692531.04        2523625.       13693125.
      2522631.62     13693887.38
#Sta/Elev= 30
  3852.8  358.16  4053.2  346.78  4177.5  335.95    4389  322.32  4438.9  316.96
  4462.3  318.08  4497.4  313.22  4532.6  311.45  4691.9  302.24  4802.2  297.08
  4912.7   295.3  4949.6  290.25  4976.7  289.64  4989.9  285.41  4990.2  284.91
  4994.6  285.41  5003.1  285.73  5007.3  288.89  5016.2  290.35  5036.3  292.19
  5057.1  297.04  5106.9  301.53  5356.2  310.65  5534.8  316.17  5806.7  317.12
  5916.6  322.07  5920.2   321.1  5941.8  325.02  5991.6  327.99  6252.2  340.33
#Mann= 7 ,-1 , 0
  3852.8     .05       0  4532.6     .07       0  4691.9     .12       0
  4989.9     .05       0  4994.6     .12       0  5016.2     .07       0
  5916.6     .05       0
Bank Sta=4989.9,4994.6
XS Rating Curve= 0 ,0
Exp/Cntr=0.3,0.1

Type RM Length L Ch R = 1 ,11820   ,449,449,449
BEGIN DESCRIPTION:
Stream0330 16.0
END DESCRIPTION:
XS GIS Cut Line= 3
      2524280.95     13692314.01        2523625.       13692675.
      2522708.79     13693582.37
#Sta/Elev= 30
  4247.1  346.36  4406.3  334.83  4444.2   330.1  4471.7  329.34  4619.2  316.29
  4639.5  316.41  4835.7  304.06  4893.1  299.95  4922.4  293.52    4966     291
    4993  283.94  5021.7  282.73    5022  282.23  5026.5  282.73  5045.3  286.92
  5137.2   292.8    5215  292.41    5333  295.87  5377.5  297.77    5611  301.39
  5653.5  302.55  5674.6  305.51    5809  308.88  5837.3  303.96  5851.5  307.03
  5858.5  305.96  5865.6  310.43  5888.1  311.33  6056.5  317.82  6285.3  330.42
#Mann= 8 ,-1 , 0
  4247.1     .05       0  4639.5     .07       0  4835.7     .12       0
  5021.7     .05       0  5026.5     .12       0    5333     .05       0
  5377.5     .07       0  5888.1     .05       0
Bank Sta=5021.7,5026.5
XS Rating Curve= 0 ,0
Exp/Cntr=0.3,0.1

Type RM Length L Ch R = 1 ,11371   ,422,422,422
BEGIN DESCRIPTION:
Stream0330 15.0
END DESCRIPTION:
XS GIS Cut Line= 3
      2523933.75     13691814.86        2523275.       13692425.
      2522772.88     13693420.43
#Sta/Elev= 30
  4097.5  342.85  4209.9  336.77  4316.3  328.68  4517.9  315.54    4698  302.66
  4733.7  302.15  4776.3  298.26  4846.6  296.07  4882.3  293.38  4917.4  288.14
  4924.8  289.63  4931.6  287.81    4939  288.57  4998.2  283.79  5009.3  277.72
  5015.3  276.42  5015.6  275.92  5020.3  276.42  5026.1  280.88  5031.7  281.19
  5040.2  284.52  5073.6  285.61  5165.5  288.86  5405.2  291.86  5433.1  294.87
  5489.7  296.92    5533  298.88  5583.6  303.66  5885.4  314.49  6110.3  323.18
#Mann= 8 ,-1 , 0
  4097.5     .05       0  4316.3     .07       0  4517.9     .12       0
  5015.3     .05       0  5020.3     .12       0  5073.6     .05       0
  5489.7     .07       0  5885.4     .05       0
Bank Sta=5015.3,5020.3
XS Rating Curve= 0 ,0
Exp/Cntr=0.3,0.1

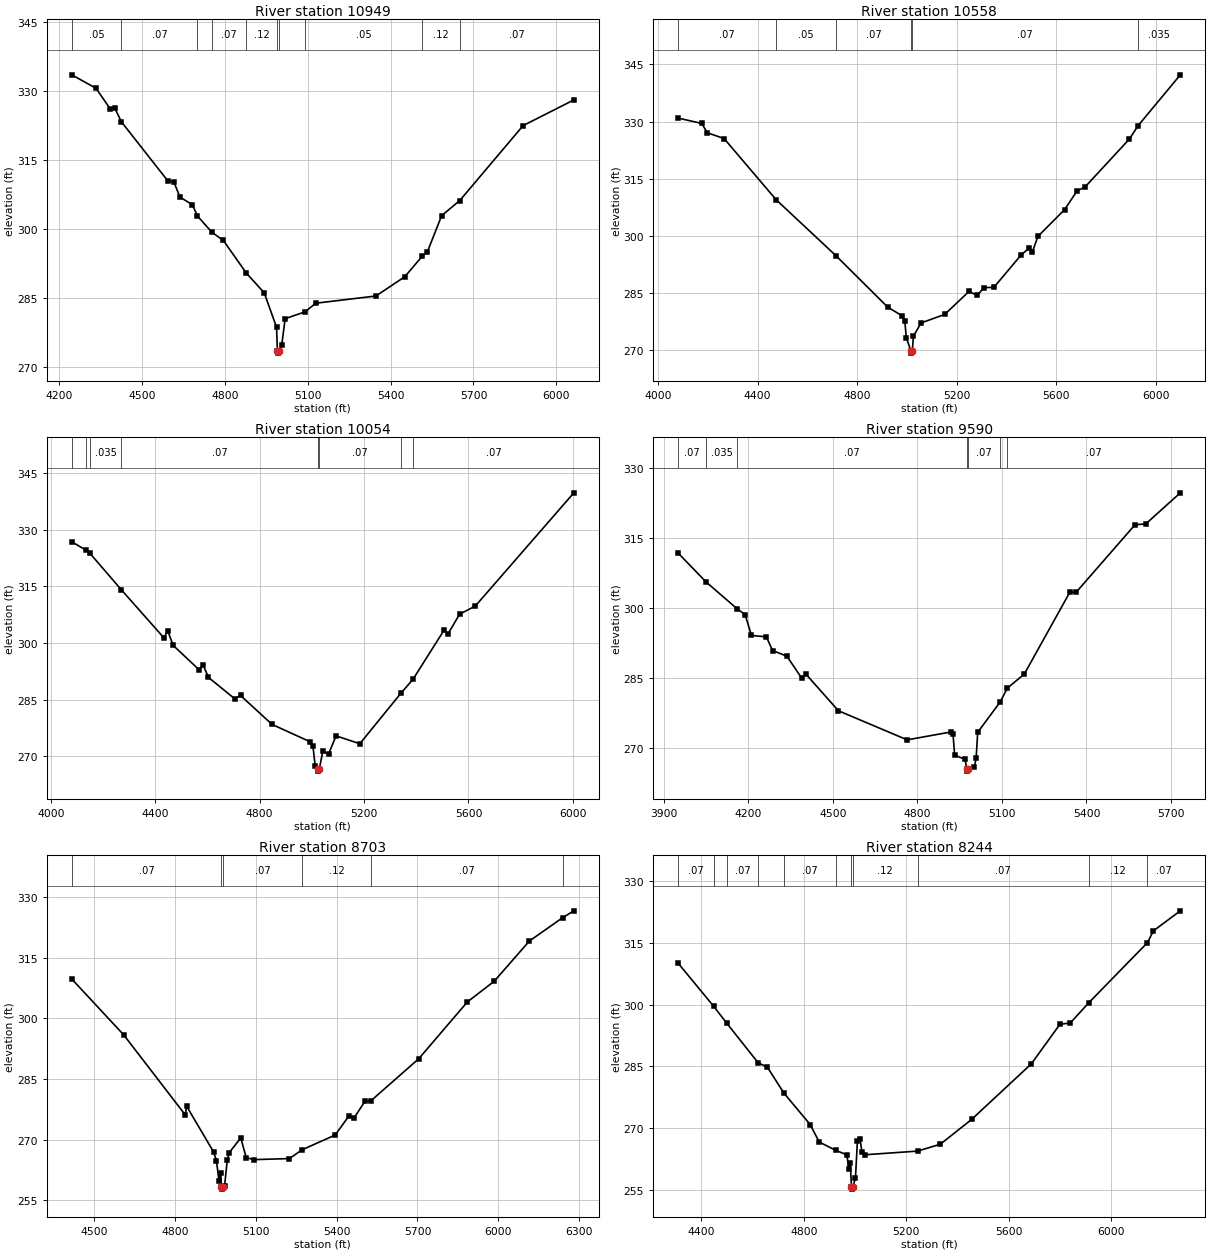
Type RM Length L Ch R = 1 ,10949   ,391,391,391
BEGIN DESCRIPTION:
Stream0330 14.0
END DESCRIPTION:
XS GIS Cut Line= 3
      2523260.98     13691554.48        2522925.       13692225.
      2522653.35     13693257.99
#Sta/Elev= 30
  4245.4  333.43  4333.4   330.5  4383.7  326.11  4400.4   326.3  4425.1  323.23
  4592.7  310.43  4615.1  310.14  4637.5  306.85  4682.2  305.22  4700.4  302.77
    4753  299.22  4794.1  297.47  4877.6  290.36  4942.3  286.08    4987  278.58
    4990  273.48  4990.4  272.98  4995.1  273.48  5005.7  274.75  5018.1  280.47
  5089.6  281.93  5128.8  283.82  5346.9  285.39  5451.5  289.58    5515  294.07
  5533.1  294.98  5584.8  302.84  5650.3  306.12  5879.8   322.4  6063.5  327.98
#Mann= 10 ,-1 , 0
  4245.4     .05       0  4425.1     .07       0  4700.4     .05       0
    4753     .07       0  4877.6     .12       0    4990     .05       0
  4995.1     .12       0  5089.6     .05       0    5515     .12       0
  5650.3     .07       0
Bank Sta=4990,4995.1
XS Rating Curve= 0 ,0
Exp/Cntr=0.3,0.1

Type RM Length L Ch R = 1 ,10558   ,504,504,504
BEGIN DESCRIPTION:
Stream0330 13.0
END DESCRIPTION:
XS GIS Cut Line= 3
      2523033.12      13691283.2      2522533.98     13692162.11
      2522100.81     13693071.78
#Sta/Elev= 30
  4081.3  330.89  4175.4   329.5  4198.4  327.04  4265.7  325.52  4474.7  309.46
    4715  294.77  4923.2  281.25  4982.4  278.92  4991.9  277.68  4998.2  273.18
  5017.3  269.66  5017.7  269.16  5022.5  269.66  5026.4  273.57  5057.4  277.09
    5152  279.31  5250.3  285.36  5282.7  284.33  5310.9  286.38    5350  286.42
  5460.8  295.03  5492.6  296.76  5505.1  295.77  5527.2  299.82  5634.4  306.86
  5685.3  311.84  5715.5  312.72  5895.2  325.42  5930.2  328.93  6099.6  342.26
#Mann= 6 ,-1 , 0
  4081.3     .07       0  4474.7     .05       0    4715     .07       0
  5017.3     .05       0  5022.5     .07       0  5930.2    .035       0
Bank Sta=5017.3,5022.5
XS Rating Curve= 0 ,0
Exp/Cntr=0.3,0.1

Type RM Length L Ch R = 1 ,10054   ,464,464,464
BEGIN DESCRIPTION:
Stream0330 12.0
END DESCRIPTION:
XS GIS Cut Line= 3
      2522772.73     13691098.71        2522225.       13691825.
      2521741.87     13692715.51
#Sta/Elev= 30
  4080.7   326.8  4135.1   324.6  4149.3  323.83  4270.1  314.13  4433.5  301.36
  4448.1  303.24  4468.9  299.36  4568.8  292.87  4583.4   294.2  4604.2  290.87
  4704.1  285.25    4727  286.08  4847.8  278.41  4993.2  273.83  5004.1  272.81
  5013.1   267.3  5023.4  266.54  5023.8  266.04  5028.6  266.54  5042.2  271.33
    5064  270.52  5092.8  275.39  5183.8   273.3  5341.9  286.73  5387.8   290.4
  5506.1  303.36  5522.3  302.48    5566  307.63  5625.9  309.76  6003.5  339.78
#Mann= 8 ,-1 , 0
  4080.7     .05       0  4135.1     .07       0  4149.3    .035       0
  4270.1     .07       0  5023.4     .05       0  5028.6     .07       0
  5341.9     .12       0  5387.8     .07       0
Bank Sta=5023.4,5028.6
XS Rating Curve= 0 ,0
Exp/Cntr=0.3,0.1

Type RM Length L Ch R = 1 ,9590    ,887,887,887
BEGIN DESCRIPTION:
Stream0330 11.0
END DESCRIPTION:
XS GIS Cut Line= 3
      2522382.09     13690957.66        2521875.       13691875.
      2521568.69     13692540.97
#Sta/Elev= 30
  3951.8   311.8  4050.2  305.65    4161  299.85    4189  298.63  4211.6  294.15
  4264.6  293.85  4286.3  290.92  4337.2   289.7  4389.4  285.03  4405.5   285.8
  4520.1  277.99    4764  271.75    4920  273.45  4926.7  272.97  4932.4  268.46
  4970.2  267.55  4974.5  265.54  4974.9  265.04  4979.7  265.54  5002.7   265.9
  5008.7  267.92  5014.2  273.36  5094.9  279.96  5119.2  282.84  5179.5  285.86
  5341.2  303.44  5363.2   303.4  5572.3   317.9  5610.5  318.08    5733  324.75
#Mann= 7 ,-1 , 0
  3951.8     .07       0  4050.2    .035       0    4161     .07       0
  4974.5     .05       0  4979.7     .07       0  5094.9     .12       0
  5119.2     .07       0
Bank Sta=4974.5,4979.7
XS Rating Curve= 0 ,0
Exp/Cntr=0.3,0.1

Type RM Length L Ch R = 1 ,8703    ,459,459,459
BEGIN DESCRIPTION:
Stream0330 10.0
END DESCRIPTION:
XS GIS Cut Line= 3
      2521514.03     13690794.88        2521425.       13691375.
      2521416.36     13692650.16
#Sta/Elev= 30
  4417.8  309.73  4610.1  295.94  4838.8  276.11  4843.9  278.24    4944  266.93
  4954.1  264.83  4964.2  259.72  4970.5  261.67  4972.9  258.25  4973.3  257.75
  4978.2  258.25  4984.5  258.46  4994.6  265.03  5002.2  266.81  5044.7  270.43
  5064.7  265.52  5094.7  265.05  5224.7  265.31  5272.5  267.49  5394.7  271.14
  5444.7  275.75  5464.7  275.36  5504.7  279.43  5527.4  279.61  5704.7  290.01
  5884.7  304.04  5984.7  309.19  6114.7  319.11  6238.3   324.9  6279.9   326.6
#Mann= 6 ,-1 , 0
  4417.8     .07       0  4972.9     .05       0  4978.2     .07       0
  5272.5     .12       0  5527.4     .07       0  6238.3     .05       0
Bank Sta=4972.9,4978.2
XS Rating Curve= 0 ,0
Exp/Cntr=0.3,0.1

Type RM Length L Ch R = 1 ,8244    ,685,685,685
BEGIN DESCRIPTION:
Stream0330 9.0
END DESCRIPTION:
XS GIS Cut Line= 3
      2521199.35     13690708.09        2521025.       13691375.
      2521231.91     13692628.72
#Sta/Elev= 30
  4310.2  310.06  4448.2  299.64  4500.3  295.45  4621.9   285.9  4658.4  284.79
  4722.9   278.5  4825.3  270.87  4860.6  266.62    4925   264.6  4968.5   263.5
  4976.7  259.97  4981.9  261.56  4986.5  255.67  4986.9  255.17  4991.8  255.67
  5002.1  257.93  5009.7  266.91  5019.8  267.24  5027.5  264.28  5040.1  263.53
  5244.3  264.41  5333.1  266.08  5455.3   272.1  5688.7  285.63  5800.2  295.24
  5840.7  295.56  5912.8  300.47  6141.8  315.08  6165.1  317.95  6270.2  322.82
#Mann= 11 ,-1 , 0
  4310.2     .07       0  4448.2     .12       0  4500.3     .07       0
  4621.9     .12       0  4722.9     .07       0    4925     .12       0
  4986.5     .05       0  4991.8     .12       0  5244.3     .07       0
  5912.8     .12       0  6141.8     .07       0
Bank Sta=4986.5,4991.8
XS Rating Curve= 0 ,0
Exp/Cntr=0.3,0.1

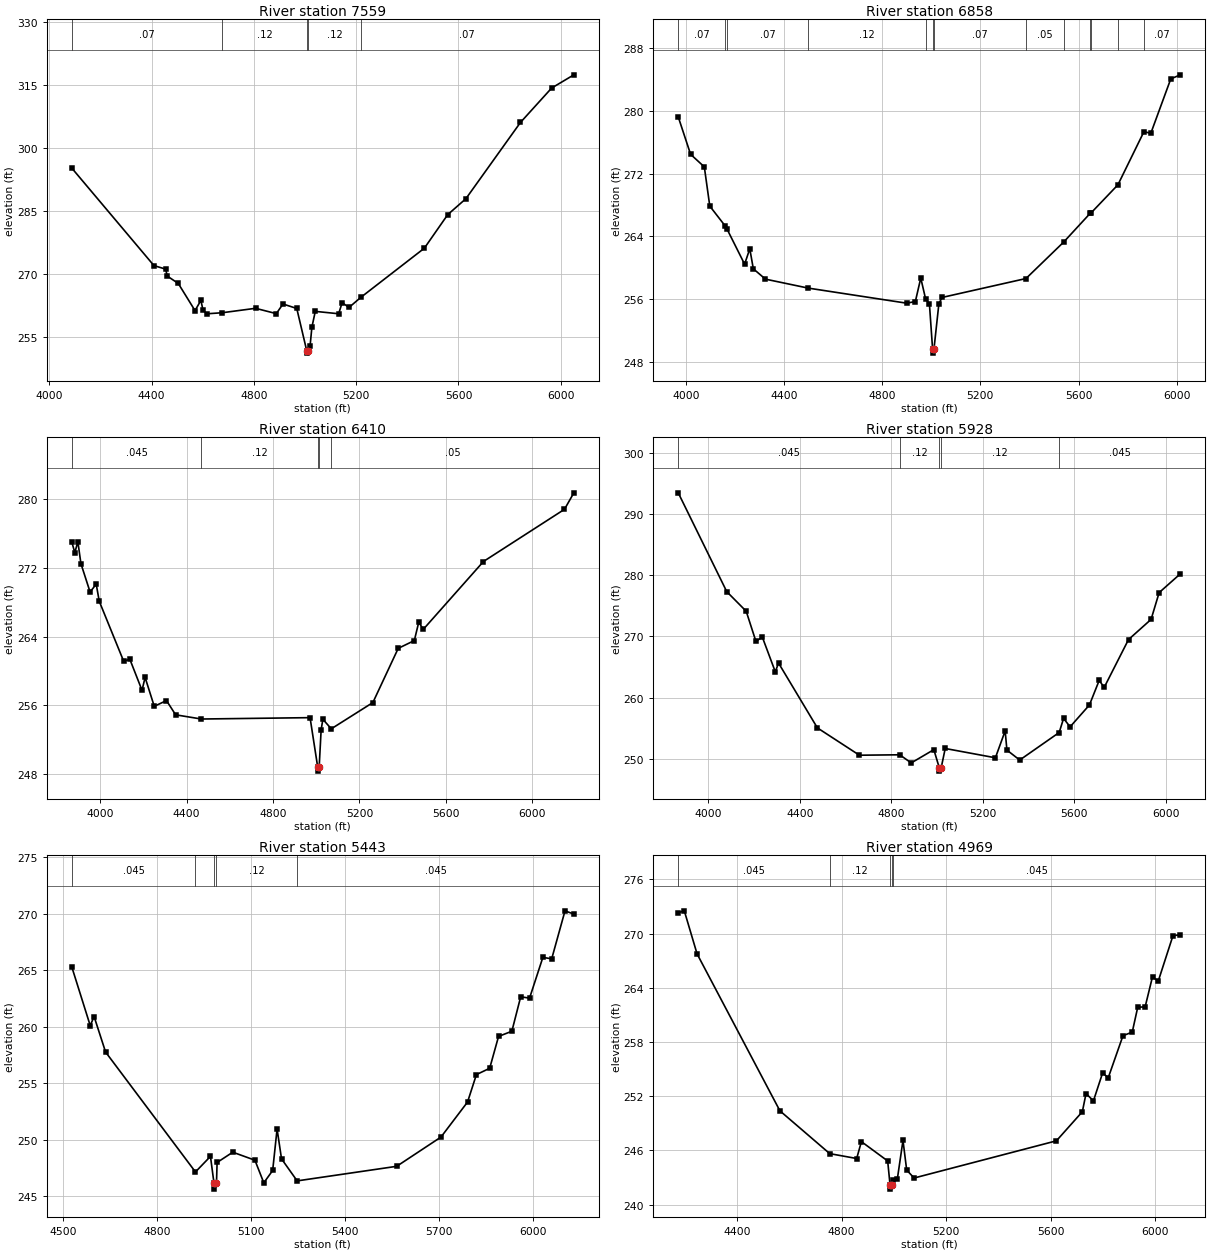
Type RM Length L Ch R = 1 ,7559    ,701,701,701
BEGIN DESCRIPTION:
XS6486
END DESCRIPTION:
XS GIS Cut Line= 3
      2520862.98     13690794.92      2520570.01     13691315.76
      2520808.61     13692660.58
#Sta/Elev= 30
  4087.9  295.23  4409.2  271.95  4455.1   271.1    4461  269.46  4504.3  267.69
  4569.9   261.2  4592.8  263.65  4601.2  261.29  4615.8  260.44  4675.8  260.69
  4806.6  261.75  4887.8  260.48  4913.8  262.78  4967.8  261.71    5007  251.55
  5007.4  251.05  5012.4  251.55  5019.9  252.82  5026.9  257.24  5040.2  261.02
  5131.6  260.45  5145.1  263.09  5172.2  261.96    5218  264.35  5466.7   276.1
  5558.1  284.11  5629.2  287.92  5842.5  306.12  5964.4  314.33  6051.3  317.49
#Mann= 5 ,-1 , 0
  4087.9     .07       0  4675.8     .12       0    5007     .05       0
  5012.4     .12       0    5218     .07       0
Bank Sta=5007,5012.4
XS Rating Curve= 0 ,0
Exp/Cntr=0.3,0.1

Type RM Length L Ch R = 1 ,6858    ,448,448,448
BEGIN DESCRIPTION:
Stream0330 8.0
END DESCRIPTION:
XS GIS Cut Line= 3
      2520624.98     13690975.02        2519975.       13691775.
      2520407.23     13692693.76
#Sta/Elev= 30
  3968.8  279.25  4019.1  274.47  4075.1  272.86  4097.4  267.85    4161  265.28
  4166.6  264.98  4239.3  260.43  4260.4   262.4  4274.8  259.84  4324.3  258.52
  4497.8  257.38  4899.7  255.45  4935.1  255.66  4957.2  258.66  4977.1  255.96
  4992.4  255.38  5005.4  249.57  5005.9  249.07  5010.9  249.57    5031  255.38
  5043.8  256.18    5386   258.6    5540  263.27  5648.5  266.96    5650  266.94
  5760.6  270.57  5866.7  277.36  5894.7  277.15    5976   284.1  6014.9  284.62
#Mann= 13 ,-1 , 0
  3968.8     .07       0    4161    .045       0  4166.6     .07       0
  4497.8     .12       0  4977.1     .07       0  5005.4     .05       0
  5010.9     .07       0    5386     .05       0    5540     .12       0
  5648.5     .05       0    5650     .07       0  5760.6     .05       0
  5866.7     .07       0
Bank Sta=5005.4,5010.9
XS Rating Curve= 0 ,0
Exp/Cntr=0.3,0.1

Type RM Length L Ch R = 1 ,6410    ,482,482,482
BEGIN DESCRIPTION:
Stream0330 7.0
END DESCRIPTION:
XS GIS Cut Line= 3
      2520374.97     13690825.03        2519575.       13691625.
      2519278.85     13692780.32
#Sta/Elev= 30
  3868.6  275.04  3882.7   273.8  3896.8  275.06    3911  272.51  3953.4   269.2
  3981.7  270.13  3995.8  268.13    4109  261.13  4137.3  261.38  4193.8  257.75
    4208  259.26  4250.4  255.89    4307  256.56  4349.4   254.9  4468.6  254.41
  4971.6  254.57  5006.8  248.84  5007.3  248.34  5013.8  248.84  5022.9  253.16
  5030.9  254.38  5069.9  253.27  5262.4  256.33  5379.6  262.64  5454.2  263.55
  5474.8   265.7  5495.5  264.85  5774.2  272.76  6149.3  278.84  6192.6  280.76
#Mann= 5 ,-1 , 0
  3868.6    .045       0  4468.6     .12       0  5006.8     .05       0
  5013.8     .12       0  5069.9     .05       0
Bank Sta=5006.8,5013.8
XS Rating Curve= 0 ,0
Exp/Cntr=0.3,0.1

Type RM Length L Ch R = 1 ,5928    ,485,485,485
BEGIN DESCRIPTION:
Stream0330 6.0
END DESCRIPTION:
XS GIS Cut Line= 3
      2520224.99     13690425.01        2519425.       13691225.
      2518624.98     13691925.02
#Sta/Elev= 30
  3868.6  293.46  4080.7  277.31  4165.6  274.11    4208   269.2  4236.3  269.87
  4292.8  264.21    4307  265.64  4476.7  255.05  4660.5  250.58  4836.8  250.65
  4886.8  249.32  4985.8  251.49  5009.9  248.48  5010.4  247.98  5017.6  248.48
  5035.5  251.68  5254.8  250.16  5297.5  254.56  5305.1  251.42  5361.1  249.79
  5533.5  254.29  5552.8  256.59  5581.3  255.22  5665.8  258.79  5708.5  262.81
  5730.3  261.66  5836.6  269.48  5935.3  272.78  5970.4  277.15    6063  280.22
#Mann= 5 ,-1 , 0
  3868.6    .045       0  4836.8     .12       0  5009.9     .05       0
  5017.6     .12       0  5533.5    .045       0
Bank Sta=5009.9,5017.6
XS Rating Curve= 0 ,0
Exp/Cntr=0.3,0.1

Type RM Length L Ch R = 1 ,5443    ,474,474,474
BEGIN DESCRIPTION:
Stream0330 5.0
END DESCRIPTION:
XS GIS Cut Line= 3
      2519724.98     13690525.01        2519325.       13690775.
      2518525.03     13691574.97
#Sta/Elev= 30
  4528.3   265.3  4587.2   260.1  4599.6   260.9  4636.2  257.76  4923.2  247.14
  4971.1  248.52  4982.5  246.12    4983  245.62  4990.3  246.12  4992.3  247.98
  5042.4  248.89  5113.1  248.18  5141.4  246.18  5169.7  247.27  5183.8  250.94
    5198   248.3  5247.9  246.35  5565.7  247.64  5707.1  250.23  5791.9  253.33
  5820.2  255.76  5862.6  256.32  5890.9  259.14  5933.4   259.6  5961.6  262.65
  5989.9  262.53  6032.4  266.14  6060.6  266.01  6103.1  270.26  6131.3  269.97
#Mann= 5 ,-1 , 0
  4528.3    .045       0  4923.2     .12       0  4982.5     .05       0
  4990.3     .12       0  5247.9    .045       0
Bank Sta=4982.5,4990.3
XS Rating Curve= 0 ,0
Exp/Cntr=0.3,0.1

Type RM Length L Ch R = 1 ,4969    ,418,418,418
BEGIN DESCRIPTION:
Stream0330 4.0
END DESCRIPTION:
XS GIS Cut Line= 3
      2519824.96     13690275.01        2519025.       13690475.
      2518224.97     13691225.02
#Sta/Elev= 30
  4175.2  272.32  4198.4  272.53  4247.3  267.76  4564.3  250.38    4755  245.64
    4858   245.1  4876.1  246.97  4976.6  244.83  4985.6  242.21  4986.1  241.71
  4993.4  242.21  4997.3  242.67  5013.7  242.85  5035.2   247.1  5049.4  243.82
  5077.7  242.94  5622.3  247.06  5721.5  250.28  5735.6  252.29    5764  251.49
  5799.1  254.58  5820.6  254.04    5877   258.7  5912.5   259.1  5933.5  261.86
  5961.8  261.89  5990.1  265.25  6011.6  264.71  6068.3  269.78  6096.4  269.88
#Mann= 5 ,-1 , 0
  4175.2    .045       0    4755     .12       0  4985.6    .045       0
  4993.4     .12       0  4997.3    .045       0
Bank Sta=4985.6,4993.4
XS Rating Curve= 0 ,0
Exp/Cntr=0.3,0.1

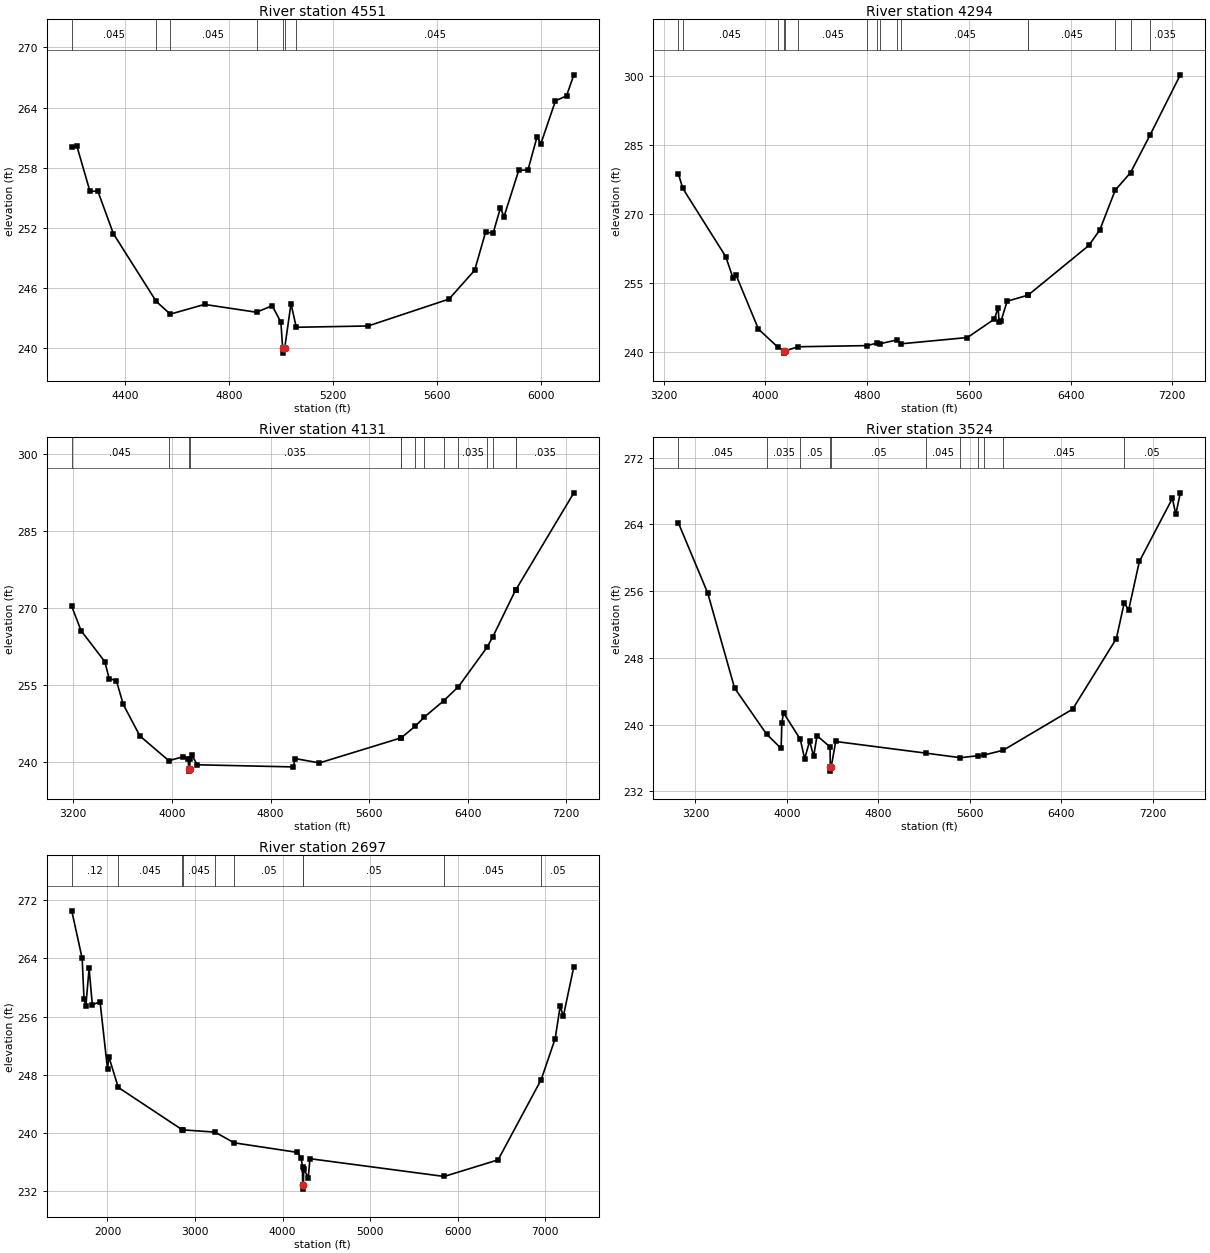
Type RM Length L Ch R = 1 ,4551    ,257,257,257
BEGIN DESCRIPTION:
Stream0330 3.0
END DESCRIPTION:
XS GIS Cut Line= 3
      2519625.02       13690175.        2518825.       13690125.
      2518025.03     13690924.97
#Sta/Elev= 30
  4193.6  260.06  4213.7  260.12  4263.8  255.63  4293.8  255.68  4353.9  251.41
  4518.8  244.66  4572.9  243.39  4704.6  244.36  4904.8  243.58  4965.1  244.23
  4998.7  242.59  5005.4     240  5005.9   239.5  5013.3     240  5037.6  244.44
  5057.8  242.08  5334.6  242.21  5645.7  244.89  5744.7  247.77  5787.1  251.61
  5815.4  251.44  5843.7  253.98  5857.8  253.13  5914.4  257.74  5949.8  257.77
  5985.1  261.11  5999.3  260.38  6055.8  264.68  6098.3  265.17  6126.5  267.27
#Mann= 7 ,-1 , 0
  4193.6    .045       0  4518.8    .035       0  4572.9    .045       0
  4904.8     .12       0  5005.4     .05       0  5013.3     .12       0
  5057.8    .045       0
Bank Sta=5005.4,5013.3
XS Rating Curve= 0 ,0
Exp/Cntr=0.3,0.1

Type RM Length L Ch R = 1 ,4294    ,163,163,163
BEGIN DESCRIPTION:
XS6485
END DESCRIPTION:
XS GIS Cut Line= 3
      2520070.84      13690111.3      2519300.48     13689547.09
      2516739.85     13691098.66
#Sta/Elev= 30
  3314.6   278.8  3350.9  275.54  3688.3  260.68  3744.7  256.07  3767.8  256.77
  3945.4  244.89  4097.3  240.97  4148.3  240.15  4148.8  239.65  4156.3  240.15
  4258.3  241.04  4800.4  241.29  4874.4  241.82  4904.6  241.72  5034.6  242.52
  5070.1  241.69  5589.3  243.05  5800.6  247.06    5831  249.58  5837.5  246.54
    5853  246.62  5901.5  250.96  6062.7  252.26  6064.8  252.26  6544.2  263.12
  6630.6  266.52  6751.6  275.17  6871.8  278.98    7025  287.15  7263.5  300.31
#Mann= 16 ,-1 , 0
  3314.6     .07       0  3350.9    .045       0  4097.3    .035       0
  4148.3     .05       0  4156.3    .035       0  4258.3    .045       0
  4800.4     .12       0  4874.4    .045       0  4904.6     .12       0
  5034.6    .035       0  5070.1    .045       0  6062.7    .035       0
  6064.8    .045       0  6751.6    .035       0  6871.8     .07       0
    7025    .035       0
Bank Sta=4148.3,4156.3
XS Rating Curve= 0 ,0
Exp/Cntr=0.3,0.1

Type RM Length L Ch R = 1 ,4131    ,607,607,607
BEGIN DESCRIPTION:
XS6484
END DESCRIPTION:
XS GIS Cut Line= 3
       2520081.7      13690024.5      2519267.93     13689395.18
      2516642.03       13690936.
#Sta/Elev= 30
  3187.6  270.31    3263  265.58  3455.9  259.53  3491.2  256.21  3549.1  255.86
  3605.3   251.2  3740.2  245.05  3974.9  240.23  4090.7  240.99  4132.3  240.51
  4136.5  238.69    4137  238.19  4144.5  238.69  4146.8   240.6  4161.3  241.35
  4204.8  239.43  4984.9  239.01  4999.4  240.64  5196.7  239.79  5855.7  244.65
  5862.2  244.72  5975.5  246.98  6047.9  248.73  6207.5  251.96  6325.1  254.67
  6555.6  262.31  6604.9  264.44  6787.7  273.48  6790.5  273.56  7260.9  292.46
#Mann= 14 ,-1 , 0
  3187.6    .045       0  3974.9    .035       0  4136.5    .035       0
  4144.5    .035       0  5855.7     .05       0  5862.2    .045       0
  5975.5     .05       0  6047.9    .035       0  6207.5     .05       0
  6325.1    .035       0  6555.6     .12       0  6604.9    .035       0
  6787.7     .12       0  6790.5    .035       0
Bank Sta=4136.5,4144.5
XS Rating Curve= 0 ,0
Exp/Cntr=0.3,0.1

Type RM Length L Ch R = 1 ,3524    ,827,827,827
BEGIN DESCRIPTION:
Stream0330 2.0
END DESCRIPTION:
XS GIS Cut Line= 4
      2520081.76     13689959.45      2519007.51     13689134.77
      2518464.97     13689210.72      2516392.52     13690588.74
#Sta/Elev= 30
  3049.7  264.22  3307.8  255.76  3542.5  244.39  3822.4  238.87  3949.5  237.16
  3955.8   240.2  3970.3  241.44  4117.2  238.25  4155.2  235.91  4198.7  238.05
  4234.1   236.2  4263.1  238.69  4377.3  237.34  4379.6  234.94  4380.1  234.44
  4387.6  234.94  4426.7  237.99  5218.2  236.59  5517.5  236.05  5668.5  236.28
    5721  236.36  5891.6  236.94  6499.3  241.87  6881.1  250.31  6949.4  254.56
  6989.3  253.78  7082.5  259.56  7371.1  267.11  7401.2  265.21  7440.6  267.78
#Mann= 11 ,-1 , 0
  3049.7    .045       0  3822.4    .035       0  4117.2     .05       0
  4379.6     .05       0  4387.6     .05       0  5218.2    .045       0
  5517.5     .05       0  5668.5    .045       0    5721     .05       0
  5891.6    .045       0  6949.4     .05       0
Bank Sta=4379.6,4387.6
XS Rating Curve= 0 ,0
Exp/Cntr=0.3,0.1

Type RM Length L Ch R = 1 ,2697    ,0,0,0
BEGIN DESCRIPTION:
Stream0330 1.0
END DESCRIPTION:
XS GIS Cut Line= 4
      2520980.26     13690182.82      2518790.49     13688830.95
      2517987.54     13688689.89      2516469.34     13690479.19
#Sta/Elev= 30
  1592.5  270.52  1711.2  263.98  1732.5  258.39  1753.7  257.49  1790.4  262.61
  1827.1  257.64  1915.8     258  2000.9  248.77  2016.3  250.46  2123.1  246.27
    2857  240.42  2861.5  240.43  3229.3  240.12  3447.7  238.65  4168.9  237.34
  4212.1  236.62  4228.3  235.36  4229.3  232.79  4229.8  232.29  4237.4  232.79
  4242.6  235.09  4293.4  233.83  4313.7  236.47  5846.6  234.03  6462.3  236.31
    6955  247.34  7114.7  252.98  7171.9  257.44    7207  256.01  7327.8  262.86
#Mann= 10 ,-1 , 0
  1592.5     .12       0  2123.1    .045       0    2857     .05       0
  2861.5    .045       0  3229.3    .035       0  3447.7     .05       0
  4229.3     .05       0  4237.4     .05       0  5846.6    .045       0
    6955     .05       0
Bank Sta=4229.3,4237.4
XS Rating Curve= 0 ,0
Exp/Cntr=0.3,0.1

Chan Stop Cuts=-1
Use User Specified Reach Order=0
Composite Channel Slope=5