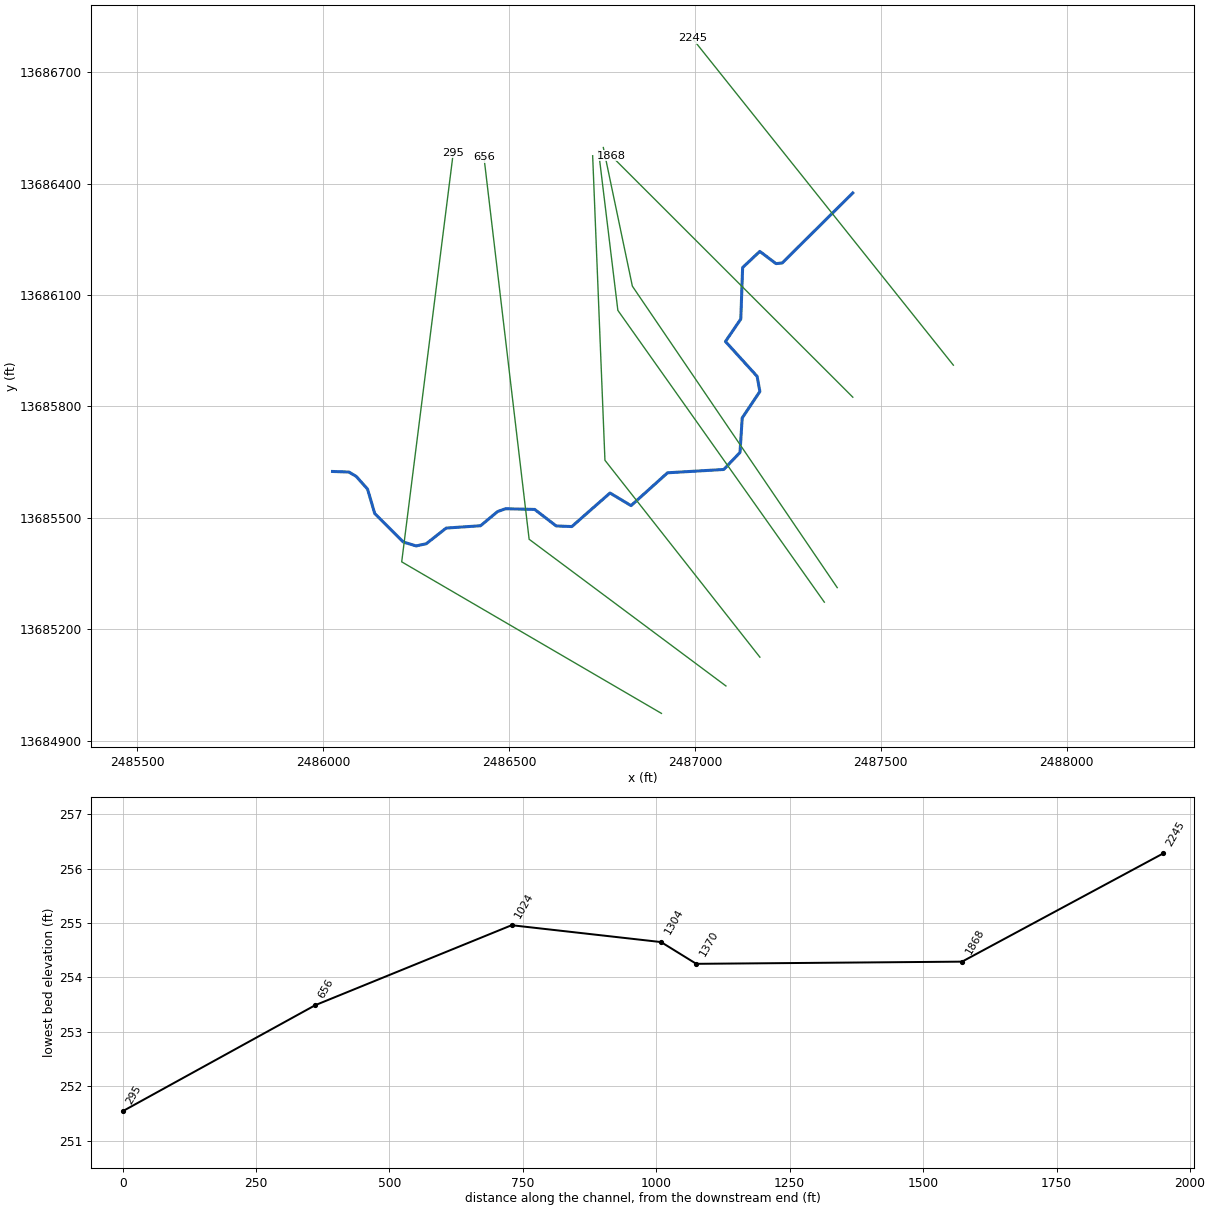
--- Stream0334.prj (project) ---

Proj Title=Stream0334 Base Level Engineering
Current Plan=p01
Default Exp/Contr=0.3,0.1
English Units
Geom File=g01
Flow File=f01
Plan File=p01
BEGIN DESCRIPTION:
Stream0334
END DESCRIPTION:

--- Stream0334.p01 (plan) ---

Plan Title=Multiple Run
Short Identifier=Multiple
Geom File=g01
Flow File=f01
Subcritical Flow
K Sum by GR= 0
Std Step Tol= 0.01
Critical Tol= 0.01
Num of Std Step Trials= 20
Max Error Tol= 0.3
Flow Tol Ratio= 0.001
Split Flow NTrial= 30
Split Flow Tol= 0.02
Split Flow Ratio= 0.02
Log Output Level= 0
Friction Slope Method= 1
Unsteady Friction Slope Method= 2
Unsteady Bridges Friction Slope Method= 1
Parabolic Critical Depth
Global Vel Dist=  1 , 1 , 1
Global Log Level= 0
CheckData=True
Encroach Param= -1, 0, 0, 0
BEGIN DESCRIPTION:
Multiple Run
END DESCRIPTION:

--- Stream0334.f01 (steady flow) ---

Flow Title=Multiple
Number of Profiles=7
Profile Names=10-year,25-year,50-year,1pct_min,100-year,1pct_plu,500-year
River Rch & RM= Stream0334,Reach-1,2245
     492     772    1018     650    1298    2589    2086
Boundary for River Rch & Prof#=Stream0334,Reach-1,1
Up Type=0
Dn Type=3
Dn Slope=0.005
Boundary for River Rch & Prof#=Stream0334,Reach-1,2
Up Type=0
Dn Type=3
Dn Slope=0.005
Boundary for River Rch & Prof#=Stream0334,Reach-1,3
Up Type=0
Dn Type=3
Dn Slope=0.005
Boundary for River Rch & Prof#=Stream0334,Reach-1,4
Up Type=0
Dn Type=3
Dn Slope=0.005
Boundary for River Rch & Prof#=Stream0334,Reach-1,5
Up Type=0
Dn Type=3
Dn Slope=0.005
Boundary for River Rch & Prof#=Stream0334,Reach-1,6
Up Type=0
Dn Type=3
Dn Slope=0.005
Boundary for River Rch & Prof#=Stream0334,Reach-1,7
Up Type=0
Dn Type=3
Dn Slope=0.005

--- Stream0334.g01 (geometry) ---

Geom Title=Existing Conditions

River Reach=Stream0334,Reach-1
Reach XY= 30
      2487425.00     13686375.00      2487234.99     13686186.25
      2487218.31     13686184.62      2487174.75     13686217.54
      2487128.54     13686174.00      2487123.60     13686035.44
      2487082.33     13685974.90      2487167.48     13685881.06
      2487174.97     13685840.42      2487127.39     13685769.03
      2487121.49     13685676.25      2487077.73     13685630.35
      2486926.47     13685621.43      2486828.33     13685533.02
      2486771.67     13685566.98      2486668.97     13685476.64
      2486626.75     13685478.35      2486569.03     13685522.81
      2486490.27     13685524.62      2486468.96     13685516.91
      2486423.40     13685478.86      2486330.97     13685472.62
      2486277.17     13685430.35      2486249.96     13685424.50
      2486215.29     13685435.18      2486138.61     13685511.76
      2486119.29     13685577.51      2486088.78     13685611.73
      2486069.13     13685623.44      2486025.00     13685625.00

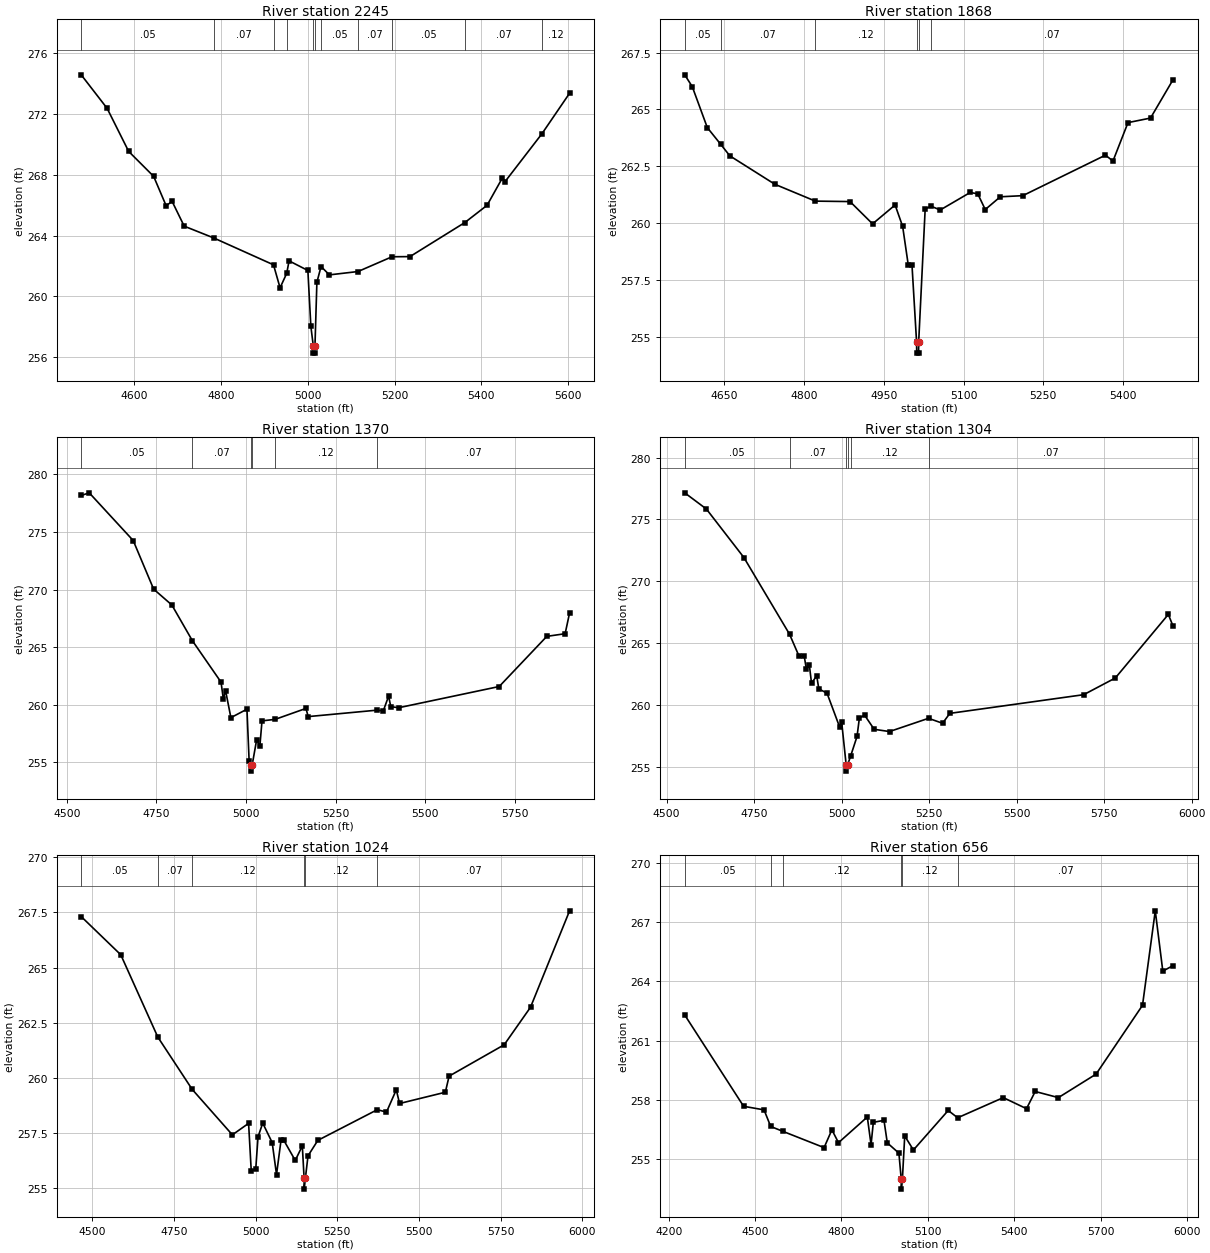
Type RM Length L Ch R = 1,2245,377,377,377
BEGIN DESCRIPTION:
XS6498
END DESCRIPTION:
XS GIS Cut Line= 2
      2487695.56     13685911.21      2486993.34     13686791.16
#Sta/Elev= 30
  4477.5  274.56  4537.2  272.36  4586.9  269.53  4644.5  267.89  4673.3  265.96
  4687.0  266.25  4714.9  264.62  4782.6  263.85  4920.8  262.08  4935.9  260.57
  4951.2  261.52  4956.7  262.34  5000.0  261.71  5006.9  258.04  5012.4  256.78
  5012.6  256.28  5016.1  256.28  5016.4  256.78  5020.8  260.93  5030.4  261.97
  5049.6  261.42  5115.6  261.64  5194.0  262.61  5235.4  262.62  5362.0  264.86
  5413.1  265.99  5448.3  267.78  5454.7  267.55  5539.6  270.69  5603.3  273.35
#Mann=11,-1,0
  4477.5    0.05       0  4782.6    0.07       0  4920.8    0.12       0
  4951.2    0.07       0  5012.4    0.05       0  5016.4    0.07       0
  5030.4    0.05       0  5115.6    0.07       0  5194.0    0.05       0
  5362.0    0.07       0  5539.6    0.12       0
Bank Sta=5012.4,5016.4
Exp/Cntr=0.3,0.1

Type RM Length L Ch R = 1,1868,498,498,498
BEGIN DESCRIPTION:
Stream0334 3.0
END DESCRIPTION:
XS GIS Cut Line= 3
      2487425.02     13685824.98      2487125.00     13686125.00
      2486774.98     13686475.02
#Sta/Elev= 30
  4575.2  266.52  4589.4  266.00  4617.7  264.20  4642.8  263.47  4660.1  262.96
  4744.9  261.71  4821.1  260.97  4886.4  260.95  4928.8  259.97  4971.2  260.80
  4985.4  259.86  4996.0  258.16  5003.0  258.16  5011.6  254.79  5011.9  254.29
  5015.4  254.29  5015.6  254.79  5027.8  260.62  5038.6  260.75  5056.1  260.58
  5112.6  261.35  5126.8  261.29  5140.9  260.60  5169.2  261.16  5211.6  261.21
  5367.2  262.99  5381.3  262.73  5409.6  264.42  5452.0  264.62  5494.5  266.31
#Mann=6,-1,0
  4575.2    0.05       0  4642.8    0.07       0  4821.1    0.12       0
  5011.6    0.05       0  5015.6    0.12       0  5038.6    0.07       0
Bank Sta=5011.6,5015.6
Exp/Cntr=0.3,0.1

Type RM Length L Ch R = 1,1370,66,66,66
BEGIN DESCRIPTION:
XS6497
END DESCRIPTION:
XS GIS Cut Line= 3
      2487383.07     13685312.25      2486831.86     13686123.87
      2486753.72     13686497.18
#Sta/Elev= 30
  4540.2  278.16  4562.6  278.39  4685.3  274.25  4742.2  270.04  4793.1  268.66
  4850.4  265.56  4930.3  261.97  4936.8  260.50  4942.9  261.24  4957.8  258.89
  5002.6  259.62  5008.7  255.11  5013.0  254.75  5013.2  254.25  5017.0  254.75
  5029.7  256.98  5038.6  256.41  5044.6  258.61  5081.2  258.74  5167.3  259.69
  5173.4  258.98  5366.0  259.54  5382.9  259.47  5397.9  260.76  5403.9  259.84
  5426.0  259.75  5706.4  261.59  5839.2  265.94  5890.3  266.17  5902.7  267.97
#Mann=6,-1,0
  4540.2    0.05       0  4850.4    0.07       0  5013.0    0.05       0
  5017.0    0.07       0  5081.2    0.12       0  5366.0    0.07       0
Bank Sta=5013,5017
Exp/Cntr=0.3,0.1

Type RM Length L Ch R = 1,1304,280,280,280
BEGIN DESCRIPTION:
XS6496
END DESCRIPTION:
XS GIS Cut Line= 3
      2487348.38     13685273.14      2486792.80     13686058.77
      2486740.71     13686488.50
#Sta/Elev= 30
  4551.9  277.15  4613.8  275.84  4720.9  271.92  4851.3  265.72  4878.5  263.94
  4893.2  263.95  4899.4  262.90  4908.0  263.20  4914.1  261.76  4928.9  262.35
  4935.0  261.30  4958.4  260.95  4994.2  258.23  5000.3  258.59  5013.1  255.15
  5013.3  254.65  5017.1  255.15  5025.7  255.86  5044.1  257.45  5050.8  258.94
  5065.6  259.18  5093.1  258.03  5136.9  257.85  5248.3  258.92  5288.4  258.52
  5309.3  259.32  5691.6  260.83  5782.0  262.18  5933.4  267.32  5947.0  266.36
#Mann=6,-1,0
  4551.9    0.05       0  4851.3    0.07       0  5013.1    0.05       0
  5017.1    0.07       0  5025.7    0.12       0  5248.3    0.07       0
Bank Sta=5013.1,5017.1
Exp/Cntr=0.3,0.1

Type RM Length L Ch R = 1,1024,368,368,368
BEGIN DESCRIPTION:
Stream0334 2.0
END DESCRIPTION:
XS GIS Cut Line= 3
      2487175.00     13685125.00      2486758.07     13685655.12
      2486725.00     13686475.02
#Sta/Elev= 30
  4466.3  267.31  4587.4  265.58  4700.8  261.85  4806.0  259.48  4929.0  257.42
  4978.7  257.94  4986.8  255.79  5000.6  255.87  5007.6  257.33  5022.0  257.95
  5050.9  257.07  5064.2  255.62  5078.1  257.19  5086.2  257.18  5121.5  256.26
  5143.2  256.92  5148.6  255.46  5148.9  254.96  5152.6  255.46  5160.6  256.47
  5190.7  257.17  5372.8  258.56  5400.8  258.45  5430.8  259.46  5440.9  258.84
  5581.0  259.35  5592.5  260.08  5761.1  261.50  5841.7  263.20  5961.3  267.57
#Mann=6,-1,0
  4466.3    0.05       0  4700.8    0.07       0  4806.0    0.12       0
  5148.6    0.05       0  5152.6    0.12       0  5372.8    0.07       0
Bank Sta=5148.6,5152.6
Exp/Cntr=0.3,0.1

Type RM Length L Ch R = 1,656,361,361,361
BEGIN DESCRIPTION:
XS6495
END DESCRIPTION:
XS GIS Cut Line= 3
      2487083.60     13685047.48      2486554.08     13685442.45
      2486432.62     13686470.50
#Sta/Elev= 30
  4255.7  262.30  4460.2  257.68  4531.1  257.50  4554.2  256.66  4597.1  256.41
  4739.6  255.59  4766.7  256.49  4789.6  255.84  4889.7  257.14  4902.7  255.74
  4910.6  256.87  4947.6  256.97  4959.1  255.83  4999.4  255.31  5007.5  253.99
  5007.7  253.49  5011.5  253.99  5019.6  256.18  5049.8  255.47  5170.6  257.47
  5203.4  257.10  5361.9  258.12  5442.5  257.56  5472.7  258.43  5553.2  258.12
  5684.2  259.31  5845.3  262.79  5889.6  267.57  5915.8  264.52  5951.5  264.80
#Mann=6,-1,0
  4255.7    0.05       0  4554.2    0.07       0  4597.1    0.12       0
  5007.5    0.05       0  5011.5    0.12       0  5203.4    0.07       0
Bank Sta=5007.5,5011.5
Exp/Cntr=0.3,0.1

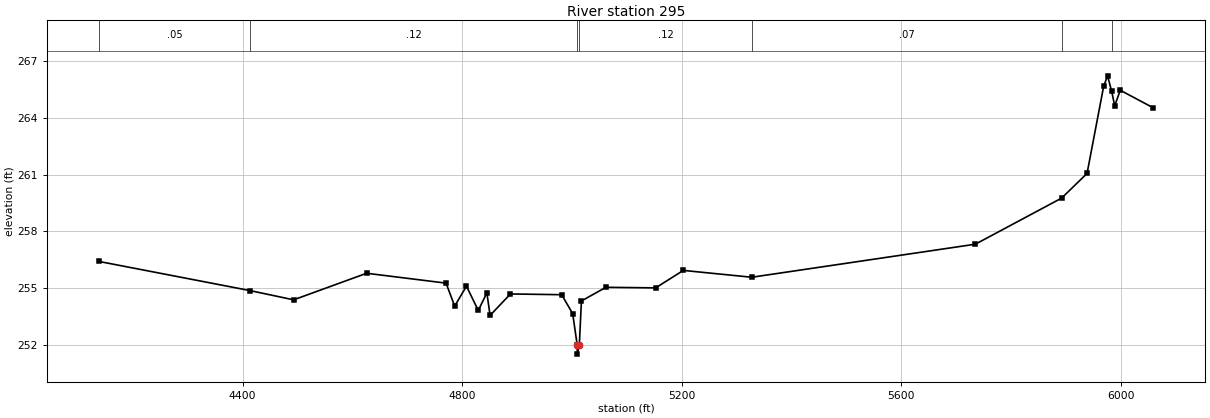
Type RM Length L Ch R = 1,295,0,0,0
BEGIN DESCRIPTION:
Stream0334 1.0
END DESCRIPTION:
XS GIS Cut Line= 3
      2486910.01     13684973.68      2486211.20     13685381.68
      2486350.04     13686483.78
#Sta/Elev= 30
  4138.7  256.42  4413.0  254.89  4493.0  254.40  4626.1  255.80  4770.8  255.28
  4786.5  254.07  4808.0  255.12  4829.5  253.84  4845.2  254.77  4851.0  253.58
  4888.2  254.71  4981.5  254.67  5001.6  253.67  5009.7  252.04  5010.0  251.54
  5013.7  252.04  5017.5  254.34  5062.1  255.06  5152.8  255.03  5203.2  255.95
  5327.9  255.59  5735.4  257.33  5892.7  259.76  5939.0  261.06  5969.2  265.64
  5976.3  266.20  5983.8  265.39  5989.4  264.62  5999.5  265.44  6058.7  264.53
#Mann=7,-1,0
  4138.7    0.05       0  4413.0    0.12       0  5009.7    0.05       0
  5013.7    0.12       0  5327.9    0.07       0  5892.7    0.12       0
  5983.8    0.07       0
Bank Sta=5009.7,5013.7
Exp/Cntr=0.3,0.1

Chan Stop Cuts=-1