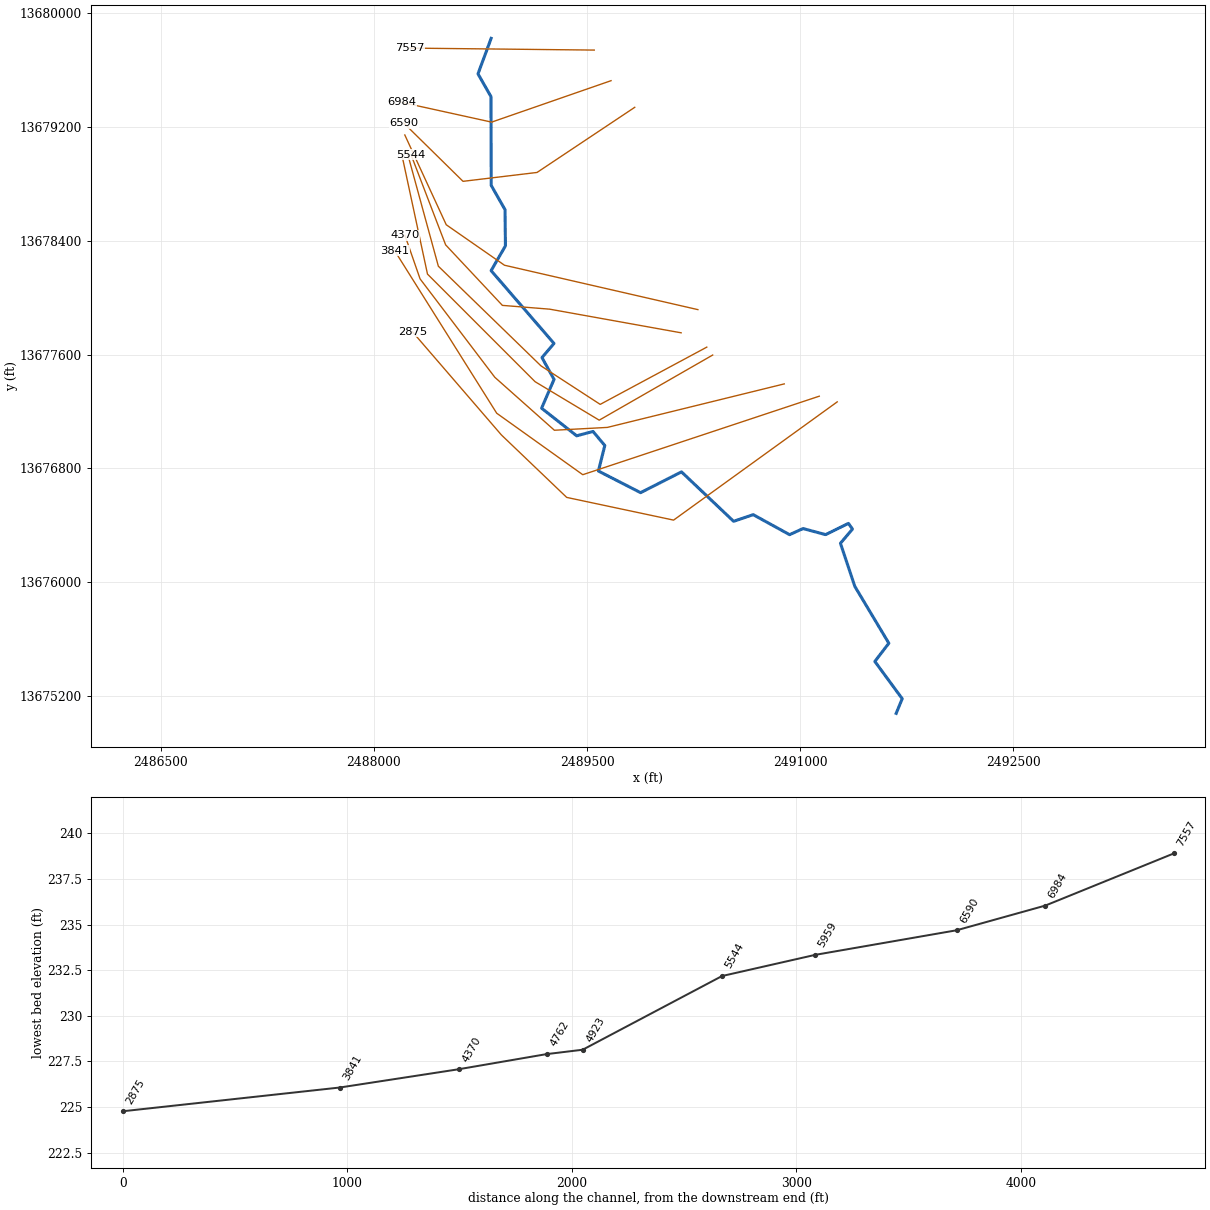
--- Stream0336.prj (project) ---

Proj Title=Stream0336 Base Level Engineering
Current Plan=p01
Default Exp/Contr=0.3,0.1
English Units
Geom File=g01
Flow File=f01
Plan File=p01
BEGIN DESCRIPTION:
Stream0336
END DESCRIPTION:

--- Stream0336.p01 (plan) ---

Plan Title=Multiple Run
Short Identifier=Multiple
Geom File=g01
Flow File=f01
Subcritical Flow
K Sum by GR= 0
Std Step Tol= 0.01
Critical Tol= 0.01
Num of Std Step Trials= 20
Max Error Tol= 0.3
Flow Tol Ratio= 0.001
Split Flow NTrial= 30
Split Flow Tol= 0.02
Split Flow Ratio= 0.02
Log Output Level= 0
Friction Slope Method= 1
Unsteady Friction Slope Method= 2
Unsteady Bridges Friction Slope Method= 1
Parabolic Critical Depth
Global Vel Dist=  1 , 1 , 1
Global Log Level= 0
CheckData=True
Encroach Param= -1, 0, 0, 0
BEGIN DESCRIPTION:
Multiple Run
END DESCRIPTION:

--- Stream0336.f01 (steady flow) ---

Flow Title=Multiple
Number of Profiles=7
Profile Names=10-year,25-year,50-year,1pct_min,100-year,1pct_plu,500-year
River Rch & RM= Stream0336,Reach-1,7557
     688    1108    1486     966    1927    3845    3206
River Rch & RM= Stream0336,Reach-1,4923
     816    1320    1776    1156    2306    4602    3852
Boundary for River Rch & Prof#=Stream0336,Reach-1,1
Up Type=0
Dn Type=3
Dn Slope=0.005
Boundary for River Rch & Prof#=Stream0336,Reach-1,2
Up Type=0
Dn Type=3
Dn Slope=0.005
Boundary for River Rch & Prof#=Stream0336,Reach-1,3
Up Type=0
Dn Type=3
Dn Slope=0.005
Boundary for River Rch & Prof#=Stream0336,Reach-1,4
Up Type=0
Dn Type=3
Dn Slope=0.005
Boundary for River Rch & Prof#=Stream0336,Reach-1,5
Up Type=0
Dn Type=3
Dn Slope=0.005
Boundary for River Rch & Prof#=Stream0336,Reach-1,6
Up Type=0
Dn Type=3
Dn Slope=0.005
Boundary for River Rch & Prof#=Stream0336,Reach-1,7
Up Type=0
Dn Type=3
Dn Slope=0.005

--- Stream0336.g01 (geometry) ---

Geom Title=Existing Conditions

River Reach=Stream0336,Reach-1
Reach XY= 30
      2488825.00     13679825.00      2488732.50     13679575.00
      2488823.80     13679414.50      2488825.51     13678790.21
      2488922.76     13678619.07      2488925.50     13678364.79
      2488824.90     13678190.36      2489267.15     13677678.23
      2489182.80     13677578.41      2489267.50     13677425.00
      2489179.98     13677222.45      2489426.65     13677028.16
      2489541.74     13677058.71      2489624.76     13676959.80
      2489579.62     13676780.25      2489876.65     13676628.11
      2490164.31     13676774.26      2490531.03     13676426.62
      2490668.89     13676473.20      2490924.99     13676332.53
      2491019.83     13676375.46      2491178.41     13676332.81
      2491339.05     13676411.89      2491367.46     13676371.90
      2491282.85     13676271.77      2491384.17     13675968.28
      2491623.40     13675568.49      2491524.88     13675440.42
      2491717.40     13675178.38      2491675.00     13675075.00

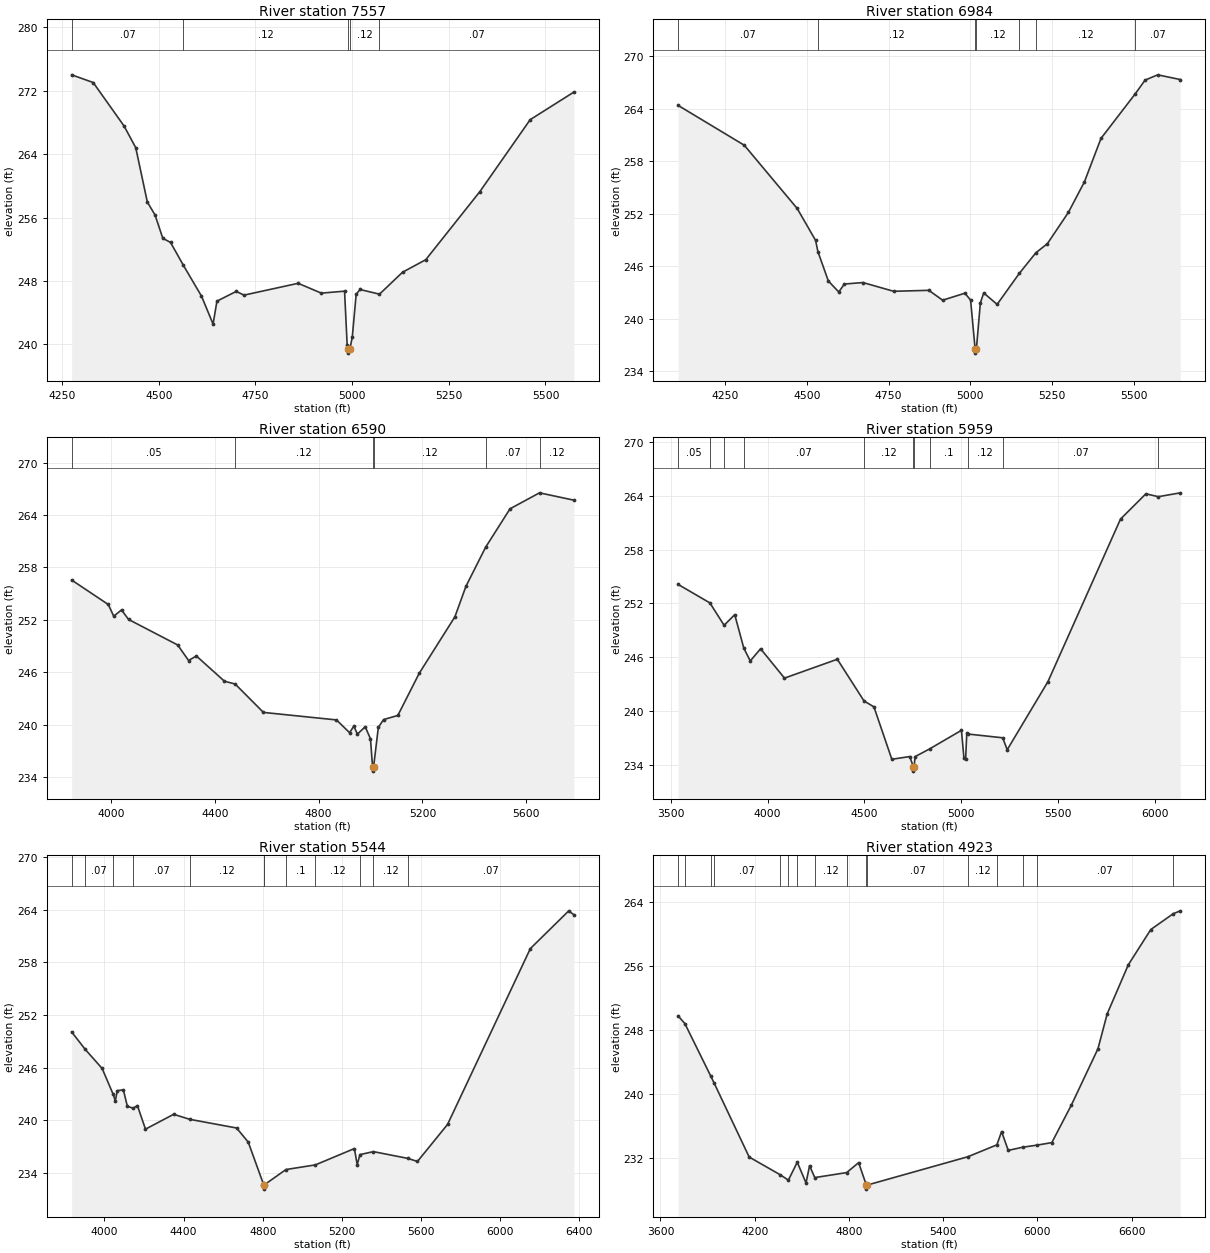
Type RM Length L Ch R = 1,7557,573,573,573
BEGIN DESCRIPTION:
XS6505
END DESCRIPTION:
XS GIS Cut Line= 2
      2489550.65     13679742.36      2488252.12     13679756.25
#Sta/Elev= 30
  4274.8  274.02  4330.5  273.05  4410.5  267.55  4440.5  264.83  4470.5  257.97
  4490.5  256.33  4510.5  253.39  4530.5  252.87  4564.0  249.96  4610.5  246.10
  4640.5  242.57  4650.5  245.46  4700.5  246.69  4720.5  246.22  4860.5  247.71
  4920.5  246.47  4980.5  246.72  4987.3  239.90  4990.3  239.40  4990.5  238.90
  4994.3  239.40  5000.5  240.93  5010.5  246.32  5020.5  246.93  5070.8  246.34
  5130.5  249.11  5190.5  250.69  5330.5  259.29  5460.5  268.36  5573.4  271.84
#Mann=5,-1,0
  4274.8    0.07       0  4564.0    0.12       0  4990.3    0.05       0
  4994.3    0.12       0  5070.8    0.07       0
Bank Sta=4990.3,4994.3
Exp/Cntr=0.3,0.1

Type RM Length L Ch R = 1,6984,394,394,394
BEGIN DESCRIPTION:
XS6504
END DESCRIPTION:
XS GIS Cut Line= 3
      2489668.75     13679527.08      2488828.47     13679235.42
      2488198.27     13679373.92
#Sta/Elev= 30
  4107.0  264.40  4309.2  259.84  4470.9  252.60  4527.1  248.95  4534.3  247.65
  4566.1  244.30  4597.9  243.04  4615.1  243.95  4672.0  244.12  4765.5  243.12
  4873.1  243.23  4915.4  242.10  4983.4  242.90  5000.8  242.11  5014.6  236.54
  5014.8  236.04  5018.6  236.54  5030.7  241.80  5041.0  242.93  5081.9  241.62
  5149.7  245.17  5200.6  247.54  5235.5  248.57  5299.7  252.15  5348.6  255.64
  5399.3  260.62  5504.1  265.73  5533.9  267.29  5572.5  267.90  5641.7  267.36
#Mann=7,-1,0
  4107.0    0.07       0  4534.3    0.12       0  5014.6    0.05       0
  5018.6    0.12       0  5149.7    0.07       0  5200.6    0.12       0
  5504.1    0.07       0
Bank Sta=5014.6,5018.6
Exp/Cntr=0.3,0.1

Type RM Length L Ch R = 1,6590,631,631,631
BEGIN DESCRIPTION:
XS6503
END DESCRIPTION:
XS GIS Cut Line= 4
      2489835.44     13679339.60      2489147.92     13678881.25
      2488627.08     13678818.75      2488210.44     13679228.45
#Sta/Elev= 30
  3848.2  256.56  3989.3  253.76  4010.4  252.42  4040.4  253.14  4067.4  252.05
  4256.7  249.13  4298.8  247.35  4328.8  247.87  4437.0  244.98  4478.3  244.66
  4587.2  241.41  4868.8  240.55  4919.2  239.09  4935.5  239.83  4949.4  238.93
  4979.6  239.77  4999.7  238.38  5007.8  235.19  5008.1  234.69  5011.8  235.19
  5030.0  239.69  5050.1  240.59  5105.1  241.06  5187.3  245.87  5325.2  252.36
  5367.6  255.84  5443.4  260.31  5537.4  264.71  5651.1  266.54  5783.4  265.70
#Mann=6,-1,0
  3848.2    0.05       0  4478.3    0.12       0  5007.8    0.05       0
  5011.8    0.12       0  5443.4    0.07       0  5651.1    0.12       0
Bank Sta=5007.8,5011.8
Exp/Cntr=0.3,0.1

Type RM Length L Ch R = 1,5959,415,415,415
BEGIN DESCRIPTION:
XS6502
END DESCRIPTION:
XS GIS Cut Line= 4
      2490279.84     13677915.98      2488918.75     13678228.47
      2488509.03     13678513.19      2488217.38     13679145.10
#Sta/Elev= 30
  3538.4  254.12  3702.3  252.06  3775.7  249.57  3830.6  250.75  3877.3  247.03
  3910.7  245.60  3964.0  246.96  4087.2  243.69  4359.9  245.79  4497.7  241.15
  4548.9  240.49  4641.2  234.66  4733.5  234.96  4752.1  233.84  4752.3  233.34
  4756.1  233.84  4761.1  234.95  4838.3  235.84  5000.4  237.88  5013.1  234.84
  5021.9  234.66  5028.0  237.56  5033.4  237.47  5213.1  237.05  5236.6  235.72
  5446.8  243.30  5821.3  261.39  5952.2  264.20  6016.3  263.88  6129.8  264.31
#Mann=11,-1,0
  3538.4    0.05       0  3702.3    0.07       0  3775.7   0.035       0
  3877.3    0.07       0  4497.7    0.12       0  4752.1    0.05       0
  4756.1    0.12       0  4838.3     0.1       0  5033.4    0.12       0
  5213.1    0.07       0  6016.3    0.12       0
Bank Sta=4752.1,4756.1
Exp/Cntr=0.3,0.1

Type RM Length L Ch R = 1,5544,621,621,621
BEGIN DESCRIPTION:
E20899
END DESCRIPTION:
XS GIS Cut Line= 5
      2490161.99     13677752.85      2489236.80     13677919.25
      2488903.99     13677945.88      2488504.63     13678371.86
      2488261.43     13679005.47
#Sta/Elev= 30
  3835.0  250.08  3903.3  248.10  3988.9  245.92  4045.1  242.96  4055.5  242.23
  4065.6  243.39  4096.1  243.49  4116.4  241.61  4145.6  241.40  4167.2  241.69
  4207.9  239.01  4350.1  240.70  4431.2  240.13  4668.2  239.14  4727.0  237.53
  4804.9  232.68  4805.2  232.18  4808.9  232.68  4917.3  234.41  5066.2  234.94
  5263.1  236.80  5277.3  234.96  5291.2  236.11  5359.2  236.45  5533.1  235.68
  5581.6  235.33  5733.7  239.55  6151.8  259.57  6345.9  263.87  6371.5  263.42
#Mann=12,-1,0
  3835.0    0.05       0  3903.3    0.07       0  4045.1   0.035       0
  4145.6    0.07       0  4431.2    0.12       0  4804.9    0.05       0
  4808.9    0.12       0  4917.3     0.1       0  5066.2    0.12       0
  5291.2    0.07       0  5359.2    0.12       0  5533.1    0.07       0
Bank Sta=4804.9,4808.9
Exp/Cntr=0.3,0.1

Type RM Length L Ch R = 1,4923,161,161,161
BEGIN DESCRIPTION:
XS6501
END DESCRIPTION:
XS GIS Cut Line= 5
      2490342.36     13677652.08      2489592.36     13677249.31
      2489175.69     13677520.14      2488453.47     13678221.53
      2488231.24     13679034.07
#Sta/Elev= 30
  3712.4  249.74  3755.1  248.79  3920.8  242.21  3942.1  241.35  4164.9  232.14
  4360.9  229.95  4414.4  229.26  4471.0  231.50  4526.7  228.91  4549.4  231.06
  4582.5  229.58  4785.4  230.20  4861.6  231.44  4910.9  228.64  4911.2  228.14
  4915.1  228.64  5557.6  232.18  5741.8  233.66  5771.9  235.31  5814.3  232.97
  5907.3  233.37  5995.9  233.62  6091.7  233.94  6216.2  238.62  6385.5  245.64
  6444.2  249.99  6579.0  256.12  6722.0  260.51  6864.8  262.48  6909.8  262.84
#Mann=16,-1,0
  3712.4    0.05       0  3755.1    0.07       0  3920.8    0.05       0
  3942.1    0.07       0  4360.9   0.035       0  4414.4    0.07       0
  4471.0   0.035       0  4582.5    0.12       0  4785.4    0.07       0
  4910.9    0.05       0  4915.1    0.07       0  5557.6    0.12       0
  5741.8    0.07       0  5907.3    0.12       0  5995.9    0.07       0
  6864.8    0.12       0
Bank Sta=4910.9,4915.1
Exp/Cntr=0.3,0.1

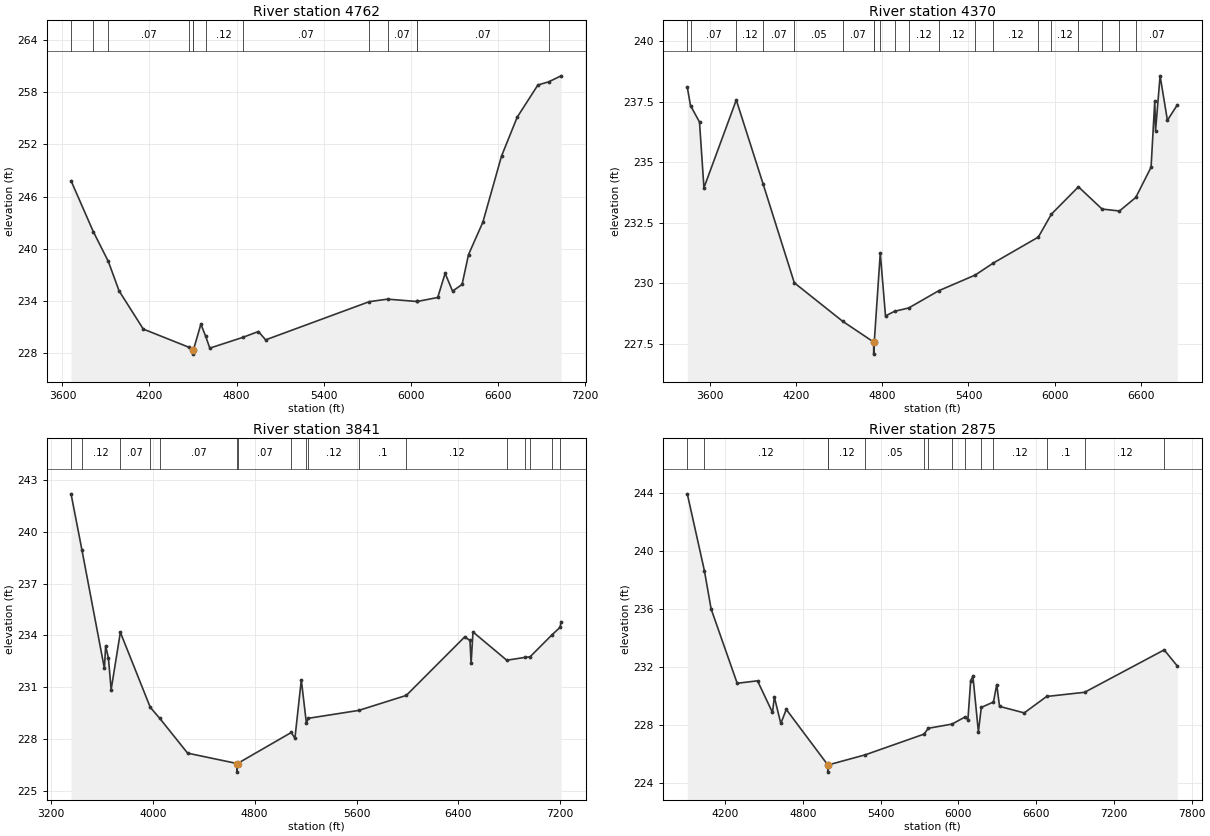
Type RM Length L Ch R = 1,4762,392,392,392
BEGIN DESCRIPTION:
XS6500
END DESCRIPTION:
XS GIS Cut Line= 5
      2490384.07     13677596.55      2489585.42     13677138.19
      2489134.03     13677409.03      2488377.08     13678165.97
      2488196.52     13679006.27
#Sta/Elev= 30
  3659.4  247.83  3812.5  241.99  3916.4  238.55  3990.5  235.17  4157.3  230.78
  4474.7  228.67  4498.9  228.40  4499.2  227.90  4503.1  228.40  4554.2  231.35
  4586.6  229.98  4615.7  228.59  4842.2  229.82  4950.6  230.50  5000.5  229.54
  5714.6  233.93  5840.4  234.22  6044.4  233.95  6044.6  233.95  6186.4  234.41
  6237.5  237.19  6288.6  235.14  6354.4  235.91  6398.6  239.34  6497.4  243.06
  6626.2  250.67  6734.0  255.13  6877.0  258.84  6951.5  259.20  7036.6  259.89
#Mann=13,-1,0
  3659.4    0.07       0  3812.5    0.05       0  3916.4    0.07       0
  4474.7   0.035       0  4498.9    0.05       0  4503.1   0.035       0
  4586.6    0.12       0  4842.2    0.07       0  5714.6    0.12       0
  5840.4    0.07       0  6044.4    0.12       0  6044.6    0.07       0
  6951.5    0.12       0
Bank Sta=4498.9,4503.1
Exp/Cntr=0.3,0.1

Type RM Length L Ch R = 1,4370,529,529,529
BEGIN DESCRIPTION:
E20898
END DESCRIPTION:
XS GIS Cut Line= 6
      2490887.54     13677393.43      2489642.82     13677087.25
      2489270.08     13677067.28      2488850.75     13677440.02
      2488324.92     13678132.25      2488218.44     13678438.38
#Sta/Elev= 30
  3442.1  238.11  3464.5  237.35  3527.1  236.67  3558.0  233.95  3783.2  237.58
  3970.9  234.09  4187.2  230.02  4523.6  228.43  4739.7  227.57  4740.0  227.07
  4743.9  227.57  4785.8  231.25  4822.2  228.65  4884.9  228.84  4983.9  228.98
  5192.2  229.69  5446.6  230.34  5573.4  230.84  5886.1  231.91  5977.4  232.86
  6165.5  233.99  6330.1  233.07  6451.2  232.99  6564.8  233.55  6671.3  234.80
  6697.1  237.55  6702.4  236.31  6734.1  238.58  6785.1  236.74  6854.1  237.38
#Mann=20,-1,0
  3442.1    0.05       0  3464.5    0.07       0  3783.2    0.12       0
  3970.9    0.07       0  4187.2    0.05       0  4523.6    0.07       0
  4739.7    0.05       0  4743.9    0.07       0  4785.8   0.035       0
  4884.9    0.07       0  4983.9    0.12       0  5192.2    0.12       0
  5446.6     0.1       0  5573.4    0.12       0  5886.1    0.07       0
  5977.4    0.12       0  6165.5    0.07       0  6330.1    0.12       0
  6451.2    0.12       0  6564.8    0.07       0
Bank Sta=4739.7,4743.9
Exp/Cntr=0.3,0.1

Type RM Length L Ch R = 1,3841,966,966,966
BEGIN DESCRIPTION:
E20897
END DESCRIPTION:
XS GIS Cut Line= 4
      2491133.77     13677306.89      2489469.76     13676754.44
      2488864.06     13677187.09      2488145.84     13678330.92
#Sta/Elev= 30
  3358.0  242.21  3443.9  238.94  3620.1  232.08  3629.6  233.38  3651.7  232.69
  3672.8  230.85  3745.3  234.18  3980.0  229.83  4054.5  229.19  4273.6  227.17
  4661.1  226.57  4661.4  226.07  4665.4  226.57  5087.6  228.37  5116.1  228.03
  5166.3  231.42  5206.3  228.90  5220.3  229.19  5617.5  229.65  5990.9  230.52
  6447.9  233.90  6490.8  233.72  6499.7  232.37  6514.4  234.20  6779.7  232.56
  6919.6  232.72  6962.8  232.76  7137.2  234.05  7198.7  234.47  7206.3  234.79
#Mann=17,-1,0
  3358.0    0.07       0  3443.9    0.12       0  3745.3    0.07       0
  3980.0    0.12       0  4054.5    0.07       0  4661.1    0.05       0
  4665.4    0.07       0  5087.6   0.035       0  5206.3    0.05       0
  5220.3    0.12       0  5617.5     0.1       0  5990.9    0.12       0
  6779.7    0.07       0  6919.6    0.12       0  6962.8    0.07       0
  7137.2    0.12       0  7198.7    0.07       0
Bank Sta=4661.1,4665.4
Exp/Cntr=0.3,0.1

Type RM Length L Ch R = 1,2875,0,0,0
BEGIN DESCRIPTION:
E20896
END DESCRIPTION:
XS GIS Cut Line= 5
      2491260.25     13677266.97      2490108.74     13676434.95
      2489356.61     13676594.70      2488897.34     13677034.00
      2488271.69     13677759.49
#Sta/Elev= 30
  3906.4  243.94  4038.4  238.65  4090.4  236.01  4291.6  230.89  4448.6  231.06
  4563.9  228.88  4578.6  229.94  4628.4  228.12  4670.6  229.09  4990.9  225.27
  4991.2  224.77  4995.4  225.27  5279.6  225.96  5734.5  227.39  5766.7  227.79
  5950.6  228.08  6052.8  228.58  6072.7  228.37  6094.2  231.08  6111.6  231.37
  6153.7  227.54  6176.2  229.23  6270.1  229.60  6295.3  230.80  6316.7  229.30
  6507.6  228.85  6680.1  229.98  6973.8  230.27  7587.9  233.19  7689.5  232.08
#Mann=14,-1,0
  3906.4    0.07       0  4038.4    0.12       0  4990.9    0.05       0
  4995.4    0.12       0  5279.6    0.05       0  5734.5    0.07       0
  5766.7    0.05       0  5950.6    0.07       0  6052.8   0.035       0
  6176.2    0.05       0  6270.1    0.12       0  6680.1     0.1       0
  6973.8    0.12       0  7587.9    0.07       0
Bank Sta=4990.9,4995.4
Exp/Cntr=0.3,0.1

Chan Stop Cuts=-1