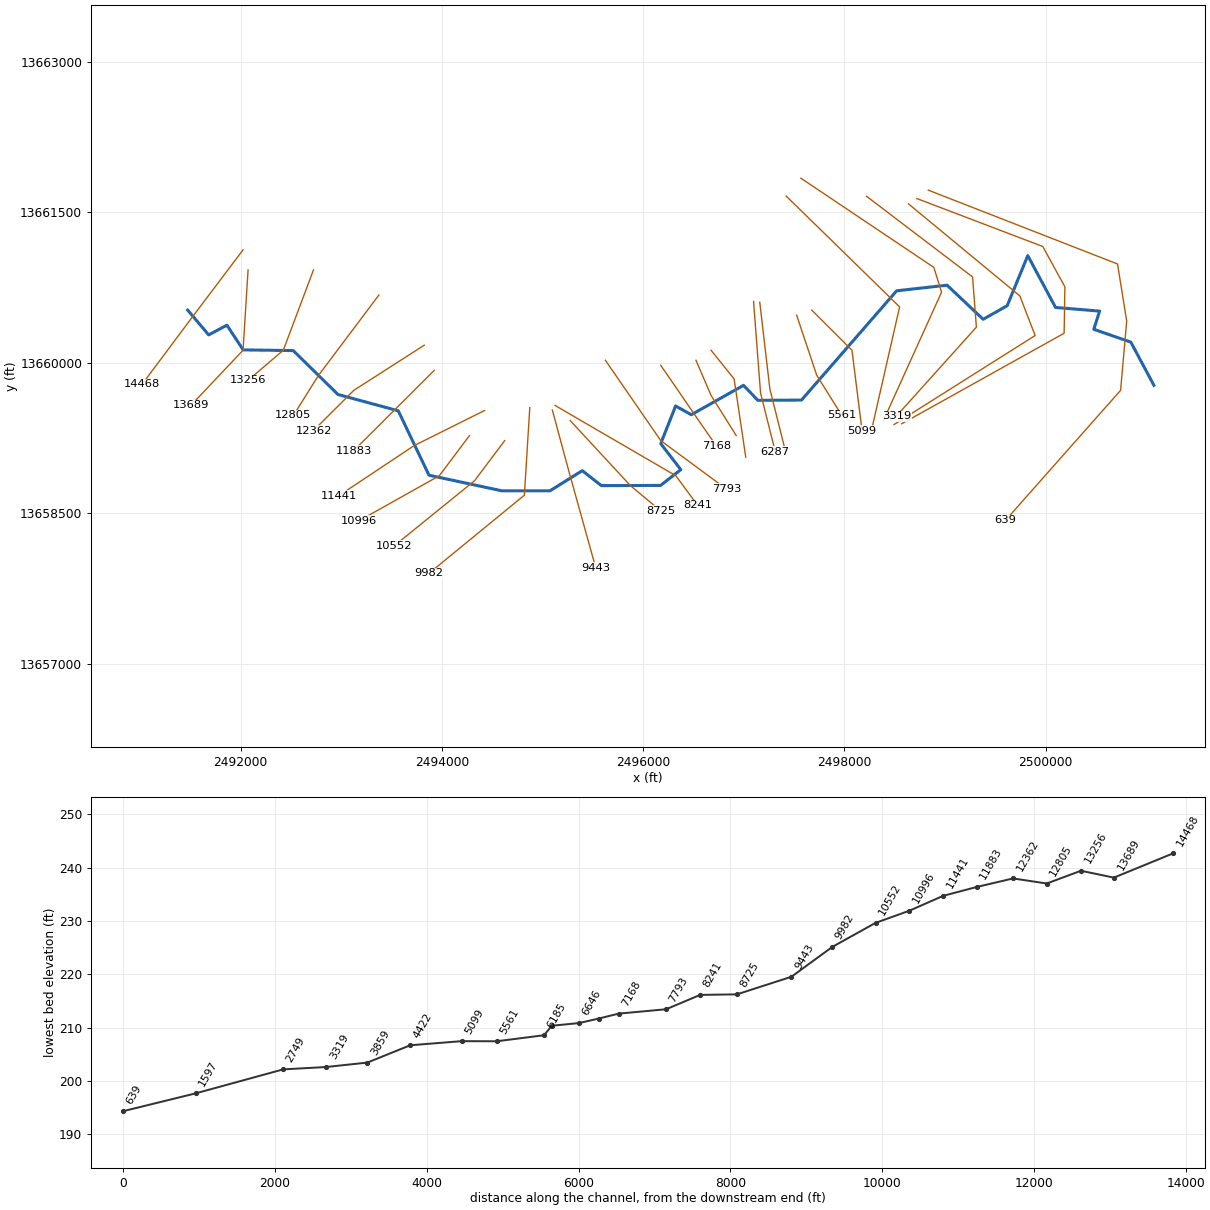
--- Stream0339.prj (project) ---

Proj Title=Stream0339 Base Level Engineering
Current Plan=p01
Default Exp/Contr=0.3,0.1
English Units
Geom File=g01
Flow File=f01
Plan File=p01
Y Axis Title=Elevation
X Axis Title(PF)=Main Channel Distance
X Axis Title(XS)=Station
BEGIN DESCRIPTION:
Stream0339
END DESCRIPTION:
DSS Export Rating Curves= 0
DSS Export Rating Curve Sorted= 0
DSS Export Volume Flow Curves= 0
DXF OffsetX= 0
DXF OffsetY= 0
DXF ScaleX= 1
DXF ScaleY= 10

--- Stream0339.p01 (plan) ---

Plan Title=Multiple Run
Program Version=4.10
Short Identifier=Multiple
Geom File=g01
Flow File=f01
Subcritical Flow
K Sum by GR= 0
Std Step Tol= 0.01
Critical Tol= 0.01
Num of Std Step Trials= 20
Max Error Tol= 0.3
Flow Tol Ratio= 0.001
Split Flow NTrial= 30
Split Flow Tol= 0.02
Split Flow Ratio= 0.02
Log Output Level= 0
Friction Slope Method= 1
Unsteady Friction Slope Method= 2
Unsteady Bridges Friction Slope Method= 1
Parabolic Critical Depth
Global Vel Dist= 1 , 1 , 1
Global Log Level= 0
CheckData=True
Encroach Param=-1 ,0,0, 0
BEGIN DESCRIPTION:
Multiple Run
END DESCRIPTION:
Computation Interval=1HOUR
Output Interval=1HOUR
Run HTab= 0
Run UNet= 0
Run PostProcess= 0
Run WQNet= 0
UNET Theta= 1
UNET Theta Warmup= 1
UNET ZTol= 0.02
UNET ZSATol= 0.05
UNET MxIter= 20
UNET MaxInSteps= 0
UNET DtIC= 0
UNET DtMin= 0
UNET MaxCRTS= 20
UNET WFStab= 2
UNET SFStab= 1
UNET WFX= 1
UNET SFX= 1
UNET DSS MLevel= 4
UNET DZMax Abort= 100
UNET Convert EG Bridges= 0
UNET Use Existing IB Tables=-1
UNET Froude Reduction=False
UNET Froude Limit= 1
UNET Froude Power= 10
UNET Time Slicing=0,0, 5
UNET Junction Losses=0
Instantaneous Interval=1HOUR
Write IC File= 0
Write IC File at Sim End=0
Echo Input=False
Echo Parameters=False
Echo Output=False
Write Detailed= 0
WQ AD Non Conservative
WQ ULTIMATE=-1
WQ Max Comp Step=1HOUR
WQ Output Interval=15MIN
WQ Output Selected Increments= 0
WQ Output face flow=0
WQ Output face velocity=0
WQ Output face area=0
WQ Output face dispersion=0
WQ Output cell volume=0
WQ Output cell surface area=0
WQ Output cell continuity=0
WQ Output cumulative cell continuity=0
WQ Output face conc=0
WQ Output face dconc_dx=0
WQ Output face courant=0
WQ Output face peclet=0
WQ Output face adv mass=0
WQ Output face disp mass=0
WQ Output cell mass=0
WQ Output cell source sink temp=0
WQ Output cell source sink nsm=0
WQ Output MaxMinRange=-1
WQ Daily Max Min Mean=-1
WQ Daily Range=0
WQ Daily Time=0
WQ Create Restart=0
WQ Fixed Restart=0
WQ System Summary=0
WQ Use Fixed Temperature=0
Sorting and Armoring Iterations= 10
XS Update Threshold= 0.02
Hydraulics Update Threshold= 0.02
Energy Slope Method= 1
Volume Change Method= 0
XS Weighting Method= 0
Number of US Weighted Cross Sections= 1
Number of DS Weighted Cross Sections= 1
Upstream XS Weight=0.25
Main XS Weight=0.5
Downstream XS Weight=0.25
Number of DS XS's Weighted with US Boundary= 1
Upstream Boundary Weight= 1
Weight of XSs Associated with US Boundary= 0
Number of US XS's Weighted with DS Boundary= 1
Downstream Boundary Weight= 0.5
Weight of XSs Associated with DS Boundary= 0.5
Sediment Output Level= 4
Mass or Volume Output= 0
Output Increment Type= 1
Profile and TS Output Increment= 10
XS Output Flag= 0
XS Output Increment= 10
Disregard all LS=0
Disregard all Conn=0
Disregard all Breaches=0
Disregard all Pumps=0

--- Stream0339.f01 (steady flow) ---

Flow Title=Multiple
Number of Profiles=7
Profile Names=10-year,25-year,50-year,1pct_min,100-year,1pct_plu,500-year
River Rch & RM= Stream0339,Reach-1,14468
     880    1444    1963    1292    2578    5143    4401
River Rch & RM= Stream0339,Reach-1,13256
     915    1497    2030    1332    2657    5302    4510
River Rch & RM= Stream0339,Reach-1,9443
    1347    2251    3097    2059    4108    8196    7162
River Rch & RM= Stream0339,Reach-1,7793
    1422    2371    3257    2160    4310    8599    7479
River Rch & RM= Stream0339,Reach-1,1597
    1753    2947    4068    2709    5405   10784    9460
Boundary for River Rch & Prof#=Stream0339,Reach-1,1
Up Type=0
Dn Type=3
Dn Slope=0.005
Boundary for River Rch & Prof#=Stream0339,Reach-1,2
Up Type=0
Dn Type=3
Dn Slope=0.005
Boundary for River Rch & Prof#=Stream0339,Reach-1,3
Up Type=0
Dn Type=3
Dn Slope=0.005
Boundary for River Rch & Prof#=Stream0339,Reach-1,4
Up Type=0
Dn Type=3
Dn Slope=0.005
Boundary for River Rch & Prof#=Stream0339,Reach-1,5
Up Type=0
Dn Type=3
Dn Slope=0.005
Boundary for River Rch & Prof#=Stream0339,Reach-1,6
Up Type=0
Dn Type=3
Dn Slope=0.005
Boundary for River Rch & Prof#=Stream0339,Reach-1,7
Up Type=0
Dn Type=3
Dn Slope=0.005

--- Stream0339.g01 (geometry) ---

Geom Title=Existing Conditions
Program Version=4.10

River Reach=Stream0339      ,Reach-1
Reach XY= 30
        2491475.       13660525.       2491683.5     13660277.59
      2491864.51     13660374.51      2492026.25     13660128.45
       2492523.5     13660121.39      2492968.26     13659684.13
      2493567.01     13659521.77      2493872.29     13658880.41
       2494595.1      13658724.9        2495075.       13658725.
      2495395.27     13658925.39      2495585.53     13658776.08
      2496173.45     13658778.75      2496374.46     13658935.63
      2496174.96     13659194.98      2496322.71     13659569.93
      2496478.35     13659482.59      2496997.84     13659775.48
      2497139.71     13659625.87       2497573.5     13659628.46
      2498518.93     13660716.87      2499019.73     13660772.88
      2499378.31     13660433.02      2499617.31     13660568.52
      2499821.66     13661067.42      2500097.66     13660550.95
      2500535.56     13660514.52      2500477.58     13660333.48
      2500845.64     13660205.59        2501075.       13659775.

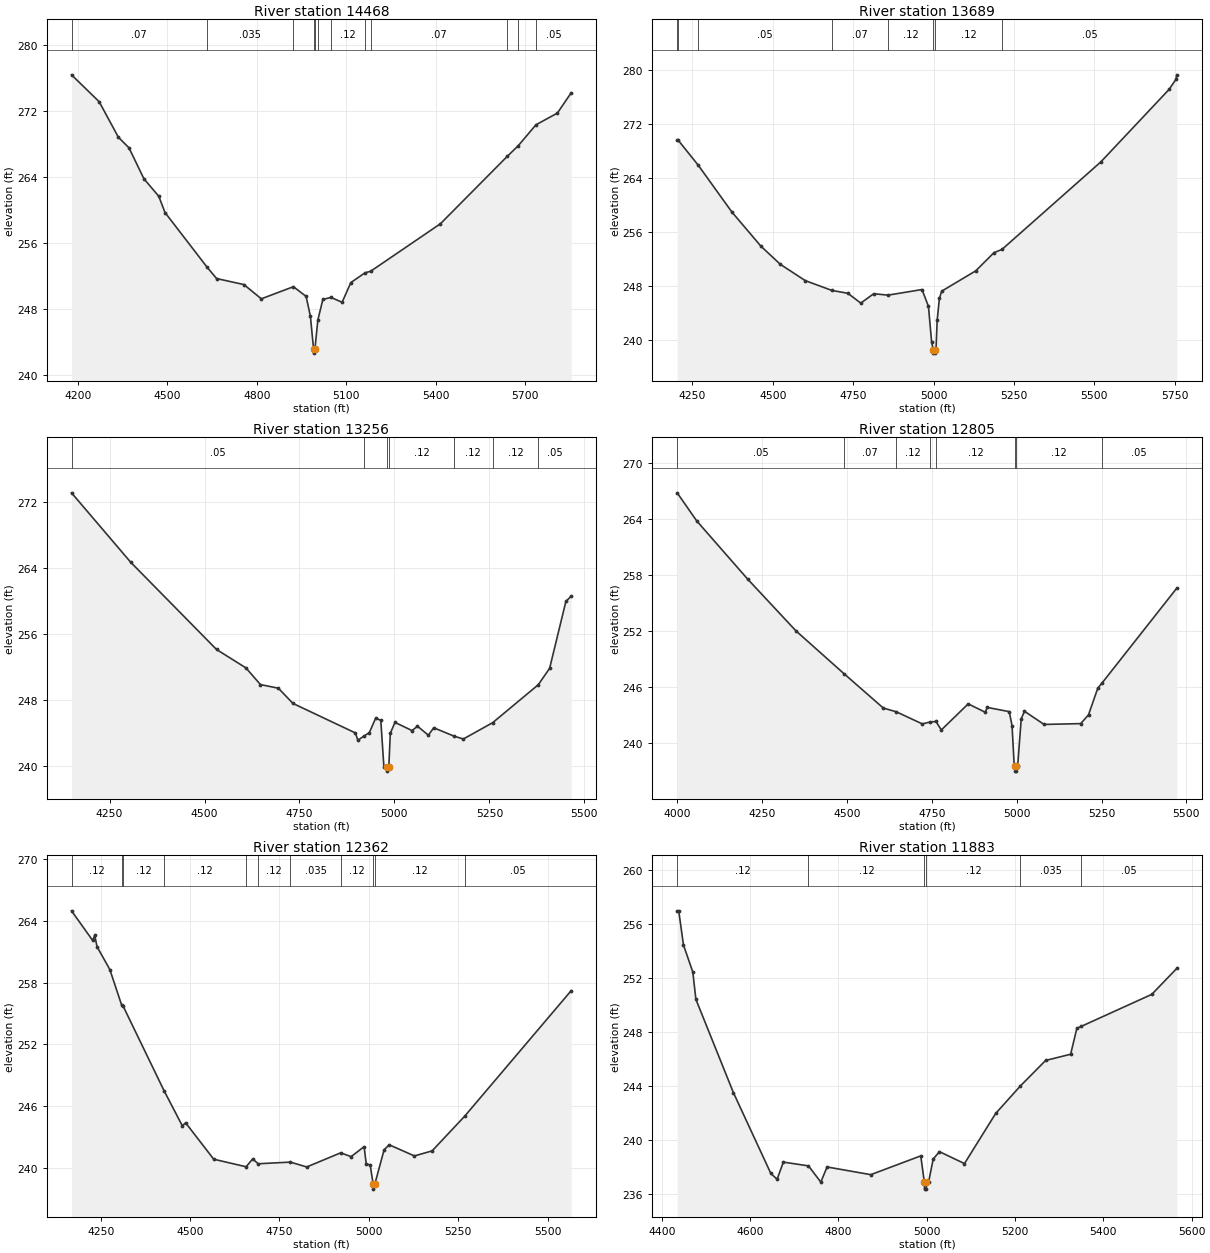
Type RM Length L Ch R = 1 ,14468   ,779,779,779
BEGIN DESCRIPTION:
Stream0339 27.0
END DESCRIPTION:
XS GIS Cut Line= 3
      2492024.98     13661124.97      2491492.89     13660417.81
      2491021.22     13659784.79
#Sta/Elev= 30
  4178.8  276.43  4271.4  273.17    4336  268.85  4371.4  267.57  4421.4  263.82
  4471.3  261.69  4492.2  259.72  4632.9   253.1    4665  251.71  4756.6  250.98
  4814.9  249.25  4922.4  250.72  4964.9  249.55  4979.4  247.14    4990  243.16
  4990.3  242.66  4994.5  243.16  5004.4  246.68  5021.1  249.17  5048.3  249.42
  5085.7  248.83  5114.9  251.22  5162.7  252.41  5181.2  252.59  5415.2  258.36
  5638.7  266.52  5675.8  267.82  5735.1  270.36  5807.2  271.79  5853.2  274.24
#Mann= 12 ,-1 , 0
  4178.8     .07       0  4632.9    .035       0  4922.4     .07       0
    4990     .05       0  4994.5     .07       0  5004.4     .12       0
  5048.3     .12       0  5162.7     .12       0  5181.2     .07       0
  5638.7     .12       0  5675.8     .07       0  5735.1     .05       0
Bank Sta=4990,4994.5
XS Rating Curve= 0 ,0
Exp/Cntr=0.3,0.1

Type RM Length L Ch R = 1 ,13689   ,433,433,433
BEGIN DESCRIPTION:
Stream0339 26.0
END DESCRIPTION:
XS GIS Cut Line= 3
        2492075.     13660924.98        2492025.       13660125.
      2491508.77     13659577.69
#Sta/Elev= 30
  4202.4  269.68  4204.6  269.68  4268.3   265.9  4372.7  258.99  4462.9  253.94
    4523  251.27  4600.7  248.85  4682.8  247.41  4733.4  246.97  4773.5  245.52
  4813.6  246.91  4858.1   246.7  4963.9  247.53  4983.9  245.04  4993.9   239.7
  4999.1  238.62  4999.5  238.12  5003.4  238.12  5003.7  238.62  5007.4  238.62
    5011  242.95  5017.9  246.21  5025.2  247.29  5131.2   250.3  5187.8  252.99
  5212.5  253.46  5520.4  266.43  5732.5  277.15  5753.8  278.64  5756.3   279.3
#Mann= 8 ,-1 , 0
  4202.4     .05       0  4204.6     .07       0  4268.3     .05       0
  4682.8     .07       0  4858.1     .12       0  4999.1     .05       0
  5003.7     .12       0  5212.5     .05       0
Bank Sta=4999.1,5003.7
XS Rating Curve= 0 ,0
Exp/Cntr=0.3,0.1

Type RM Length L Ch R = 1 ,13256   ,451,451,451
BEGIN DESCRIPTION:
Stream0339 25.0
END DESCRIPTION:
XS GIS Cut Line= 3
        2492725.     13660924.99        2492425.       13660125.
      2492074.98     13659824.98
#Sta/Elev= 30
  4149.8  273.11  4305.5  264.71  4531.6  254.14    4609  251.91  4647.3  249.89
  4694.5  249.45  4732.7  247.61  4897.4  244.03  4903.6  243.15    4919  243.63
  4933.9  244.07  4950.8  245.84  4964.1  245.55  4972.2  239.96  4980.5  239.91
  4980.8  239.41  4985.2  239.91  4989.1     244  5001.5  245.31  5046.4  244.32
  5060.7  244.85  5089.3  243.76  5103.5  244.66  5156.7  243.65  5181.4   243.3
  5258.7  245.28  5378.7  249.87  5408.6  251.86  5451.4  259.96  5465.2  260.59
#Mann= 7 ,-1 , 0
  4149.8     .05       0    4919     .12       0  4980.5     .05       0
  4985.2     .12       0  5156.7     .12       0  5258.7     .12       0
  5378.7     .05       0
Bank Sta=4980.5,4985.2
XS Rating Curve= 0 ,0
Exp/Cntr=0.3,0.1

Type RM Length L Ch R = 1 ,12805   ,443,443,443
BEGIN DESCRIPTION:
Stream0339 24.0
END DESCRIPTION:
XS GIS Cut Line= 3
      2493374.99     13660674.99        2492775.       13659875.
      2492524.99     13659474.99
#Sta/Elev= 30
    4000  266.77  4057.3  263.78  4207.3  257.56    4350  252.01    4491  247.45
  4607.3  243.76    4645  243.37  4721.9  242.07    4744  242.26  4762.3  242.33
  4778.1  241.42  4857.3  244.21  4907.3  243.32  4913.5  243.83  4978.1  243.38
  4986.4  241.89  4992.7  237.69  4994.5  237.52  4994.9  237.02  4998.9  237.02
  4999.2  237.52  5002.9  237.52  5013.5  242.62    5023  243.42  5080.8  242.01
  5188.7   242.1  5211.7  243.04  5238.8  245.87  5250.7   246.4  5471.7  256.58
#Mann= 8 ,-1 , 0
    4000     .05       0    4491     .07       0    4645     .12       0
    4744     .07       0  4762.3     .12       0  4994.5     .05       0
  4999.2     .12       0  5250.7     .05       0
Bank Sta=4994.5,4999.2
XS Rating Curve= 0 ,0
Exp/Cntr=0.3,0.1

Type RM Length L Ch R = 1 ,12362   ,479,479,479
BEGIN DESCRIPTION:
Stream0339 23.0
END DESCRIPTION:
XS GIS Cut Line= 3
      2493824.96     13660174.97        2493125.       13659725.
        2492725.       13659325.
#Sta/Elev= 30
  4168.2  264.96  4227.3  262.09  4233.2  262.58  4239.5  261.49  4275.5  259.26
  4308.5  255.81    4312  255.76  4426.9  247.53  4478.2  244.11  4487.5   244.4
  4566.1  240.87  4656.7  240.14    4675   240.9  4690.4  240.43  4780.5  240.59
  4826.3  240.12  4921.3  241.49  4950.5  241.12  4986.8  242.09  4992.7  240.44
  5003.9  240.29  5012.1  238.47  5012.4  237.97  5016.9  238.47  5042.7  241.78
  5056.9  242.27  5127.6  241.19  5177.1  241.68  5268.1  245.04    5566  257.21
#Mann= 11 ,-1 , 0
  4168.2     .12       0  4308.5     .07       0    4312     .12       0
  4426.9     .12       0  4656.7    .035       0  4690.4     .12       0
  4780.5    .035       0  4921.3     .12       0  5012.1     .05       0
  5016.9     .12       0  5268.1     .05       0
Bank Sta=5012.1,5016.9
XS Rating Curve= 0 ,0
Exp/Cntr=0.3,0.1

Type RM Length L Ch R = 1 ,11883   ,442,442,442
BEGIN DESCRIPTION:
Stream0339 22.0
END DESCRIPTION:
XS GIS Cut Line= 3
      2493925.01     13659925.01        2493525.       13659525.
      2493124.99     13659124.99
#Sta/Elev= 30
    4435  256.96  4438.5  256.96  4449.2  254.44  4470.4  252.43  4477.4  250.41
  4562.3  243.51  4647.1  237.53  4661.3   237.1  4675.4  238.37  4732.3  238.09
  4760.3  236.89  4774.4  238.01  4873.4  237.44  4986.6  238.83  4994.8  236.87
  4995.1  236.37  4999.2  236.37  4999.6  236.87  5004.2  236.87  5014.8   238.6
    5029  239.14  5085.6  238.26  5156.3  241.97  5212.4  244.01  5269.4  245.89
    5326  246.35  5340.1  248.27    5350  248.41  5509.8  250.78  5566.4   252.7
#Mann= 6 ,-1 , 0
    4435     .12       0  4732.3     .12       0  4994.8     .05       0
  4999.6     .12       0  5212.4    .035       0    5350     .05       0
Bank Sta=4994.8,4999.6
XS Rating Curve= 0 ,0
Exp/Cntr=0.3,0.1

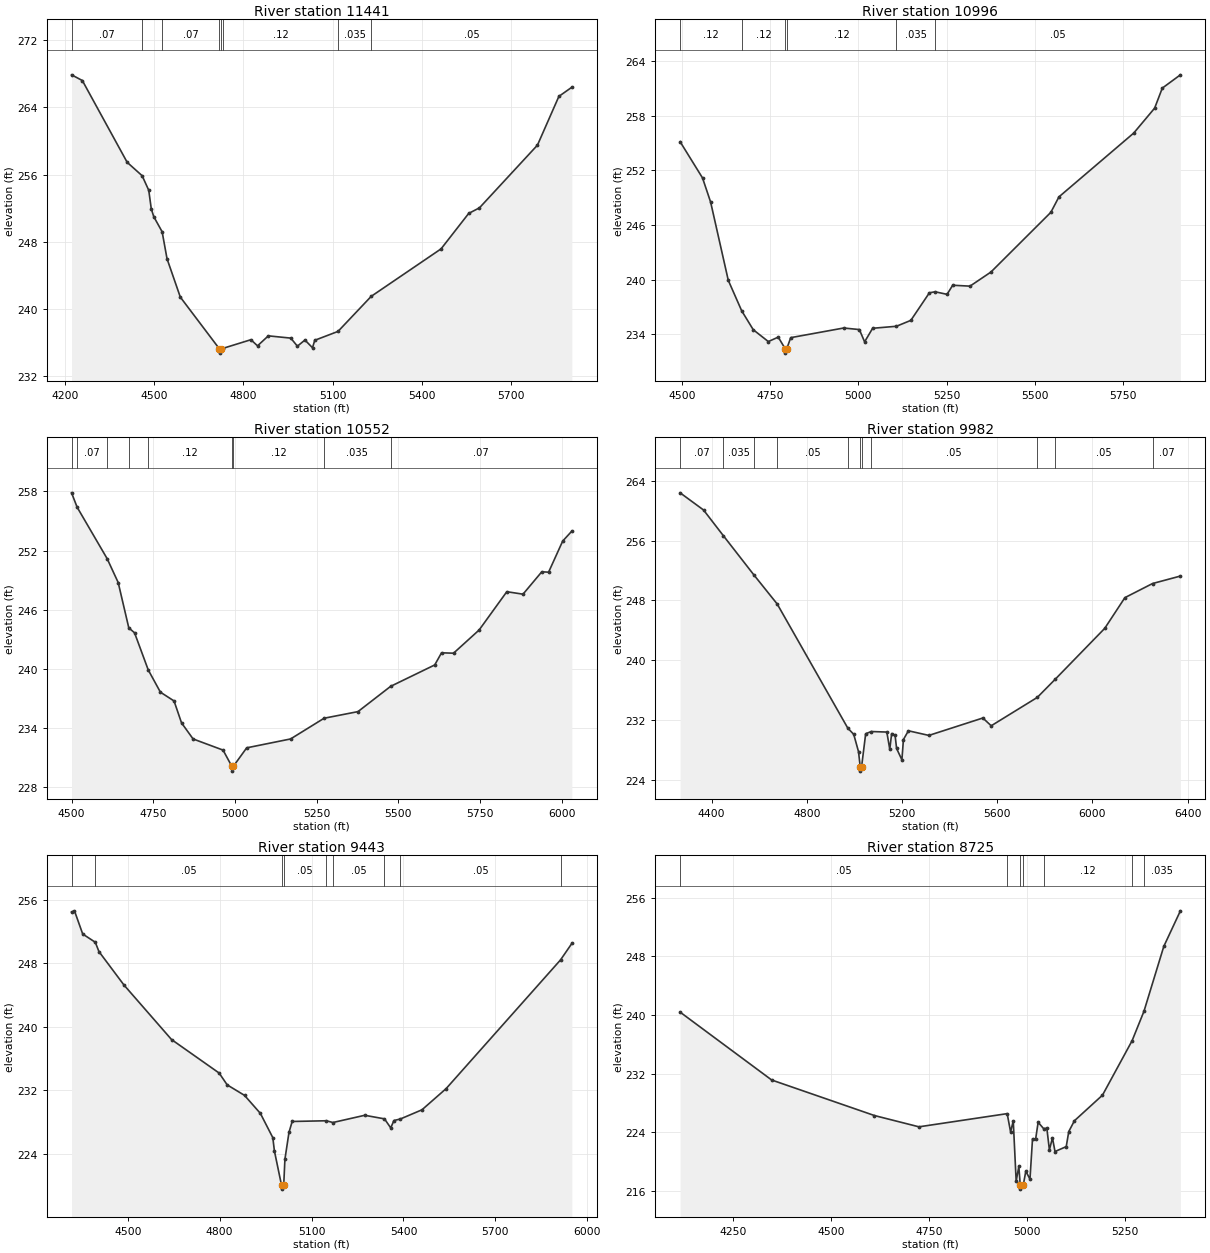
Type RM Length L Ch R = 1 ,11441   ,445,445,445
BEGIN DESCRIPTION:
Stream0339 21.0
END DESCRIPTION:
XS GIS Cut Line= 3
      2494424.96     13659524.98        2493725.       13659175.
      2492974.97     13658674.98
#Sta/Elev= 30
  4221.6  267.89  4257.9  267.21  4408.8  257.46  4459.2  255.86  4481.5  254.12
  4489.9  251.92  4498.3  250.98  4526.5  249.18    4543  245.96  4587.7  241.39
  4719.5  235.21  4719.8  234.71  4724.3  235.21  4732.3  235.29  4825.3  236.31
  4847.6  235.58    4884  236.77  4959.5   236.5  4981.8  235.54  5007.2  236.27
  5032.7  235.35  5040.2  236.24  5118.6   237.3  5230.3  241.48  5465.4  247.14
  5558.5  251.37  5594.6  252.03  5789.9  259.51    5862  265.32  5905.6  266.41
#Mann= 8 ,-1 , 0
  4221.6     .07       0  4459.2     .12       0  4526.5     .07       0
  4719.5     .05       0  4724.3     .07       0  4732.3     .12       0
  5118.6    .035       0  5230.3     .05       0
Bank Sta=4719.5,4724.3
XS Rating Curve= 0 ,0
Exp/Cntr=0.3,0.1

Type RM Length L Ch R = 1 ,10996   ,444,444,444
BEGIN DESCRIPTION:
Stream0339 20.0
END DESCRIPTION:
XS GIS Cut Line= 3
        2494275.       13659275.        2493975.       13658875.
      2493174.98     13658424.99
#Sta/Elev= 30
  4494.7  255.15  4558.2  251.17  4581.2  248.51  4631.2  239.92  4669.2  236.57
    4702  234.49  4744.7  233.19  4772.8  233.68  4792.2  232.42  4792.6  231.92
  4797.1  232.42  4808.2  233.62  4958.2  234.68  5002.7  234.51  5017.6  233.16
  5040.3  234.65  5107.7  234.87  5148.6  235.52  5201.2  238.55  5217.4  238.66
  5251.3  238.38  5267.2  239.38  5316.3  239.28  5375.6  240.83  5545.4  247.39
  5568.4  249.09  5780.3   256.1  5839.6  258.84  5861.3  261.04  5912.6   262.5
#Mann= 6 ,-1 , 0
  4494.7     .12       0  4669.2     .12       0  4792.2     .05       0
  4797.1     .12       0  5107.7    .035       0  5217.4     .05       0
Bank Sta=4792.2,4797.1
XS Rating Curve= 0 ,0
Exp/Cntr=0.3,0.1

Type RM Length L Ch R = 1 ,10552   ,570,570,570
BEGIN DESCRIPTION:
Stream0339 19.0
END DESCRIPTION:
XS GIS Cut Line= 3
      2494625.01     13659225.01        2494325.       13658825.
      2493524.99     13658174.99
#Sta/Elev= 30
    4500  257.85  4517.1  256.39  4608.9  251.18  4642.7  248.76  4675.2  244.16
  4692.7  243.67  4734.7   239.9  4771.9  237.65  4813.6  236.76  4836.5  234.54
  4871.9  232.91  4963.6  231.78  4990.2  230.15  4990.6  229.65  4995.3  230.15
  5035.9  232.01  5170.2  232.91  5272.8  235.01  5376.4  235.68  5476.3  238.24
  5611.3  240.41  5632.1  241.64  5668.8   241.6  5747.1  243.95  5831.8  247.83
  5881.4  247.58  5938.9  249.85  5959.7  249.81  6002.8  252.96  6030.8  253.97
#Mann= 9 ,-1 , 0
    4500     .12       0  4517.1     .07       0  4608.9     .12       0
  4675.2     .07       0  4734.7     .12       0  4990.2     .05       0
  4995.3     .12       0  5272.8    .035       0  5476.3     .07       0
Bank Sta=4990.2,4995.3
XS Rating Curve= 0 ,0
Exp/Cntr=0.3,0.1

Type RM Length L Ch R = 1 ,9982    ,539,539,539
BEGIN DESCRIPTION:
Stream0339 18.0
END DESCRIPTION:
XS GIS Cut Line= 3
      2494873.95     13659553.26      2494819.91     13658680.96
      2493870.46     13657901.33
#Sta/Elev= 30
  4267.4   262.4  4365.9   260.1  4449.4  256.65  4576.5  251.45  4675.4  247.52
    4972  230.91  4997.1  230.07  5017.1  227.76  5024.6  225.65    5025  225.15
  5029.7  225.65  5047.2  230.15  5070.8  230.45  5136.1  230.38  5148.5  228.08
  5156.4  230.18  5170.8  229.95  5177.2  228.18  5199.5  226.66  5205.9  229.38
  5226.8  230.55  5312.8  229.93  5539.6  232.26  5574.8  231.22  5768.6  235.02
  5844.8  237.48  6051.9  244.26  6136.6  248.37  6252.9  250.26  6369.9  251.26
#Mann= 11 ,-1 , 0
  4267.4     .07       0  4449.4    .035       0  4576.5     .12       0
  4675.4     .05       0    4972     .15       0  5024.6     .05       0
  5029.7     .15       0  5070.8     .05       0  5768.6    .035       0
  5844.8     .05       0  6252.9     .07       0
Bank Sta=5024.6,5029.7
XS Rating Curve= 0 ,0
Exp/Cntr=0.3,0.1

Type RM Length L Ch R = 1 ,9443    ,718,718,718
BEGIN DESCRIPTION:
Stream0339 17.0
END DESCRIPTION:
XS GIS Cut Line= 3
       2495097.8     13659530.12      2495259.91     13658927.98
      2495530.05     13657955.48
#Sta/Elev= 30
  4316.7  254.44  4326.2   254.6  4353.1  251.68  4394.2  250.64  4406.1  249.47
  4487.7  245.26    4643  238.39  4798.4  234.17  4824.7  232.68  4881.2  231.36
    4933  229.09  4973.6  226.03  4978.8  224.36    5002  220.05  5002.5  219.55
  5009.2  220.05  5013.1  223.31  5026.4   226.7  5036.8  228.07  5148.3  228.16
  5169.8  227.94  5273.6  228.85  5338.1   228.4  5358.5  227.26  5368.9  228.19
  5389.7  228.38  5460.4  229.54  5539.3  232.21  5912.7  248.42  5949.6  250.49
#Mann= 9 ,-1 , 0
  4316.7    .035       0  4394.2     .05       0    5002     .05       0
  5009.2     .05       0  5148.3     .07       0  5169.8     .05       0
  5338.1     .07       0  5389.7     .05       0  5912.7    .035       0
Bank Sta=5002,5009.2
XS Rating Curve= 0 ,0
Exp/Cntr=0.3,0.1

Type RM Length L Ch R = 1 ,8725    ,484,484,484
BEGIN DESCRIPTION:
Stream0339 16.0
END DESCRIPTION:
XS GIS Cut Line= 3
      2495275.03     13659424.97        2495875.       13658775.
      2496175.03     13658524.97
#Sta/Elev= 30
  4115.3   240.4  4348.6  231.14  4610.6  226.29    4724  224.75  4948.9  226.55
  4957.6  224.06  4964.4  225.56  4971.8  217.33  4978.6  219.35  4982.3  216.75
  4982.8  216.25  4989.7  216.75  4996.4   218.7    5007  217.61  5013.5  223.13
  5021.3  223.03  5027.8  225.37  5041.7  224.51    5050  224.55  5056.5  221.61
  5064.3  223.24  5070.8  221.38  5099.4  222.05  5105.9  224.11  5120.3  225.58
  5191.8  229.07  5267.3   236.5  5297.5  240.51  5348.1  249.37  5390.4  254.22
#Mann= 7 ,-1 , 0
  4115.3     .05       0  4948.9     .12       0  4982.3     .05       0
  4989.7     .12       0  5041.7     .12       0  5267.3     .05       0
  5297.5    .035       0
Bank Sta=4982.3,4989.7
XS Rating Curve= 0 ,0
Exp/Cntr=0.3,0.1

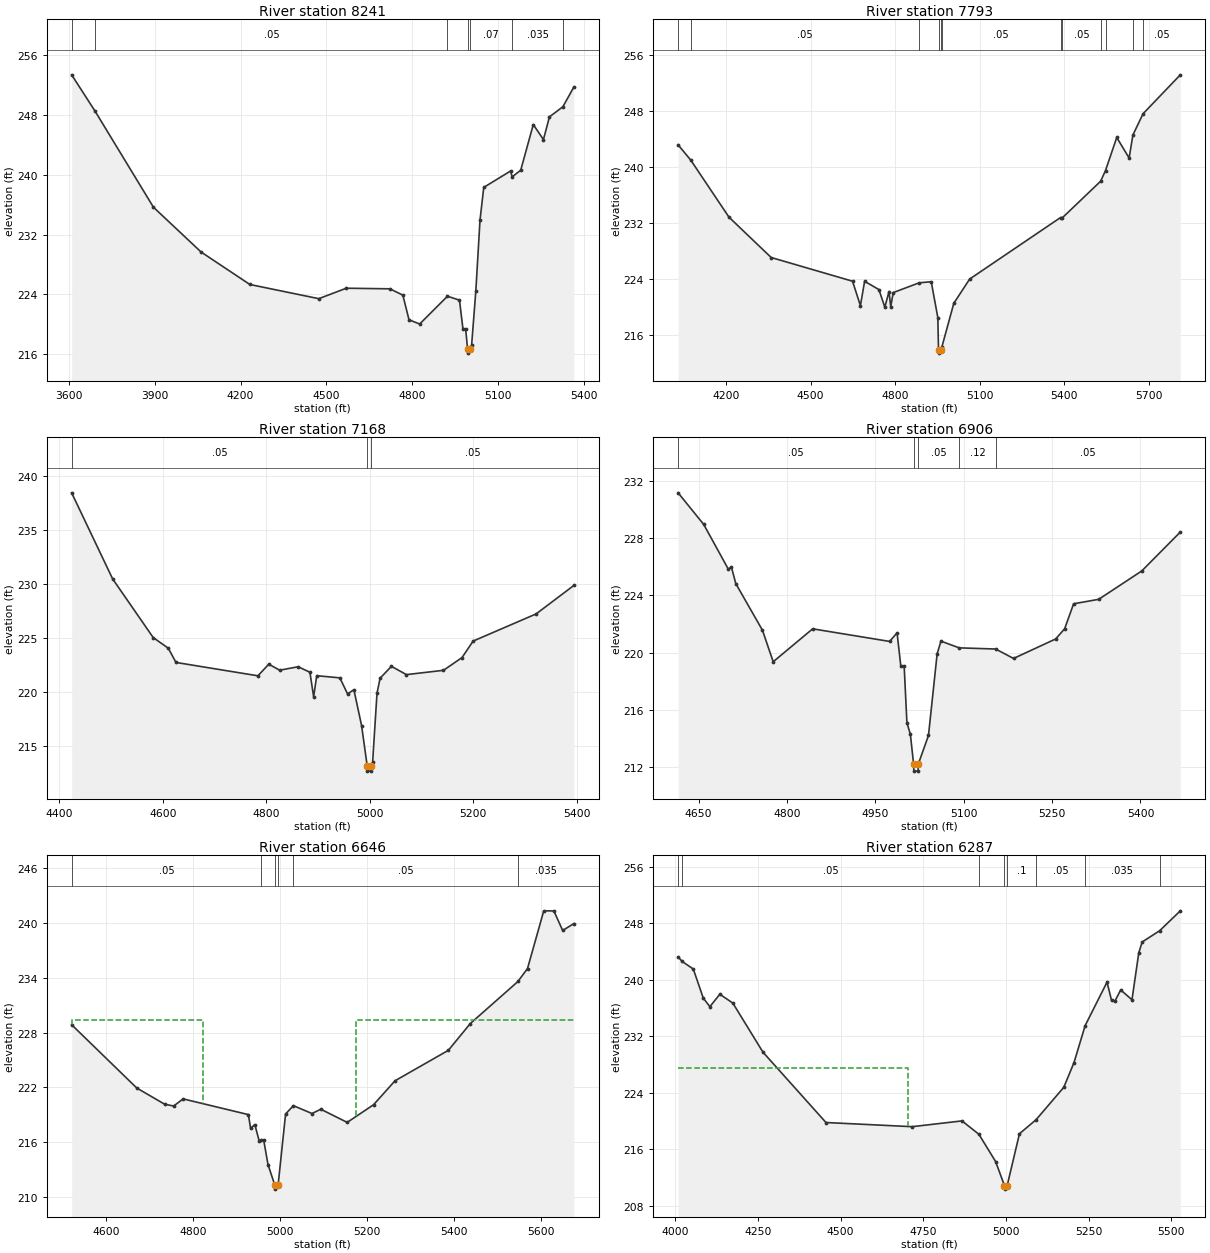
Type RM Length L Ch R = 1 ,8241    ,448,448,448
BEGIN DESCRIPTION:
Stream0339 15.0
END DESCRIPTION:
XS GIS Cut Line= 3
      2495125.02     13659574.99        2496325.       13658875.
      2496540.64     13658581.53
#Sta/Elev= 30
  3610.3  253.41  3692.6  248.51    3896  235.68  4062.2  229.69  4232.5  225.34
  4473.2  223.44  4569.1  224.84  4721.7  224.76  4766.7  223.91  4788.2  220.61
  4825.5  220.05  4922.5  223.77  4964.4  223.24  4976.4  219.44  4985.9   219.4
  4992.9  216.65  4993.4  216.15  5000.3  216.65  5006.8  217.23  5021.5  224.47
  5036.1  233.97  5049.2  238.34  5142.6  240.53  5148.5  239.75  5178.2  240.64
  5222.1  246.75  5257.6  244.74  5278.5  247.78  5325.5  249.14  5363.7  251.77
#Mann= 7 ,-1 , 0
  3610.3    .035       0  3692.6     .05       0  4922.5     .07       0
  4992.9     .05       0  5000.3     .07       0  5148.5    .035       0
  5325.5     .05       0
Bank Sta=4992.9,5000.3
XS Rating Curve= 0 ,0
Exp/Cntr=0.3,0.1

Type RM Length L Ch R = 1 ,7793    ,625,625,625
BEGIN DESCRIPTION:
Stream0339 14.0
END DESCRIPTION:
XS GIS Cut Line= 3
      2495624.98     13660025.03        2496175.       13659225.
      2496826.94     13658742.71
#Sta/Elev= 30
  4029.9  243.15  4074.8  240.97  4210.6  232.83  4360.1  227.09  4648.8  223.71
  4676.7  220.23  4691.6   223.7  4742.3  222.52  4763.3  220.01  4778.2  222.24
  4784.3  220.08  4793.1  222.09  4885.1  223.48    4928  223.64  4951.4  218.52
  4953.8  213.96  4954.3  213.46  4961.2  213.96  4965.5   214.3  5008.1  220.57
  5064.4  224.02  5386.8  232.79  5393.4  232.76  5529.2  237.97  5546.3  239.49
  5586.2   244.2  5630.1  241.27  5643.5  244.55  5679.5  247.58  5811.7  253.13
#Mann= 12 ,-1 , 0
  4029.9    .035       0  4074.8     .05       0  4885.1     .07       0
  4953.8     .05       0  4961.2     .07       0  4965.5     .05       0
  5386.8     .07       0  5393.4     .05       0  5529.2    .035       0
  5546.3     .05       0  5643.5    .035       0  5679.5     .05       0
Bank Sta=4953.8,4961.2
XS Rating Curve= 0 ,0
Exp/Cntr=0.3,0.1

Type RM Length L Ch R = 1 ,7168    ,262,262,262
BEGIN DESCRIPTION:
Stream0339 13.0
END DESCRIPTION:
XS GIS Cut Line= 3
      2496175.01     13659974.99      2496564.47     13659406.58
      2496724.99     13659175.01
#Sta/Elev= 30
  4423.8  238.45    4503  230.47  4581.4  225.03  4610.6  224.04  4625.5  222.72
  4783.9  221.48  4804.9  222.56  4825.9     222  4861.7  222.32  4884.4  221.81
  4891.6  219.53  4897.6  221.49  4942.3  221.29  4957.2   219.8  4969.4  220.19
  4984.3  216.86  4995.1  213.14  4995.6  212.64  5002.7  212.64  5003.2  213.14
  5005.6  213.46  5014.1  219.87  5020.1  221.26    5042  222.36  5070.9  221.59
  5142.6  221.99  5178.4  223.17  5199.9   224.7  5321.7  227.22  5394.6  229.86
#Mann= 3 ,-1 , 0
  4423.8     .05       0  4995.1     .05       0  5003.2     .05       0
Bank Sta=4995.1,5003.2
XS Rating Curve= 0 ,0
Exp/Cntr=0.3,0.1

Type RM Length L Ch R = 1 ,6906    ,260,260,260
BEGIN DESCRIPTION:
Stream0339 12.0
END DESCRIPTION:
XS GIS Cut Line= 3
      2496525.01     13660024.97        2496675.       13659675.
      2496925.02     13659274.96
#Sta/Elev= 30
  4615.1  231.16  4658.6  228.95  4700.3  225.83  4705.7  225.96    4713  224.82
  4758.3  221.56  4776.5  219.36  4843.5  221.66  4974.1  220.78  4986.8  221.38
  4993.1  219.08  4998.8  219.08  5003.5   215.1  5009.4  214.29  5014.8  212.22
  5015.3  211.72  5022.4  211.72  5022.9  212.22  5040.1  214.21  5054.8  219.91
  5061.3   220.8  5092.3  220.33  5154.1  220.25  5184.5  219.59  5255.9  220.95
  5271.2  221.66  5286.5  223.41    5329  223.72  5402.1   225.7  5467.6  228.42
#Mann= 5 ,-1 , 0
  4615.1     .05       0  5014.8     .05       0  5022.9     .05       0
  5092.3     .12       0  5154.1     .05       0
Bank Sta=5014.8,5022.9
XS Rating Curve= 0 ,0
Exp/Cntr=0.3,0.1

Type RM Length L Ch R = 1 ,6646    ,359,359,359
BEGIN DESCRIPTION:
Stream0339 11.0
END DESCRIPTION:
XS GIS Cut Line= 3
      2496674.97     13660125.04      2496904.12     13659838.86
      2497019.85     13659059.62
#Sta/Elev= 30
  4521.6  228.85  4671.3  221.93  4735.3  220.16  4756.1  219.96  4777.9  220.74
  4927.9  219.02  4932.9  217.52  4942.7  217.93  4952.8  216.12    4958   216.2
  4962.9  216.28    4973  213.55  4988.2  211.37  4988.7  210.87  4996.3  211.37
  5013.4  219.09  5031.3     220  5074.1  219.14  5094.3  219.61    5155  218.17
  5215.6   220.1  5264.9  222.72  5387.5  226.05    5438  228.98  5547.5  233.58
  5569.5     235  5606.9  241.31  5630.1   241.3  5650.3  239.16    5676  239.91
#Mann= 6 ,-1 , 0
  4521.6     .05       0    4958     .12       0  4988.2     .05       0
  4996.3     .12       0  5031.3     .05       0  5547.5    .035       0
#XS Ineff= 2 , 0
       0  4824.1  229.41  5175.9       0  229.41
Permanent Ineff=
       F       F
Bank Sta=4988.2,4996.3
XS Rating Curve= 0 ,0
Exp/Cntr=0.3,0.1

Type RM Length L Ch R = 1 ,6287    ,102,102,102
BEGIN DESCRIPTION:
XS6516
END DESCRIPTION:
XS GIS Cut Line= 3
      2497097.11     13660610.75      2497166.58     13659699.91
      2497313.24     13659113.25
#Sta/Elev= 30
  4008.7  243.25  4020.7  242.61  4054.6  241.53  4084.7  237.42  4104.7   236.2
  4134.8  237.96  4174.1  236.71  4265.2  229.76  4455.7   219.8  4716.5  219.21
  4866.9  220.03  4917.9  218.14  4968.5  214.28  4995.3  210.87  4995.8  210.37
  5003.5  210.87  5040.6  218.21  5090.9   220.2  5174.6  224.78  5205.6  228.29
  5239.2  233.52  5305.4  239.68  5318.9   237.1  5329.3     237  5346.7  238.57
  5380.8  237.18  5401.4  243.84  5411.7  245.36  5464.6  246.96  5526.9  249.77
#Mann= 8 ,-1 , 0
  4008.7    .035       0  4020.7     .05       0  4917.9      .1       0
  4995.3     .05       0  5003.5      .1       0  5090.9     .05       0
  5239.2    .035       0  5464.6     .05       0
#XS Ineff= 2 , 0
       0  4702.4  227.51               0
Permanent Ineff=
       F       F
Bank Sta=4995.3,5003.5
XS Rating Curve= 0 ,0
Exp/Cntr=0.3,0.1

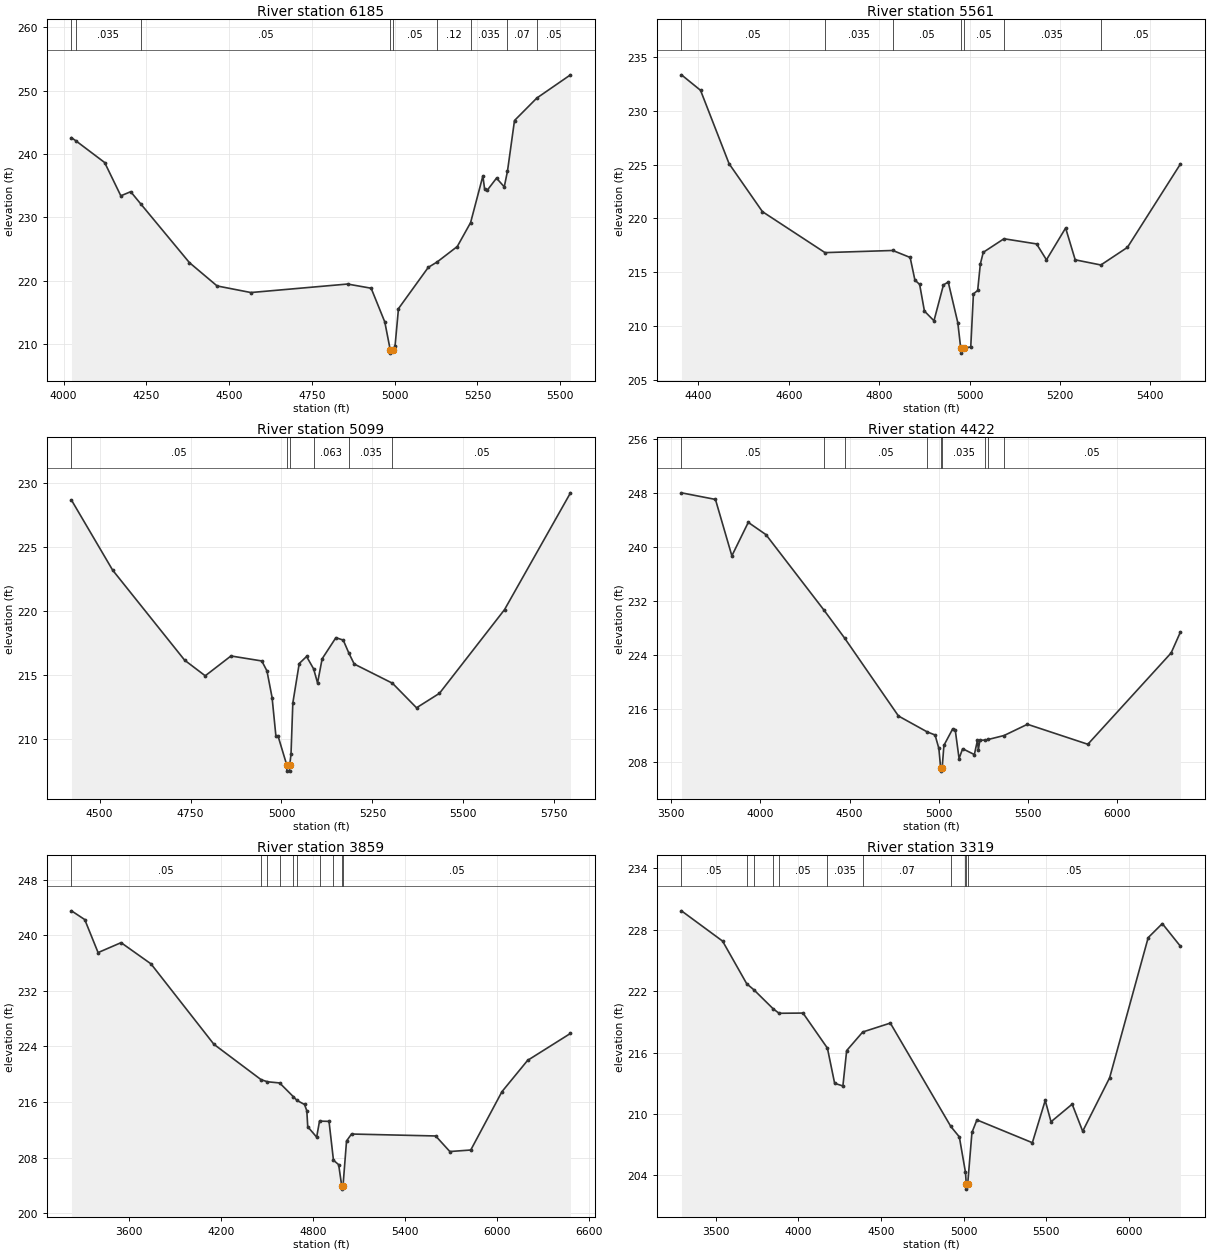
Type RM Length L Ch R = 1 ,6185    ,624,624,624
BEGIN DESCRIPTION:
Stream0339 10.0
END DESCRIPTION:
XS GIS Cut Line= 3
      2497158.86     13660603.06      2497259.21     13659738.51
       2497413.6     13659120.97
#Sta/Elev= 30
    4024  242.58  4036.7  242.11  4124.2  238.66    4173  233.41  4202.8  234.06
  4234.3  232.06  4380.1  222.87  4463.7  219.19  4565.7  218.15  4857.6  219.49
  4928.9  218.83  4970.1  213.51  4986.6  209.09  4987.1  208.59  4994.8  209.09
    5001  209.66  5011.4  215.61  5101.4  222.12  5128.4  222.98    5189  225.41
  5229.2  229.18  5266.3  236.54  5271.4  234.54  5279.4  234.28  5307.5   236.2
  5330.9  234.82  5340.6   237.3  5361.8  245.29  5429.3  248.84  5530.9   252.5
#Mann= 9 ,-1 , 0
    4024     .05       0  4036.7    .035       0  4234.3     .05       0
  4986.6     .05       0  4994.8     .05       0  5128.4     .12       0
  5229.2    .035       0  5340.6     .07       0  5429.3     .05       0
Bank Sta=4986.6,4994.8
XS Rating Curve= 0 ,0
Exp/Cntr=0.3,0.1

Type RM Length L Ch R = 1 ,5561    ,462,462,462
BEGIN DESCRIPTION:
Stream0339 9.0
END DESCRIPTION:
XS GIS Cut Line= 3
        2497525.     13660474.99        2497725.       13659875.
      2497974.98     13659475.04
#Sta/Elev= 30
  4362.5  233.35  4404.7  231.91  4467.9  225.08  4541.7  220.62  4680.1  216.81
  4830.1  217.01  4868.5  216.36    4879  214.26  4889.5  213.85  4900.1  211.37
  4921.2  210.47  4942.2  213.81  4952.8  214.07  4973.9   210.3  4980.3  207.96
  4980.8  207.46  4988.5  207.96  5002.6  208.03  5008.5  212.97  5017.9  213.29
  5023.8  215.75  5030.3  216.84  5076.1   218.1  5148.2  217.62  5170.1  216.14
  5212.5   219.1  5233.7  216.14  5290.5  215.66  5349.3   217.3  5466.6  225.06
#Mann= 7 ,-1 , 0
  4362.5     .05       0  4680.1    .035       0  4830.1     .05       0
  4980.3     .05       0  4988.5     .05       0  5076.1    .035       0
  5290.5     .05       0
Bank Sta=4980.3,4988.5
XS Rating Curve= 0 ,0
Exp/Cntr=0.3,0.1

Type RM Length L Ch R = 1 ,5099    ,677,677,677
BEGIN DESCRIPTION:
Stream0339 8.0
END DESCRIPTION:
XS GIS Cut Line= 3
      2497675.02     13660524.98        2498075.       13660125.
        2498175.     13659324.98
#Sta/Elev= 30
  4422.7  228.66  4535.8  223.19  4733.8  216.15  4790.4  214.93  4861.1  216.48
  4945.9  216.09  4960.1  215.31  4974.2  213.23  4984.8  210.19  4990.9  210.19
  5014.3  207.98  5014.8  207.48  5022.3  207.48  5022.8  207.98  5026.2   208.8
  5031.2   212.8  5048.8  215.89    5069  216.44  5088.4  215.47  5099.2  214.37
  5111.8  216.26  5149.6  217.91  5169.8  217.72  5185.2  216.71    5200  215.85
  5305.1  214.35  5371.3  212.43  5434.3  213.56  5613.2   220.1  5794.6  229.23
#Mann= 6 ,-1 , 0
  4422.7     .05       0  5014.3     .05       0  5022.8     .05       0
  5088.4    .063       0  5185.2    .035       0  5305.1     .05       0
Bank Sta=5014.3,5022.8
XS Rating Curve= 0 ,0
Exp/Cntr=0.3,0.1

Type RM Length L Ch R = 1 ,4422    ,563,563,563
BEGIN DESCRIPTION:
Stream0339 7.0
END DESCRIPTION:
XS GIS Cut Line= 3
       2497421.3     13661660.63      2498548.33     13660556.75
      2498278.39     13659369.02
#Sta/Elev= 30
  3558.3  248.06  3748.7  247.08  3840.7   238.7  3932.6  243.67  4031.6  241.85
  4356.8  230.63    4472  226.49  4774.1   214.9  4934.9  212.54  4979.1  212.08
  5000.4  210.08  5010.3  207.21  5010.8  206.71  5018.9  207.21  5028.7  210.54
  5078.1     213  5092.3  212.79  5113.6  208.58  5133.6  210.04  5199.2  209.17
  5216.6  211.29  5221.7  209.89    5230  211.29  5260.8  211.33  5277.9  211.42
  5365.5     212  5496.6  213.67    5835   210.7  6301.6  224.27  6353.9  227.39
#Mann= 9 ,-1 , 0
  3558.3     .05       0  4356.8    .035       0    4472     .05       0
  4934.9    .035       0  5010.3    .035       0  5018.9    .035       0
  5260.8     .05       0  5277.9    .035       0  5365.5     .05       0
Bank Sta=5010.3,5018.9
XS Rating Curve= 0 ,0
Exp/Cntr=0.3,0.1

Type RM Length L Ch R = 1 ,3859    ,540,540,540
BEGIN DESCRIPTION:
Stream0339 6.0
END DESCRIPTION:
XS GIS Cut Line= 4
      2497567.98     13661838.16      2498887.98     13660950.44
      2498965.18     13660703.42      2498386.21     13659421.98
#Sta/Elev= 30
  3225.6  243.52  3312.1  242.26  3399.1  237.51  3549.1  238.94  3744.1  235.89
    4155  224.31  4462.8  219.22  4504.4  218.92  4583.7  218.75  4673.7  216.76
  4696.4  216.24    4746  215.65  4760.9  214.75    4767  212.45  4825.2  210.95
  4843.8  213.26  4905.8  213.22  4934.8  207.63  4968.7  206.99  4988.5  203.97
    4989  203.47  4997.2  203.97  5020.1   210.4  5052.5   211.4  5601.7  211.12
  5694.1  208.88  5830.6   209.1  6034.2   217.5  6201.5     222  6481.3  225.88
#Mann= 10 ,-1 , 0
  3225.6     .05       0  4462.8    .035       0  4504.4     .05       0
  4583.7    .035       0  4673.7     .05       0  4696.4    .035       0
  4843.8     .07       0  4934.8     .05       0  4988.5     .05       0
  4997.2     .05       0
Bank Sta=4988.5,4997.2
XS Rating Curve= 0 ,0
Exp/Cntr=0.3,0.1

Type RM Length L Ch R = 1 ,3319    ,570,570,570
BEGIN DESCRIPTION:
E20904
END DESCRIPTION:
XS GIS Cut Line= 4
      2498219.46     13661658.59      2499273.19     13660855.03
      2499311.09      13660354.7       2498516.1     13659468.85
#Sta/Elev= 30
  3293.3  229.86  3541.9   226.9  3688.2  222.72  3730.3  222.15  3847.7  220.28
  3883.4  219.84  4028.2  219.86  4175.8  216.43  4219.5  212.99  4269.4  212.73
  4292.2  216.19  4389.4  218.01  4556.2  218.88  4921.9  208.77  4973.4  207.75
  5010.6  204.28  5015.3  203.14  5015.8  202.64    5024  203.14  5049.7  208.18
  5079.8  209.41    5415  207.18  5492.7  211.31  5527.9  209.23  5655.7  210.95
  5719.3   208.3  5882.2  213.53  6115.4  227.24  6200.7  228.61  6310.5  226.39
#Mann= 11 ,-1 , 0
  3293.3     .05       0  3688.2    .035       0  3730.3     .05       0
  3847.7    .035       0  3883.4     .05       0  4175.8    .035       0
  4389.4     .07       0  4921.9     .12       0  5010.6     .07       0
  5015.3     .05       0    5024     .05       0
Bank Sta=5015.3,5024
XS Rating Curve= 0 ,0
Exp/Cntr=0.3,0.1

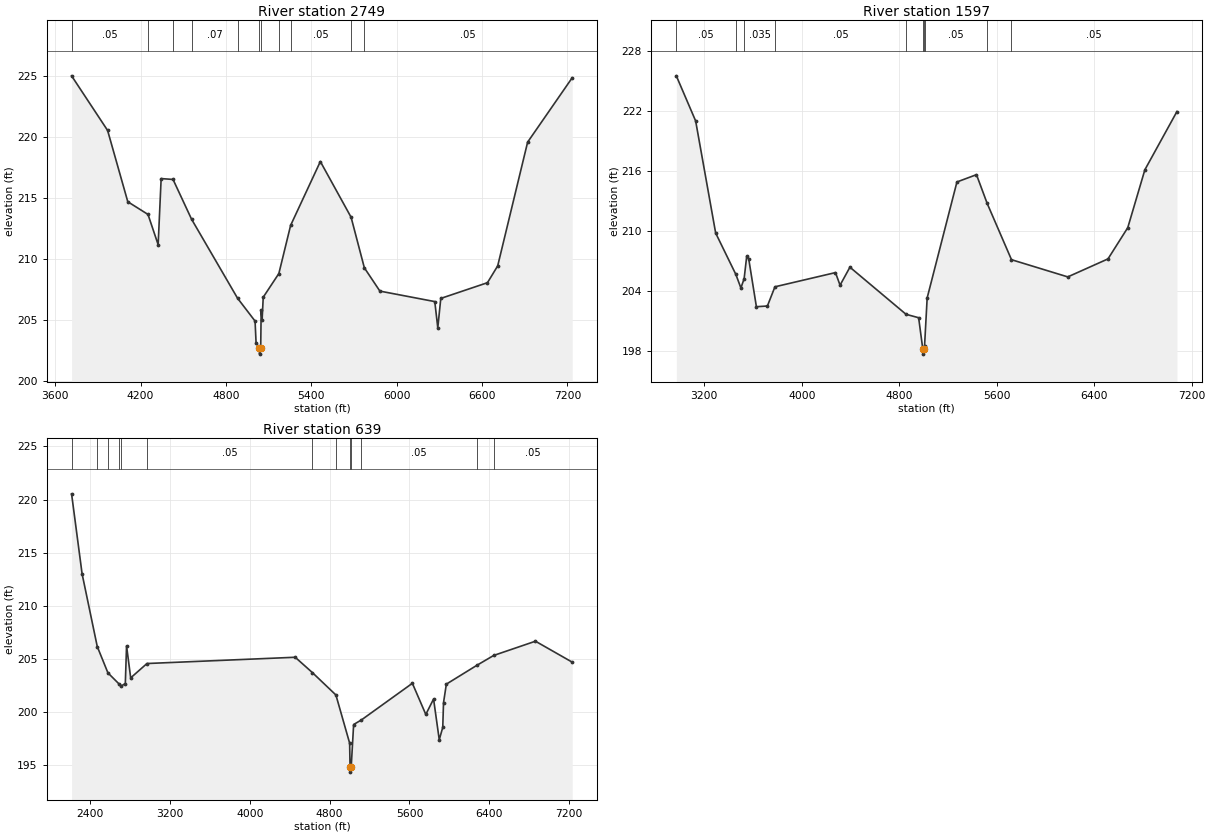
Type RM Length L Ch R = 1 ,2749    ,1152,1152,1152
BEGIN DESCRIPTION:
E20903
END DESCRIPTION:
XS GIS Cut Line= 4
       2498636.4     13661582.79       2499743.2     13660665.51
      2499894.81     13660271.31      2498492.39     13659384.37
#Sta/Elev= 30
  3714.8  225.02  3968.1  220.54    4110  214.69    4252  213.65  4323.4  211.17
  4344.5  216.59  4428.1  216.52  4558.2  213.26  4881.4  206.78  5004.7   204.9
  5011.8  203.11  5035.6  202.69  5036.1  202.19  5044.3  202.69  5047.7   205.8
  5054.2  204.99  5062.1  206.86  5171.9   208.8  5254.6  212.75  5463.6  217.99
  5679.7  213.42    5773  209.27  5882.2  207.36    6268   206.5  6289.2  204.35
  6310.3  206.76  6638.4  208.05  6710.3  209.43  6920.7  219.58    7234  224.86
#Mann= 11 ,-1 , 0
  3714.8     .05       0    4252    .035       0  4428.1     .12       0
  4558.2     .07       0  4881.4     .12       0  5035.6     .05       0
  5044.3     .12       0  5171.9     .07       0  5254.6     .05       0
  5679.7     .07       0    5773     .05       0
Bank Sta=5035.6,5044.3
XS Rating Curve= 0 ,0
Exp/Cntr=0.3,0.1

Type RM Length L Ch R = 1 ,1597    ,958,958,958
BEGIN DESCRIPTION:
E20902
END DESCRIPTION:
XS GIS Cut Line= 5
      2498719.83     13661635.83      2499970.62     13661158.26
      2500190.46     13660756.48      2500182.88     13660294.05
       2498569.1     13659392.46
#Sta/Elev= 30
  2970.9  225.52  3129.5  221.01  3293.9   209.8  3459.4  205.67  3500.9  204.31
  3527.5  205.25  3548.5  207.48  3565.2  207.21    3628  202.44  3718.3  202.51
  3780.1  204.43  4276.9  205.85  4314.5  204.59  4395.4  206.39    4856  201.68
  4959.3  201.34  4993.5   198.2    4994   197.7    5005   198.2  5008.1  198.56
  5029.3  203.32  5273.6  214.91    5434  215.64  5521.2  212.78  5721.2  207.14
    6183  205.42  6513.1  207.22  6675.3  210.34  6815.8  216.13  7078.8  221.95
#Mann= 10 ,-1 , 0
  2970.9     .05       0  3459.4     .07       0  3527.5    .035       0
  3780.1     .05       0    4856     .12       0  4993.5     .05       0
    5005     .12       0  5008.1     .05       0  5521.2     .07       0
  5721.2     .05       0
Bank Sta=4993.5,5005
XS Rating Curve= 0 ,0
Exp/Cntr=0.3,0.1

Type RM Length L Ch R = 1 ,639     ,0,0,0
BEGIN DESCRIPTION:
E20901
END DESCRIPTION:
XS GIS Cut Line= 5
      2498833.52     13661719.23      2500713.54      13660983.9
       2500804.5     13660415.34      2500743.86     13659725.49
      2499599.95     13658430.07
#Sta/Elev= 30
  2214.9  220.54  2320.5     213  2472.2  206.17  2579.1  203.69  2685.9  202.69
    2714  202.46  2753.4  202.69  2765.7  206.23  2807.1  203.22  2970.1  204.57
  4455.3  205.16  4628.1  203.71    4863  201.61  5000.5  197.08  5004.7  194.85
  5005.2  194.35  5016.3  194.85  5040.6  198.83  5118.3  199.26    5629  202.71
  5763.6  199.78  5841.4  201.23  5898.3   197.4  5933.4  198.56    5941  200.88
  5969.4  202.63    6273  204.39  6443.6  205.33    6862  206.67  7230.1   204.7
#Mann= 13 ,-1 , 0
  2214.9     .05       0  2472.2     .07       0  2579.1     .05       0
  2685.9     .07       0    2714    .035       0  2970.1     .05       0
  4628.1     .07       0    4863     .12       0  5004.7     .05       0
  5016.3     .12       0  5118.3     .05       0    6273    .035       0
  6443.6     .05       0
Bank Sta=5004.7,5016.3
XS Rating Curve= 0 ,0
Exp/Cntr=0.3,0.1

Chan Stop Cuts=-1
Use User Specified Reach Order=0
Composite Channel Slope=5