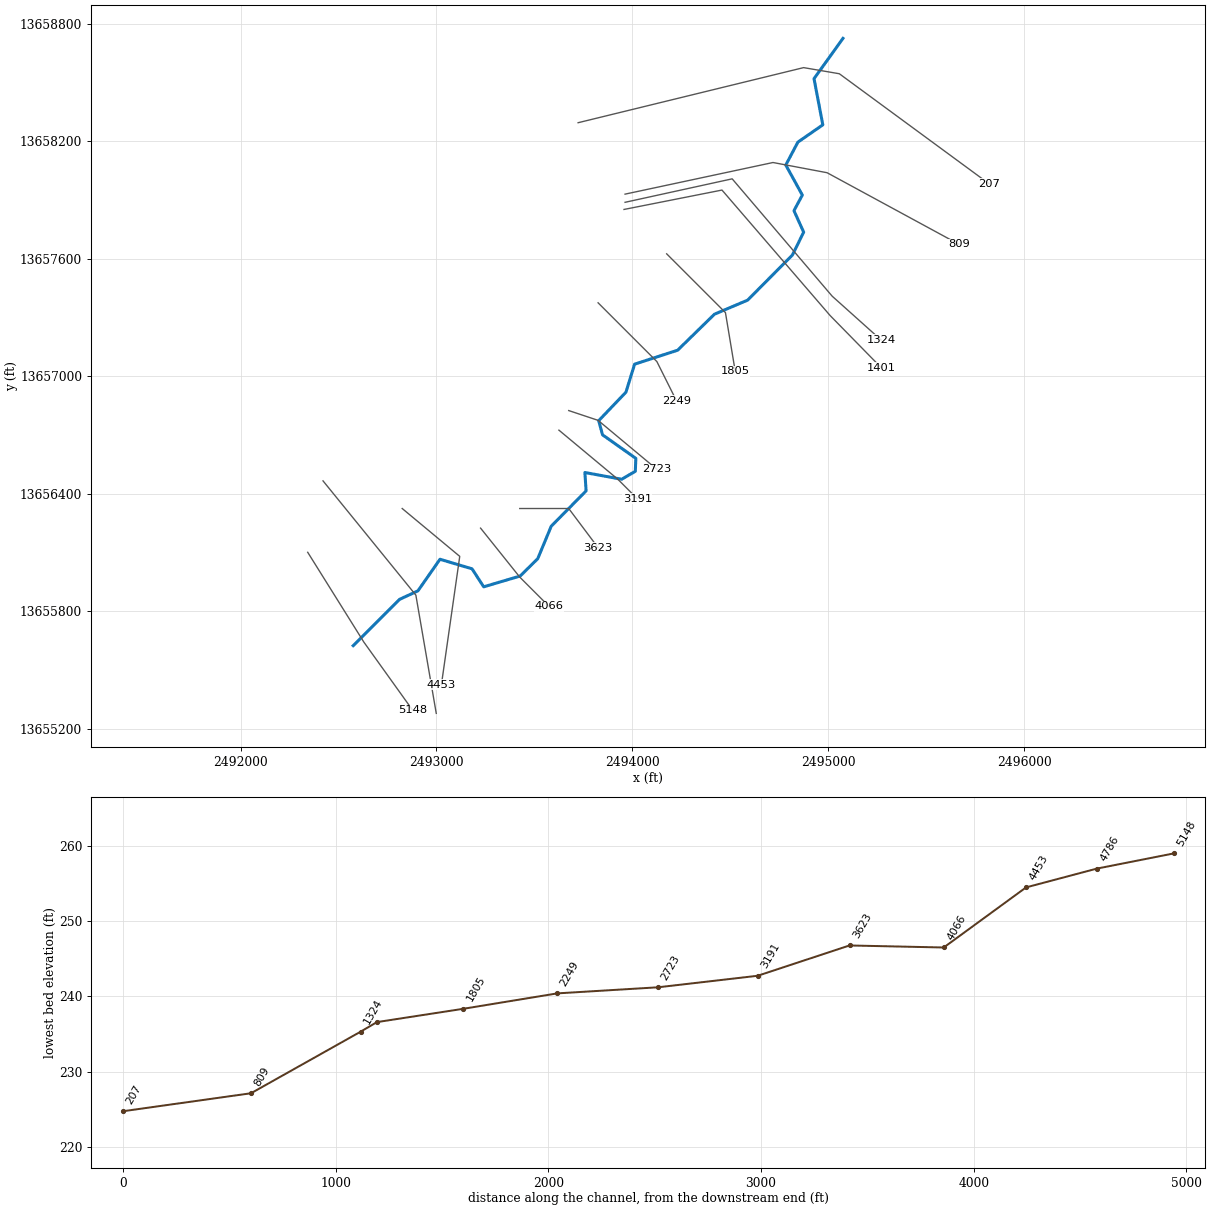
--- Stream0340.prj (project) ---

Proj Title=Stream0340 Base Level Engineering
Current Plan=p01
Default Exp/Contr=0.3,0.1
English Units
Geom File=g01
Flow File=f01
Plan File=p01
BEGIN DESCRIPTION:
Stream0340
END DESCRIPTION:

--- Stream0340.p01 (plan) ---

Plan Title=Multiple Run
Short Identifier=Multiple
Geom File=g01
Flow File=f01
Subcritical Flow
K Sum by GR= 0
Std Step Tol= 0.01
Critical Tol= 0.01
Num of Std Step Trials= 20
Max Error Tol= 0.3
Flow Tol Ratio= 0.001
Split Flow NTrial= 30
Split Flow Tol= 0.02
Split Flow Ratio= 0.02
Log Output Level= 0
Friction Slope Method= 1
Unsteady Friction Slope Method= 2
Unsteady Bridges Friction Slope Method= 1
Parabolic Critical Depth
Global Vel Dist=  1 , 1 , 1
Global Log Level= 0
CheckData=True
Encroach Param= -1, 0, 0, 0
BEGIN DESCRIPTION:
Multiple Run
END DESCRIPTION:

--- Stream0340.f01 (steady flow) ---

Flow Title=Multiple
Number of Profiles=7
Profile Names=10-year,25-year,50-year,1pct_min,100-year,1pct_plu,500-year
River Rch & RM= Stream0340,Reach-1,5148
     679    1096    1475     962    1919    3828    3213
Boundary for River Rch & Prof#=Stream0340,Reach-1,1
Up Type=0
Dn Type=3
Dn Slope=0.005
Boundary for River Rch & Prof#=Stream0340,Reach-1,2
Up Type=0
Dn Type=3
Dn Slope=0.005
Boundary for River Rch & Prof#=Stream0340,Reach-1,3
Up Type=0
Dn Type=3
Dn Slope=0.005
Boundary for River Rch & Prof#=Stream0340,Reach-1,4
Up Type=0
Dn Type=3
Dn Slope=0.005
Boundary for River Rch & Prof#=Stream0340,Reach-1,5
Up Type=0
Dn Type=3
Dn Slope=0.005
Boundary for River Rch & Prof#=Stream0340,Reach-1,6
Up Type=0
Dn Type=3
Dn Slope=0.005
Boundary for River Rch & Prof#=Stream0340,Reach-1,7
Up Type=0
Dn Type=3
Dn Slope=0.005

--- Stream0340.g01 (geometry) ---

Geom Title=Existing Conditions

River Reach=Stream0340,Reach-1
Reach XY= 30
      2492575.00     13655625.00      2492811.79     13655861.37
      2492905.23     13655904.59      2493017.98     13656065.99
      2493181.44     13656017.20      2493241.02     13655925.25
      2493427.44     13655980.52      2493516.87     13656068.93
      2493585.76     13656234.68      2493763.75     13656415.01
      2493757.47     13656508.78      2493945.16     13656474.30
      2494014.98     13656514.94      2494017.55     13656581.04
      2493847.55     13656701.16      2493828.08     13656773.32
      2493967.14     13656918.83      2494011.28     13657061.77
      2494231.06     13657133.14      2494418.94     13657316.86
      2494588.21     13657388.62      2494816.86     13657618.94
      2494874.25     13657735.69      2494824.80     13657845.20
      2494867.44     13657925.00      2494783.02     13658078.31
      2494844.76     13658195.13      2494972.02     13658283.34
      2494927.14     13658519.04      2495075.00     13658725.00

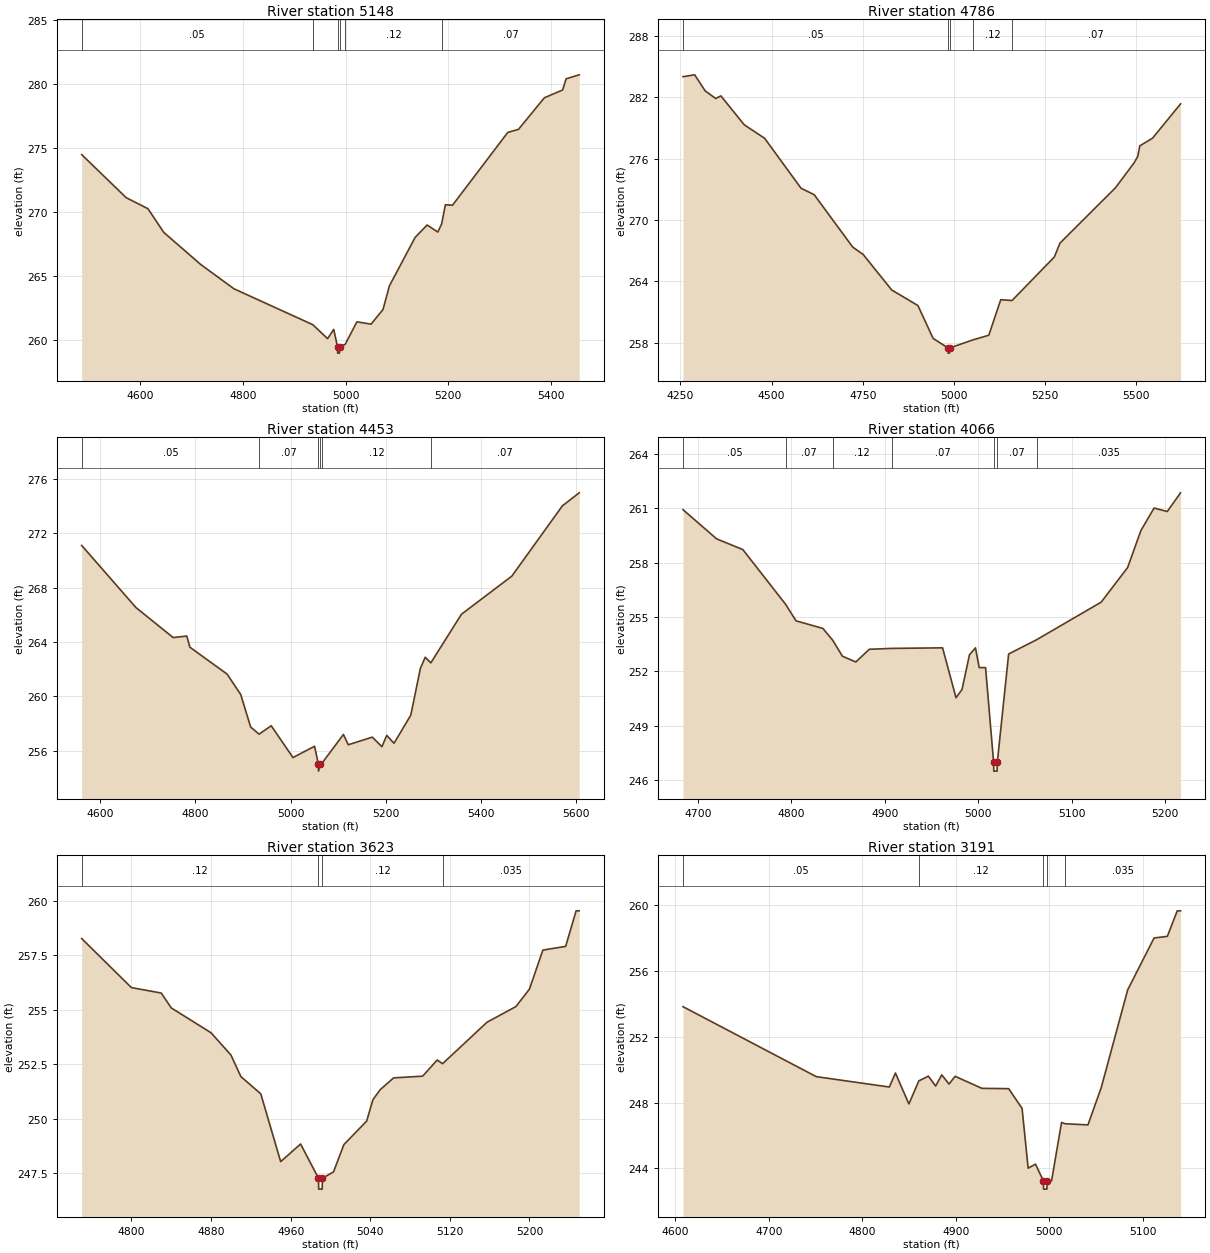
Type RM Length L Ch R = 1,5148,362,362,362
BEGIN DESCRIPTION:
XS6521
END DESCRIPTION:
XS GIS Cut Line= 3
      2492342.71     13656101.56      2492629.17     13655643.23
      2492879.19     13655294.23
#Sta/Elev= 30
  4485.6  274.49  4572.4  271.13  4614.9  270.27  4645.5  268.43  4717.4  265.93
  4782.3  264.03  4936.0  261.23  4965.0  260.14  4976.9  260.86  4984.3  259.51
  4984.6  259.01  4988.1  259.01  4988.3  259.51  4999.2  259.69  5022.1  261.45
  5049.7  261.27  5073.0  262.41  5085.4  264.25  5135.7  268.04  5159.0  269.00
  5179.9  268.45  5187.3  269.09  5194.6  270.58  5208.4  270.54  5316.2  276.22
  5337.1  276.46  5387.5  278.92  5423.1  279.53  5429.9  280.40  5455.4  280.71
#Mann=6,-1,0
  4485.6    0.05       0  4936.0    0.07       0  4984.3    0.05       0
  4988.3    0.07       0  4999.2    0.12       0  5187.3    0.07       0
Bank Sta=4984.3,4988.3
Exp/Cntr=0.3,0.1

Type RM Length L Ch R = 1,4786,333,333,333
BEGIN DESCRIPTION:
Stream0340 11.0
END DESCRIPTION:
XS GIS Cut Line= 3
      2492420.85     13656466.13      2492894.79     13655882.81
      2492998.84     13655279.31
#Sta/Elev= 30
  4257.1  284.00  4289.1  284.18  4317.9  282.61  4346.6  281.87  4361.0  282.12
  4424.9  279.30  4480.9  277.98  4580.7  273.10  4616.7  272.47  4722.4  267.35
  4751.0  266.63  4829.3  263.16  4901.1  261.64  4942.8  258.43  4983.9  257.49
  4984.1  256.99  4987.6  256.99  4987.9  257.49  5051.6  258.28  5095.5  258.74
  5128.2  262.21  5159.2  262.13  5275.1  266.38  5290.6  267.74  5442.8  273.15
  5493.6  275.57  5503.7  276.20  5509.5  277.24  5544.3  277.99  5621.1  281.34
#Mann=5,-1,0
  4257.1    0.05       0  4983.9    0.05       0  4987.9    0.05       0
  5051.6    0.12       0  5159.2    0.07       0
Bank Sta=4983.9,4987.9
Exp/Cntr=0.3,0.1

Type RM Length L Ch R = 1,4453,387,387,387
BEGIN DESCRIPTION:
Stream0340 10.0
END DESCRIPTION:
XS GIS Cut Line= 3
      2492825.00     13656325.00      2493118.75     13656080.73
      2493025.01     13655425.04
#Sta/Elev= 30
  4561.6  271.10  4675.5  266.53  4753.6  264.32  4782.3  264.43  4788.8  263.61
  4866.9  261.63  4895.6  260.12  4916.4  257.73  4934.0  257.21  4959.5  257.83
  5005.2  255.49  5050.5  256.32  5058.6  254.99  5058.8  254.49  5062.6  254.99
  5066.2  255.08  5111.1  257.19  5121.2  256.43  5171.7  256.99  5191.9  256.29
  5202.0  257.12  5217.3  256.54  5252.5  258.61  5272.7  262.06  5282.8  262.87
  5294.6  262.46  5358.7  266.03  5464.6  268.84  5570.7  274.01  5606.0  274.97
#Mann=6,-1,0
  4561.6    0.05       0  4934.0    0.07       0  5058.6    0.05       0
  5062.6    0.07       0  5066.2    0.12       0  5294.6    0.07       0
Bank Sta=5058.6,5062.6
Exp/Cntr=0.3,0.1

Type RM Length L Ch R = 1,4066,443,443,443
BEGIN DESCRIPTION:
Stream0340 9.0
END DESCRIPTION:
XS GIS Cut Line= 3
      2493225.01     13656224.99      2493425.00     13655975.00
      2493575.01     13655824.99
#Sta/Elev= 30
  4684.0  260.92  4720.0  259.31  4748.0  258.72  4793.8  255.70  4804.9  254.79
  4833.7  254.37  4844.3  253.71  4854.5  252.84  4868.9  252.52  4883.3  253.22
  4907.3  253.27  4961.7  253.30  4976.1  250.55  4982.5  251.00  4990.5  252.92
  4996.9  253.30  5000.9  252.21  5007.7  252.21  5016.3  247.00  5016.5  246.50
  5020.0  246.50  5020.3  247.00  5032.4  252.96  5062.4  253.75  5131.4  255.82
  5159.7  257.73  5173.9  259.77  5188.0  261.01  5202.1  260.82  5216.3  261.85
#Mann=7,-1,0
  4684.0    0.05       0  4793.8    0.07       0  4844.3    0.12       0
  4907.3    0.07       0  5016.3    0.05       0  5020.3    0.07       0
  5062.4   0.035       0
Bank Sta=5016.3,5020.3
Exp/Cntr=0.3,0.1

Type RM Length L Ch R = 1,3623,432,432,432
BEGIN DESCRIPTION:
Stream0340 8.0
END DESCRIPTION:
XS GIS Cut Line= 3
      2493425.02     13656325.00      2493675.00     13656325.00
      2493825.01     13656124.99
#Sta/Elev= 30
  4750.0  258.26  4800.0  256.01  4830.0  255.76  4840.0  255.08  4880.0  253.94
  4900.0  252.92  4910.0  251.93  4930.0  251.14  4950.0  248.03  4970.0  248.84
  4988.0  247.27  4988.2  246.77  4991.7  246.77  4992.0  247.27  5003.1  247.56
  5013.5  248.81  5036.4  249.89  5042.7  250.87  5050.0  251.33  5063.5  251.87
  5092.7  251.95  5107.3  252.69  5112.7  252.52  5157.3  254.42  5186.4  255.14
  5200.0  255.94  5213.5  257.73  5236.4  257.90  5246.9  259.53  5250.0  259.53
#Mann=4,-1,0
  4750.0    0.12       0  4988.0    0.05       0  4992.0    0.12       0
  5112.7   0.035       0
Bank Sta=4988,4992
Exp/Cntr=0.3,0.1

Type RM Length L Ch R = 1,3191,468,468,468
BEGIN DESCRIPTION:
Stream0340 7.0
END DESCRIPTION:
XS GIS Cut Line= 3
      2493625.00     13656725.00      2493925.00     13656475.00
      2494024.98     13656375.02
#Sta/Elev= 30
  4608.3  253.82  4750.8  249.57  4828.9  248.94  4835.4  249.79  4849.8  247.91
  4860.4  249.31  4870.6  249.60  4878.4  249.00  4884.9  249.68  4892.7  249.12
  4899.2  249.59  4927.9  248.86  4956.5  248.84  4970.8  247.64  4977.3  244.01
  4985.1  244.26  4993.6  243.24  4993.8  242.74  4997.3  242.74  4997.6  243.24
  5002.3  243.24  5013.0  246.79  5016.7  246.71  5041.2  246.64  5055.4  248.90
  5083.7  254.84  5111.9  257.99  5126.1  258.09  5136.7  259.64  5140.2  259.64
#Mann=5,-1,0
  4608.3    0.05       0  4860.4    0.12       0  4993.6    0.05       0
  4997.6    0.12       0  5016.7   0.035       0
Bank Sta=4993.6,4997.6
Exp/Cntr=0.3,0.1

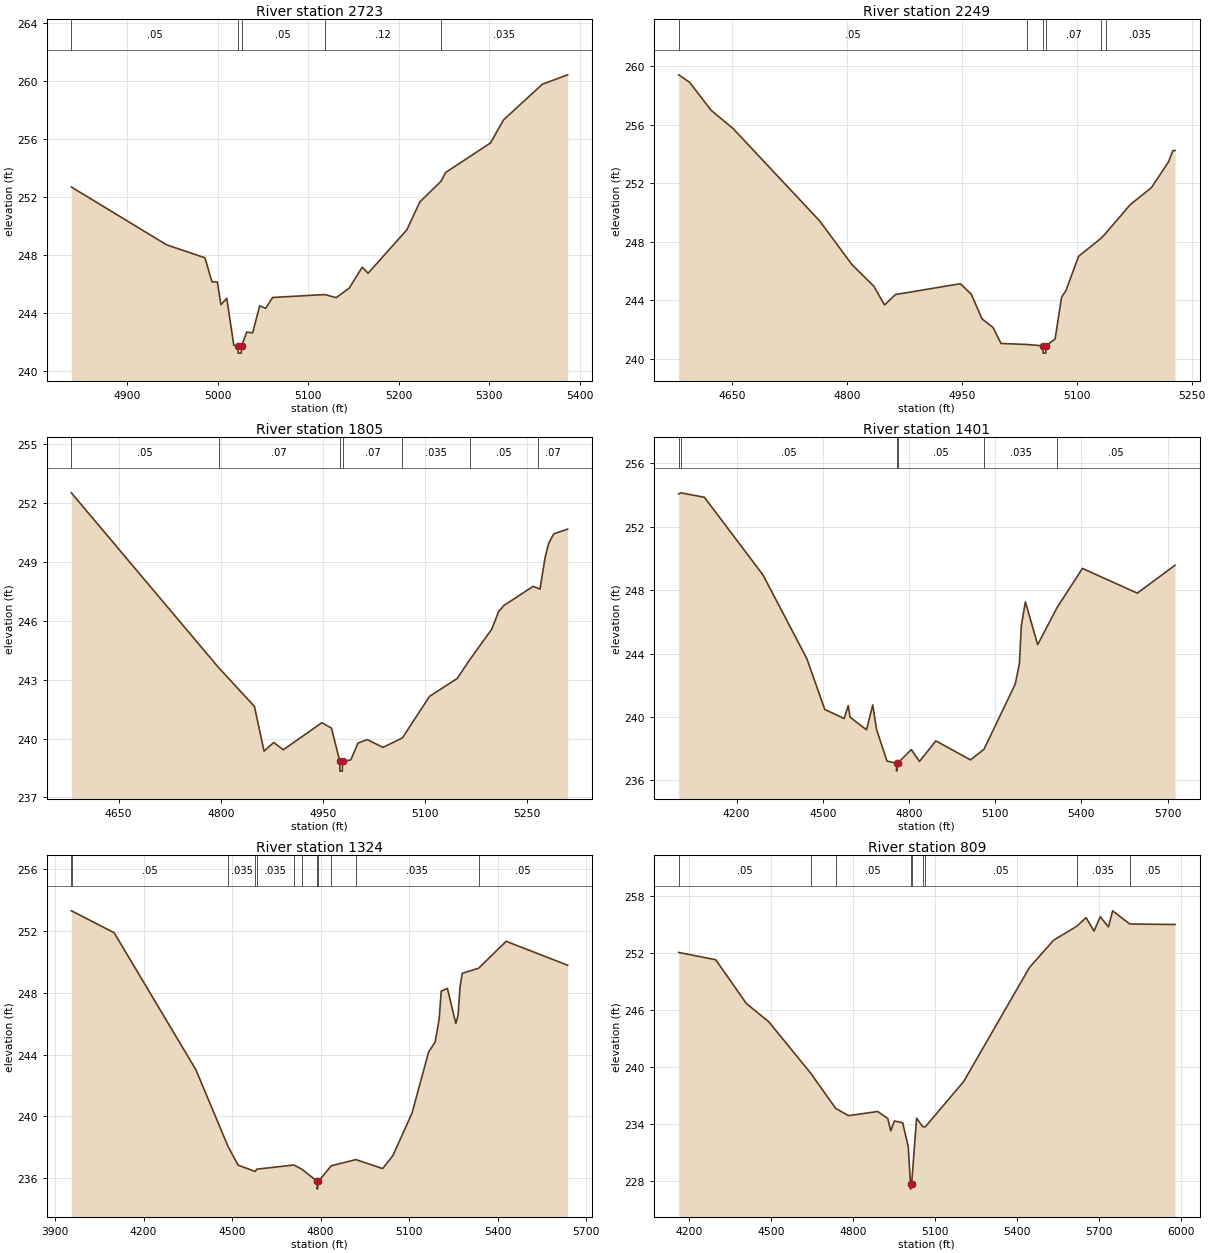
Type RM Length L Ch R = 1,2723,474,474,474
BEGIN DESCRIPTION:
Stream0340 6.0
END DESCRIPTION:
XS GIS Cut Line= 3
      2493675.02     13656824.99      2493825.00     13656775.00
      2494124.99     13656525.01
#Sta/Elev= 30
  4838.2  252.67  4943.6  248.68  4985.8  247.79  4993.7  246.12  4999.6  246.12
  5003.5  244.55  5010.0  244.99  5017.8  241.74  5022.3  241.71  5022.5  241.21
  5026.0  241.21  5026.3  241.71  5032.1  242.66  5038.6  242.61  5046.4  244.48
  5052.9  244.30  5060.7  245.05  5118.3  245.25  5131.0  245.04  5145.3  245.69
  5159.7  247.14  5166.2  246.72  5209.1  249.72  5223.4  251.64  5246.7  253.06
  5252.1  253.68  5301.5  255.71  5315.9  257.30  5358.8  259.76  5386.8  260.41
#Mann=5,-1,0
  4838.2    0.05       0  5022.3    0.05       0  5026.3    0.05       0
  5118.3    0.12       0  5246.7   0.035       0
Bank Sta=5022.3,5026.3
Exp/Cntr=0.3,0.1

Type RM Length L Ch R = 1,2249,444,444,444
BEGIN DESCRIPTION:
Stream0340 5.0
END DESCRIPTION:
XS GIS Cut Line= 3
      2493824.97     13657375.03      2494125.00     13657075.00
      2494224.99     13656875.01
#Sta/Elev= 30
  4580.3  259.41  4594.5  258.90  4622.8  256.98  4651.1  255.75  4764.2  249.44
  4806.6  246.44  4834.9  244.98  4849.0  243.69  4863.2  244.40  4948.0  245.14
  4962.2  244.43  4976.3  242.74  4990.5  242.16  5001.1  241.06  5035.1  240.99
  5055.7  240.90  5056.0  240.40  5059.5  240.40  5059.7  240.90  5071.7  241.37
  5080.1  244.22  5085.7  244.66  5102.4  247.02  5131.8  248.25  5137.5  248.57
  5169.5  250.53  5197.5  251.71  5219.8  253.47  5225.4  254.24  5228.2  254.24
#Mann=6,-1,0
  4580.3    0.05       0  5035.1    0.07       0  5055.7    0.05       0
  5059.7    0.07       0  5131.8    0.05       0  5137.5   0.035       0
Bank Sta=5055.7,5059.7
Exp/Cntr=0.3,0.1

Type RM Length L Ch R = 1,1805,404,404,404
BEGIN DESCRIPTION:
Stream0340 4.0
END DESCRIPTION:
XS GIS Cut Line= 3
      2494175.01     13657624.99      2494475.00     13657325.00
      2494525.00     13657024.99
#Sta/Elev= 30
  4580.8  252.53  4796.9  243.62  4849.5  241.64  4863.6  239.36  4877.8  239.80
  4891.9  239.43  4948.5  240.81  4962.6  240.53  4974.8  238.84  4975.0  238.34
  4978.5  238.34  4978.8  238.84  4990.9  238.91  5001.5  239.77  5015.2  239.95
  5038.0  239.55  5066.6  240.03  5106.4  242.15  5147.0  243.06  5165.9  244.04
  5197.7  245.57  5207.8  246.47  5215.4  246.78  5258.5  247.76  5265.3  247.67
  5268.6  247.62  5276.2  249.25  5281.3  249.95  5288.9  250.44  5309.2  250.68
#Mann=7,-1,0
  4580.8    0.05       0  4796.9    0.07       0  4974.8    0.05       0
  4978.8    0.07       0  5066.6   0.035       0  5165.9    0.05       0
  5265.3    0.07       0
Bank Sta=4974.8,4978.8
Exp/Cntr=0.3,0.1

Type RM Length L Ch R = 1,1401,77,77,77
BEGIN DESCRIPTION:
XS6520
END DESCRIPTION:
XS GIS Cut Line= 4
      2493957.27     13657851.56      2494457.29     13657950.52
      2495009.38     13657309.90      2495269.79     13657044.27
#Sta/Elev= 30
  3998.5  254.07  4005.7  254.14  4087.9  253.86  4291.8  248.96  4444.7  243.67
  4506.9  240.47  4574.3  239.90  4588.5  240.71  4595.1  239.98  4652.2  239.19
  4673.9  240.76  4687.3  239.20  4723.5  237.21  4756.6  237.08  4756.8  236.58
  4760.6  237.08  4808.0  237.94  4836.5  237.19  4893.5  238.49  5014.2  237.29
  5061.1  237.96  5170.0  242.08  5184.3  243.36  5190.9  245.74  5205.1  247.26
  5247.9  244.56  5315.4  246.90  5403.7  249.37  5594.7  247.81  5725.9  249.57
#Mann=6,-1,0
  3998.5    0.07       0  4005.7    0.05       0  4756.6    0.05       0
  4760.6    0.05       0  5061.1   0.035       0  5315.4    0.05       0
Bank Sta=4756.6,4760.6
Exp/Cntr=0.3,0.1

Type RM Length L Ch R = 1,1324,515,515,515
BEGIN DESCRIPTION:
XS6519
END DESCRIPTION:
XS GIS Cut Line= 4
      2493962.54     13657888.03      2494509.38     13658007.81
      2495019.79     13657408.85      2495269.80     13657184.89
#Sta/Elev= 30
  3955.2  253.30  3956.0  253.30  4100.3  251.88  4377.4  243.02  4486.1  238.07
  4520.6  236.85  4579.0  236.44  4583.4  236.59  4709.8  236.86  4737.3  236.58
  4788.8  235.80  4789.0  235.30  4792.8  235.80  4836.1  236.81  4919.8  237.21
  5010.4  236.63  5045.5  237.48  5109.9  240.21  5166.3  244.17  5188.3  244.81
  5201.9  246.28  5209.1  248.11  5230.0  248.28  5258.5  246.01  5266.2  246.55
  5272.8  248.39  5280.5  249.26  5335.9  249.59  5429.1  251.33  5637.6  249.78
#Mann=12,-1,0
  3955.2    0.07       0  3956.0    0.05       0  4486.1   0.035       0
  4579.0    0.05       0  4583.4   0.035       0  4709.8    0.05       0
  4737.3   0.035       0  4788.8   0.035       0  4792.8   0.035       0
  4836.1    0.05       0  4919.8   0.035       0  5335.9    0.05       0
Bank Sta=4788.8,4792.8
Exp/Cntr=0.3,0.1

Type RM Length L Ch R = 1,809,602,602,602
BEGIN DESCRIPTION:
XS6518
END DESCRIPTION:
XS GIS Cut Line= 4
      2493962.54     13657929.70      2494717.71     13658091.15
      2494993.75     13658039.06      2495665.65     13657674.46
#Sta/Elev= 30
  4161.1  252.09  4296.6  251.32  4409.0  246.70  4490.8  244.78  4645.4  239.32
  4736.1  235.63  4783.3  234.87  4889.7  235.31  4926.7  234.58  4937.6  233.27
  4950.9  234.31  4981.5  234.11  5001.8  231.59  5010.0  227.62  5010.2  227.12
  5014.0  227.62  5032.3  234.61  5055.1  233.70  5064.4  233.70  5204.7  238.47
  5445.9  250.51  5534.2  253.38  5618.8  254.85  5653.1  255.76  5682.1  254.34
  5704.9  255.86  5734.9  254.78  5750.4  256.48  5812.8  255.09  5978.7  255.04
#Mann=9,-1,0
  4161.1    0.05       0  4645.4   0.035       0  4736.1    0.05       0
  5010.0    0.05       0  5014.0    0.05       0  5055.1     0.1       0
  5064.4    0.05       0  5618.8   0.035       0  5812.8    0.05       0
Bank Sta=5010,5014
Exp/Cntr=0.3,0.1

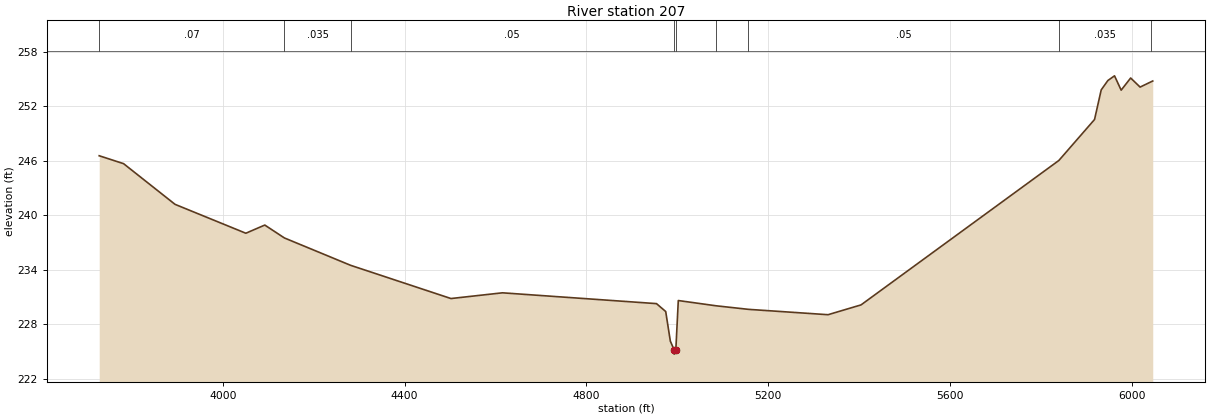
Type RM Length L Ch R = 1,207,0,0,0
BEGIN DESCRIPTION:
XS6517
END DESCRIPTION:
XS GIS Cut Line= 4
      2493722.91     13658294.27      2494873.96     13658575.52
      2495056.25     13658544.27      2495820.90     13657982.48
#Sta/Elev= 30
  3727.9  246.57  3781.5  245.70  3894.8  241.22  4050.6  238.04  4092.3  238.94
  4135.5  237.52  4281.1  234.51  4502.1  230.85  4615.3  231.48  4954.4  230.29
  4974.7  229.42  4984.9  226.16  4993.0  225.23  4993.3  224.73  4997.0  225.23
  5002.4  230.63  5085.7  230.05  5156.9  229.66  5332.0  229.07  5404.6  230.15
  5840.0  246.05  5918.5  250.56  5933.2  253.82  5947.8  254.85  5962.5  255.37
  5977.1  253.79  5998.0  255.13  6018.8  254.13  6042.4  254.70  6046.6  254.80
#Mann=9,-1,0
  3727.9    0.07       0  4135.5   0.035       0  4281.1    0.05       0
  4993.0    0.05       0  4997.0    0.05       0  5085.7    0.07       0
  5156.9    0.05       0  5840.0   0.035       0  6042.4    0.05       0
Bank Sta=4993,4997
Exp/Cntr=0.3,0.1

Chan Stop Cuts=-1