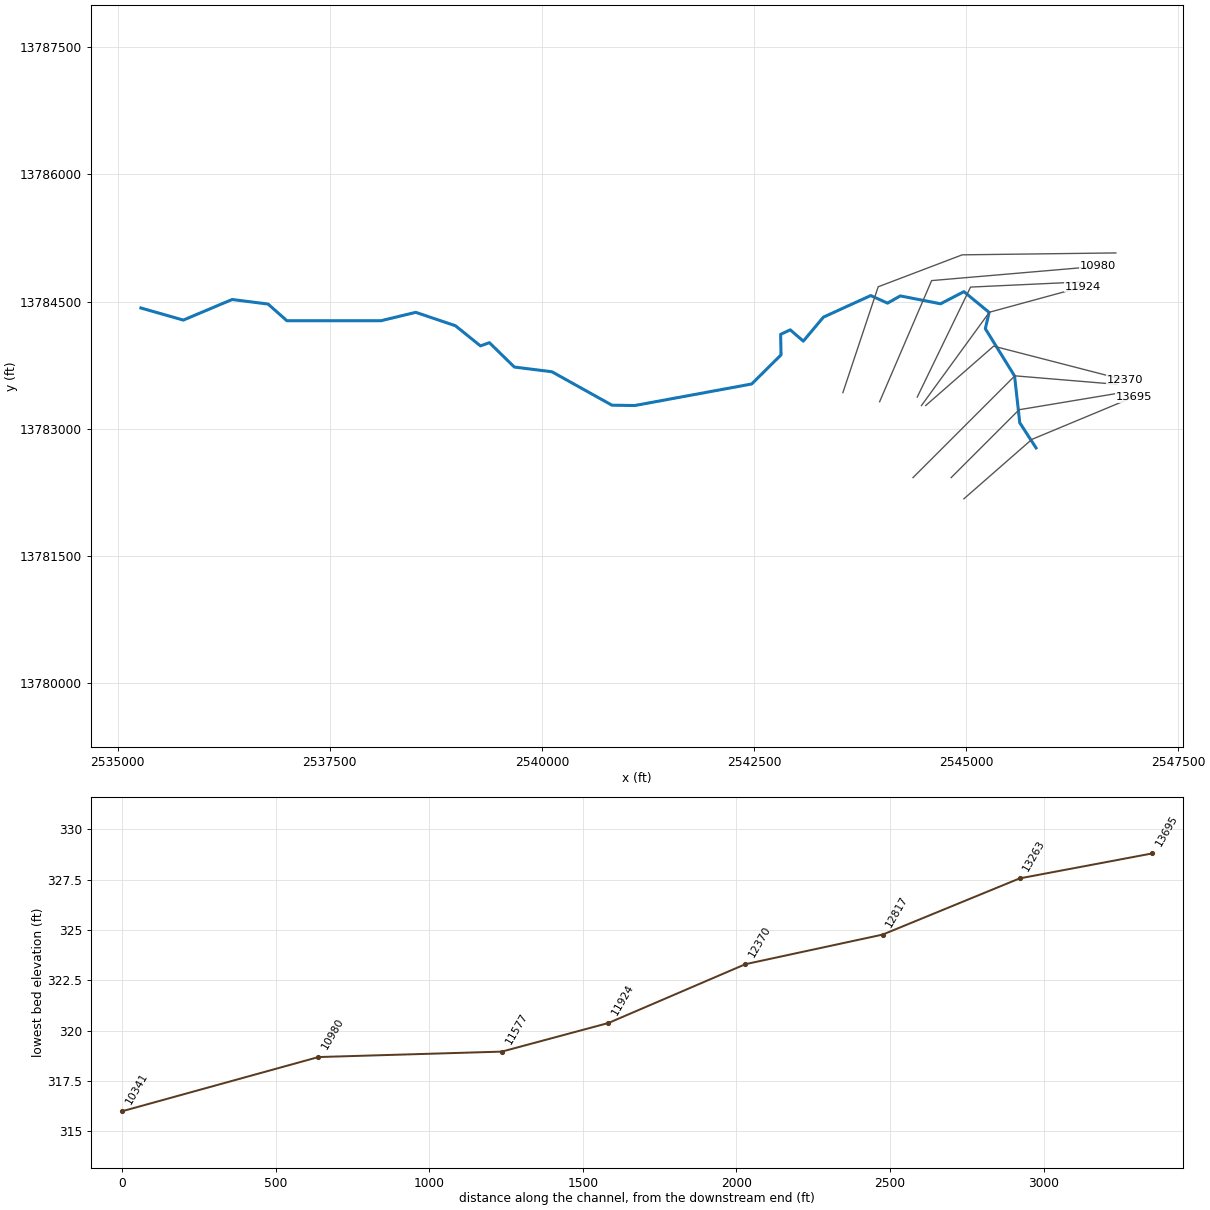
--- Stream0347.prj (project) ---

Proj Title=Stream0347 Base Level Engineering
Current Plan=p01
Default Exp/Contr=0.3,0.1
English Units
Geom File=g01
Flow File=f01
Plan File=p01
BEGIN DESCRIPTION:
Stream0347
END DESCRIPTION:

--- Stream0347.p01 (plan) ---

Plan Title=Multiple Run
Short Identifier=Multiple
Geom File=g01
Flow File=f01
Subcritical Flow
K Sum by GR= 0
Std Step Tol= 0.01
Critical Tol= 0.01
Num of Std Step Trials= 20
Max Error Tol= 0.3
Flow Tol Ratio= 0.001
Split Flow NTrial= 30
Split Flow Tol= 0.02
Split Flow Ratio= 0.02
Log Output Level= 0
Friction Slope Method= 1
Unsteady Friction Slope Method= 2
Unsteady Bridges Friction Slope Method= 1
Parabolic Critical Depth
Global Vel Dist=  1 , 1 , 1
Global Log Level= 0
CheckData=True
Encroach Param= -1, 0, 0, 0
BEGIN DESCRIPTION:
Multiple Run
END DESCRIPTION:

--- Stream0347.f01 (steady flow) ---

Flow Title=Multiple
Number of Profiles=7
Profile Names=10-year,25-year,50-year,1pct_min,100-year,1pct_plu,500-year
River Rch & RM= Stream0347,Reach-1,13695
     869    1415    1915    1255    2505    4998    4238
River Rch & RM= Stream0347,Reach-1,11577
    1131    1854    2519    1654    3300    6584    5608
Boundary for River Rch & Prof#=Stream0347,Reach-1,1
Up Type=0
Dn Type=3
Dn Slope=0.005
Boundary for River Rch & Prof#=Stream0347,Reach-1,2
Up Type=0
Dn Type=3
Dn Slope=0.005
Boundary for River Rch & Prof#=Stream0347,Reach-1,3
Up Type=0
Dn Type=3
Dn Slope=0.005
Boundary for River Rch & Prof#=Stream0347,Reach-1,4
Up Type=0
Dn Type=3
Dn Slope=0.005
Boundary for River Rch & Prof#=Stream0347,Reach-1,5
Up Type=0
Dn Type=3
Dn Slope=0.005
Boundary for River Rch & Prof#=Stream0347,Reach-1,6
Up Type=0
Dn Type=3
Dn Slope=0.005
Boundary for River Rch & Prof#=Stream0347,Reach-1,7
Up Type=0
Dn Type=3
Dn Slope=0.005

--- Stream0347.g01 (geometry) ---

Geom Title=Existing Conditions

River Reach=Stream0347,Reach-1
Reach XY= 30
      2545825.00     13782775.00      2545632.99     13783071.66
      2545571.86     13783623.36      2545227.14     13784180.97
      2545271.87     13784373.37      2544974.92     13784617.70
      2544700.08     13784474.80      2544224.99     13784567.47
      2544074.92     13784482.30      2543876.50     13784571.53
      2543318.66     13784316.98      2543081.67     13784033.95
      2542928.41     13784167.23      2542814.59     13784114.26
      2542819.55     13783872.54      2542473.48     13783528.74
      2541095.15     13783274.64      2540826.55     13783278.75
      2540119.14     13783672.92      2539676.26     13783728.48
      2539382.01     13784015.97      2539276.65     13783978.17
      2538981.67     13784215.70      2538514.49     13784373.80
      2538104.96     13784275.05      2536994.99     13784274.94
      2536773.54     13784471.46      2536349.92     13784525.20
      2535774.99     13784282.53      2535275.00     13784425.00

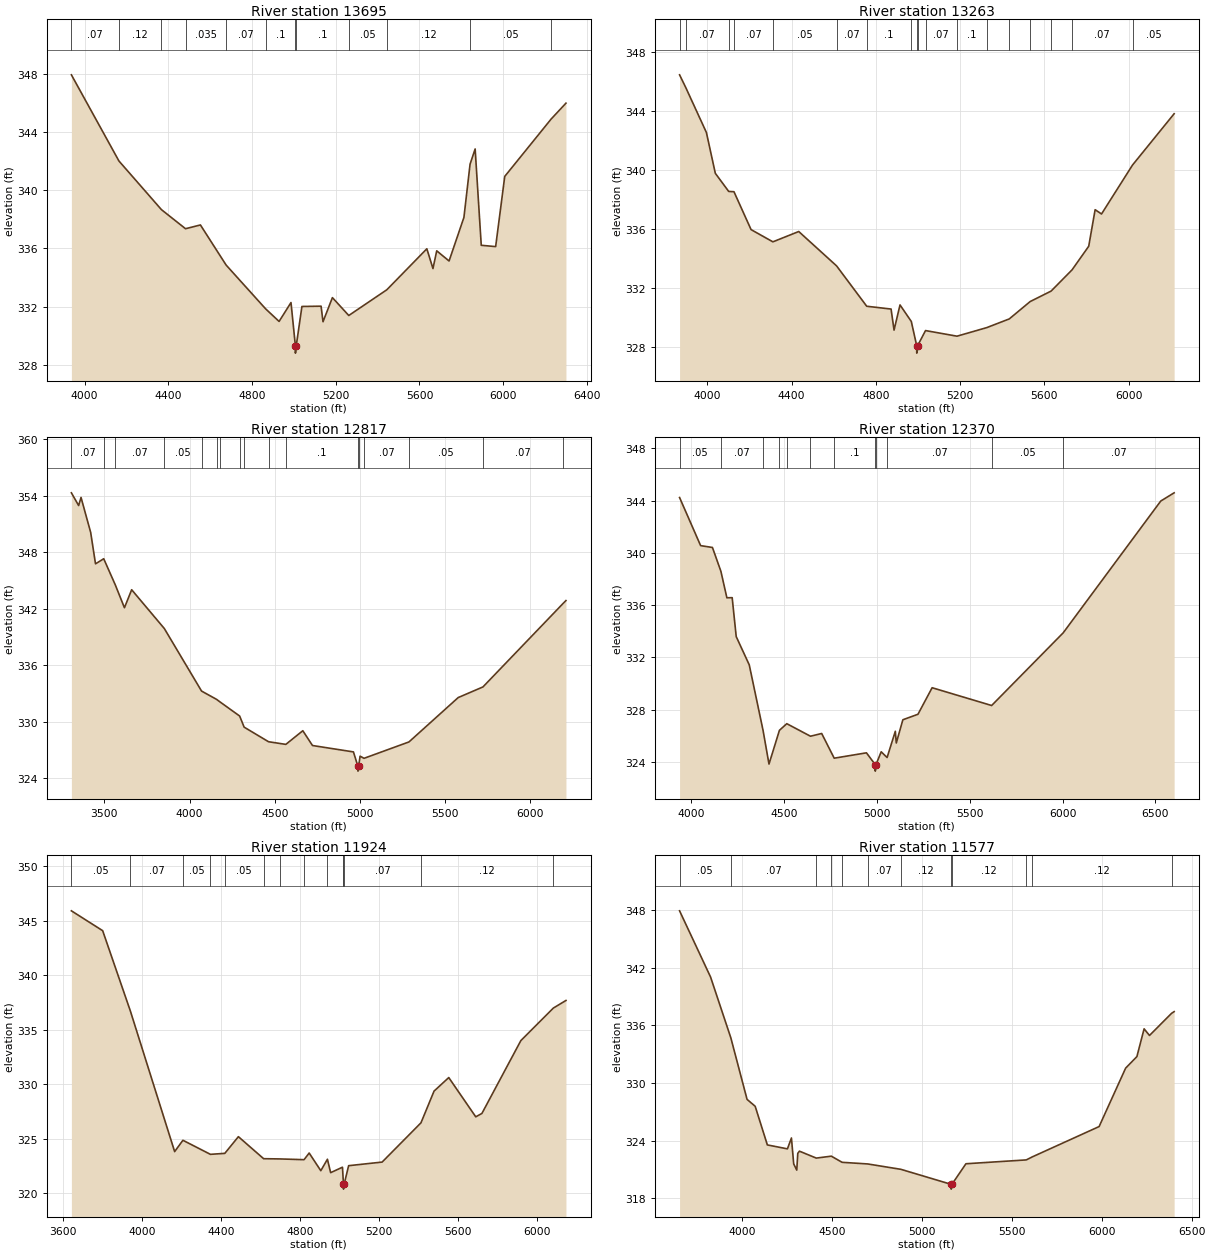
Type RM Length L Ch R = 1,13695,432,432,432
BEGIN DESCRIPTION:
Stream0347 7.0
END DESCRIPTION:
XS GIS Cut Line= 3
      2544974.96     13782174.97      2545775.00     13782875.00
      2546975.04     13783375.01
#Sta/Elev= 30
  3936.8  347.95  4164.0  342.02  4367.3  338.67  4482.2  337.36  4553.3  337.62
  4676.1  334.86  4864.7  331.85  4929.2  330.98  4986.1  332.28  5007.1  329.30
  5007.3  328.80  5011.1  329.30  5038.3  332.01  5129.9  332.03  5139.1  330.96
  5184.0  332.62  5262.2  331.39  5444.0  333.16  5635.2  335.98  5664.5  334.62
  5682.4  335.84  5741.4  335.14  5812.4  338.14  5841.7  341.80  5866.0  342.85
  5895.2  336.22  5964.0  336.13  6007.4  340.96  6228.7  344.90  6299.9  346.00
#Mann=12,-1,0
  3936.8    0.07       0  4164.0    0.12       0  4367.3    0.07       0
  4482.2   0.035       0  4676.1    0.07       0  4864.7     0.1       0
  5007.1    0.05       0  5011.1     0.1       0  5262.2    0.05       0
  5444.0    0.12       0  5841.7    0.05       0  6228.7    0.07       0
Bank Sta=5007.1,5011.1
Exp/Cntr=0.3,0.1

Type RM Length L Ch R = 1,13263,446,446,446
BEGIN DESCRIPTION:
Stream0347 6.0
END DESCRIPTION:
XS GIS Cut Line= 3
      2544825.01     13782425.01      2545625.00     13783225.00
      2546824.98     13783425.00
#Sta/Elev= 30
  3868.6  346.44  3897.9  345.58  3995.9  342.53  4038.3  339.76  4101.8  338.53
  4126.8  338.51  4208.0  335.94  4311.6  335.11  4434.3  335.81  4613.9  333.48
  4757.1  330.74  4872.7  330.55  4886.8  329.12  4915.1  330.83  4968.7  329.71
  4994.4  328.06  4994.6  327.56  4998.5  328.06  5036.2  329.09  5185.6  328.71
  5326.8  329.29  5433.7  329.88  5533.1  331.06  5632.5  331.77  5731.9  333.21
  5811.0  334.81  5841.4  337.29  5871.8  337.00  6018.9  340.32  6216.5  343.80
#Mann=18,-1,0
  3868.6    0.12       0  3897.9    0.07       0  4101.8   0.035       0
  4126.8    0.07       0  4311.6    0.05       0  4613.9    0.07       0
  4757.1     0.1       0  4968.7    0.12       0  4994.4    0.05       0
  4998.5    0.12       0  5036.2    0.07       0  5185.6     0.1       0
  5326.8    0.07       0  5433.7    0.12       0  5533.1    0.07       0
  5632.5    0.05       0  5731.9    0.07       0  6018.9    0.05       0
Bank Sta=4994.4,4998.5
Exp/Cntr=0.3,0.1

Type RM Length L Ch R = 1,12817,447,447,447
BEGIN DESCRIPTION:
Stream0347 5.0
END DESCRIPTION:
XS GIS Cut Line= 3
      2544374.97     13782424.97      2545575.00     13783625.00
      2546775.04     13783525.00
#Sta/Elev= 30
  3306.8  354.32  3349.3  352.97  3363.4  353.83  3420.0  350.11  3448.3  346.78
  3496.5  347.32  3564.5  344.54  3618.0  342.12  3660.4  344.03  3852.0  339.91
  4070.4  333.27  4158.4  332.39  4177.0  332.14  4293.9  330.62  4320.2  329.44
  4463.4  327.89  4564.8  327.61  4664.5  329.06  4721.1  327.49  4961.5  326.81
  4987.7  325.27  4988.0  324.77  4991.8  325.27  5000.4  326.36  5023.5  326.13
  5287.2  327.87  5575.9  332.58  5721.2  333.71  6190.6  342.56  6208.1  342.88
#Mann=17,-1,0
  3306.8    0.07       0  3496.5   0.035       0  3564.5    0.07       0
  3852.0    0.05       0  4070.4    0.07       0  4158.4    0.05       0
  4177.0    0.07       0  4293.9    0.12       0  4320.2    0.07       0
  4463.4    0.12       0  4564.8     0.1       0  4987.7    0.05       0
  4991.8     0.1       0  5023.5    0.07       0  5287.2    0.05       0
  5721.2    0.07       0  6190.6    0.05       0
Bank Sta=4987.7,4991.8
Exp/Cntr=0.3,0.1

Type RM Length L Ch R = 1,12370,446,446,446
BEGIN DESCRIPTION:
Stream0347 4.0
END DESCRIPTION:
XS GIS Cut Line= 3
      2544525.04     13783275.03      2545325.00     13783975.00
      2546874.95     13783575.01
#Sta/Elev= 30
  3937.1  344.23  4050.5  340.55  4114.1  340.41  4159.6  338.59  4191.9  336.56
  4220.4  336.57  4242.2  333.59  4312.4  331.43  4386.7  326.42  4418.7  323.84
  4474.9  326.42  4514.5  326.93  4642.2  325.97  4702.5  326.18  4769.9  324.29
  4943.6  324.70  4990.8  323.80  4991.1  323.30  4995.1  323.80  5023.0  324.78
  5054.8  324.34  5099.1  326.35  5104.3  325.45  5139.8  327.23  5221.1  327.65
  5297.3  329.68  5617.9  328.32  6003.3  333.88  6528.6  343.96  6600.8  344.59
#Mann=12,-1,0
  3937.1    0.05       0  4159.6    0.07       0  4386.7     0.1       0
  4474.9    0.05       0  4514.5    0.07       0  4642.2    0.05       0
  4769.9     0.1       0  4990.8    0.05       0  4995.1     0.1       0
  5054.8    0.07       0  5617.9    0.05       0  6003.3    0.07       0
Bank Sta=4990.8,4995.1
Exp/Cntr=0.3,0.1

Type RM Length L Ch R = 1,11924,347,347,347
BEGIN DESCRIPTION:
Stream0347 3.0
END DESCRIPTION:
XS GIS Cut Line= 3
      2544474.99     13783274.99      2545275.00     13784375.00
      2546374.97     13784674.99
#Sta/Elev= 30
  3644.1  345.90  3802.2  344.08  3942.5  336.70  4166.1  323.82  4207.9  324.86
  4346.9  323.57  4419.7  323.66  4488.4  325.19  4616.0  323.17  4696.2  323.15
  4820.4  323.08  4846.2  323.69  4905.0  322.07  4938.5  323.12  4954.8  321.89
  5014.6  322.39  5018.1  321.29  5019.4  320.88  5019.7  320.38  5023.7  320.88
  5045.7  322.53  5215.0  322.86  5411.4  326.46  5477.6  329.37  5551.9  330.61
  5688.4  327.01  5719.5  327.32  5916.4  334.00  6080.4  336.98  6144.4  337.68
#Mann=14,-1,0
  3644.1    0.05       0  3942.5    0.07       0  4207.9    0.05       0
  4346.9    0.07       0  4419.7    0.05       0  4616.0    0.07       0
  4696.2    0.05       0  4820.4    0.07       0  4938.5    0.05       0
  5018.1    0.07       0  5019.4    0.05       0  5023.7    0.07       0
  5411.4    0.12       0  6080.4    0.07       0
Bank Sta=5019.4,5023.7
Exp/Cntr=0.3,0.1

Type RM Length L Ch R = 1,11577,597,597,597
BEGIN DESCRIPTION:
Stream0347 2.0
END DESCRIPTION:
XS GIS Cut Line= 3
      2544424.99     13783374.97      2545053.13     13784671.70
      2546361.96     13784732.38
#Sta/Elev= 30
  3651.5  347.92  3823.7  341.04  3936.7  334.70  4026.9  328.30  4072.1  327.58
  4139.8  323.56  4251.5  323.15  4273.8  324.28  4286.4  321.58  4303.4  320.94
  4309.0  322.68  4318.2  322.91  4411.9  322.19  4495.5  322.39  4555.7  321.75
  4698.0  321.58  4882.7  321.02  5162.1  319.46  5162.4  318.96  5166.5  319.46
  5244.4  321.60  5580.1  322.00  5613.0  322.31  5985.2  325.47  6132.8  331.55
  6195.4  332.75  6235.5  335.64  6265.5  334.95  6388.6  337.26  6402.6  337.43
#Mann=12,-1,0
  3651.5    0.05       0  3936.7    0.07       0  4411.9    0.05       0
  4495.5    0.07       0  4555.7    0.05       0  4698.0    0.07       0
  4882.7    0.12       0  5162.1    0.05       0  5166.5    0.12       0
  5580.1    0.07       0  5613.0    0.12       0  6388.6    0.07       0
Bank Sta=5162.1,5166.5
Exp/Cntr=0.3,0.1

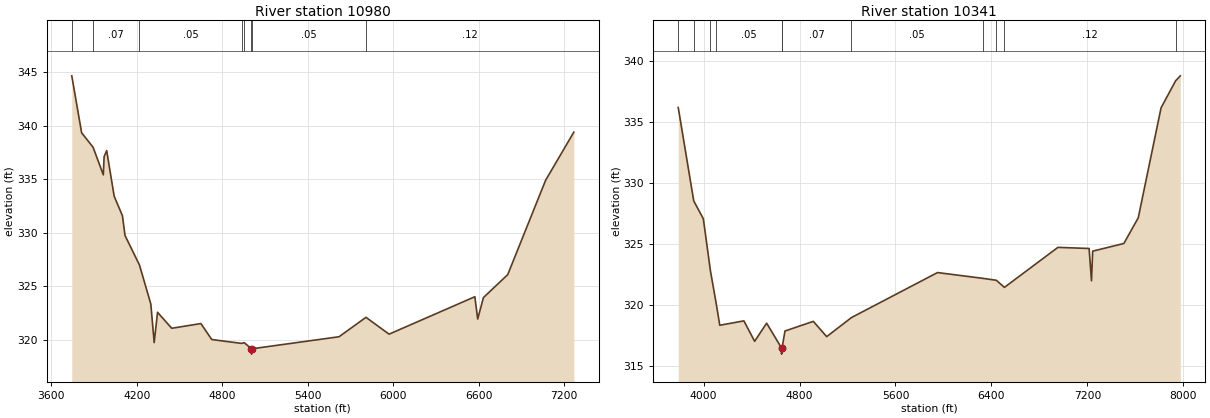
Type RM Length L Ch R = 1,10980,639,639,639
BEGIN DESCRIPTION:
E20908
END DESCRIPTION:
XS GIS Cut Line= 3
      2543981.32     13783319.48      2544594.43     13784748.20
      2546557.48     13784916.94
#Sta/Elev= 30
  3743.0  344.63  3812.3  339.32  3892.8  337.97  3964.5  335.40  3970.0  337.09
  3988.1  337.66  4040.7  333.41  4098.7  331.59  4116.8  329.75  4218.5  326.99
  4298.0  323.36  4321.6  319.77  4345.2  322.59  4444.8  321.10  4649.6  321.54
  4725.8  320.05  4935.1  319.69  4953.5  319.76  5004.5  319.19  5004.8  318.69
  5008.9  319.19  5619.5  320.31  5808.7  322.12  5970.8  320.55  6573.0  324.04
  6593.0  321.96  6633.2  323.96  6803.8  326.10  7070.0  334.90  7268.0  339.38
#Mann=8,-1,0
  3743.0    0.05       0  3892.8    0.07       0  4218.5    0.05       0
  4935.1    0.07       0  4953.5    0.05       0  5004.5    0.05       0
  5008.9    0.05       0  5808.7    0.12       0
Bank Sta=5004.5,5008.9
Exp/Cntr=0.3,0.1

Type RM Length L Ch R = 1,10341,0,0,0
BEGIN DESCRIPTION:
E20907
END DESCRIPTION:
XS GIS Cut Line= 4
      2543548.25     13783426.43      2543964.47     13784675.08
      2544954.41     13785051.93      2546765.53     13785074.43
#Sta/Elev= 30
  3788.4  336.17  3917.7  328.53  3997.7  327.07  4056.6  322.83  4105.7  320.10
  4134.7  318.36  4335.9  318.72  4425.5  317.05  4525.6  318.53  4649.9  316.50
  4650.2  316.00  4654.4  316.50  4654.7  316.53  4678.5  317.89  4914.8  318.68
  5026.3  317.43  5232.9  318.99  5950.5  322.67  6326.8  322.20  6440.8  322.04
  6508.5  321.46  6954.5  324.73  7214.5  324.64  7234.5  322.00  7244.5  324.42
  7504.5  325.05  7624.5  327.15  7814.6  336.14  7935.8  338.35  7975.1  338.76
#Mann=12,-1,0
  3788.4    0.07       0  3917.7    0.12       0  4056.6    0.07       0
  4105.7    0.05       0  4649.9    0.05       0  4654.4    0.05       0
  4654.7    0.07       0  5232.9    0.05       0  6326.8    0.12       0
  6440.8    0.05       0  6508.5    0.12       0  7935.8    0.07       0
Bank Sta=4649.9,4654.4
Exp/Cntr=0.3,0.1

Chan Stop Cuts=-1