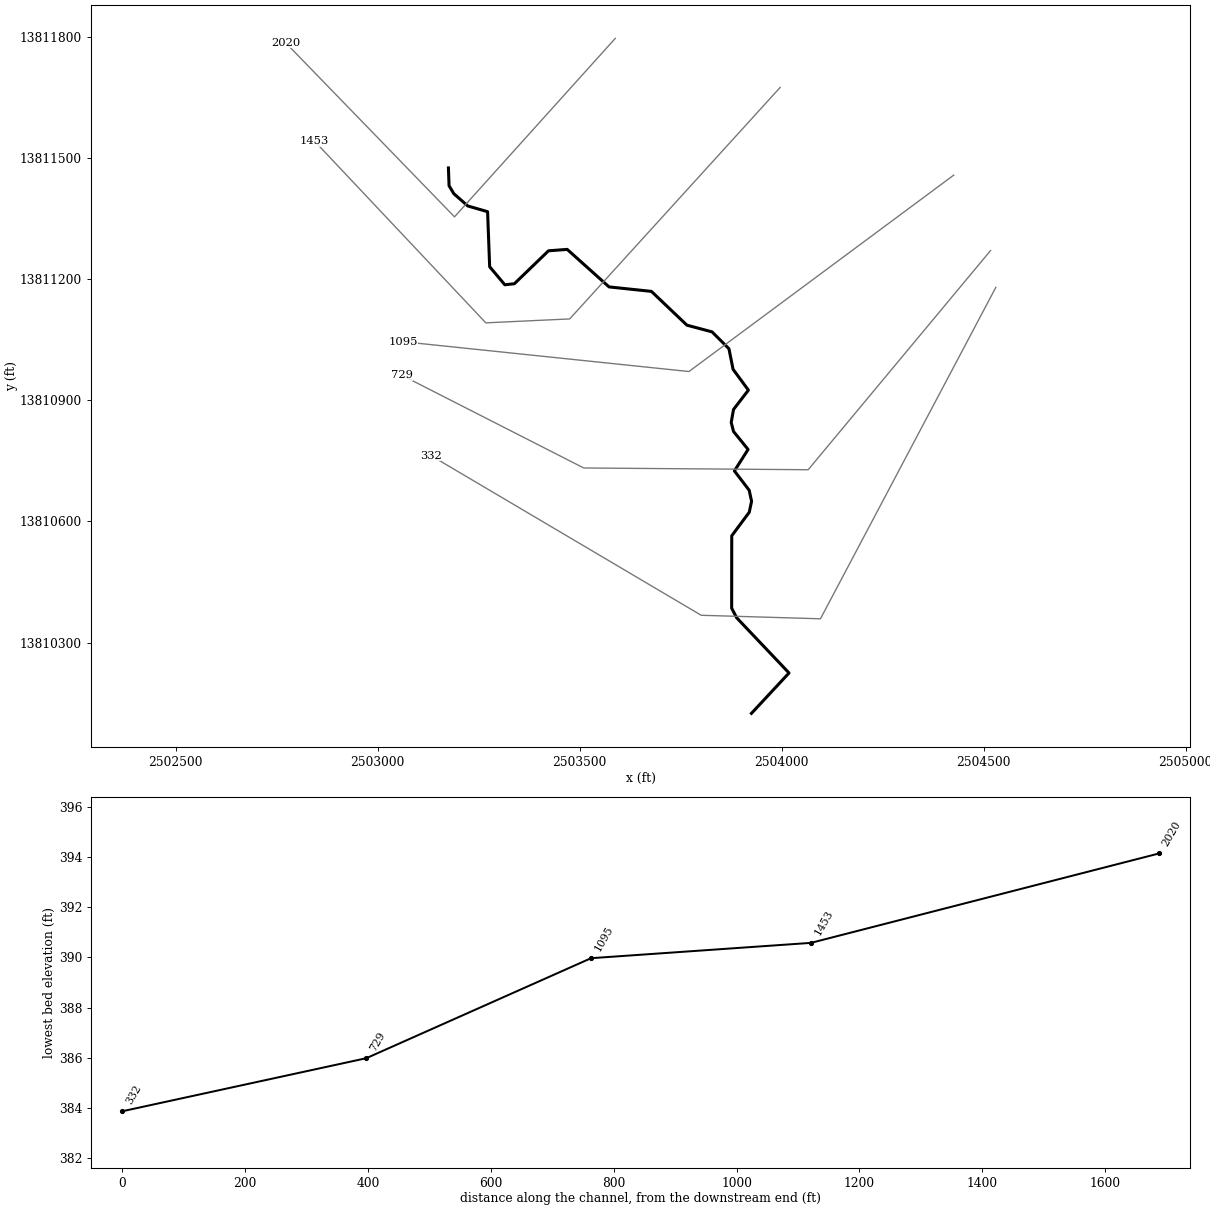
--- Stream0349.prj (project) ---

Proj Title=Stream0349 Base Level Engineering
Current Plan=p01
Default Exp/Contr=0.3,0.1
English Units
Geom File=g01
Flow File=f01
Plan File=p01
Y Axis Title=Elevation
X Axis Title(PF)=Main Channel Distance
X Axis Title(XS)=Station
BEGIN DESCRIPTION:
Stream0349
END DESCRIPTION:
DSS Export Rating Curves= 0
DSS Export Rating Curve Sorted= 0
DSS Export Volume Flow Curves= 0
DXF OffsetX= 0
DXF OffsetY= 0
DXF ScaleX= 1
DXF ScaleY= 10

--- Stream0349.p01 (plan) ---

Plan Title=Multiple Run
Short Identifier=Multiple
Geom File=g01
Flow File=f01
Subcritical Flow
K Sum by GR= 0
Std Step Tol= 0.01
Critical Tol= 0.01
Num of Std Step Trials= 20
Max Error Tol= 0.3
Flow Tol Ratio= 0.001
Split Flow NTrial= 30
Split Flow Tol= 0.02
Split Flow Ratio= 0.02
Log Output Level= 0
Friction Slope Method= 1
Unsteady Friction Slope Method= 2
Unsteady Bridges Friction Slope Method= 1
Parabolic Critical Depth
Global Vel Dist=  1 , 1 , 1
Global Log Level= 0
CheckData=True
Encroach Param= -1, 0, 0, 0
BEGIN DESCRIPTION:
Multiple Run
END DESCRIPTION:

--- Stream0349.f01 (steady flow) ---

Flow Title=Multiple
Number of Profiles=7
Profile Names=10-year,25-year,50-year,1pct_min,100-year,1pct_plu,500-year
River Rch & RM= Stream0349,Reach-1,2020
     350     539     701     443     883    1762    1386
Boundary for River Rch & Prof#=Stream0349,Reach-1,1
Up Type=0
Dn Type=3
Dn Slope=0.005
Boundary for River Rch & Prof#=Stream0349,Reach-1,2
Up Type=0
Dn Type=3
Dn Slope=0.005
Boundary for River Rch & Prof#=Stream0349,Reach-1,3
Up Type=0
Dn Type=3
Dn Slope=0.005
Boundary for River Rch & Prof#=Stream0349,Reach-1,4
Up Type=0
Dn Type=3
Dn Slope=0.005
Boundary for River Rch & Prof#=Stream0349,Reach-1,5
Up Type=0
Dn Type=3
Dn Slope=0.005
Boundary for River Rch & Prof#=Stream0349,Reach-1,6
Up Type=0
Dn Type=3
Dn Slope=0.005
Boundary for River Rch & Prof#=Stream0349,Reach-1,7
Up Type=0
Dn Type=3
Dn Slope=0.005

--- Stream0349.g01 (geometry) ---

Geom Title=Existing Conditions

River Reach=Stream0349,Reach-1
Reach XY= 30
      2503175.00     13811475.00      2503176.60     13811430.88
      2503188.37     13811411.26      2503222.93     13811380.89
      2503271.93     13811366.72      2503277.07     13811230.45
      2503314.62     13811185.80      2503338.20     13811188.39
      2503422.71     13811269.90      2503468.95     13811273.41
      2503572.58     13811180.54      2503677.42     13811169.46
      2503765.35     13811085.81      2503827.54     13811069.25
      2503869.30     13811027.54      2503879.47     13810976.68
      2503917.44     13810925.00      2503880.67     13810877.28
      2503874.90     13810845.16      2503880.66     13810822.71
      2503916.68     13810778.23      2503882.82     13810725.08
      2503919.37     13810677.30      2503925.32     13810650.04
      2503919.60     13810622.83      2503876.24     13810564.50
      2503876.05     13810385.43      2503888.37     13810361.68
      2504018.03     13810225.00      2503925.00     13810125.00

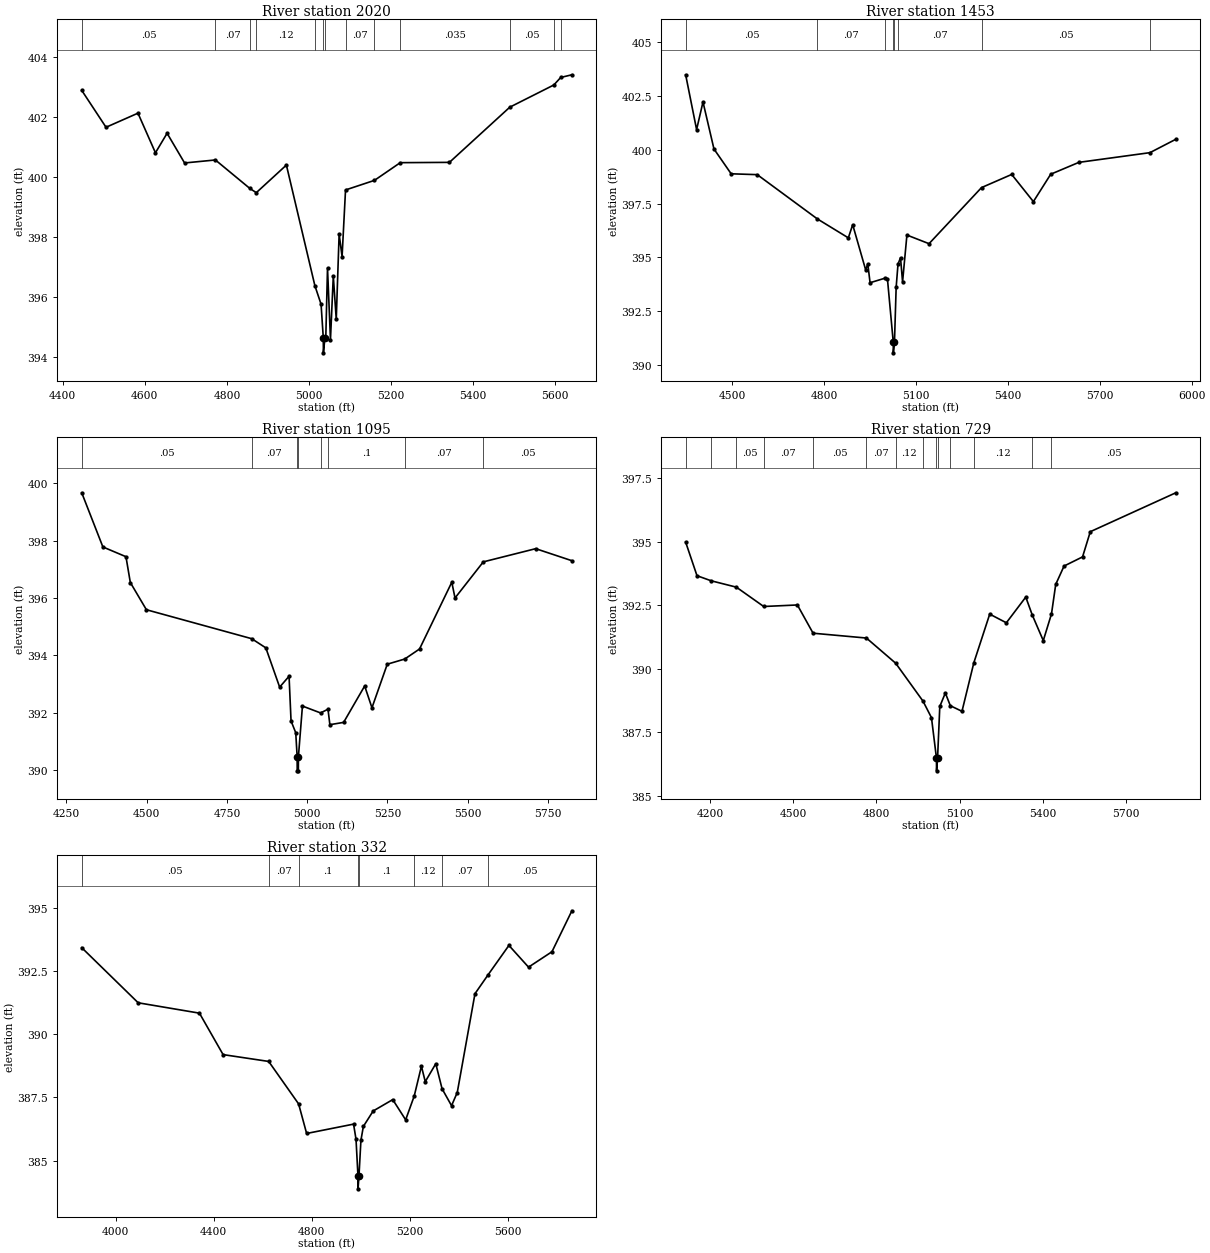
Type RM Length L Ch R = 1,2020,567,567,567
BEGIN DESCRIPTION:
XS6533
END DESCRIPTION:
XS GIS Cut Line= 3
      2503588.05     13811795.78      2503190.05     13811353.96
      2502772.48     13811784.47
#Sta/Elev= 30
  4446.2  402.89  4505.4  401.66  4583.2  402.13  4625.8  400.81  4654.2  401.46
  4696.8  400.47  4771.9  400.57  4855.9  399.62  4871.6  399.48  4944.9  400.40
  5014.3  396.38  5029.4  395.76  5034.8  394.64  5035.1  394.14  5038.8  394.64
  5040.9  394.64  5045.1  396.97  5052.3  394.58  5059.2  396.70  5066.4  395.26
  5073.4  398.10  5080.6  397.35  5089.0  399.57  5159.5  399.89  5222.4  400.48
  5342.2  400.49  5489.3  402.33  5596.6  403.07  5613.3  403.32  5640.6  403.41
#Mann=13,-1,0
  4446.2    0.05       0  4771.9    0.07       0  4855.9    0.05       0
  4871.6    0.12       0  5014.3    0.05       0  5034.8    0.05       0
  5038.8    0.05       0  5089.0    0.07       0  5159.5    0.05       0
  5222.4   0.035       0  5489.3    0.05       0  5596.6    0.07       0
  5613.3    0.05       0
Bank Sta=5034.8,5038.8
Exp/Cntr=0.3,0.1

Type RM Length L Ch R = 1,1453,358,358,358
BEGIN DESCRIPTION:
XS6532
END DESCRIPTION:
XS GIS Cut Line= 4
      2503995.98     13811674.19      2503475.17     13811101.30
      2503267.53     13811091.57      2502843.83     13811541.17
#Sta/Elev= 30
  4348.4  403.47  4384.1  400.93  4405.0  402.21  4440.8  400.03  4496.9  398.88
  4582.1  398.84  4778.1  396.79  4879.4  395.91  4893.6  396.52  4936.1  394.42
  4942.9  394.71  4950.3  393.83  4998.8  394.04  5007.1  394.00  5026.0  391.08
  5026.3  390.58  5030.0  391.08  5035.5  393.62  5041.5  394.69  5049.7  394.99
  5056.4  393.87  5070.6  396.04  5142.8  395.64  5314.1  398.24  5412.6  398.85
  5483.4  397.59  5540.0  398.86  5631.9  399.41  5863.9  399.86  5948.3  400.48
#Mann=8,-1,0
  4348.4    0.05       0  4778.1    0.07       0  4998.8    0.12       0
  5026.0    0.05       0  5030.0    0.12       0  5041.5    0.07       0
  5314.1    0.05       0  5863.9   0.035       0
Bank Sta=5026,5030
Exp/Cntr=0.3,0.1

Type RM Length L Ch R = 1,1095,366,366,366
BEGIN DESCRIPTION:
XS6531
END DESCRIPTION:
XS GIS Cut Line= 3
      2504425.67     13811457.19      2503770.31     13810971.09
      2503062.80     13811044.88
#Sta/Elev= 30
  4297.5  399.67  4363.4  397.78  4435.3  397.44  4448.9  396.54  4499.0  395.59
  4827.1  394.58  4871.1  394.26  4914.2  392.89  4943.5  393.27  4949.7  391.71
  4964.3  391.30  4968.7  390.47  4968.9  389.97  4972.4  389.97  4972.7  390.47
  4985.2  392.23  5041.7  391.99  5064.8  392.12  5070.7  391.58  5113.5  391.66
  5179.1  392.93  5201.8  392.17  5249.5  393.69  5303.9  393.87  5350.0  394.22
  5450.6  396.55  5460.6  396.00  5548.8  397.26  5712.0  397.72  5824.8  397.30
#Mann=8,-1,0
  4297.5    0.05       0  4827.1    0.07       0  4968.7    0.05       0
  4972.7    0.07       0  5041.7    0.12       0  5064.8     0.1       0
  5303.9    0.07       0  5548.8    0.05       0
Bank Sta=4968.7,4972.7
Exp/Cntr=0.3,0.1

Type RM Length L Ch R = 1,729,397,397,397
BEGIN DESCRIPTION:
XS6530
END DESCRIPTION:
XS GIS Cut Line= 4
      2504516.85     13811270.58      2504065.45     13810728.04
      2503509.90     13810732.38      2503059.28     13810962.02
#Sta/Elev= 30
  4112.6  394.98  4153.5  393.66  4204.7  393.46  4295.4  393.21  4394.0  392.45
  4515.4  392.51  4572.0  391.40  4764.3  391.21  4869.8  390.22  4968.3  388.73
  4998.8  388.08  5016.8  386.49  5017.1  385.99  5020.8  386.49  5028.8  388.52
  5048.8  389.05  5066.8  388.55  5108.8  388.33  5151.6  390.24  5208.8  392.15
  5268.8  391.81  5338.8  392.82  5362.4  392.11  5401.9  391.11  5431.5  392.16
  5446.8  393.32  5476.8  394.04  5543.5  394.40  5571.4  395.39  5879.7  396.92
#Mann=14,-1,0
  4112.6    0.05       0  4204.7    0.07       0  4295.4    0.05       0
  4394.0    0.07       0  4572.0    0.05       0  4764.3    0.07       0
  4869.8    0.12       0  4968.3    0.07       0  5016.8    0.05       0
  5020.8    0.07       0  5066.8     0.1       0  5151.6    0.12       0
  5362.4    0.07       0  5431.5    0.05       0
Bank Sta=5016.8,5020.8
Exp/Cntr=0.3,0.1

Type RM Length L Ch R = 1,332,0,0,0
BEGIN DESCRIPTION:
XS6529
END DESCRIPTION:
XS GIS Cut Line= 4
      2504529.87     13811179.44      2504095.83     13810359.11
      2503800.69     13810367.80      2503132.31     13810762.75
#Sta/Elev= 30
  3861.4  393.42  4091.7  391.24  4341.6  390.83  4438.1  389.19  4624.1  388.92
  4746.2  387.24  4778.9  386.07  4970.4  386.44  4980.4  385.84  4988.4  384.38
  4988.6  383.88  4992.4  384.38  5000.4  385.80  5010.4  386.35  5050.4  386.96
  5130.2  387.41  5182.9  386.61  5217.8  387.55  5247.2  388.73  5262.9  388.12
  5305.8  388.83  5331.4  387.84  5370.1  387.17  5393.4  387.69  5465.7  391.60
  5519.4  392.35  5604.2  393.51  5684.2  392.65  5779.8  393.26  5861.1  394.88
#Mann=8,-1,0
  3861.4    0.05       0  4624.1    0.07       0  4746.2     0.1       0
  4988.4    0.05       0  4992.4     0.1       0  5217.8    0.12       0
  5331.4    0.07       0  5519.4    0.05       0
Bank Sta=4988.4,4992.4
Exp/Cntr=0.3,0.1

Chan Stop Cuts=-1