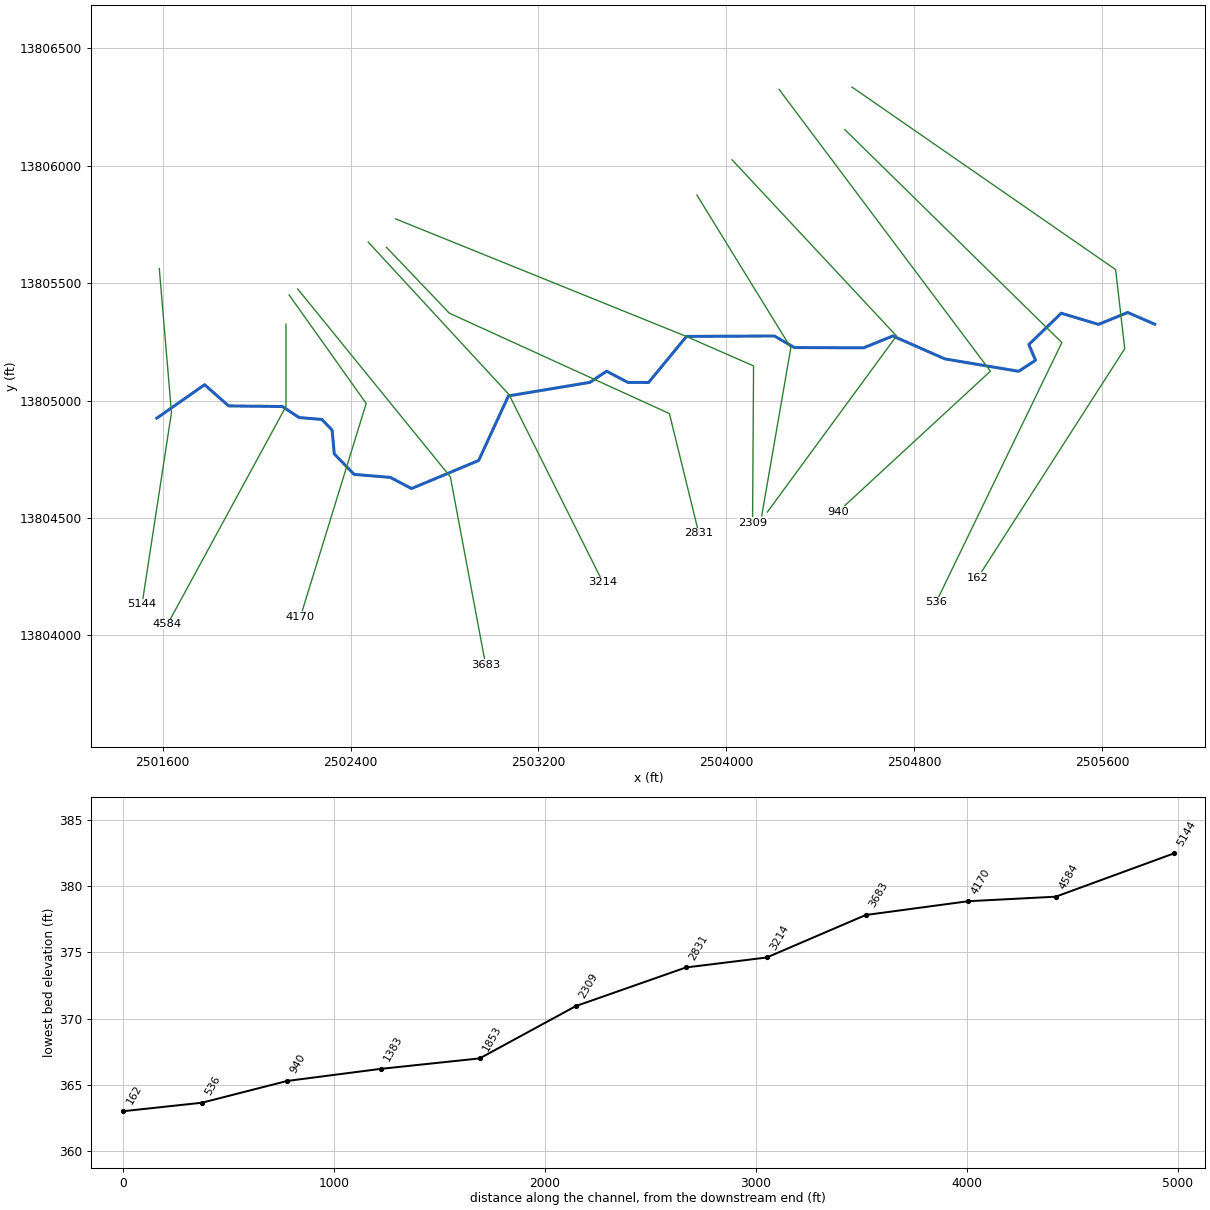
--- Stream0350.prj (project) ---

Proj Title=Stream0350 Base Level Engineering
Current Plan=p01
Default Exp/Contr=0.3,0.1
English Units
Geom File=g01
Flow File=f01
Plan File=p01
BEGIN DESCRIPTION:
Stream0350
END DESCRIPTION:

--- Stream0350.p01 (plan) ---

Plan Title=Multiple Run
Short Identifier=Multiple
Geom File=g01
Flow File=f01
Subcritical Flow
K Sum by GR= 0
Std Step Tol= 0.01
Critical Tol= 0.01
Num of Std Step Trials= 20
Max Error Tol= 0.3
Flow Tol Ratio= 0.001
Split Flow NTrial= 30
Split Flow Tol= 0.02
Split Flow Ratio= 0.02
Log Output Level= 0
Friction Slope Method= 1
Unsteady Friction Slope Method= 2
Unsteady Bridges Friction Slope Method= 1
Parabolic Critical Depth
Global Vel Dist=  1 , 1 , 1
Global Log Level= 0
CheckData=True
Encroach Param= -1, 0, 0, 0
BEGIN DESCRIPTION:
Multiple Run
END DESCRIPTION:

--- Stream0350.f01 (steady flow) ---

Flow Title=Multiple
Number of Profiles=7
Profile Names=10-year,25-year,50-year,1pct_min,100-year,1pct_plu,500-year
River Rch & RM= Stream0350,Reach-1,5144
     673    1076    1438     931    1857    3705    3064
River Rch & RM= Stream0350,Reach-1,3683
     882    1430    1928    1257    2508    5005    4205
Boundary for River Rch & Prof#=Stream0350,Reach-1,1
Up Type=0
Dn Type=3
Dn Slope=0.005
Boundary for River Rch & Prof#=Stream0350,Reach-1,2
Up Type=0
Dn Type=3
Dn Slope=0.005
Boundary for River Rch & Prof#=Stream0350,Reach-1,3
Up Type=0
Dn Type=3
Dn Slope=0.005
Boundary for River Rch & Prof#=Stream0350,Reach-1,4
Up Type=0
Dn Type=3
Dn Slope=0.005
Boundary for River Rch & Prof#=Stream0350,Reach-1,5
Up Type=0
Dn Type=3
Dn Slope=0.005
Boundary for River Rch & Prof#=Stream0350,Reach-1,6
Up Type=0
Dn Type=3
Dn Slope=0.005
Boundary for River Rch & Prof#=Stream0350,Reach-1,7
Up Type=0
Dn Type=3
Dn Slope=0.005

--- Stream0350.g01 (geometry) ---

Geom Title=Existing Conditions

River Reach=Stream0350,Reach-1
Reach XY= 30
      2501575.00     13804925.00      2501778.33     13805067.39
      2501880.85     13804977.08      2502109.78     13804974.48
      2502180.98     13804927.36      2502277.71     13804919.60
      2502321.49     13804873.75      2502330.52     13804772.56
      2502415.18     13804685.47      2502569.07     13804672.70
      2502659.61     13804625.09      2502945.48     13804744.62
      2503072.27     13805019.65      2503419.07     13805077.30
      2503490.39     13805124.91      2503580.97     13805077.19
      2503669.12     13805076.96      2503830.67     13805273.02
      2504204.97     13805274.93      2504290.22     13805225.52
      2504585.19     13805224.55      2504709.61     13805274.91
      2504930.94     13805177.27      2505245.31     13805124.54
      2505317.12     13805171.38      2505288.65     13805238.33
      2505426.63     13805371.87      2505585.05     13805324.23
      2505709.62     13805375.02      2505825.00     13805325.00

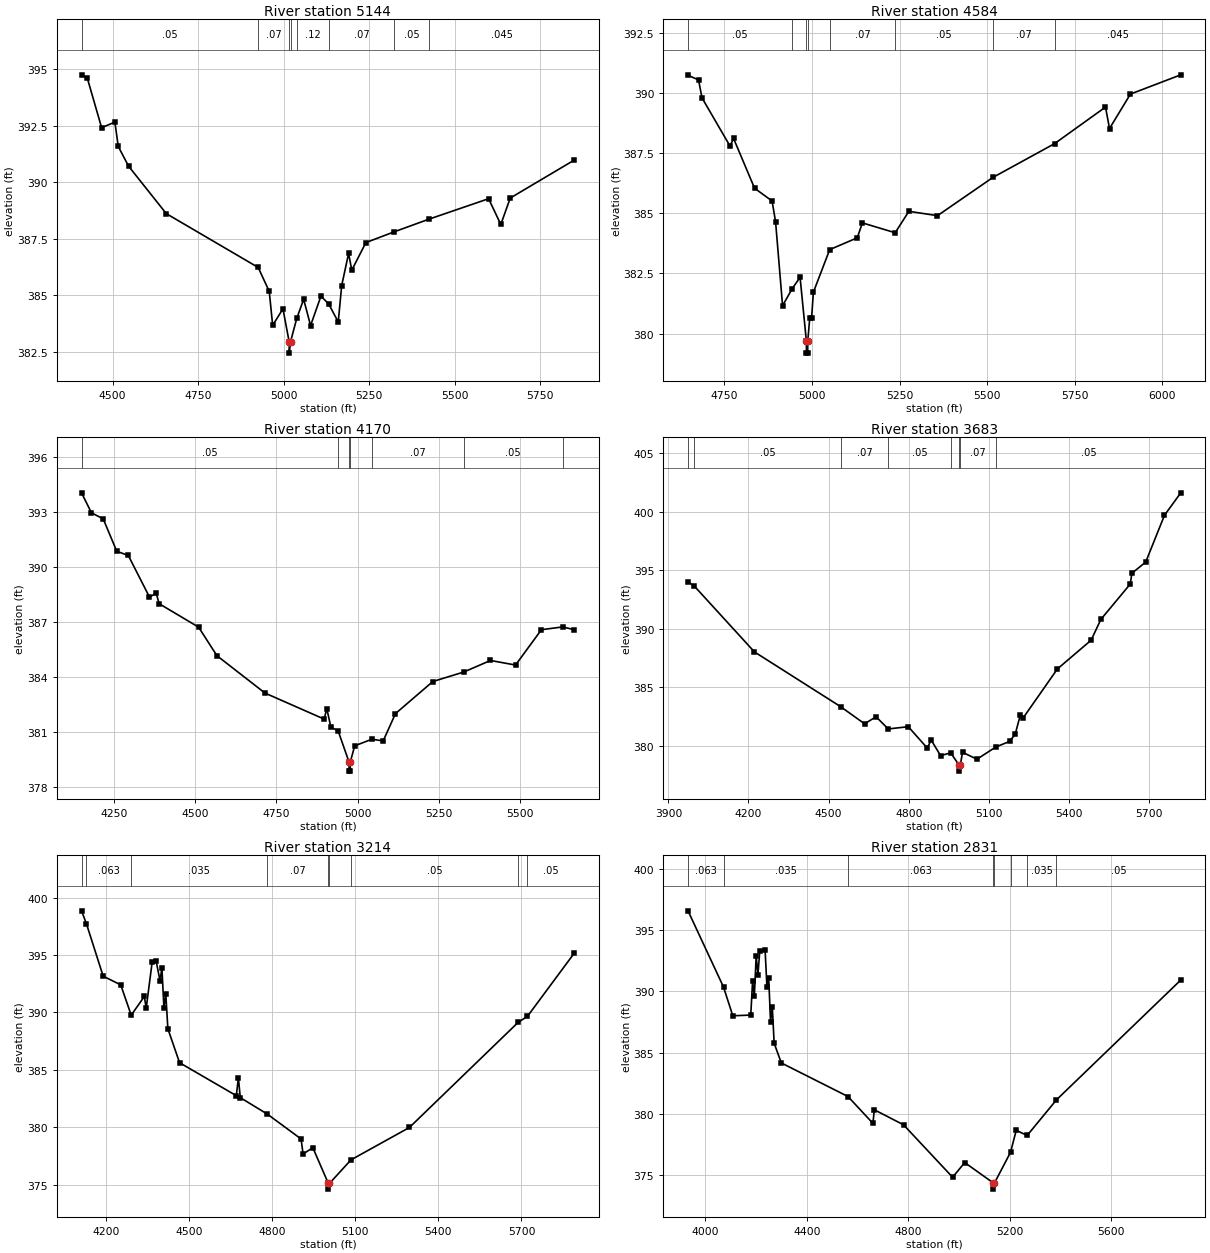
Type RM Length L Ch R = 1,5144,560,560,560
BEGIN DESCRIPTION:
XS6534
END DESCRIPTION:
XS GIS Cut Line= 3
      2501585.35     13805562.04      2501637.18     13804948.75
      2501511.93     13804132.48
#Sta/Elev= 30
  4409.1  394.76  4426.2  394.60  4467.8  392.42  4506.5  392.67  4516.5  391.59
  4546.6  390.72  4657.0  388.62  4925.7  386.24  4958.1  385.18  4968.1  383.68
  4998.2  384.41  5016.3  382.95  5016.6  382.45  5020.3  382.95  5038.6  383.99
  5058.7  384.83  5079.0  383.67  5109.3  384.97  5131.7  384.63  5159.9  383.83
  5170.0  385.44  5190.2  386.86  5199.5  386.12  5240.8  387.34  5324.3  387.82
  5424.2  388.37  5599.7  389.28  5635.4  388.14  5663.0  389.31  5850.4  390.99
#Mann=8,-1,0
  4409.1    0.05       0  4925.7    0.07       0  5016.3    0.05       0
  5020.3    0.07       0  5038.6    0.12       0  5131.7    0.07       0
  5324.3    0.05       0  5424.2   0.045       0
Bank Sta=5016.3,5020.3
Exp/Cntr=0.3,0.1

Type RM Length L Ch R = 1,4584,414,414,414
BEGIN DESCRIPTION:
Stream0350 9.0
END DESCRIPTION:
XS GIS Cut Line= 3
      2502125.00     13805324.96      2502125.00     13804975.00
      2501619.96     13804046.19
#Sta/Elev= 30
  4645.9  390.73  4675.9  390.54  4685.9  389.79  4765.9  387.79  4775.9  388.11
  4835.9  386.04  4885.9  385.51  4895.9  384.65  4915.9  381.16  4943.5  381.87
  4965.9  382.34  4983.9  379.69  4984.1  379.19  4987.6  379.19  4987.9  379.69
  4993.4  380.63  4998.7  380.63  5003.9  381.72  5050.5  383.49  5129.3  383.98
  5143.8  384.60  5237.5  384.19  5276.6  385.08  5358.3  384.90  5516.8  386.49
  5692.5  387.89  5838.1  389.41  5849.6  388.52  5909.3  389.95  6053.1  390.75
#Mann=8,-1,0
  4645.9    0.05       0  4943.5    0.12       0  4983.9    0.05       0
  4987.9    0.12       0  5050.5    0.07       0  5237.5    0.05       0
  5516.8    0.07       0  5692.5   0.045       0
Bank Sta=4983.9,4987.9
Exp/Cntr=0.3,0.1

Type RM Length L Ch R = 1,4170,487,487,487
BEGIN DESCRIPTION:
XS6535
END DESCRIPTION:
XS GIS Cut Line= 3
      2502138.16     13805449.79      2502466.43     13804987.63
      2502186.27     13804078.18
#Sta/Elev= 30
  4149.3  394.04  4179.7  392.95  4216.0  392.62  4257.8  390.85  4293.4  390.62
  4358.6  388.35  4379.5  388.56  4388.2  387.99  4509.9  386.71  4566.5  385.15
  4714.7  383.11  4896.8  381.69  4905.0  382.26  4917.7  381.25  4939.9  381.05
  4973.5  379.35  4973.8  378.85  4977.3  378.85  4977.5  379.35  4991.0  380.23
  5043.8  380.59  5078.8  380.50  5116.7  381.99  5231.7  383.74  5327.3  384.26
  5409.5  384.89  5486.7  384.64  5566.5  386.57  5632.0  386.72  5667.8  386.57
#Mann=7,-1,0
  4149.3    0.05       0  4939.9    0.12       0  4973.5    0.05       0
  4977.5    0.12       0  5043.8    0.07       0  5327.3    0.05       0
  5632.0   0.045       0
Bank Sta=4973.5,4977.5
Exp/Cntr=0.3,0.1

Type RM Length L Ch R = 1,3683,469,469,469
BEGIN DESCRIPTION:
Stream0350 8.0
END DESCRIPTION:
XS GIS Cut Line= 3
      2502174.98     13805475.02      2502825.00     13804675.00
      2502974.99     13803875.04
#Sta/Elev= 30
  3973.6  394.01  3997.2  393.64  4222.2  388.01  4544.6  383.33  4634.5  381.86
  4677.6  382.46  4723.0  381.42  4798.2  381.61  4869.4  379.78  4883.7  380.48
  4918.9  379.14  4957.1  379.37  4988.8  378.31  4989.0  377.81  4992.8  378.31
  5001.2  379.42  5055.3  378.83  5126.3  379.88  5177.4  380.35  5198.6  380.98
  5218.1  382.65  5228.2  382.36  5356.3  386.55  5482.6  389.01  5519.1  390.79
  5629.3  393.82  5635.2  394.74  5686.9  395.69  5757.3  399.70  5818.3  401.62
#Mann=8,-1,0
  3973.6   0.035       0  3997.2    0.05       0  4544.6    0.07       0
  4723.0    0.05       0  4957.1    0.07       0  4988.8    0.05       0
  4992.8    0.07       0  5126.3    0.05       0
Bank Sta=4988.8,4992.8
Exp/Cntr=0.3,0.1

Type RM Length L Ch R = 1,3214,383,383,383
BEGIN DESCRIPTION:
Stream0350 7.0
END DESCRIPTION:
XS GIS Cut Line= 3
      2502474.99     13805675.01      2503075.00     13805025.00
      2503474.98     13804225.03
#Sta/Elev= 30
  4111.7  398.85  4129.5  397.71  4189.7  393.16  4253.2  392.40  4290.9  389.76
  4338.3  391.39  4345.1  390.37  4366.6  394.38  4380.8  394.51  4395.0  392.75
  4401.8  393.88  4409.1  390.38  4415.9  391.59  4423.3  388.58  4465.6  385.62
  4670.5  382.75  4677.9  384.32  4684.7  382.58  4782.1  381.15  4904.2  378.98
  4911.5  377.67  4946.7  378.22  5002.6  375.11  5002.9  374.61  5006.8  375.11
  5084.5  377.16  5295.4  379.98  5689.0  389.16  5721.2  389.65  5890.7  395.17
#Mann=9,-1,0
  4111.7   0.035       0  4129.5   0.063       0  4290.9   0.035       0
  4782.1    0.07       0  5002.6    0.05       0  5006.8    0.07       0
  5084.5    0.05       0  5689.0    0.07       0  5721.2    0.05       0
Bank Sta=5002.6,5006.8
Exp/Cntr=0.3,0.1

Type RM Length L Ch R = 1,2831,522,522,522
BEGIN DESCRIPTION:
Stream0350 6.0
END DESCRIPTION:
XS GIS Cut Line= 4
      2502552.82     13805652.75      2502820.59     13805372.02
      2503757.82     13804944.44      2503883.06     13804434.81
#Sta/Elev= 30
  3932.1  396.58  4072.0  390.36  4108.7  388.01  4179.5  388.07  4186.7  390.84
  4193.6  389.63  4200.9  392.91  4207.8  391.35  4215.0  393.31  4236.1  393.36
  4243.3  390.34  4250.3  391.08  4257.5  387.51  4264.4  388.73  4271.7  385.77
  4300.0  384.16  4562.8  381.42  4661.2  379.23  4666.7  380.34  4781.9  379.11
  4975.4  374.83  5023.2  376.03  5136.2  374.36  5136.5  373.86  5140.4  374.36
  5203.8  376.87  5226.2  378.66  5269.2  378.24  5384.9  381.15  5875.0  390.93
#Mann=8,-1,0
  3932.1   0.063       0  4072.0   0.035       0  4562.8   0.063       0
  5136.2    0.05       0  5140.4   0.063       0  5203.8    0.07       0
  5269.2   0.035       0  5384.9    0.05       0
Bank Sta=5136.2,5140.4
Exp/Cntr=0.3,0.1

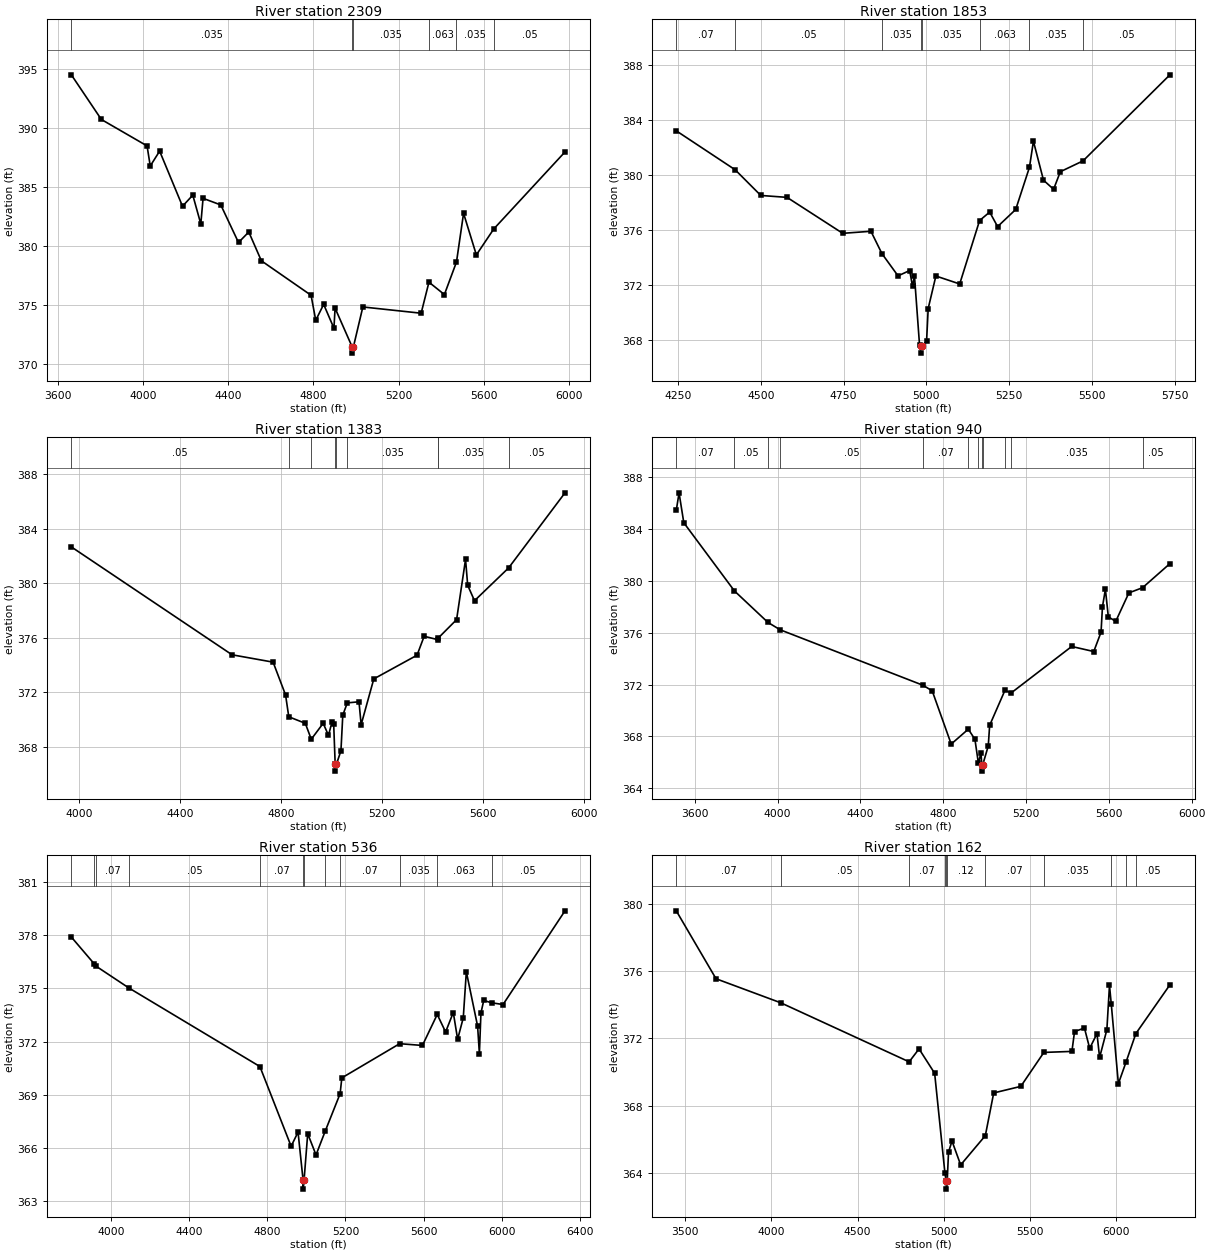
Type RM Length L Ch R = 1,2309,456,456,456
BEGIN DESCRIPTION:
Stream0350 5.0
END DESCRIPTION:
XS GIS Cut Line= 4
      2502591.68     13805773.69      2503825.00     13805275.00
      2504116.29     13805147.43      2504111.98     13804478.97
#Sta/Elev= 30
  3664.2  394.52  3805.0  390.74  4019.6  388.50  4034.5  386.80  4078.6  388.06
  4185.9  383.39  4234.2  384.33  4271.8  381.89  4282.4  384.06  4365.6  383.50
  4448.7  380.32  4497.0  381.21  4556.0  378.77  4789.3  375.85  4811.2  373.73
  4848.4  375.08  4896.6  373.06  4902.0  374.76  4982.8  371.45  4983.1  370.95
  4987.6  371.45  5032.3  374.86  5305.9  374.33  5342.5  376.96  5415.0  375.91
  5471.8  378.67  5505.0  382.79  5565.0  379.27  5646.9  381.47  5981.0  387.99
#Mann=6,-1,0
  3664.2   0.035       0  4982.8   0.035       0  4987.6   0.035       0
  5342.5   0.063       0  5471.8   0.035       0  5646.9    0.05       0
Bank Sta=4982.8,4987.6
Exp/Cntr=0.3,0.1

Type RM Length L Ch R = 1,1853,470,470,470
BEGIN DESCRIPTION:
Stream0350 4.0
END DESCRIPTION:
XS GIS Cut Line= 3
      2503874.98     13805875.03      2504275.00     13805225.00
      2504151.00     13804509.11
#Sta/Elev= 30
  4245.0  383.21  4422.8  380.37  4500.1  378.50  4579.3  378.36  4747.4  375.74
  4832.5  375.89  4865.7  374.26  4914.3  372.64  4949.5  373.03  4958.0  371.88
  4963.9  372.63  4979.3  367.57  4982.7  367.51  4983.1  367.01  4987.6  367.51
  5000.5  367.91  5005.3  370.26  5028.5  372.63  5100.4  372.05  5160.4  376.67
  5190.9  377.29  5214.8  376.23  5269.5  377.48  5310.9  380.55  5322.9  382.45
  5353.3  379.61  5383.8  378.95  5404.1  380.23  5472.7  381.02  5734.8  387.29
#Mann=8,-1,0
  4245.0    0.07       0  4422.8    0.05       0  4865.7   0.035       0
  4982.7   0.035       0  4987.6   0.035       0  5160.4   0.063       0
  5310.9   0.035       0  5472.7    0.05       0
Bank Sta=4982.7,4987.6
Exp/Cntr=0.3,0.1

Type RM Length L Ch R = 1,1383,443,443,443
BEGIN DESCRIPTION:
Stream0350 3.0
END DESCRIPTION:
XS GIS Cut Line= 3
      2504025.02     13806024.97      2504725.00     13805275.00
      2504175.02     13804525.03
#Sta/Elev= 30
  3970.2  382.68  4607.0  374.76  4769.6  374.22  4819.0  371.81  4831.7  370.21
  4897.2  369.73  4920.8  368.56  4968.0  369.73  4989.0  368.85  5003.4  369.85
  5009.6  369.69  5015.6  366.72  5016.0  366.22  5020.5  366.72  5038.4  367.72
  5045.7  370.33  5063.6  371.23  5109.9  371.31  5118.4  369.63  5168.6  372.99
  5339.9  374.73  5368.1  376.12  5422.3  375.87  5423.9  375.99  5496.6  377.34
  5532.1  381.76  5540.6  379.86  5567.6  378.73  5702.8  381.14  5926.1  386.65
#Mann=9,-1,0
  3970.2    0.05       0  4831.7    0.07       0  4920.8    0.12       0
  5015.6    0.05       0  5020.5    0.12       0  5063.6   0.035       0
  5422.3   0.063       0  5423.9   0.035       0  5702.8    0.05       0
Bank Sta=5015.6,5020.5
Exp/Cntr=0.3,0.1

Type RM Length L Ch R = 1,940,404,404,404
BEGIN DESCRIPTION:
Stream0350 2.0
END DESCRIPTION:
XS GIS Cut Line= 3
      2504225.01     13806324.98      2505125.00     13805125.00
      2504474.98     13804524.98
#Sta/Elev= 30
  3510.3  385.45  3523.8  386.81  3546.7  384.50  3791.3  379.23  3953.1  376.80
  4012.0  376.23  4702.6  371.94  4746.7  371.51  4838.4  367.40  4921.0  368.55
  4953.0  367.77  4969.9  365.91  4982.2  366.73  4986.0  365.81  4986.3  365.31
  4990.9  365.81  5017.4  367.25  5024.2  368.85  5098.0  371.55  5128.1  371.35
  5420.5  374.94  5527.1  374.55  5562.3  376.05  5569.1  378.01  5583.3  379.35
  5597.5  377.23  5633.2  376.88  5696.7  379.08  5762.8  379.48  5894.9  381.34
#Mann=12,-1,0
  3510.3    0.07       0  3791.3    0.05       0  3953.1    0.07       0
  4012.0    0.05       0  4702.6    0.07       0  4921.0    0.12       0
  4969.9    0.07       0  4986.0    0.05       0  4990.9    0.07       0
  5098.0    0.12       0  5128.1   0.035       0  5762.8    0.05       0
Bank Sta=4986,4990.9
Exp/Cntr=0.3,0.1

Type RM Length L Ch R = 1,536,374,374,374
BEGIN DESCRIPTION:
Stream0350 1.0
END DESCRIPTION:
XS GIS Cut Line= 3
      2504504.98     13806153.79      2505429.28     13805246.77
      2504893.74     13804141.13
#Sta/Elev= 30
  3798.9  377.90  3917.1  376.37  3927.3  376.24  4092.4  375.03  4762.8  370.59
  4922.4  366.09  4957.8  366.89  4983.6  364.17  4984.0  363.67  4988.5  364.17
  5007.2  366.80  5049.7  365.60  5096.2  366.93  5172.9  369.06  5181.6  369.95
  5477.3  371.88  5593.6  371.78  5669.3  373.53  5712.1  372.54  5751.4  373.64
  5773.6  372.13  5802.4  373.34  5818.1  375.94  5875.7  372.87  5884.8  371.32
  5892.7  373.61  5907.0  374.32  5947.0  374.19  6005.6  374.09  6322.4  379.38
#Mann=12,-1,0
  3798.9    0.07       0  3917.1    0.05       0  3927.3    0.07       0
  4092.4    0.05       0  4762.8    0.07       0  4983.6    0.05       0
  4988.5    0.07       0  5096.2    0.12       0  5172.9    0.07       0
  5477.3   0.035       0  5669.3   0.063       0  5947.0    0.05       0
Bank Sta=4983.6,4988.5
Exp/Cntr=0.3,0.1

Type RM Length L Ch R = 1,162,0,0,0
BEGIN DESCRIPTION:
XS6536
END DESCRIPTION:
XS GIS Cut Line= 4
      2504535.25     13806335.15      2505658.18     13805557.74
      2505697.06     13805220.85      2505070.81     13804244.77
#Sta/Elev= 30
  3447.9  379.58  3678.7  375.54  4054.5  374.11  4799.3  370.60  4856.7  371.37
  4947.3  369.92  5006.7  364.01  5015.2  363.53  5015.6  363.03  5020.3  363.53
  5027.8  365.23  5048.0  365.89  5098.3  364.47  5241.4  366.21  5290.0  368.75
  5447.2  369.14  5581.1  371.16  5743.9  371.22  5759.1  372.40  5816.6  372.61
  5847.0  371.40  5889.3  372.28  5904.5  370.86  5946.7  372.51  5961.9  375.15
  5972.3  374.03  6013.5  369.30  6057.4  370.57  6114.9  372.28  6312.5  375.18
#Mann=11,-1,0
  3447.9    0.07       0  4054.5    0.05       0  4799.3    0.07       0
  5006.7    0.12       0  5015.2    0.05       0  5020.3    0.12       0
  5241.4    0.07       0  5581.1   0.035       0  5972.3   0.063       0
  6057.4    0.07       0  6114.9    0.05       0
Bank Sta=5015.2,5020.3
Exp/Cntr=0.3,0.1

Chan Stop Cuts=-1