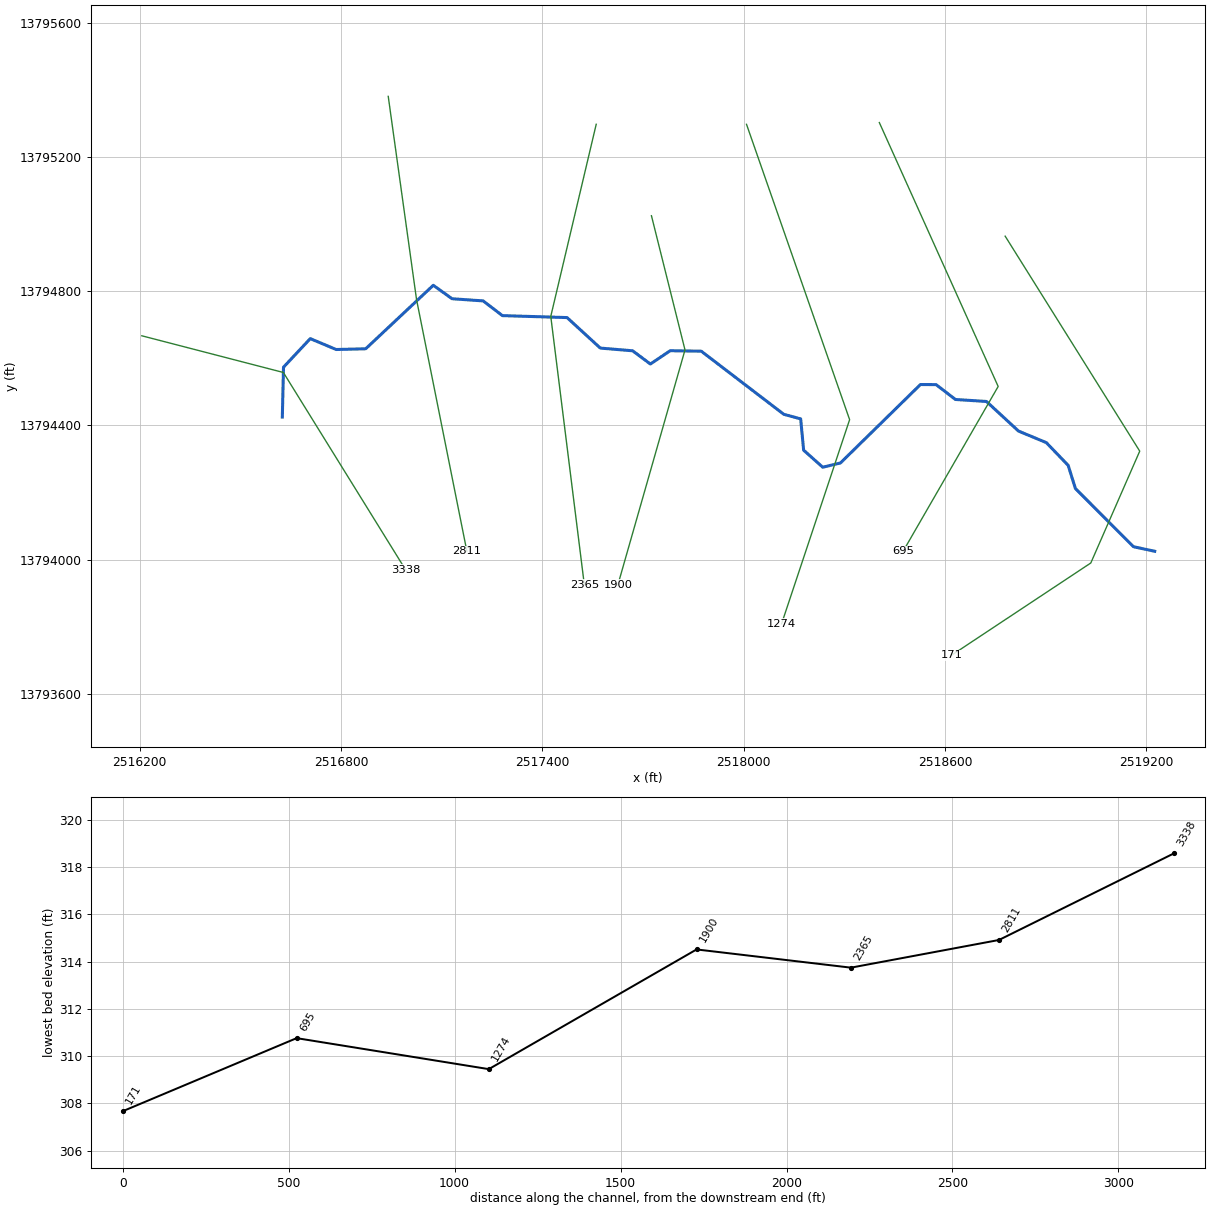
--- Stream0355.prj (project) ---

Proj Title=Stream0355 Base Level Engineering
Current Plan=p01
Default Exp/Contr=0.3,0.1
English Units
Geom File=g01
Flow File=f01
Plan File=p01
BEGIN DESCRIPTION:
Stream0355
END DESCRIPTION:

--- Stream0355.p01 (plan) ---

Plan Title=Multiple Run
Short Identifier=Multiple
Geom File=g01
Flow File=f01
Subcritical Flow
K Sum by GR= 0
Std Step Tol= 0.01
Critical Tol= 0.01
Num of Std Step Trials= 20
Max Error Tol= 0.3
Flow Tol Ratio= 0.001
Split Flow NTrial= 30
Split Flow Tol= 0.02
Split Flow Ratio= 0.02
Log Output Level= 0
Friction Slope Method= 1
Unsteady Friction Slope Method= 2
Unsteady Bridges Friction Slope Method= 1
Parabolic Critical Depth
Global Vel Dist=  1 , 1 , 1
Global Log Level= 0
CheckData=True
Encroach Param= -1, 0, 0, 0
BEGIN DESCRIPTION:
Multiple Run
END DESCRIPTION:

--- Stream0355.f01 (steady flow) ---

Flow Title=Multiple
Number of Profiles=7
Profile Names=10-year,25-year,50-year,1pct_min,100-year,1pct_plu,500-year
River Rch & RM= Stream0355,Reach-1,3338
     520     821    1089     701    1398    2789    2277
River Rch & RM= Stream0355,Reach-1,2811
     925    1510    2044    1339    2672    5332    4522
Boundary for River Rch & Prof#=Stream0355,Reach-1,1
Up Type=0
Dn Type=3
Dn Slope=0.005
Boundary for River Rch & Prof#=Stream0355,Reach-1,2
Up Type=0
Dn Type=3
Dn Slope=0.005
Boundary for River Rch & Prof#=Stream0355,Reach-1,3
Up Type=0
Dn Type=3
Dn Slope=0.005
Boundary for River Rch & Prof#=Stream0355,Reach-1,4
Up Type=0
Dn Type=3
Dn Slope=0.005
Boundary for River Rch & Prof#=Stream0355,Reach-1,5
Up Type=0
Dn Type=3
Dn Slope=0.005
Boundary for River Rch & Prof#=Stream0355,Reach-1,6
Up Type=0
Dn Type=3
Dn Slope=0.005
Boundary for River Rch & Prof#=Stream0355,Reach-1,7
Up Type=0
Dn Type=3
Dn Slope=0.005

--- Stream0355.g01 (geometry) ---

Geom Title=Existing Conditions

River Reach=Stream0355,Reach-1
Reach XY= 30
      2516625.00     13794425.00      2516628.50     13794573.58
      2516708.26     13794658.72      2516785.48     13794626.27
      2516873.50     13794628.46      2517074.90     13794817.69
      2517130.89     13794777.56      2517223.40     13794771.15
      2517280.94     13794727.26      2517473.53     13794721.45
      2517572.58     13794630.54      2517669.10     13794622.44
      2517721.70     13794583.08      2517780.89     13794622.64
      2517873.41     13794621.32      2518119.30     13794433.30
      2518169.74     13794419.52      2518178.56     13794326.29
      2518235.47     13794275.48      2518288.20     13794288.10
      2518526.63     13794521.87      2518573.25     13794521.66
      2518630.97     13794477.38      2518723.50     13794471.38
      2518818.96     13794383.18      2518901.88     13794348.73
      2518966.85     13794281.07      2518988.63     13794211.79
      2519161.73     13794038.47      2519225.00     13794025.00

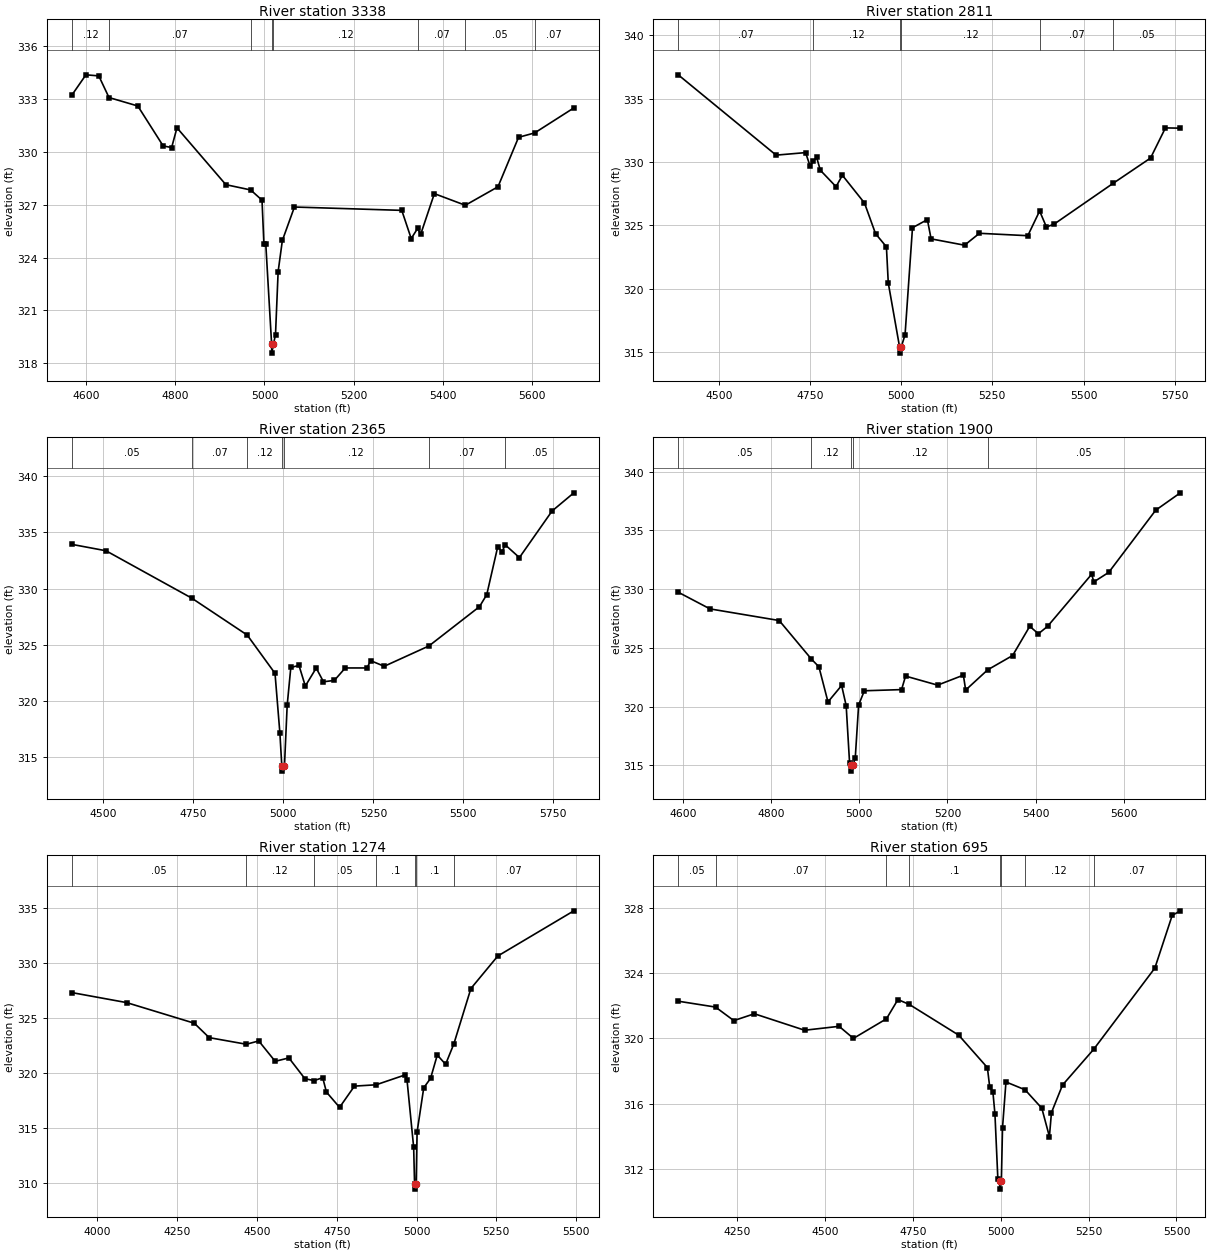
Type RM Length L Ch R = 1,3338,527,527,527
BEGIN DESCRIPTION:
Stream0355 6.0
END DESCRIPTION:
XS GIS Cut Line= 3
      2516206.25     13794667.19      2516628.13     13794557.81
      2516992.48     13793969.65
#Sta/Elev= 30
  4567.2  333.22  4599.0  334.38  4627.9  334.32  4650.8  333.09  4715.5  332.61
  4772.5  330.34  4791.5  330.25  4803.5  331.37  4913.3  328.14  4969.0  327.84
  4994.5  327.26  4998.8  324.75  5003.0  324.75  5016.1  319.07  5016.3  318.57
  5020.1  319.07  5024.8  319.62  5030.7  323.20  5040.2  324.97  5067.3  326.87
  5308.4  326.68  5329.6  325.08  5343.9  325.65  5350.9  325.32  5381.6  327.63
  5451.1  326.97  5524.5  328.02  5570.7  330.83  5606.9  331.08  5694.9  332.50
#Mann=8,-1,0
  4567.2    0.12       0  4650.8    0.07       0  4969.0    0.12       0
  5016.1    0.05       0  5020.1    0.12       0  5343.9    0.07       0
  5451.1    0.05       0  5606.9    0.07       0
Bank Sta=5016.1,5020.1
Exp/Cntr=0.3,0.1

Type RM Length L Ch R = 1,2811,446,446,446
BEGIN DESCRIPTION:
Stream0355 5.0
END DESCRIPTION:
XS GIS Cut Line= 3
      2516940.62     13795380.73      2517025.00     13794775.00
      2517174.99     13794025.03
#Sta/Elev= 30
  4388.9  336.88  4657.2  330.54  4738.0  330.74  4750.0  329.71  4759.2  330.04
  4768.3  330.36  4778.4  329.35  4821.5  328.05  4838.9  328.95  4899.5  326.76
  4929.8  324.34  4959.6  323.30  4964.7  320.45  4995.6  315.41  4995.9  314.91
  5000.4  315.41  5010.7  316.36  5031.1  324.81  5071.9  325.45  5082.1  323.93
  5173.8  323.43  5214.6  324.37  5347.2  324.18  5379.6  326.13  5398.2  324.87
  5418.6  325.08  5580.9  328.31  5683.7  330.31  5724.5  332.69  5765.3  332.67
#Mann=6,-1,0
  4388.9    0.07       0  4759.2    0.12       0  4995.6    0.05       0
  5000.4    0.12       0  5379.6    0.07       0  5580.9    0.05       0
Bank Sta=4995.6,5000.4
Exp/Cntr=0.3,0.1

Type RM Length L Ch R = 1,2365,465,465,465
BEGIN DESCRIPTION:
Stream0355 4.0
END DESCRIPTION:
XS GIS Cut Line= 3
      2517560.43     13795297.44      2517425.00     13794725.00
      2517525.00     13793924.97
#Sta/Elev= 30
  4412.2  333.94  4507.2  333.37  4744.9  329.16  4899.5  325.86  4976.7  322.45
  4990.2  317.15  4995.5  314.24  4995.8  313.74  5000.3  314.24  5003.0  314.24
  5010.5  319.61  5020.6  322.98  5043.3  323.15  5060.9  321.32  5091.1  322.92
  5111.3  321.70  5141.5  321.82  5171.8  322.93  5232.2  322.93  5242.3  323.58
  5280.1  323.08  5404.2  324.89  5544.6  328.39  5564.8  329.46  5595.0  333.69
  5607.6  333.30  5616.0  333.90  5655.5  332.76  5746.2  336.91  5806.7  338.53
#Mann=7,-1,0
  4412.2    0.05       0  4744.9    0.07       0  4899.5    0.12       0
  4995.5    0.05       0  5000.3    0.12       0  5404.2    0.07       0
  5616.0    0.05       0
Bank Sta=4995.5,5000.3
Exp/Cntr=0.3,0.1

Type RM Length L Ch R = 1,1900,626,626,626
BEGIN DESCRIPTION:
Stream0355 3.0
END DESCRIPTION:
XS GIS Cut Line= 3
      2517725.01     13795024.98      2517825.00     13794625.00
      2517625.00     13793925.00
#Sta/Elev= 30
  4588.5  329.74  4660.6  328.32  4817.8  327.33  4891.1  324.04  4908.0  323.39
  4928.6  320.40  4959.6  321.80  4969.9  320.09  4977.6  315.23  4980.3  315.01
  4980.7  314.51  4985.2  315.01  4990.5  315.61  4998.2  320.14  5011.2  321.35
  5095.7  321.45  5104.8  322.60  5177.6  321.83  5236.1  322.68  5241.3  321.41
  5291.2  323.13  5347.9  324.35  5386.9  326.84  5406.4  326.20  5427.2  326.83
  5527.3  331.26  5532.5  330.62  5566.3  331.43  5672.9  336.72  5728.8  338.20
#Mann=5,-1,0
  4588.5    0.05       0  4891.1    0.12       0  4980.3    0.05       0
  4985.2    0.12       0  5291.2    0.05       0
Bank Sta=4980.3,4985.2
Exp/Cntr=0.3,0.1

Type RM Length L Ch R = 1,1274,579,579,579
BEGIN DESCRIPTION:
Stream0355 2.0
END DESCRIPTION:
XS GIS Cut Line= 3
      2518008.33     13795297.41      2518315.63     13794417.19
      2518112.87     13793808.92
#Sta/Elev= 30
  3919.4  327.29  4091.4  326.38  4303.3  324.51  4350.1  323.20  4466.5  322.60
  4505.4  322.90  4556.9  321.05  4599.8  321.36  4650.1  319.47  4679.3  319.30
  4705.8  319.57  4717.5  318.26  4758.7  316.87  4805.3  318.80  4873.1  318.92
  4964.5  319.82  4970.0  319.37  4990.9  313.24  4993.7  309.95  4994.1  309.45
  4998.6  309.95  5001.6  314.63  5022.5  318.65  5043.8  319.50  5064.9  321.62
  5091.0  320.78  5116.9  322.64  5170.3  327.66  5254.6  330.61  5492.9  334.71
#Mann=7,-1,0
  3919.4    0.05       0  4466.5    0.12       0  4679.3    0.05       0
  4873.1     0.1       0  4993.7    0.05       0  4998.6     0.1       0
  5116.9    0.07       0
Bank Sta=4993.7,4998.6
Exp/Cntr=0.3,0.1

Type RM Length L Ch R = 1,695,524,524,524
BEGIN DESCRIPTION:
Stream0355 1.0
END DESCRIPTION:
XS GIS Cut Line= 3
      2518404.18     13795302.58      2518758.33     13794516.15
      2518475.00     13794025.00
#Sta/Elev= 30
  4081.5  322.28  4187.7  321.92  4239.8  321.09  4298.2  321.51  4441.4  320.50
  4539.5  320.74  4580.3  320.00  4674.3  321.20  4707.0  322.38  4739.6  322.08
  4880.0  320.20  4961.7  318.21  4968.4  317.01  4977.4  316.72  4983.2  315.37
  4991.5  311.39  4996.5  311.26  4996.9  310.76  5001.5  311.26  5004.8  314.53
  5014.6  317.33  5069.0  316.85  5116.7  315.72  5138.3  313.98  5144.1  315.45
  5175.6  317.14  5264.3  319.33  5438.5  324.31  5487.9  327.54  5511.0  327.82
#Mann=8,-1,0
  4081.5    0.05       0  4187.7    0.07       0  4674.3    0.05       0
  4739.6     0.1       0  4996.5    0.05       0  5001.5     0.1       0
  5069.0    0.12       0  5264.3    0.07       0
Bank Sta=4996.5,5001.5
Exp/Cntr=0.3,0.1

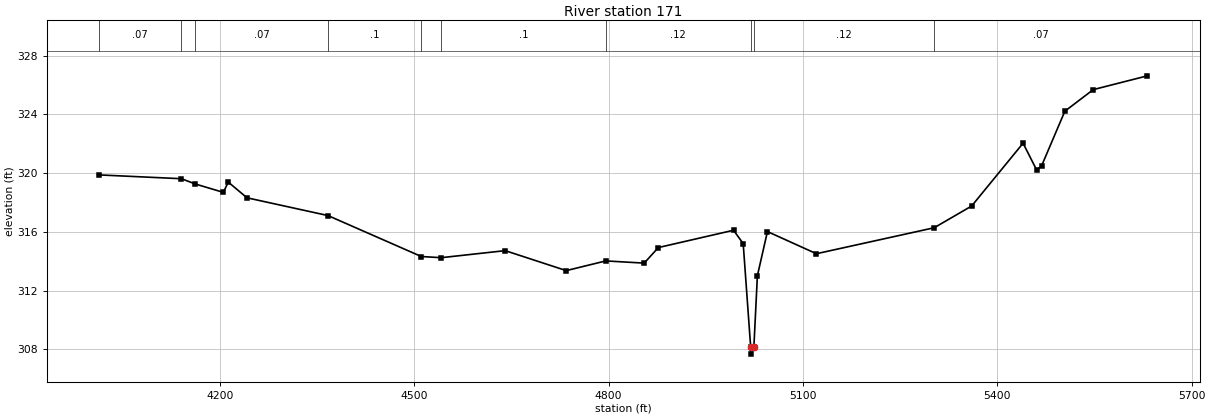
Type RM Length L Ch R = 1,171,0,0,0
BEGIN DESCRIPTION:
XS6540
END DESCRIPTION:
XS GIS Cut Line= 4
      2518779.17     13794964.06      2519180.21     13794323.44
      2519034.38     13793990.10      2518618.83     13793714.80
#Sta/Elev= 30
  4013.6  319.88  4140.7  319.62  4162.2  319.26  4205.4  318.69  4213.0  319.39
  4241.9  318.32  4366.9  317.11  4511.0  314.32  4541.6  314.24  4640.4  314.72
  4734.7  313.36  4795.7  314.02  4855.0  313.87  4876.8  314.93  4992.9  316.11
  5007.8  315.20  5019.3  308.17  5019.7  307.67  5024.3  308.17  5029.7  313.01
  5045.2  316.02  5120.8  314.51  5302.6  316.28  5360.4  317.76  5439.8  322.04
  5460.8  320.21  5468.4  320.50  5504.3  324.22  5548.1  325.69  5631.7  326.63
#Mann=10,-1,0
  4013.6    0.07       0  4140.7    0.05       0  4162.2    0.07       0
  4366.9     0.1       0  4511.0    0.07       0  4541.6     0.1       0
  4795.7    0.12       0  5019.3    0.05       0  5024.3    0.12       0
  5302.6    0.07       0
Bank Sta=5019.3,5024.3
Exp/Cntr=0.3,0.1

Chan Stop Cuts=-1