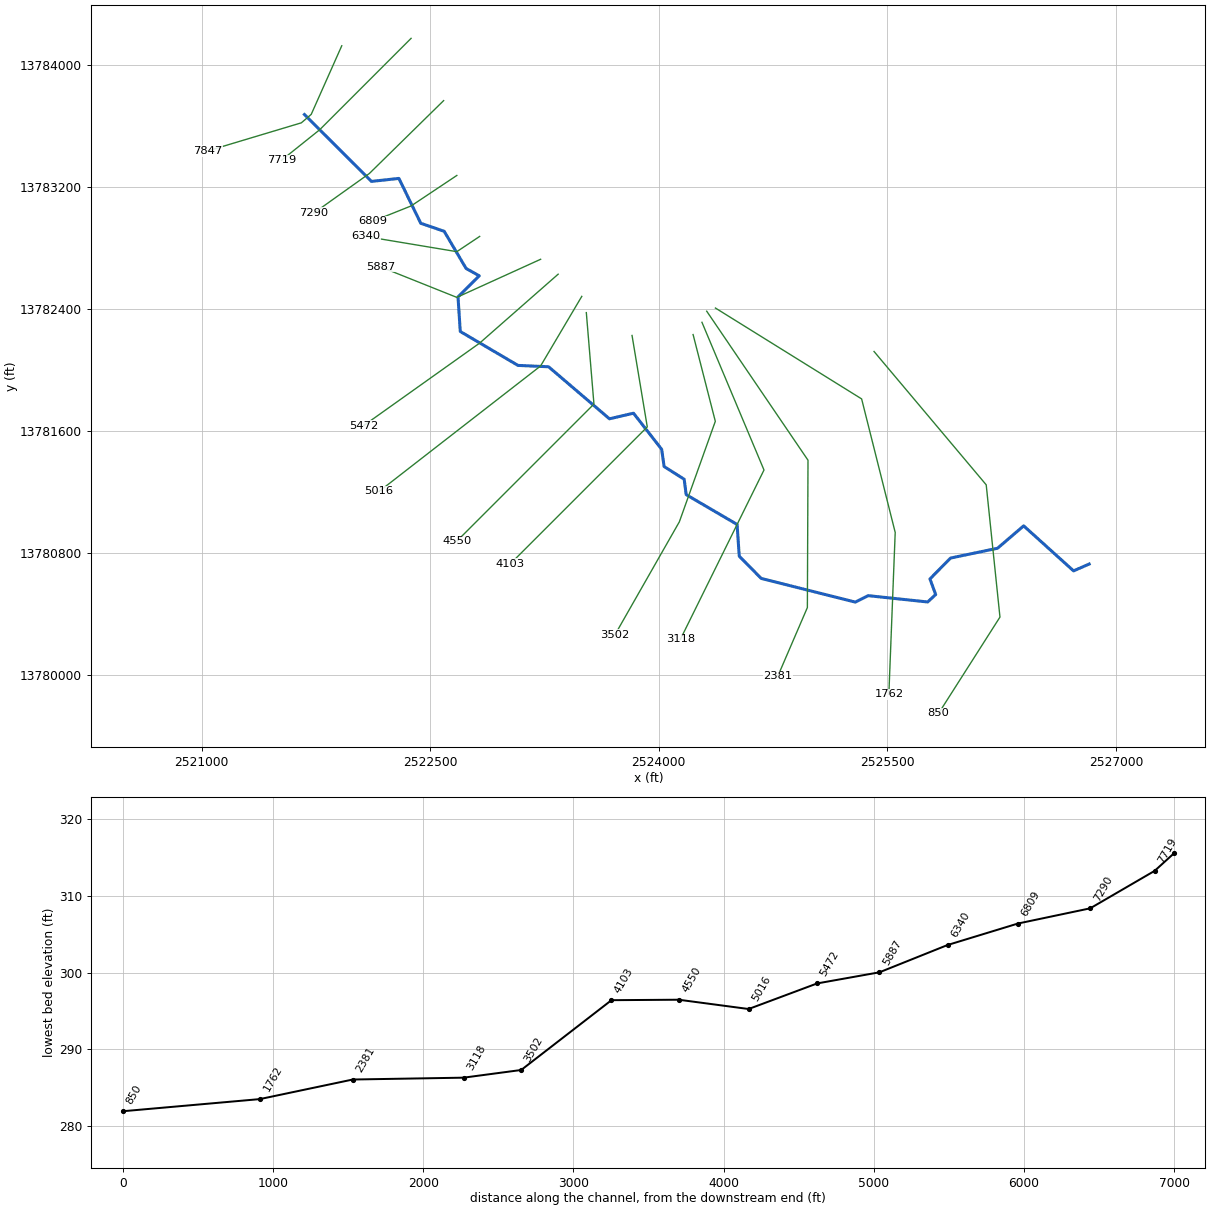
--- Stream0356.prj (project) ---

Proj Title=Stream0356 Base Level Engineering
Current Plan=p01
Default Exp/Contr=0.3,0.1
English Units
Geom File=g01
Flow File=f01
Plan File=p01
BEGIN DESCRIPTION:
Stream0356
END DESCRIPTION:

--- Stream0356.p01 (plan) ---

Plan Title=Multiple Run
Short Identifier=Multiple
Geom File=g01
Flow File=f01
Subcritical Flow
K Sum by GR= 0
Std Step Tol= 0.01
Critical Tol= 0.01
Num of Std Step Trials= 20
Max Error Tol= 0.3
Flow Tol Ratio= 0.001
Split Flow NTrial= 30
Split Flow Tol= 0.02
Split Flow Ratio= 0.02
Log Output Level= 0
Friction Slope Method= 1
Unsteady Friction Slope Method= 2
Unsteady Bridges Friction Slope Method= 1
Parabolic Critical Depth
Global Vel Dist=  1 , 1 , 1
Global Log Level= 0
CheckData=True
Encroach Param= -1, 0, 0, 0
BEGIN DESCRIPTION:
Multiple Run
END DESCRIPTION:

--- Stream0356.f01 (steady flow) ---

Flow Title=Multiple
Number of Profiles=7
Profile Names=10-year,25-year,50-year,1pct_min,100-year,1pct_plu,500-year
River Rch & RM= Stream0356,Reach-1,7847
     640    1022    1364     883    1761    3513    2902
River Rch & RM= Stream0356,Reach-1,3502
     950    1554    2108    1383    2760    5508    4686
River Rch & RM= Stream0356,Reach-1,3118
     956    1561    2114    1385    2763    5512    4672
Boundary for River Rch & Prof#=Stream0356,Reach-1,1
Up Type=0
Dn Type=3
Dn Slope=0.005
Boundary for River Rch & Prof#=Stream0356,Reach-1,2
Up Type=0
Dn Type=3
Dn Slope=0.005
Boundary for River Rch & Prof#=Stream0356,Reach-1,3
Up Type=0
Dn Type=3
Dn Slope=0.005
Boundary for River Rch & Prof#=Stream0356,Reach-1,4
Up Type=0
Dn Type=3
Dn Slope=0.005
Boundary for River Rch & Prof#=Stream0356,Reach-1,5
Up Type=0
Dn Type=3
Dn Slope=0.005
Boundary for River Rch & Prof#=Stream0356,Reach-1,6
Up Type=0
Dn Type=3
Dn Slope=0.005
Boundary for River Rch & Prof#=Stream0356,Reach-1,7
Up Type=0
Dn Type=3
Dn Slope=0.005

--- Stream0356.g01 (geometry) ---

Geom Title=Existing Conditions

River Reach=Stream0356,Reach-1
Reach XY= 30
      2521675.00     13783675.00      2522115.00     13783236.23
      2522295.04     13783255.65      2522438.45     13782961.37
      2522592.13     13782908.70      2522735.71     13782665.03
      2522822.40     13782616.46      2522682.89     13782478.58
      2522697.69     13782251.11      2523076.47     13782028.55
      2523277.45     13782019.53      2523676.64     13781678.14
      2523834.71     13781714.82      2524019.54     13781477.65
      2524035.39     13781364.90      2524167.23     13781281.41
      2524180.25     13781180.45      2524514.53     13780984.82
      2524528.54     13780776.46      2524672.57     13780630.52
      2525290.42     13780475.15      2525374.99     13780517.41
      2525764.90     13780476.04      2525817.75     13780524.67
      2525780.12     13780627.29      2525915.32     13780764.24
      2526223.54     13780828.54      2526395.23     13780975.50
      2526722.66     13780680.06      2526825.00     13780725.00

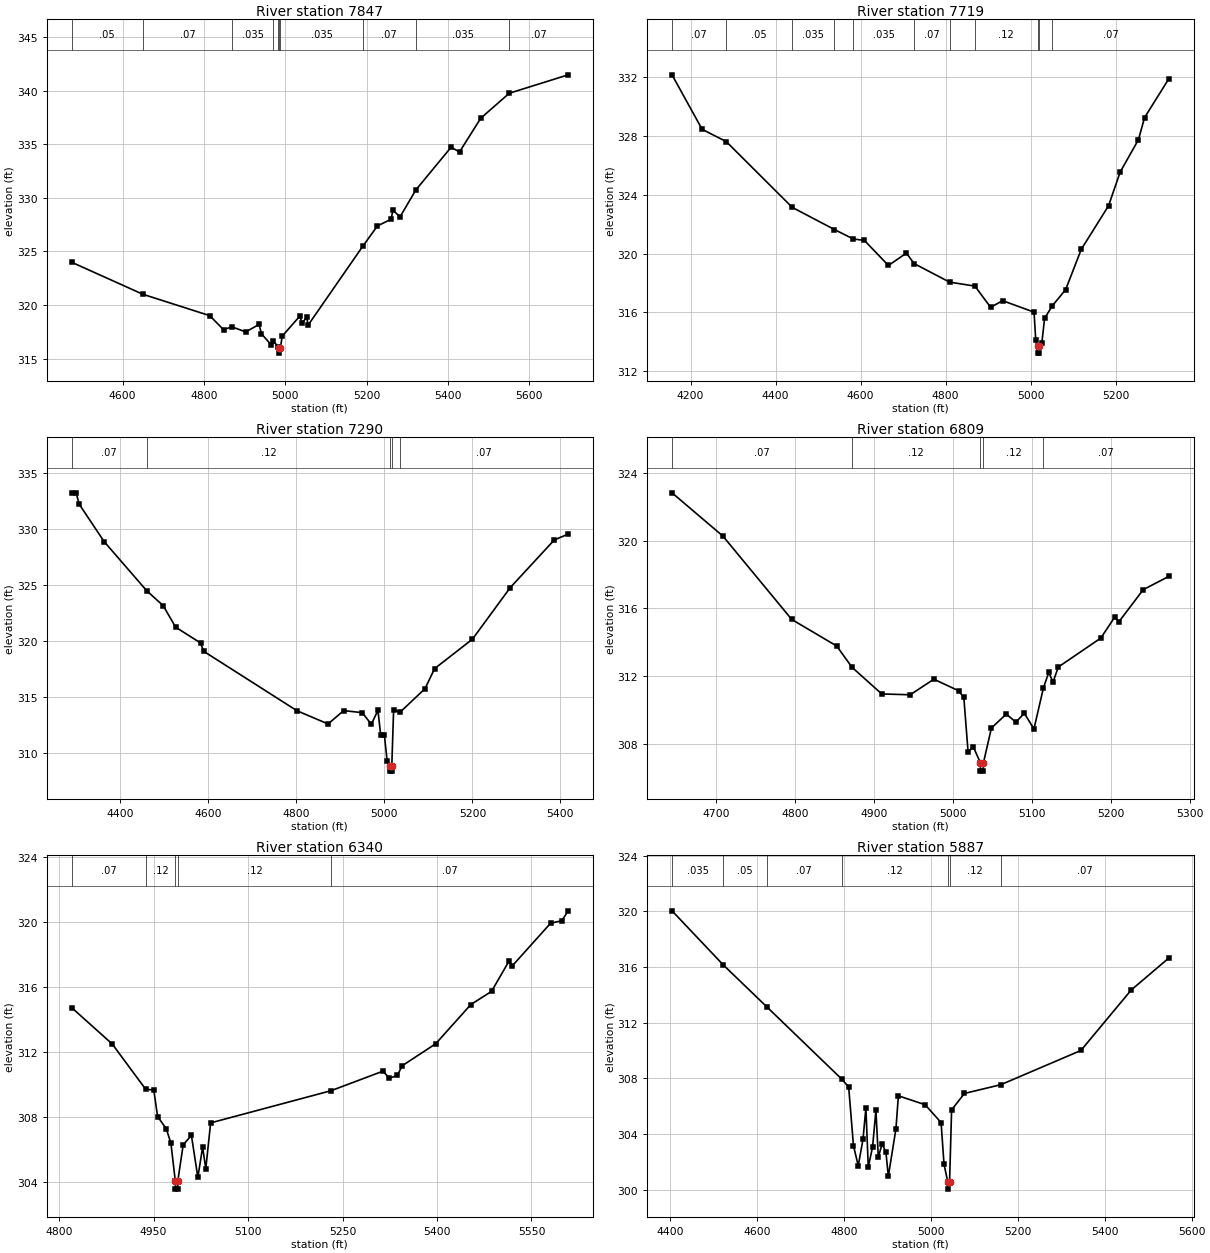
Type RM Length L Ch R = 1,7847,128,128,128
BEGIN DESCRIPTION:
E21659
END DESCRIPTION:
XS GIS Cut Line= 4
      2521919.97     13784126.21      2521719.57     13783676.07
      2521654.82     13783620.58      2521039.14     13783435.87
#Sta/Elev= 30
  4474.5  324.00  4650.2  321.00  4814.2  319.01  4848.4  317.69  4868.4  317.97
  4902.7  317.49  4935.6  318.19  4941.3  317.32  4964.6  316.31  4970.1  316.68
  4981.9  316.10  4983.9  316.01  4984.1  315.51  4987.9  316.01  4992.5  317.10
  5035.3  318.95  5041.9  318.30  5052.5  318.89  5056.0  318.12  5190.1  325.47
  5226.6  327.39  5259.6  328.00  5264.8  328.85  5282.0  328.23  5321.2  330.76
  5407.5  334.73  5428.2  334.29  5480.4  337.44  5550.5  339.77  5695.3  341.49
#Mann=10,-1,0
  4474.5    0.05       0  4650.2    0.07       0  4868.4   0.035       0
  4970.1    0.12       0  4981.9   0.035       0  4983.9   0.035       0
  4987.9   0.035       0  5190.1    0.07       0  5321.2   0.035       0
  5550.5    0.07       0
Bank Sta=4983.9,4987.9
Exp/Cntr=0.3,0.1

Type RM Length L Ch R = 1,7719,429,429,429
BEGIN DESCRIPTION:
Stream0356 12.0
END DESCRIPTION:
XS GIS Cut Line= 3
      2522375.03     13784175.03      2521775.00     13783575.00
      2521525.02     13783375.02
#Sta/Elev= 30
  4156.5  332.13  4227.3  328.43  4284.0  327.60  4439.5  323.13  4538.6  321.63
  4582.8  320.99  4609.1  320.89  4665.7  319.19  4708.1  320.03  4726.0  319.32
  4809.5  318.06  4869.2  317.79  4906.1  316.35  4934.4  316.80  5008.3  316.02
  5012.3  314.15  5016.7  313.74  5016.9  313.24  5020.4  313.24  5020.7  313.74
  5026.7  313.93  5033.1  315.60  5051.5  316.46  5082.7  317.55  5119.5  320.29
  5183.6  323.24  5210.8  325.52  5254.0  327.73  5268.4  329.23  5325.2  331.85
#Mann=11,-1,0
  4156.5    0.07       0  4284.0    0.05       0  4439.5   0.035       0
  4538.6    0.05       0  4582.8   0.035       0  4726.0    0.07       0
  4809.5   0.035       0  4869.2    0.12       0  5016.7    0.05       0
  5020.7    0.12       0  5051.5    0.07       0
Bank Sta=5016.7,5020.7
Exp/Cntr=0.3,0.1

Type RM Length L Ch R = 1,7290,481,481,481
BEGIN DESCRIPTION:
Stream0356 11.0
END DESCRIPTION:
XS GIS Cut Line= 3
      2522588.49     13783766.28      2522101.03     13783287.93
      2521737.76     13783029.10
#Sta/Elev= 30
  4288.7  333.20  4299.1  333.20  4306.3  332.18  4362.8  328.85  4459.7  324.46
  4497.1  323.13  4525.4  321.21  4582.0  319.80  4589.0  319.06  4801.2  313.75
  4871.9  312.57  4907.3  313.76  4949.7  313.58  4970.2  312.54  4985.3  313.78
  4991.4  311.62  5000.0  311.56  5006.2  309.25  5012.8  308.86  5013.0  308.36
  5016.5  308.36  5016.8  308.86  5020.9  313.83  5035.4  313.61  5092.2  315.72
  5114.1  317.51  5200.1  320.14  5286.0  324.74  5386.0  328.99  5417.7  329.52
#Mann=5,-1,0
  4288.7    0.07       0  4459.7    0.12       0  5012.8    0.05       0
  5016.8    0.12       0  5035.4    0.07       0
Bank Sta=5012.8,5016.8
Exp/Cntr=0.3,0.1

Type RM Length L Ch R = 1,6809,469,469,469
BEGIN DESCRIPTION:
Stream0356 10.0
END DESCRIPTION:
XS GIS Cut Line= 3
      2522675.02     13783275.01      2522375.00     13783075.00
      2522125.03     13782975.01
#Sta/Elev= 30
  4643.7  322.82  4708.3  320.26  4795.5  315.34  4852.5  313.77  4872.0  312.51
  4909.6  310.94  4945.7  310.89  4975.7  311.81  5007.0  311.13  5013.7  310.73
  5019.1  307.51  5025.8  307.81  5034.6  306.88  5034.8  306.38  5038.3  306.38
  5038.6  306.88  5048.7  308.93  5067.6  309.75  5079.7  309.27  5090.4  309.80
  5102.6  308.87  5114.7  311.31  5121.4  312.21  5126.8  311.64  5133.5  312.53
  5187.4  314.24  5204.9  315.47  5210.3  315.20  5241.2  317.10  5273.5  317.88
#Mann=5,-1,0
  4643.7    0.07       0  4872.0    0.12       0  5034.6    0.05       0
  5038.6    0.12       0  5114.7    0.07       0
Bank Sta=5034.6,5038.6
Exp/Cntr=0.3,0.1

Type RM Length L Ch R = 1,6340,453,453,453
BEGIN DESCRIPTION:
Stream0356 9.0
END DESCRIPTION:
XS GIS Cut Line= 3
      2522825.02     13782875.01      2522675.00     13782775.00
      2522074.98     13782875.00
#Sta/Elev= 30
  4819.7  314.74  4884.3  312.50  4937.2  309.73  4950.4  309.66  4956.4  308.04
  4970.0  307.30  4977.5  306.41  4984.5  304.08  4984.7  303.58  4988.2  303.58
  4988.5  304.08  4997.0  306.30  5010.1  306.88  5020.3  304.30  5027.9  306.16
  5032.9  304.83  5040.6  307.65  5232.0  309.63  5314.3  310.83  5324.4  310.39
  5337.1  310.57  5344.7  311.16  5397.9  312.51  5453.7  314.92  5486.6  315.73
  5514.5  317.60  5519.6  317.30  5580.4  319.92  5598.1  320.07  5608.3  320.68
#Mann=5,-1,0
  4819.7    0.07       0  4937.2    0.12       0  4984.5    0.05       0
  4988.5    0.12       0  5232.0    0.07       0
Bank Sta=4984.5,4988.5
Exp/Cntr=0.3,0.1

Type RM Length L Ch R = 1,5887,415,415,415
BEGIN DESCRIPTION:
Stream0356 8.0
END DESCRIPTION:
XS GIS Cut Line= 3
      2523225.02     13782725.01      2522675.00     13782475.00
      2522174.99     13782675.01
#Sta/Elev= 30
  4404.5  320.04  4522.4  316.15  4622.1  313.15  4795.3  307.93  4810.9  307.37
  4821.9  303.16  4832.9  301.71  4843.9  303.62  4850.5  305.87  4856.0  301.62
  4865.9  303.07  4873.6  305.70  4879.1  302.31  4887.8  303.30  4896.6  302.68
  4902.1  300.95  4919.7  304.38  4925.2  306.74  4986.7  306.10  5023.5  304.82
  5030.2  301.83  5039.0  300.53  5039.2  300.03  5043.0  300.53  5047.7  305.73
  5077.3  306.91  5161.0  307.54  5345.2  310.00  5461.0  314.35  5547.2  316.64
#Mann=7,-1,0
  4404.5   0.035       0  4522.4    0.05       0  4622.1    0.07       0
  4795.3    0.12       0  5039.0    0.05       0  5043.0    0.12       0
  5161.0    0.07       0
Bank Sta=5039,5043
Exp/Cntr=0.3,0.1

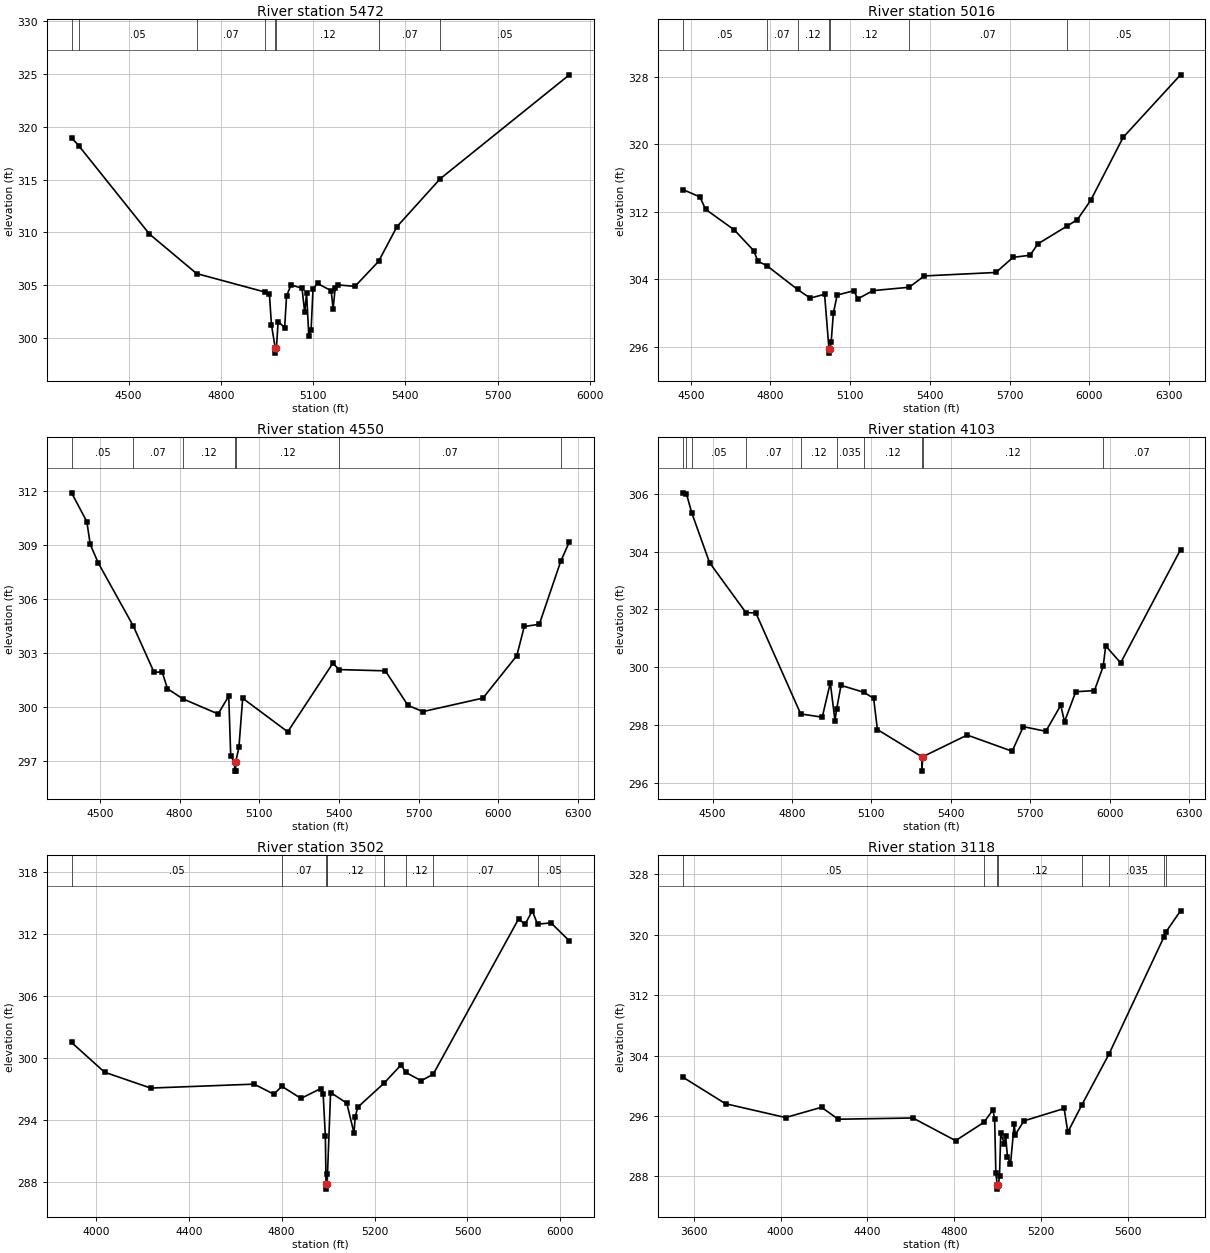
Type RM Length L Ch R = 1,5472,456,456,456
BEGIN DESCRIPTION:
Stream0356 7.0
END DESCRIPTION:
XS GIS Cut Line= 3
      2523340.21     13782627.30      2522825.00     13782175.00
      2522064.60     13781634.15
#Sta/Elev= 30
  4314.4  318.96  4337.3  318.23  4567.7  309.85  4721.0  306.11  4944.8  304.35
  4957.7  304.20  4964.4  301.27  4976.6  299.08  4976.9  298.58  4980.6  299.08
  4986.2  301.57  5007.4  300.99  5013.5  304.00  5028.3  305.04  5063.9  304.72
  5072.5  302.44  5078.7  304.23  5085.9  300.22  5093.4  300.81  5099.6  304.67
  5114.3  305.17  5158.6  304.49  5164.8  302.79  5171.8  304.72  5179.5  305.04
  5236.1  304.90  5312.7  307.26  5372.6  310.55  5513.1  315.08  5933.1  324.92
#Mann=8,-1,0
  4314.4   0.035       0  4337.3    0.05       0  4721.0    0.07       0
  4944.8    0.12       0  4976.6    0.05       0  4980.6    0.12       0
  5312.7    0.07       0  5513.1    0.05       0
Bank Sta=4976.6,4980.6
Exp/Cntr=0.3,0.1

Type RM Length L Ch R = 1,5016,466,466,466
BEGIN DESCRIPTION:
Stream0356 6.0
END DESCRIPTION:
XS GIS Cut Line= 3
      2523495.15     13782481.56      2523225.00     13782025.00
      2522164.77     13781201.29
#Sta/Elev= 30
  4470.0  314.62  4534.5  313.75  4555.9  312.28  4663.5  309.85  4737.2  307.38
  4752.9  306.13  4785.8  305.62  4902.0  302.79  4949.8  301.76  5003.7  302.22
  5020.2  295.75  5020.5  295.25  5024.2  295.75  5028.6  296.59  5036.7  299.97
  5051.2  302.13  5114.5  302.64  5128.1  301.67  5186.0  302.65  5322.1  303.05
  5378.8  304.39  5648.5  304.80  5712.8  306.59  5777.0  306.84  5806.0  308.18
  5916.1  310.29  5955.3  311.07  6005.1  313.34  6127.3  320.80  6343.1  328.20
#Mann=7,-1,0
  4470.0    0.05       0  4785.8    0.07       0  4902.0    0.12       0
  5020.2    0.05       0  5024.2    0.12       0  5322.1    0.07       0
  5916.1    0.05       0
Bank Sta=5020.2,5024.2
Exp/Cntr=0.3,0.1

Type RM Length L Ch R = 1,4550,447,447,447
BEGIN DESCRIPTION:
Stream0356 5.0
END DESCRIPTION:
XS GIS Cut Line= 3
      2523525.00     13782374.97      2523575.00     13781775.00
      2522675.03     13780875.03
#Sta/Elev= 30
  4393.1  311.89  4450.8  310.29  4463.3  309.04  4493.4  308.01  4625.5  304.51
  4704.1  301.93  4734.2  301.97  4754.3  301.03  4812.1  300.47  4945.0  299.63
  4985.1  300.62  4992.6  297.30  5007.3  296.96  5007.5  296.46  5011.0  296.46
  5011.3  296.96  5023.4  297.78  5037.6  300.50  5207.3  298.64  5377.0  302.44
  5401.1  302.09  5575.0  302.02  5659.8  300.11  5716.4  299.76  5942.7  300.51
  6070.0  302.86  6098.2  304.48  6154.8  304.60  6235.6  308.10  6267.9  309.17
#Mann=7,-1,0
  4393.1    0.05       0  4625.5    0.07       0  4812.1    0.12       0
  5007.3    0.05       0  5011.3    0.12       0  5401.1    0.07       0
  6235.6    0.05       0
Bank Sta=5007.3,5011.3
Exp/Cntr=0.3,0.1

Type RM Length L Ch R = 1,4103,601,601,601
BEGIN DESCRIPTION:
Stream0356 4.0
END DESCRIPTION:
XS GIS Cut Line= 3
      2523825.00     13782225.01      2523925.00     13781625.00
      2523024.98     13780724.98
#Sta/Elev= 30
  4387.3  306.04  4401.4  306.00  4421.6  305.34  4488.7  303.62  4626.1  301.89
  4663.6  301.88  4833.1  298.38  4914.5  298.27  4944.9  299.46  4962.6  298.15
  4968.7  298.54  4985.4  299.37  5072.2  299.13  5108.7  298.92  5122.9  297.84
  5290.6  296.90  5290.8  296.40  5294.6  296.90  5462.3  297.65  5632.0  297.09
  5674.4  297.94  5759.3  297.78  5815.8  298.68  5830.0  298.11  5872.4  299.15
  5943.1  299.19  5976.2  300.03  5985.5  300.74  6042.1  300.15  6268.4  304.07
#Mann=10,-1,0
  4387.3    0.05       0  4401.4   0.035       0  4421.6    0.05       0
  4626.1    0.07       0  4833.1    0.12       0  4968.7   0.035       0
  5072.2    0.12       0  5290.6   0.035       0  5294.6    0.12       0
  5976.2    0.07       0
Bank Sta=5290.6,5294.6
Exp/Cntr=0.3,0.1

Type RM Length L Ch R = 1,3502,384,384,384
BEGIN DESCRIPTION:
E20913
END DESCRIPTION:
XS GIS Cut Line= 4
      2524225.70     13782230.98      2524371.53     13781661.56
      2524135.42     13781001.83      2523712.16     13780259.40
#Sta/Elev= 30
  3895.5  301.52  4037.4  298.64  4236.2  297.10  4681.4  297.48  4766.4  296.51
  4800.9  297.27  4883.2  296.10  4968.2  297.05  4978.8  296.49  4988.2  292.44
  4991.1  287.81  4991.4  287.31  4996.1  287.81  4997.4  288.75  5010.7  296.67
  5080.5  295.64  5111.3  292.76  5116.9  294.33  5127.5  295.24  5239.7  297.55
  5314.4  299.35  5333.6  298.63  5400.8  297.81  5452.5  298.44  5820.0  313.48
  5848.0  312.97  5879.1  314.27  5901.6  312.98  5959.8  313.10  6038.6  311.36
#Mann=9,-1,0
  3895.5    0.05       0  4800.9    0.07       0  4991.1    0.05       0
  4996.1    0.07       0  4997.4    0.12       0  5239.7   0.035       0
  5333.6    0.12       0  5452.5    0.07       0  5901.6    0.05       0
Bank Sta=4991.1,4996.1
Exp/Cntr=0.3,0.1

Type RM Length L Ch R = 1,3118,737,737,737
BEGIN DESCRIPTION:
E20912
END DESCRIPTION:
XS GIS Cut Line= 3
      2524283.80     13782311.48      2524690.97     13781342.11
      2524142.35     13780230.98
#Sta/Elev= 30
  3550.1  301.15  3746.9  297.62  4023.5  295.79  4188.7  297.15  4265.4  295.57
  4609.4  295.73  4805.8  292.73  4936.1  295.16  4977.5  296.80  4985.4  295.59
  4990.9  288.43  4997.3  286.81  4997.6  286.31  5002.3  286.81  5007.8  288.10
  5013.4  293.68  5030.3  292.32  5035.8  293.37  5044.4  290.61  5058.3  289.61
  5075.2  294.90  5080.7  293.53  5120.0  295.35  5305.2  296.99  5322.1  293.86
  5387.0  297.49  5510.9  304.16  5764.9  319.74  5773.8  320.38  5840.7  323.17
#Mann=8,-1,0
  3550.1    0.05       0  4936.1    0.12       0  4997.3    0.05       0
  5002.3    0.12       0  5387.0    0.07       0  5510.9   0.035       0
  5764.9    0.07       0  5773.8    0.05       0
Bank Sta=4997.3,5002.3
Exp/Cntr=0.3,0.1

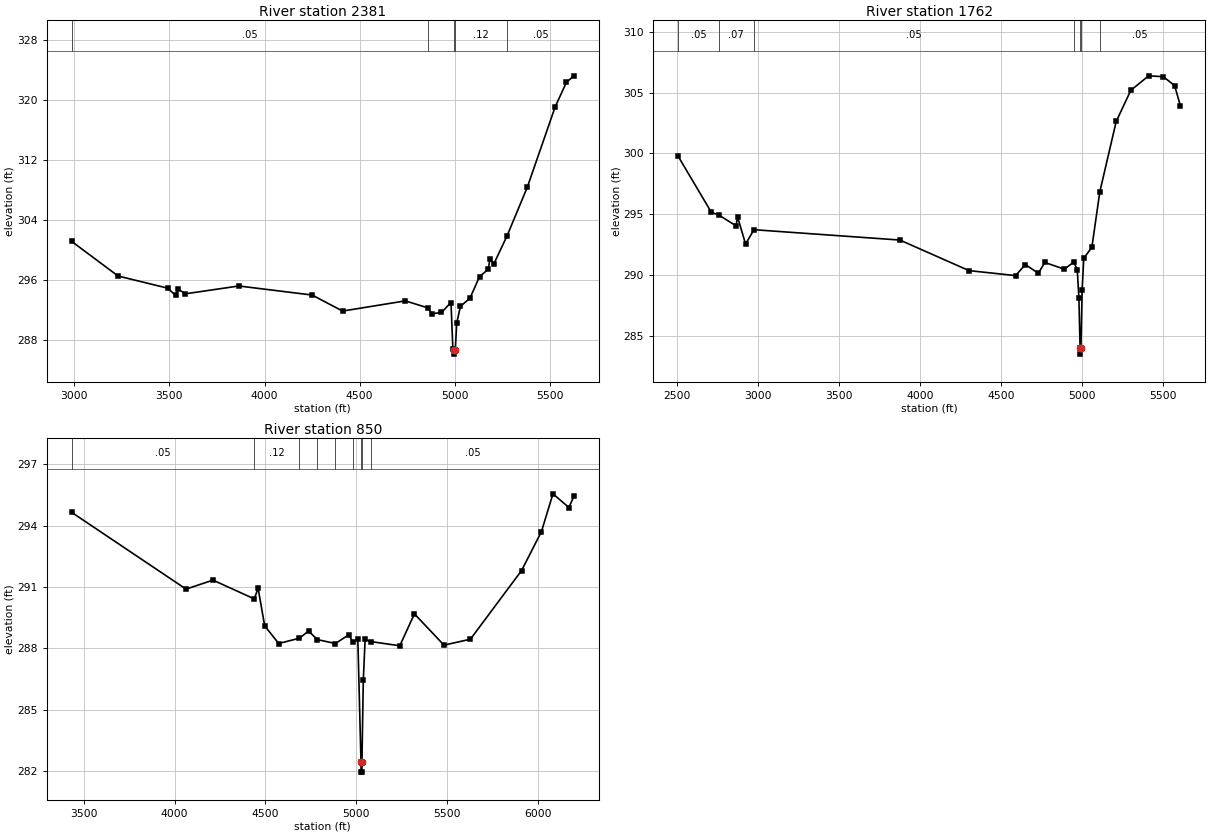
Type RM Length L Ch R = 1,2381,619,619,619
BEGIN DESCRIPTION:
E20911
END DESCRIPTION:
XS GIS Cut Line= 4
      2524315.04     13782384.25      2524979.81     13781406.29
      2524975.69     13780439.33      2524781.71     13779989.01
#Sta/Elev= 30
  2986.6  301.11  3230.1  296.50  3490.5  294.88  3532.5  293.92  3547.4  294.74
  3583.3  294.12  3864.7  295.17  4250.4  293.96  4410.4  291.82  4740.4  293.18
  4858.8  292.25  4880.4  291.46  4930.4  291.64  4980.4  292.96  4990.4  286.80
  4997.9  286.57  4998.3  286.07  5003.0  286.57  5010.4  290.21  5030.4  292.46
  5080.4  293.54  5130.4  296.42  5177.3  297.42  5184.3  298.72  5206.3  298.15
  5274.7  301.83  5381.9  308.37  5528.5  319.11  5587.2  322.35  5626.4  323.23
#Mann=5,-1,0
  2986.6    0.05       0  4858.8    0.12       0  4997.9    0.05       0
  5003.0    0.12       0  5274.7    0.05       0
Bank Sta=4997.9,5003
Exp/Cntr=0.3,0.1

Type RM Length L Ch R = 1,1762,912,912,912
BEGIN DESCRIPTION:
E20910
END DESCRIPTION:
XS GIS Cut Line= 4
      2524372.24     13782405.08      2525331.69     13781808.72
      2525552.08     13780932.39      2525510.42     13779869.91
#Sta/Elev= 30
  2508.9  299.76  2713.1  295.17  2757.7  294.96  2865.4  294.06  2874.9  294.79
  2924.2  292.56  2976.0  293.74  3876.0  292.89  4302.3  290.38  4589.6  289.97
  4649.7  290.88  4729.7  290.16  4769.8  291.05  4889.9  290.50  4948.7  291.08
  4969.9  290.44  4979.9  288.17  4987.4  284.02  4987.7  283.52  4992.5  284.02
  4999.9  288.76  5010.0  291.40  5060.0  292.29  5108.8  296.84  5210.1  302.63
  5300.2  305.19  5410.3  306.38  5500.3  306.31  5570.4  305.58  5605.5  303.94
#Mann=7,-1,0
  2508.9    0.05       0  2757.7    0.07       0  2976.0    0.05       0
  4948.7    0.12       0  4987.4    0.05       0  4992.5    0.12       0
  5108.8    0.05       0
Bank Sta=4987.4,4992.5
Exp/Cntr=0.3,0.1

Type RM Length L Ch R = 1,850,0,0,0
BEGIN DESCRIPTION:
E20909
END DESCRIPTION:
XS GIS Cut Line= 4
      2525413.22     13782119.85      2526149.31     13781244.89
      2526239.58     13780376.83      2525836.82     13779744.92
#Sta/Elev= 30
  3434.0  294.64  4063.5  290.89  4211.8  291.33  4439.8  290.41  4460.2  290.94
  4496.6  289.09  4574.1  288.23  4687.9  288.49  4738.2  288.84  4787.3  288.42
  4885.9  288.23  4959.3  288.65  4984.6  288.28  5009.6  288.45  5027.1  282.44
  5027.5  281.94  5031.9  281.94  5032.3  282.44  5039.8  286.43  5049.8  288.43
  5083.3  288.32  5240.9  288.12  5321.3  289.68  5484.3  288.15  5629.8  288.44
  5911.7  291.80  6020.9  293.70  6084.4  295.55  6172.4  294.88  6199.5  295.43
#Mann=9,-1,0
  3434.0    0.05       0  4439.8    0.12       0  4687.9    0.07       0
  4787.3    0.12       0  4885.9     0.1       0  4984.6    0.07       0
  5027.1    0.05       0  5032.3    0.07       0  5083.3    0.05       0
Bank Sta=5027.1,5032.3
Exp/Cntr=0.3,0.1

Chan Stop Cuts=-1