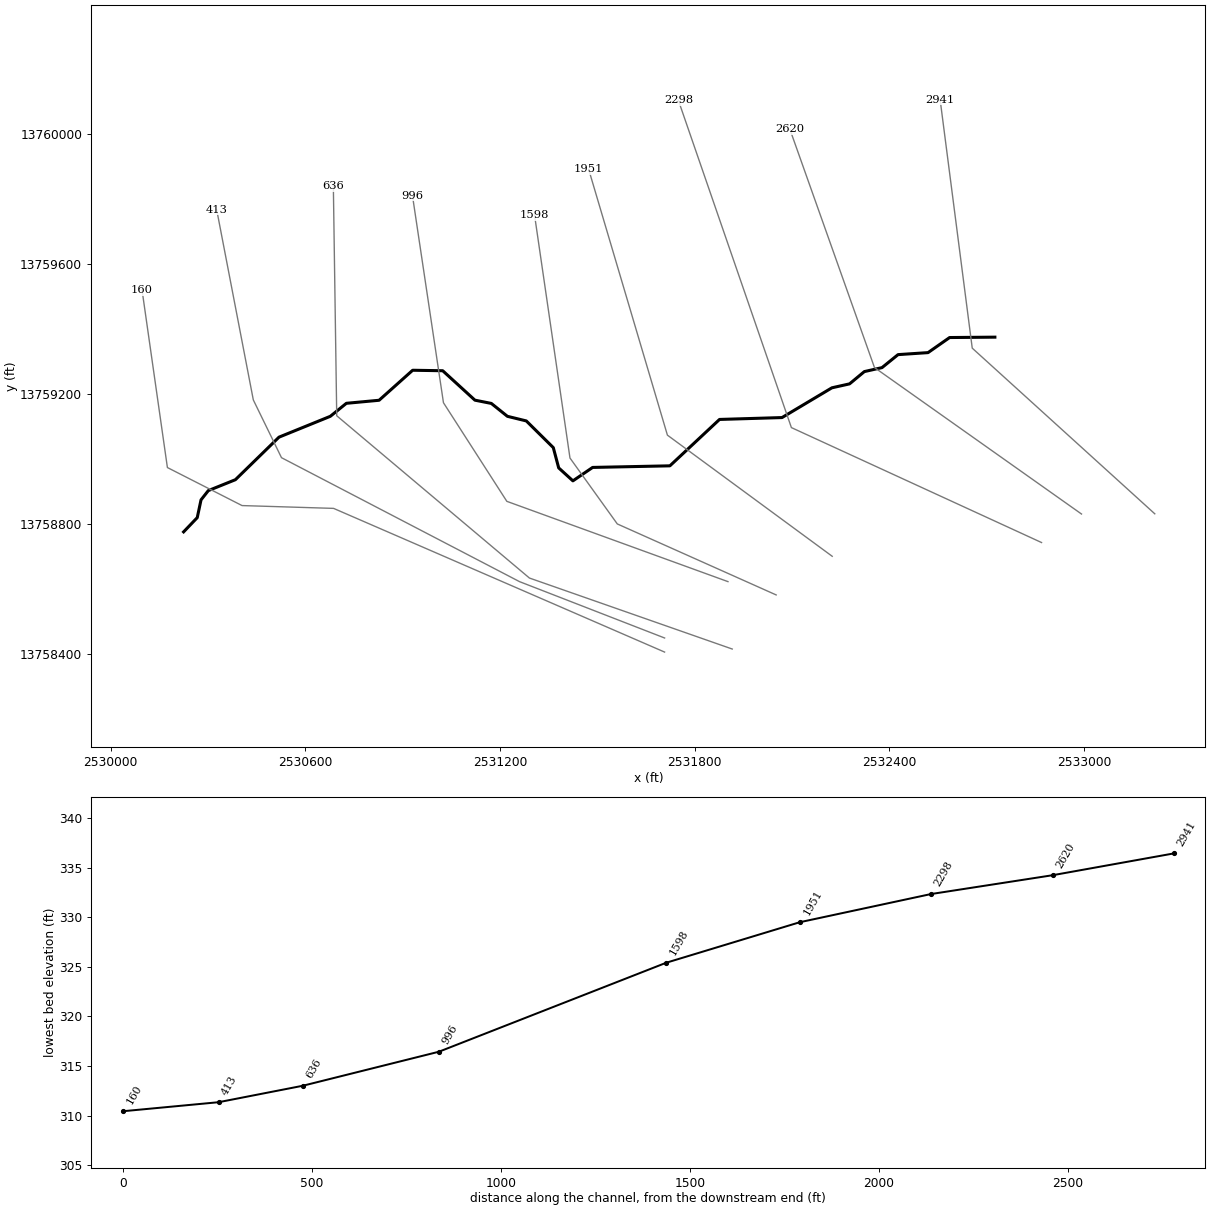
--- Stream0363.prj (project) ---

Proj Title=Stream0363 Base Level Engineering
Current Plan=p01
Default Exp/Contr=0.3,0.1
English Units
Geom File=g01
Flow File=f01
Plan File=p01
BEGIN DESCRIPTION:
Stream0363
END DESCRIPTION:

--- Stream0363.p01 (plan) ---

Plan Title=Multiple Run
Short Identifier=Multiple
Geom File=g01
Flow File=f01
Subcritical Flow
K Sum by GR= 0
Std Step Tol= 0.01
Critical Tol= 0.01
Num of Std Step Trials= 20
Max Error Tol= 0.3
Flow Tol Ratio= 0.001
Split Flow NTrial= 30
Split Flow Tol= 0.02
Split Flow Ratio= 0.02
Log Output Level= 0
Friction Slope Method= 1
Unsteady Friction Slope Method= 2
Unsteady Bridges Friction Slope Method= 1
Parabolic Critical Depth
Global Vel Dist=  1 , 1 , 1
Global Log Level= 0
CheckData=True
Encroach Param= -1, 0, 0, 0
BEGIN DESCRIPTION:
Multiple Run
END DESCRIPTION:

--- Stream0363.f01 (steady flow) ---

Flow Title=Multiple
Number of Profiles=7
Profile Names=10-year,25-year,50-year,1pct_min,100-year,1pct_plu,500-year
River Rch & RM= Stream0363,Reach-1,2941
     468     737     975     626    1249    2491    2025
Boundary for River Rch & Prof#=Stream0363,Reach-1,1
Up Type=0
Dn Type=3
Dn Slope=0.005
Boundary for River Rch & Prof#=Stream0363,Reach-1,2
Up Type=0
Dn Type=3
Dn Slope=0.005
Boundary for River Rch & Prof#=Stream0363,Reach-1,3
Up Type=0
Dn Type=3
Dn Slope=0.005
Boundary for River Rch & Prof#=Stream0363,Reach-1,4
Up Type=0
Dn Type=3
Dn Slope=0.005
Boundary for River Rch & Prof#=Stream0363,Reach-1,5
Up Type=0
Dn Type=3
Dn Slope=0.005
Boundary for River Rch & Prof#=Stream0363,Reach-1,6
Up Type=0
Dn Type=3
Dn Slope=0.005
Boundary for River Rch & Prof#=Stream0363,Reach-1,7
Up Type=0
Dn Type=3
Dn Slope=0.005

--- Stream0363.g01 (geometry) ---

Geom Title=Existing Conditions

River Reach=Stream0363,Reach-1
Reach XY= 30
      2532725.00     13759375.00      2532585.48     13759373.83
      2532519.03     13759327.35      2532426.58     13759321.17
      2532377.18     13759281.12      2532322.80     13759268.92
      2532277.20     13759231.08      2532222.80     13759218.92
      2532069.07     13759127.24      2531876.46     13759121.46
      2531723.54     13758978.54      2531485.43     13758973.61
      2531424.68     13758932.23      2531380.85     13758972.15
      2531364.23     13759034.67      2531281.07     13759116.87
      2531222.81     13759131.10      2531173.27     13759170.81
      2531122.71     13759180.85      2531023.50     13759271.53
      2530930.90     13759273.03      2530827.42     13759180.54
      2530726.59     13759171.17      2530677.18     13759131.12
      2530518.94     13759066.86      2530384.66     13758935.79
      2530301.14     13758902.16      2530278.71     13758873.66
      2530267.05     13758818.89      2530225.00     13758775.00

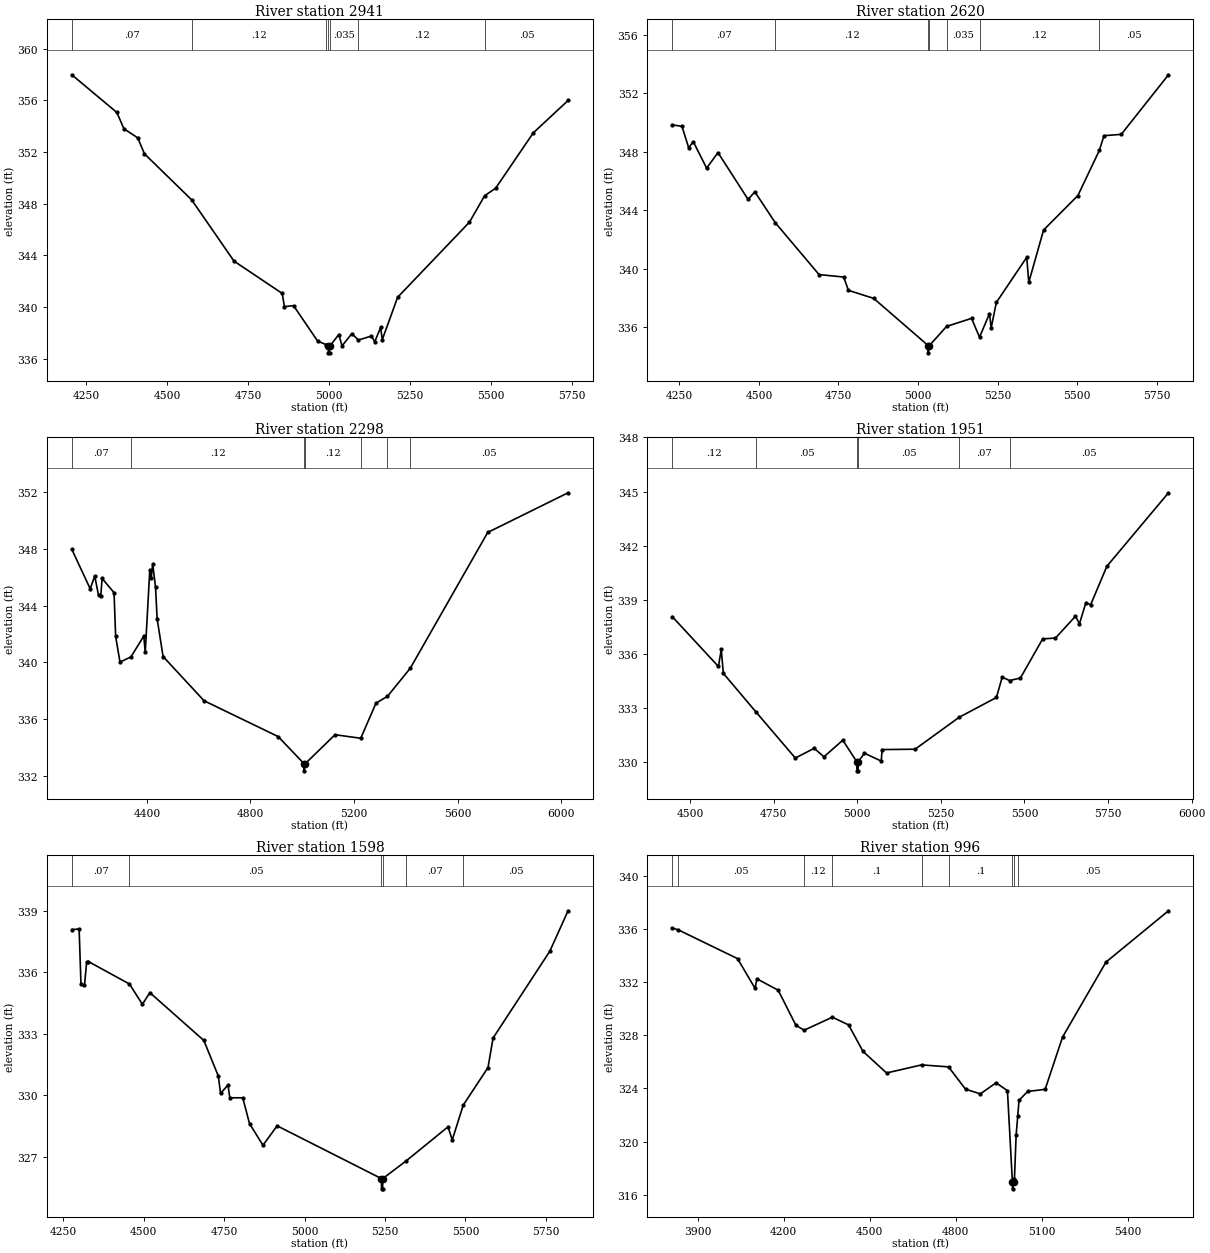
Type RM Length L Ch R = 1,2941,321,321,321
BEGIN DESCRIPTION:
XS6546
END DESCRIPTION:
XS GIS Cut Line= 3
      2533217.72     13758830.72      2532655.21     13759341.15
      2532556.25     13760106.81
#Sta/Elev= 30
  4206.0  357.97  4345.2  355.05  4366.8  353.79  4409.4  353.09  4430.3  351.85
  4575.8  348.29  4706.7  343.54  4855.4  341.04  4862.1  340.02  4890.5  340.09
  4964.7  337.35  4991.4  337.07  4997.7  336.94  4998.0  336.44  5001.5  336.44
  5001.7  336.94  5030.0  337.86  5040.0  336.98  5070.3  337.93  5090.3  337.43
  5130.8  337.74  5140.9  337.29  5159.1  338.41  5164.2  337.46  5211.5  340.74
  5433.3  346.56  5480.2  348.61  5513.9  349.18  5630.1  353.47  5737.6  355.98
#Mann=7,-1,0
  4206.0    0.07       0  4575.8    0.12       0  4991.4   0.035       0
  4997.7   0.035       0  5001.7   0.035       0  5090.3    0.12       0
  5480.2    0.05       0
Bank Sta=4997.7,5001.7
Exp/Cntr=0.3,0.1

Type RM Length L Ch R = 1,2620,322,322,322
BEGIN DESCRIPTION:
E20918
END DESCRIPTION:
XS GIS Cut Line= 3
      2532991.91     13758830.05      2532353.91     13759281.42
      2532093.49     13760014.94
#Sta/Elev= 30
  4227.5  349.85  4258.2  349.75  4279.1  348.29  4293.9  348.69  4335.7  346.89
  4371.4  347.95  4466.2  344.74  4487.1  345.27  4551.5  343.15  4689.0  339.60
  4766.5  339.43  4781.3  338.52  4860.7  337.97  5032.0  334.74  5032.3  334.24
  5036.0  334.74  5089.9  336.05  5168.4  336.60  5193.4  335.31  5224.8  336.92
  5230.1  335.95  5246.3  337.69  5341.8  340.78  5348.3  339.07  5394.8  342.65
  5502.6  345.01  5570.1  348.10  5584.6  349.11  5638.9  349.20  5787.4  353.28
#Mann=7,-1,0
  4227.5    0.07       0  4551.5    0.12       0  5032.0    0.05       0
  5036.0    0.12       0  5089.9   0.035       0  5193.4    0.12       0
  5570.1    0.05       0
Bank Sta=5032,5036
Exp/Cntr=0.3,0.1

Type RM Length L Ch R = 1,2298,347,347,347
BEGIN DESCRIPTION:
XS6545
END DESCRIPTION:
XS GIS Cut Line= 3
      2532868.76     13758742.19      2532097.92     13759096.35
      2531749.48     13760105.27
#Sta/Elev= 30
  4110.2  347.98  4181.3  345.19  4198.8  346.09  4213.4  344.73  4221.8  344.66
  4227.3  345.92  4273.3  344.92  4279.4  341.84  4296.2  340.02  4338.4  340.38
  4388.2  341.86  4393.7  340.70  4411.2  346.49  4416.7  345.92  4422.5  346.95
  4433.5  345.29  4439.6  343.08  4462.6  340.41  4620.6  337.29  4906.7  334.76
  5007.0  332.84  5007.3  332.34  5011.0  332.84  5126.3  334.89  5225.6  334.64
  5284.4  337.12  5328.7  337.60  5417.0  339.59  5715.7  349.17  6025.9  351.97
#Mann=7,-1,0
  4110.2    0.07       0  4338.4    0.12       0  5007.0    0.05       0
  5011.0    0.12       0  5225.6    0.07       0  5328.7   0.035       0
  5417.0    0.05       0
Bank Sta=5007,5011
Exp/Cntr=0.3,0.1

Type RM Length L Ch R = 1,1951,353,353,353
BEGIN DESCRIPTION:
E20917
END DESCRIPTION:
XS GIS Cut Line= 3
      2532223.69     13758699.83      2531715.89     13759073.09
      2531473.34     13759891.68
#Sta/Elev= 30
  4446.7  338.06  4584.9  335.29  4593.4  336.24  4599.6  334.91  4698.4  332.74
  4814.8  330.21  4871.2  330.75  4900.5  330.28  4956.8  331.20  4998.8  330.00
  4999.0  329.50  5002.5  329.50  5002.8  330.00  5021.6  330.48  5071.8  330.04
  5074.4  330.68  5173.0  330.70  5304.6  332.47  5416.2  333.57  5433.5  334.70
  5455.4  334.51  5487.9  334.65  5554.4  336.82  5592.8  336.87  5652.6  338.08
  5664.5  337.66  5683.8  338.84  5697.8  338.71  5746.4  340.85  5930.7  344.93
#Mann=6,-1,0
  4446.7    0.12       0  4698.4    0.05       0  4998.8    0.05       0
  5002.8    0.05       0  5304.6    0.07       0  5455.4    0.05       0
Bank Sta=4998.8,5002.8
Exp/Cntr=0.3,0.1

Type RM Length L Ch R = 1,1598,602,602,602
BEGIN DESCRIPTION:
XS6544
END DESCRIPTION:
XS GIS Cut Line= 4
      2532051.01     13758580.74      2531561.46     13758799.48
      2531415.63     13759002.60      2531306.43     13759751.34
#Sta/Elev= 30
  4276.3  338.09  4299.1  338.12  4304.8  335.44  4315.7  335.36  4322.4  336.49
  4327.8  336.53  4455.6  335.43  4495.8  334.44  4519.0  335.01  4686.9  332.67
  4731.9  330.93  4738.8  330.08  4762.0  330.50  4767.5  329.87  4807.8  329.87
  4828.8  328.61  4870.6  327.55  4914.7  328.50  5239.0  325.92  5239.2  325.42
  5242.7  325.42  5243.0  325.92  5315.4  326.78  5446.0  328.45  5459.1  327.81
  5493.2  329.51  5570.3  331.35  5586.0  332.79  5762.3  337.03  5819.2  339.01
#Mann=6,-1,0
  4276.3    0.07       0  4455.6    0.05       0  5239.0    0.05       0
  5243.0    0.05       0  5315.4    0.07       0  5493.2    0.05       0
Bank Sta=5239,5243
Exp/Cntr=0.3,0.1

Type RM Length L Ch R = 1,996,360,360,360
BEGIN DESCRIPTION:
E20916
END DESCRIPTION:
XS GIS Cut Line= 4
      2531902.53     13758621.70      2531221.09     13758869.10
      2531025.78     13759172.92      2530930.36     13759810.48
#Sta/Elev= 30
  3811.0  336.07  3832.5  335.93  4038.8  333.77  4100.0  331.53  4106.3  332.25
  4180.7  331.39  4242.4  328.75  4271.1  328.38  4369.5  329.36  4426.1  328.78
  4476.6  326.78  4558.6  325.16  4680.7  325.77  4774.7  325.62  4834.0  323.94
  4885.6  323.59  4940.5  324.42  4980.1  323.83  4997.5  316.94  4997.8  316.44
  5001.5  316.94  5004.6  317.21  5010.5  320.49  5016.1  321.94  5020.6  323.11
  5050.9  323.77  5111.6  323.93  5172.3  327.86  5323.9  333.51  5541.8  337.37
#Mann=9,-1,0
  3811.0    0.07       0  3832.5    0.05       0  4271.1    0.12       0
  4369.5     0.1       0  4680.7    0.05       0  4774.7     0.1       0
  4997.5    0.05       0  5001.5     0.1       0  5016.1    0.05       0
Bank Sta=4997.5,5001.5
Exp/Cntr=0.3,0.1

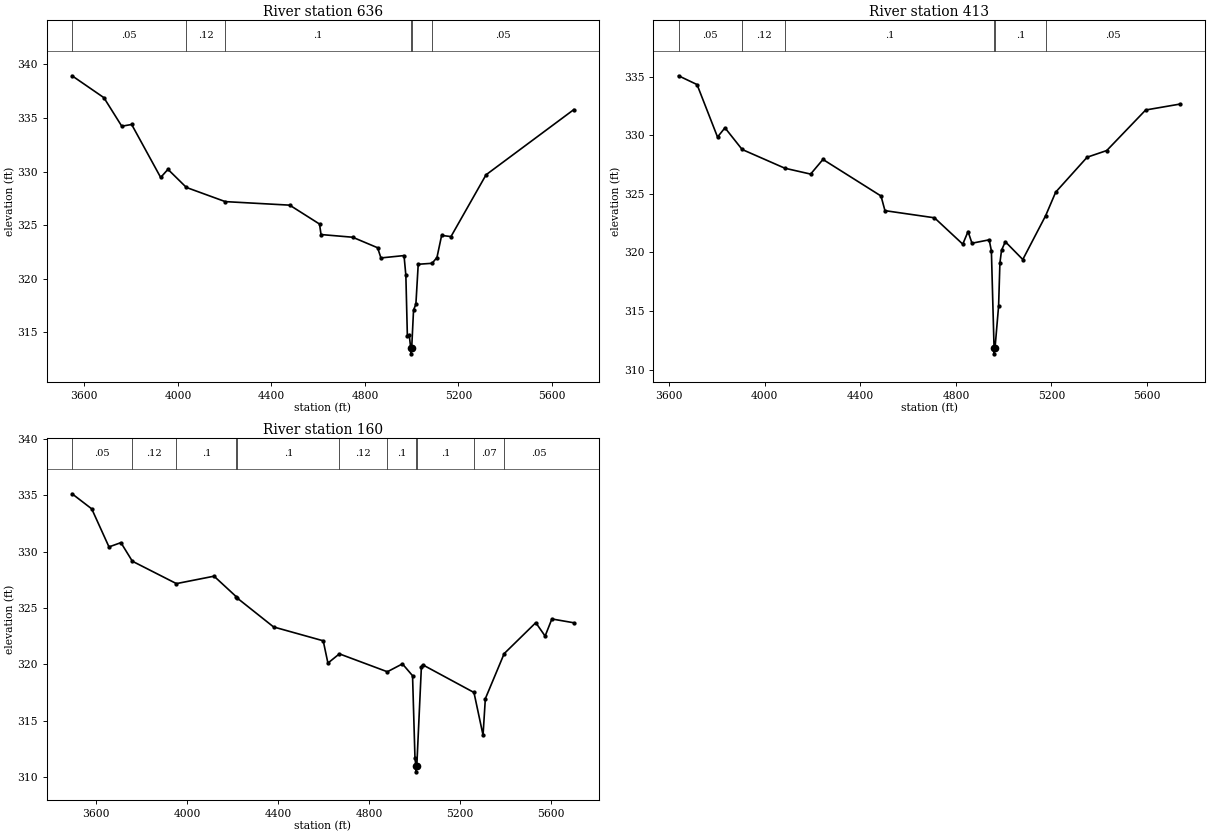
Type RM Length L Ch R = 1,636,223,223,223
BEGIN DESCRIPTION:
XS6543
END DESCRIPTION:
XS GIS Cut Line= 4
      2531915.66     13758414.05      2531290.63     13758632.81
      2530696.88     13759132.81      2530686.47     13759840.59
#Sta/Elev= 30
  3547.4  338.93  3683.5  336.89  3760.0  334.23  3802.3  334.39  3926.4  329.45
  3957.5  330.21  4036.4  328.52  4202.7  327.20  4478.3  326.87  4605.8  325.11
  4612.3  324.13  4747.5  323.88  4854.2  322.90  4868.5  321.95  4967.3  322.17
  4975.1  320.33  4981.6  314.66  4989.4  314.80  4996.0  313.51  4996.3  313.01
  5000.0  313.51  5008.0  317.10  5018.0  317.63  5028.0  321.36  5087.3  321.45
  5108.1  321.99  5128.1  324.05  5168.1  323.94  5318.1  329.70  5693.7  335.78
#Mann=6,-1,0
  3547.4    0.05       0  4036.4    0.12       0  4202.7     0.1       0
  4996.0    0.05       0  5000.0     0.1       0  5087.3    0.05       0
Bank Sta=4996,5000
Exp/Cntr=0.3,0.1

Type RM Length L Ch R = 1,413,253,253,253
BEGIN DESCRIPTION:
E20915
END DESCRIPTION:
XS GIS Cut Line= 5
      2531707.25     13758448.07      2531260.16     13758621.70
      2530526.65     13759003.65      2530439.84     13759181.60
      2530327.00     13759767.52
#Sta/Elev= 30
  3638.5  335.08  3716.0  334.33  3801.8  329.85  3832.9  330.64  3904.9  328.79
  4083.9  327.19  4191.6  326.69  4243.3  327.94  4486.4  324.82  4502.9  323.57
  4710.2  322.96  4828.8  320.71  4850.9  321.79  4867.3  320.79  4939.3  321.08
  4948.6  320.14  4959.8  311.85  4960.0  311.35  4963.8  311.85  4978.8  315.43
  4984.3  319.10  4991.1  320.19  5006.9  320.92  5080.1  319.40  5175.8  323.14
  5217.9  325.15  5349.5  328.13  5431.7  328.70  5594.7  332.16  5739.8  332.67
#Mann=6,-1,0
  3638.5    0.05       0  3904.9    0.12       0  4083.9     0.1       0
  4959.8    0.05       0  4963.8     0.1       0  5175.8    0.05       0
Bank Sta=4959.8,4963.8
Exp/Cntr=0.3,0.1

Type RM Length L Ch R = 1,160,0,0,0
BEGIN DESCRIPTION:
E20914
END DESCRIPTION:
XS GIS Cut Line= 5
      2531707.18     13758404.70      2530687.24     13758847.40
      2530405.12     13758856.08      2530175.09     13758973.26
      2530096.98     13759520.03
#Sta/Elev= 30
  3494.5  335.14  3580.9  333.80  3656.7  330.42  3709.1  330.80  3759.3  329.15
  3952.9  327.16  4118.3  327.82  4216.3  325.99  4221.1  325.86  4379.9  323.31
  4597.9  322.08  4618.6  320.10  4668.9  320.92  4879.7  319.33  4945.9  320.03
  4990.4  318.98  5001.0  311.69  5005.0  310.94  5005.3  310.44  5009.0  310.94
  5029.2  319.76  5034.9  319.95  5260.2  317.49  5300.1  313.70  5310.2  316.94
  5392.9  320.94  5531.8  323.69  5572.8  322.50  5602.5  324.02  5699.1  323.68
#Mann=11,-1,0
  3494.5    0.05       0  3759.3    0.12       0  3952.9     0.1       0
  4216.3    0.07       0  4221.1     0.1       0  4668.9    0.12       0
  4879.7     0.1       0  5005.0    0.05       0  5009.0     0.1       0
  5260.2    0.07       0  5392.9    0.05       0
Bank Sta=5005,5009
Exp/Cntr=0.3,0.1

Chan Stop Cuts=-1