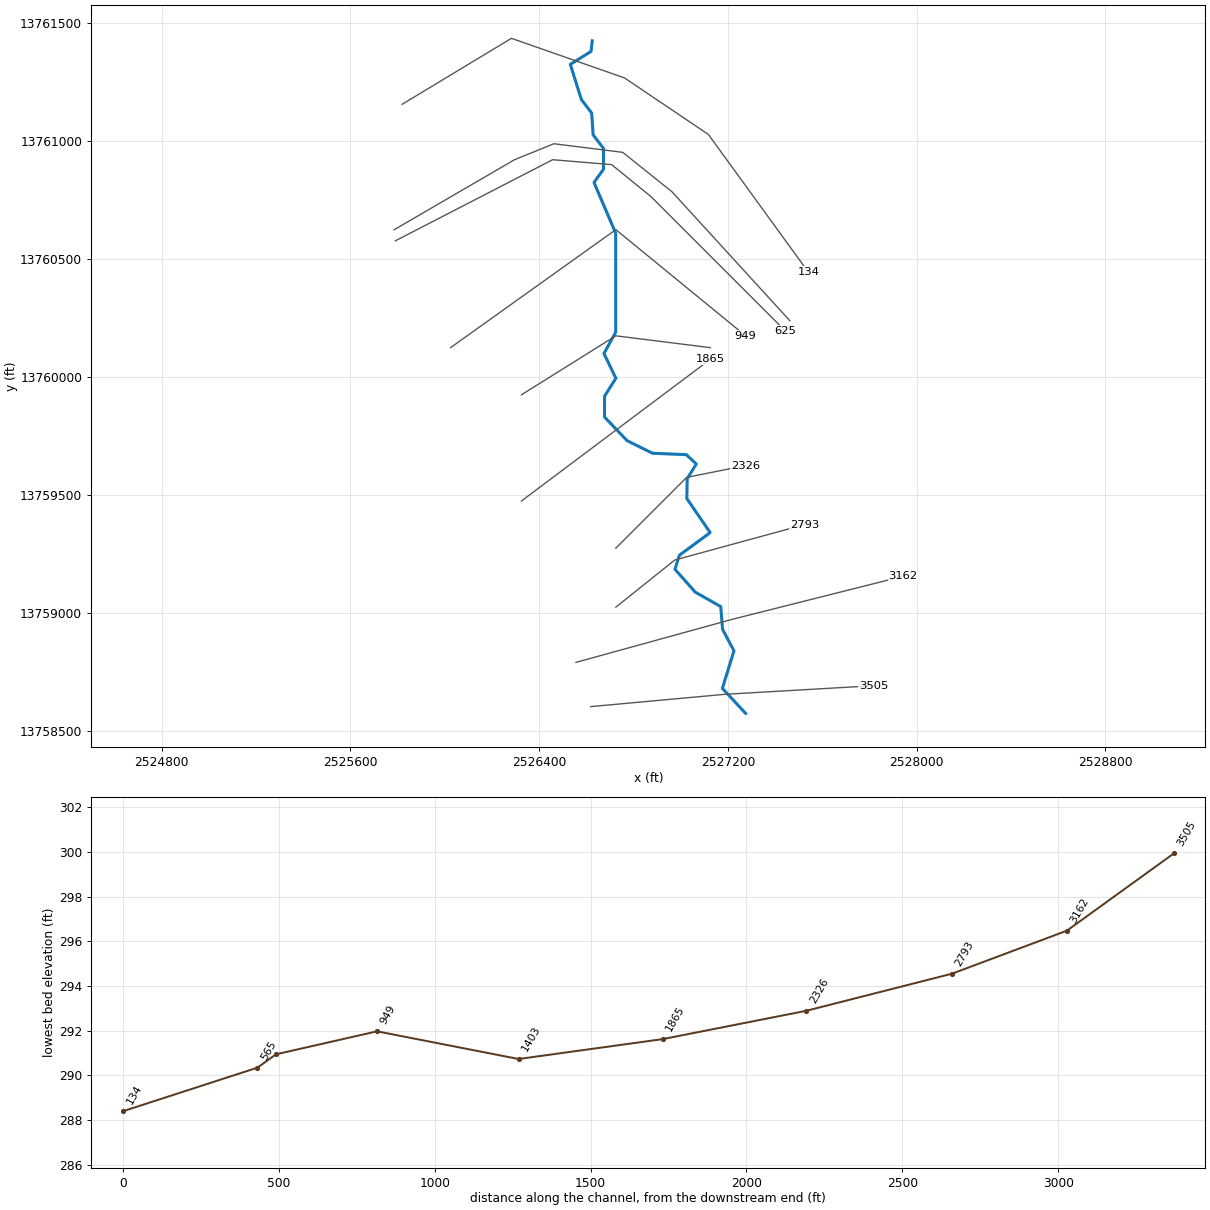
--- Stream0364.prj (project) ---

Proj Title=Stream0364 Base Level Engineering
Current Plan=p01
Default Exp/Contr=0.3,0.1
English Units
Geom File=g01
Flow File=f01
Plan File=p01
BEGIN DESCRIPTION:
Stream0364
END DESCRIPTION:

--- Stream0364.p01 (plan) ---

Plan Title=Multiple Run
Short Identifier=Multiple
Geom File=g01
Flow File=f01
Subcritical Flow
K Sum by GR= 0
Std Step Tol= 0.01
Critical Tol= 0.01
Num of Std Step Trials= 20
Max Error Tol= 0.3
Flow Tol Ratio= 0.001
Split Flow NTrial= 30
Split Flow Tol= 0.02
Split Flow Ratio= 0.02
Log Output Level= 0
Friction Slope Method= 1
Unsteady Friction Slope Method= 2
Unsteady Bridges Friction Slope Method= 1
Parabolic Critical Depth
Global Vel Dist=  1 , 1 , 1
Global Log Level= 0
CheckData=True
Encroach Param= -1, 0, 0, 0
BEGIN DESCRIPTION:
Multiple Run
END DESCRIPTION:

--- Stream0364.f01 (steady flow) ---

Flow Title=Multiple
Number of Profiles=7
Profile Names=10-year,25-year,50-year,1pct_min,100-year,1pct_plu,500-year
River Rch & RM= Stream0364,Reach-1,3505
     695    1114    1491     966    1928    3847    3191
River Rch & RM= Stream0364,Reach-1,1865
     710    1137    1522     986    1967    3925    3252
Boundary for River Rch & Prof#=Stream0364,Reach-1,1
Up Type=0
Dn Type=3
Dn Slope=0.005
Boundary for River Rch & Prof#=Stream0364,Reach-1,2
Up Type=0
Dn Type=3
Dn Slope=0.005
Boundary for River Rch & Prof#=Stream0364,Reach-1,3
Up Type=0
Dn Type=3
Dn Slope=0.005
Boundary for River Rch & Prof#=Stream0364,Reach-1,4
Up Type=0
Dn Type=3
Dn Slope=0.005
Boundary for River Rch & Prof#=Stream0364,Reach-1,5
Up Type=0
Dn Type=3
Dn Slope=0.005
Boundary for River Rch & Prof#=Stream0364,Reach-1,6
Up Type=0
Dn Type=3
Dn Slope=0.005
Boundary for River Rch & Prof#=Stream0364,Reach-1,7
Up Type=0
Dn Type=3
Dn Slope=0.005

--- Stream0364.g01 (geometry) ---

Geom Title=Existing Conditions

River Reach=Stream0364,Reach-1
Reach XY= 30
      2527275.00     13758575.00      2527176.56     13758681.03
      2527225.71     13758840.06      2527177.36     13758930.98
      2527169.58     13759027.67      2527061.77     13759088.63
      2526975.54     13759185.64      2526994.40     13759245.12
      2527124.83     13759341.04      2527025.95     13759485.49
      2527027.37     13759569.12      2527066.01     13759632.07
      2527024.01     13759671.46      2526880.93     13759677.25
      2526772.69     13759730.82      2526676.96     13759830.88
      2526677.19     13759919.03      2526725.27     13759995.18
      2526674.61     13760100.00      2526724.46     13760190.21
      2526724.48     13760609.78      2526632.56     13760825.00
      2526672.64     13760880.89      2526672.83     13760969.02
      2526628.86     13761026.60      2526622.65     13761119.03
      2526578.85     13761176.60      2526532.21     13761325.30
      2526619.99     13761380.33      2526625.00     13761425.00

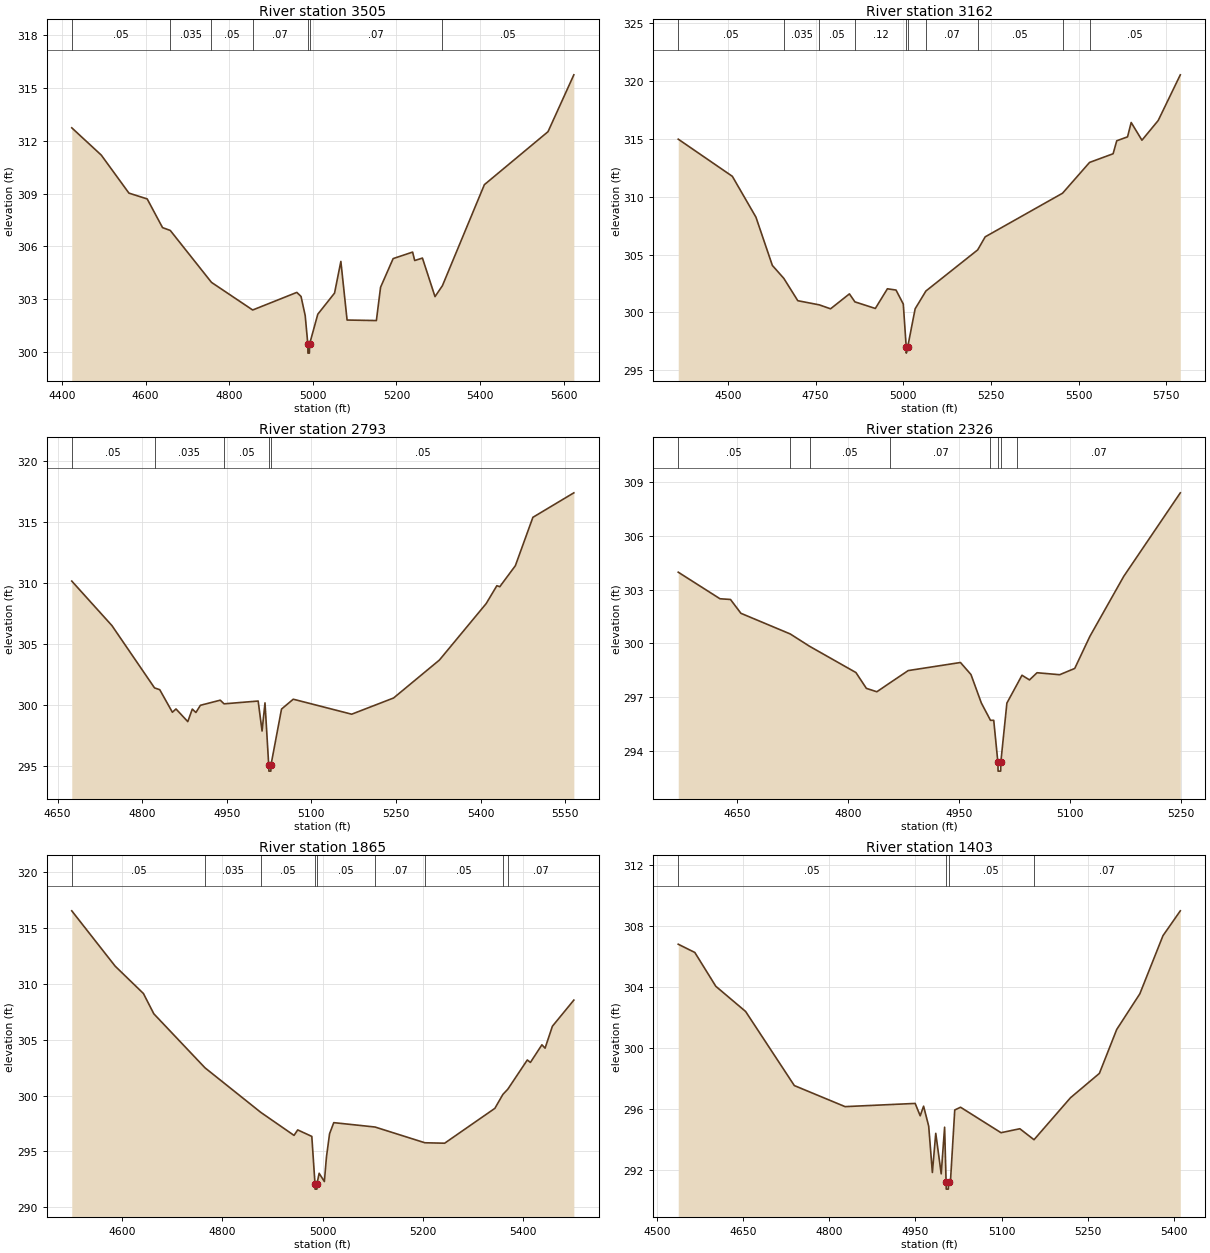
Type RM Length L Ch R = 1,3505,343,343,343
BEGIN DESCRIPTION:
Stream0364 6.0
END DESCRIPTION:
XS GIS Cut Line= 3
      2526618.73     13758603.64      2527186.46     13758655.73
      2527816.69     13758692.19
#Sta/Elev= 30
  4423.2  312.74  4493.8  311.19  4560.0  309.03  4603.7  308.70  4640.4  307.07
  4658.9  306.91  4757.5  303.96  4856.1  302.39  4961.7  303.39  4971.8  303.16
  4981.8  302.07  4988.1  300.44  4988.3  299.94  4991.8  299.94  4992.1  300.44
  5011.9  302.15  5052.0  303.35  5067.1  305.15  5082.0  301.82  5152.1  301.79
  5162.1  303.68  5192.2  305.31  5238.8  305.68  5243.8  305.20  5262.3  305.34
  5292.4  303.15  5310.1  303.77  5410.5  309.51  5562.8  312.52  5624.6  315.75
#Mann=7,-1,0
  4423.2    0.05       0  4658.9   0.035       0  4757.5    0.05       0
  4856.1    0.07       0  4988.1    0.05       0  4992.1    0.07       0
  5310.1    0.05       0
Bank Sta=4988.1,4992.1
Exp/Cntr=0.3,0.1

Type RM Length L Ch R = 1,3162,369,369,369
BEGIN DESCRIPTION:
XS6547
END DESCRIPTION:
XS GIS Cut Line= 3
      2526556.26     13758791.15      2527217.71     13758973.44
      2527940.83     13759155.52
#Sta/Elev= 30
  4358.3  314.97  4512.6  311.76  4579.9  308.23  4626.7  304.06  4659.4  302.94
  4699.3  301.01  4760.7  300.65  4792.7  300.31  4846.5  301.60  4862.1  300.91
  4920.4  300.34  4954.8  302.04  4979.4  301.93  5000.1  300.72  5008.5  296.98
  5008.7  296.48  5012.5  296.98  5033.9  300.31  5064.7  301.85  5212.2  305.40
  5233.7  306.53  5454.3  310.30  5531.3  312.96  5598.5  313.71  5608.8  314.83
  5639.6  315.17  5650.0  316.41  5680.7  314.88  5727.0  316.58  5790.1  320.53
#Mann=10,-1,0
  4358.3    0.05       0  4659.4   0.035       0  4760.7    0.05       0
  4862.1    0.12       0  5008.5    0.05       0  5012.5    0.12       0
  5064.7    0.07       0  5212.2    0.05       0  5454.3   0.035       0
  5531.3    0.05       0
Bank Sta=5008.5,5012.5
Exp/Cntr=0.3,0.1

Type RM Length L Ch R = 1,2793,467,467,467
BEGIN DESCRIPTION:
Stream0364 5.0
END DESCRIPTION:
XS GIS Cut Line= 3
      2526725.04     13759025.03      2526975.00     13759225.00
      2527525.00     13759375.00
#Sta/Elev= 30
  4675.2  310.14  4746.4  306.49  4821.9  301.38  4831.2  301.23  4853.6  299.38
  4860.0  299.65  4880.9  298.61  4888.9  299.64  4895.3  299.36  4903.3  299.95
  4938.5  300.37  4945.2  300.07  5005.7  300.30  5012.6  297.84  5017.8  300.15
  5024.4  295.05  5024.7  294.55  5028.2  294.55  5028.4  295.05  5047.1  299.64
  5067.9  300.45  5171.5  299.22  5245.8  300.55  5327.0  303.66  5409.9  308.29
  5428.9  309.76  5434.1  309.68  5461.7  311.40  5492.8  315.37  5565.4  317.38
#Mann=5,-1,0
  4675.2    0.05       0  4821.9   0.035       0  4945.2    0.05       0
  5024.4    0.05       0  5028.4    0.05       0
Bank Sta=5024.4,5028.4
Exp/Cntr=0.3,0.1

Type RM Length L Ch R = 1,2326,461,461,461
BEGIN DESCRIPTION:
Stream0364 4.0
END DESCRIPTION:
XS GIS Cut Line= 3
      2526725.02     13759275.02      2527025.00     13759575.00
      2527275.01     13759625.00
#Sta/Elev= 30
  4570.4  303.97  4626.9  302.49  4641.1  302.45  4655.2  301.68  4721.9  300.53
  4748.2  299.84  4810.8  298.38  4824.9  297.50  4839.1  297.31  4857.3  297.82
  4881.5  298.49  4952.2  298.94  4966.4  298.27  4980.5  296.68  4992.8  295.72
  4997.2  295.72  5002.8  293.39  5003.1  292.89  5006.6  292.89  5006.8  293.39
  5015.0  296.68  5029.0  297.74  5035.4  298.23  5045.6  297.97  5055.8  298.37
  5086.4  298.26  5106.8  298.61  5127.2  300.39  5173.1  303.74  5249.6  308.39
#Mann=8,-1,0
  4570.4    0.05       0  4721.9   0.035       0  4748.2    0.05       0
  4857.3    0.07       0  4992.8    0.05       0  5002.8    0.05       0
  5006.8    0.05       0  5029.0    0.07       0
Bank Sta=5002.8,5006.8
Exp/Cntr=0.3,0.1

Type RM Length L Ch R = 1,1865,462,462,462
BEGIN DESCRIPTION:
Stream0364 3.0
END DESCRIPTION:
XS GIS Cut Line= 3
      2526325.03     13759475.02      2526725.00     13759775.00
      2527125.03     13760075.02
#Sta/Elev= 30
  4500.5  316.53  4586.9  311.58  4643.2  309.13  4664.0  307.31  4765.8  302.48
  4877.0  298.49  4943.2  296.43  4950.5  296.92  4978.6  296.34  4984.9  292.12
  4985.1  291.62  4988.7  291.62  4989.0  292.12  4993.2  293.04  5003.6  292.30
  5007.8  294.51  5014.0  296.58  5022.3  297.57  5104.4  297.18  5203.8  295.77
  5243.2  295.73  5343.2  298.85  5359.2  300.10  5368.9  300.56  5407.8  303.18
  5414.0  302.96  5436.9  304.54  5443.2  304.24  5457.8  306.20  5500.5  308.54
#Mann=9,-1,0
  4500.5    0.05       0  4765.8   0.035       0  4877.0    0.05       0
  4984.9    0.05       0  4989.0    0.05       0  5104.4    0.07       0
  5203.8    0.05       0  5359.2   0.035       0  5368.9    0.07       0
Bank Sta=4984.9,4989
Exp/Cntr=0.3,0.1

Type RM Length L Ch R = 1,1403,454,454,454
BEGIN DESCRIPTION:
Stream0364 2.0
END DESCRIPTION:
XS GIS Cut Line= 3
      2526324.97     13759924.98      2526725.00     13760175.00
      2527124.95     13760125.01
#Sta/Elev= 30
  4536.7  306.79  4565.6  306.25  4602.2  304.03  4654.1  302.38  4739.0  297.52
  4827.4  296.14  4949.5  296.35  4958.3  295.54  4964.2  296.17  4973.1  294.86
  4979.5  291.82  4985.4  294.39  4994.9  291.73  5000.8  294.79  5003.4  291.23
  5003.7  290.73  5007.3  290.73  5007.6  291.23  5011.0  291.23  5018.5  295.92
  5028.6  296.10  5099.1  294.43  5131.9  294.69  5156.6  293.97  5220.1  296.72
  5270.5  298.32  5300.7  301.20  5341.0  303.54  5381.3  307.35  5411.5  308.98
#Mann=4,-1,0
  4536.7    0.05       0  5003.4    0.05       0  5007.6    0.05       0
  5156.6    0.07       0
Bank Sta=5003.4,5007.6
Exp/Cntr=0.3,0.1

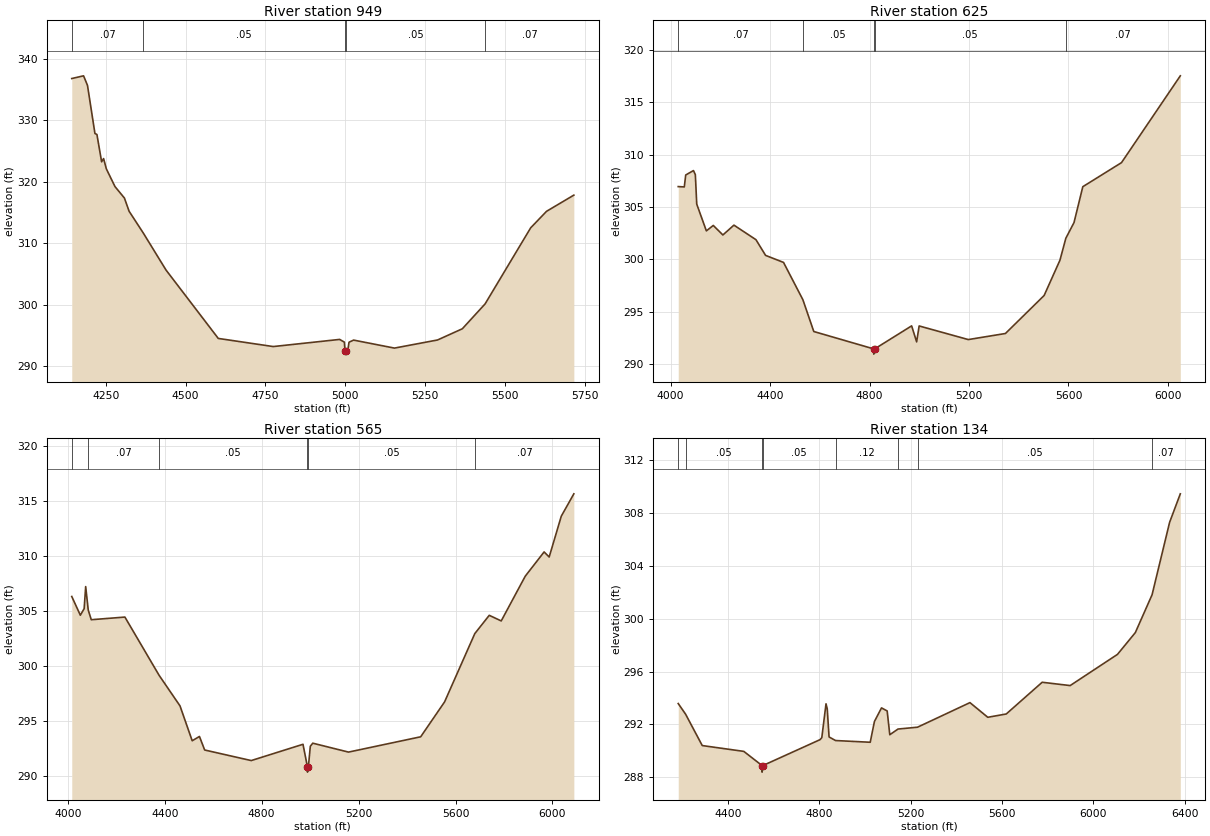
Type RM Length L Ch R = 1,949,324,324,324
BEGIN DESCRIPTION:
Stream0364 1.0
END DESCRIPTION:
XS GIS Cut Line= 3
      2526024.98     13760124.99      2526725.00     13760625.00
      2527275.01     13760174.99
#Sta/Elev= 30
  4144.0  336.76  4180.9  337.20  4193.2  335.65  4216.5  327.83  4222.7  327.67
  4237.4  323.23  4243.6  323.75  4252.2  322.08  4279.2  319.20  4308.7  317.34
  4323.4  315.19  4367.9  311.64  4439.0  305.63  4602.4  294.52  4774.4  293.20
  4982.1  294.36  4996.9  293.92  4999.1  292.47  4999.4  291.97  5003.3  292.47
  5007.5  292.47  5011.4  293.90  5025.8  294.25  5153.6  292.95  5288.5  294.27
  5366.0  296.09  5437.2  300.13  5579.9  312.50  5629.5  315.18  5714.9  317.81
#Mann=5,-1,0
  4144.0    0.07       0  4367.9    0.05       0  4999.1    0.05       0
  5003.3    0.05       0  5437.2    0.07       0
Bank Sta=4999.1,5003.3
Exp/Cntr=0.3,0.1

Type RM Length L Ch R = 1,625,60,60,60
BEGIN DESCRIPTION:
XS6549
END DESCRIPTION:
XS GIS Cut Line= 5
      2525790.61     13760577.60      2526457.29     13760921.35
      2526707.29     13760900.52      2526873.96     13760765.10
      2527441.69     13760197.37
#Sta/Elev= 30
  4031.0  306.94  4055.4  306.91  4061.1  308.05  4092.2  308.47  4099.8  308.08
  4105.4  305.27  4144.1  302.71  4171.9  303.23  4210.6  302.32  4254.9  303.26
  4343.5  301.87  4382.2  300.37  4454.3  299.70  4532.1  296.14  4576.0  293.10
  4816.8  291.44  4817.1  290.94  4821.0  291.44  4969.4  293.64  4989.5  292.11
  4999.6  293.63  5197.2  292.33  5346.5  292.91  5502.1  296.54  5565.7  299.91
  5589.4  302.01  5622.3  303.51  5657.6  306.93  5813.2  309.23  6049.6  317.52
#Mann=5,-1,0
  4031.0    0.07       0  4532.1    0.05       0  4816.8    0.05       0
  4821.0    0.05       0  5589.4    0.07       0
Bank Sta=4816.8,4821
Exp/Cntr=0.3,0.1

Type RM Length L Ch R = 1,565,431,431,431
BEGIN DESCRIPTION:
XS6548
END DESCRIPTION:
XS GIS Cut Line= 6
      2525785.41     13760624.47      2526295.83     13760921.35
      2526462.50     13760989.06      2526754.17     13760952.60
      2526962.50     13760785.94      2527462.50     13760239.07
#Sta/Elev= 30
  4016.3  306.30  4051.7  304.60  4067.5  305.20  4073.7  307.20  4084.3  305.07
  4096.8  304.19  4235.6  304.43  4376.7  299.14  4463.0  296.36  4513.3  293.19
  4543.3  293.58  4564.8  292.35  4757.0  291.39  4970.6  292.87  4988.7  290.84
  4989.0  290.34  4992.9  290.84  5000.8  292.69  5010.9  292.97  5158.5  292.16
  5456.3  293.55  5554.9  296.72  5679.7  302.93  5739.3  304.59  5788.7  304.08
  5888.0  308.15  5965.7  310.35  5986.6  309.89  6036.6  313.60  6088.4  315.63
#Mann=6,-1,0
  4016.3    0.05       0  4084.3    0.07       0  4376.7    0.05       0
  4988.7    0.05       0  4992.9    0.05       0  5679.7    0.07       0
Bank Sta=4988.7,4992.9
Exp/Cntr=0.3,0.1

Type RM Length L Ch R = 1,134,0,0,0
BEGIN DESCRIPTION:
E20919
END DESCRIPTION:
XS GIS Cut Line= 5
      2525819.30     13761156.14      2526282.60     13761435.71
      2526761.83     13761267.98      2527117.27     13761028.36
      2527540.27     13760445.73
#Sta/Elev= 30
  4182.7  293.58  4215.1  292.77  4287.8  290.40  4469.7  289.96  4549.3  288.89
  4549.6  288.39  4553.6  288.89  4803.7  290.85  4811.1  291.00  4829.5  293.56
  4834.8  293.19  4842.9  291.05  4871.3  290.78  5023.0  290.65  5041.4  292.22
  5072.4  293.25  5097.2  293.02  5108.7  291.22  5144.7  291.65  5230.1  291.79
  5459.5  293.65  5537.5  292.54  5618.4  292.79  5775.6  295.19  5898.1  294.94
  6105.2  297.30  6183.4  298.95  6256.6  301.81  6333.3  307.29  6380.2  309.45
#Mann=8,-1,0
  4182.7    0.07       0  4215.1    0.05       0  4549.3    0.05       0
  4553.6    0.05       0  4871.3    0.12       0  5144.7     0.1       0
  5230.1    0.05       0  6256.6    0.07       0
Bank Sta=4549.3,4553.6
Exp/Cntr=0.3,0.1

Chan Stop Cuts=-1