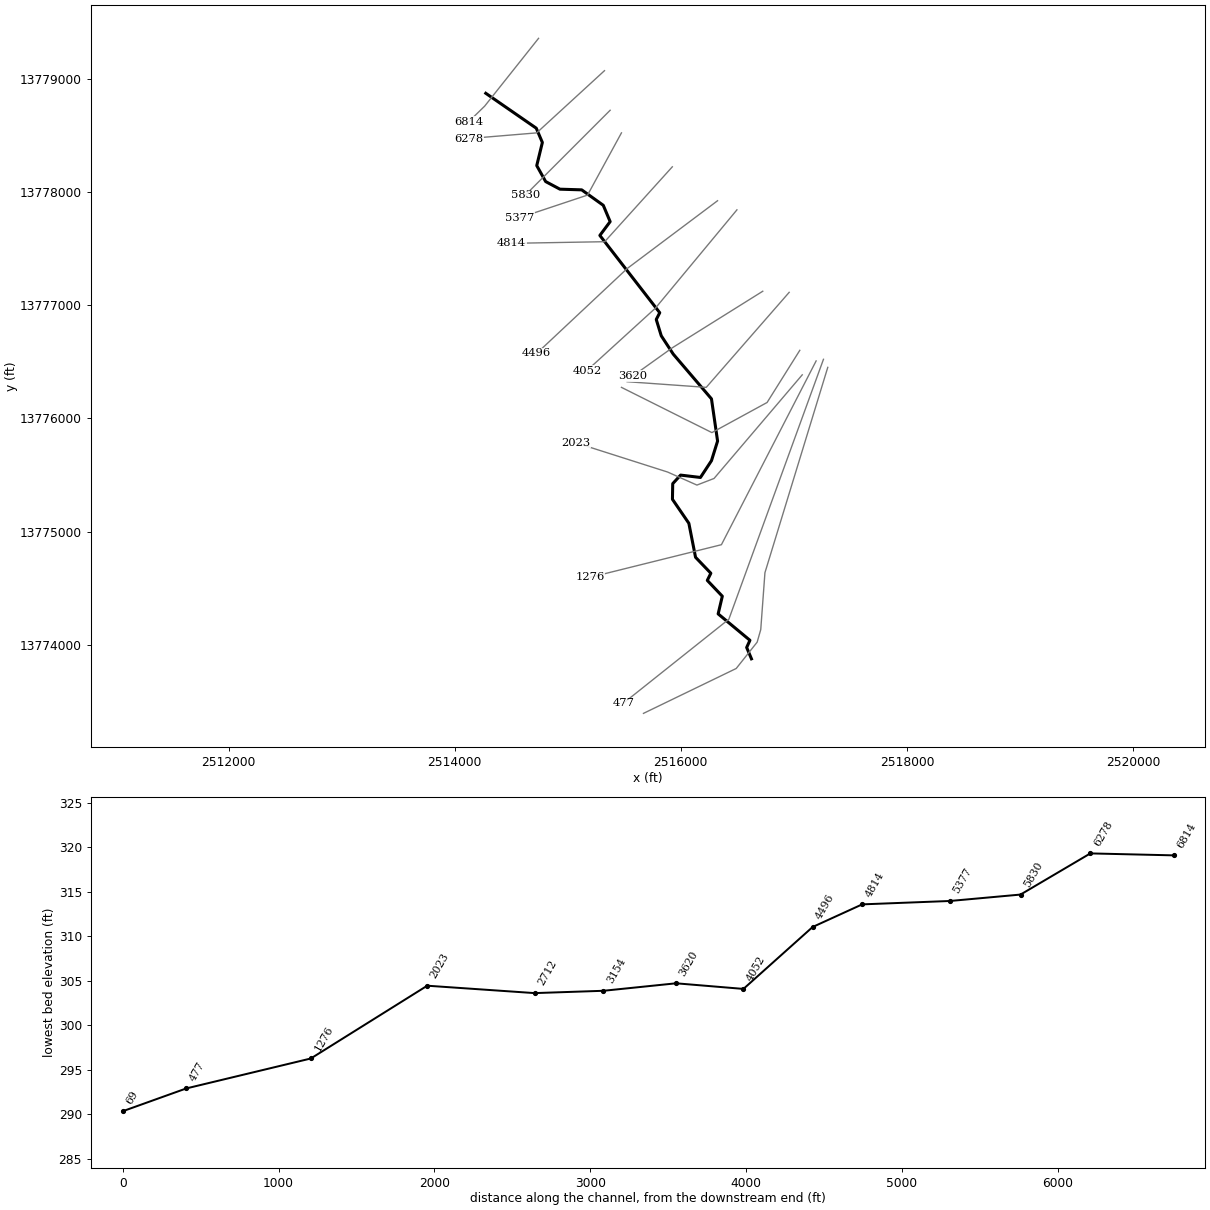
--- Stream0366.prj (project) ---

Proj Title=Stream0366 Base Level Engineering
Current Plan=p01
Default Exp/Contr=0.3,0.1
English Units
Geom File=g01
Flow File=f01
Plan File=p01
BEGIN DESCRIPTION:
Stream0366
END DESCRIPTION:

--- Stream0366.p01 (plan) ---

Plan Title=Multiple Run
Short Identifier=Multiple
Geom File=g01
Flow File=f01
Subcritical Flow
K Sum by GR= 0
Std Step Tol= 0.01
Critical Tol= 0.01
Num of Std Step Trials= 20
Max Error Tol= 0.3
Flow Tol Ratio= 0.001
Split Flow NTrial= 30
Split Flow Tol= 0.02
Split Flow Ratio= 0.02
Log Output Level= 0
Friction Slope Method= 1
Unsteady Friction Slope Method= 2
Unsteady Bridges Friction Slope Method= 1
Parabolic Critical Depth
Global Vel Dist=  1 , 1 , 1
Global Log Level= 0
CheckData=True
Encroach Param= -1, 0, 0, 0
BEGIN DESCRIPTION:
Multiple Run
END DESCRIPTION:

--- Stream0366.f01 (steady flow) ---

Flow Title=Multiple
Number of Profiles=7
Profile Names=10-year,25-year,50-year,1pct_min,100-year,1pct_plu,500-year
River Rch & RM= Stream0366,Reach-1,6814
     694    1111    1484     961    1917    3824    3163
River Rch & RM= Stream0366,Reach-1,4052
     818    1318    1770    1149    2293    4576    3812
Boundary for River Rch & Prof#=Stream0366,Reach-1,1
Up Type=0
Dn Type=3
Dn Slope=0.005
Boundary for River Rch & Prof#=Stream0366,Reach-1,2
Up Type=0
Dn Type=3
Dn Slope=0.005
Boundary for River Rch & Prof#=Stream0366,Reach-1,3
Up Type=0
Dn Type=3
Dn Slope=0.005
Boundary for River Rch & Prof#=Stream0366,Reach-1,4
Up Type=0
Dn Type=3
Dn Slope=0.005
Boundary for River Rch & Prof#=Stream0366,Reach-1,5
Up Type=0
Dn Type=3
Dn Slope=0.005
Boundary for River Rch & Prof#=Stream0366,Reach-1,6
Up Type=0
Dn Type=3
Dn Slope=0.005
Boundary for River Rch & Prof#=Stream0366,Reach-1,7
Up Type=0
Dn Type=3
Dn Slope=0.005

--- Stream0366.g01 (geometry) ---

Geom Title=Existing Conditions

River Reach=Stream0366,Reach-1
Reach XY= 30
      2514275.00     13778875.00      2514721.50     13778566.54
      2514775.48     13778440.17      2514725.75     13778235.68
      2514804.52     13778094.62      2514930.93     13778027.24
      2515123.45     13778021.25      2515314.25     13777884.70
      2515375.04     13777740.34      2515283.98     13777618.34
      2515813.76     13776935.00      2515782.80     13776875.10
      2515827.15     13776730.90      2515933.16     13776568.95
      2516271.24     13776173.44      2516325.31     13775800.04
      2516271.18     13775626.58      2516173.72     13775478.37
      2515998.24     13775499.31      2515928.53     13775423.56
      2515926.04     13775285.44      2516071.17     13775073.42
      2516130.47     13774772.55      2516265.70     13774631.67
      2516234.30     13774568.33      2516367.20     13774428.42
      2516330.30     13774272.33      2516611.51     13774038.69
      2516582.59     13773975.08      2516625.00     13773875.00

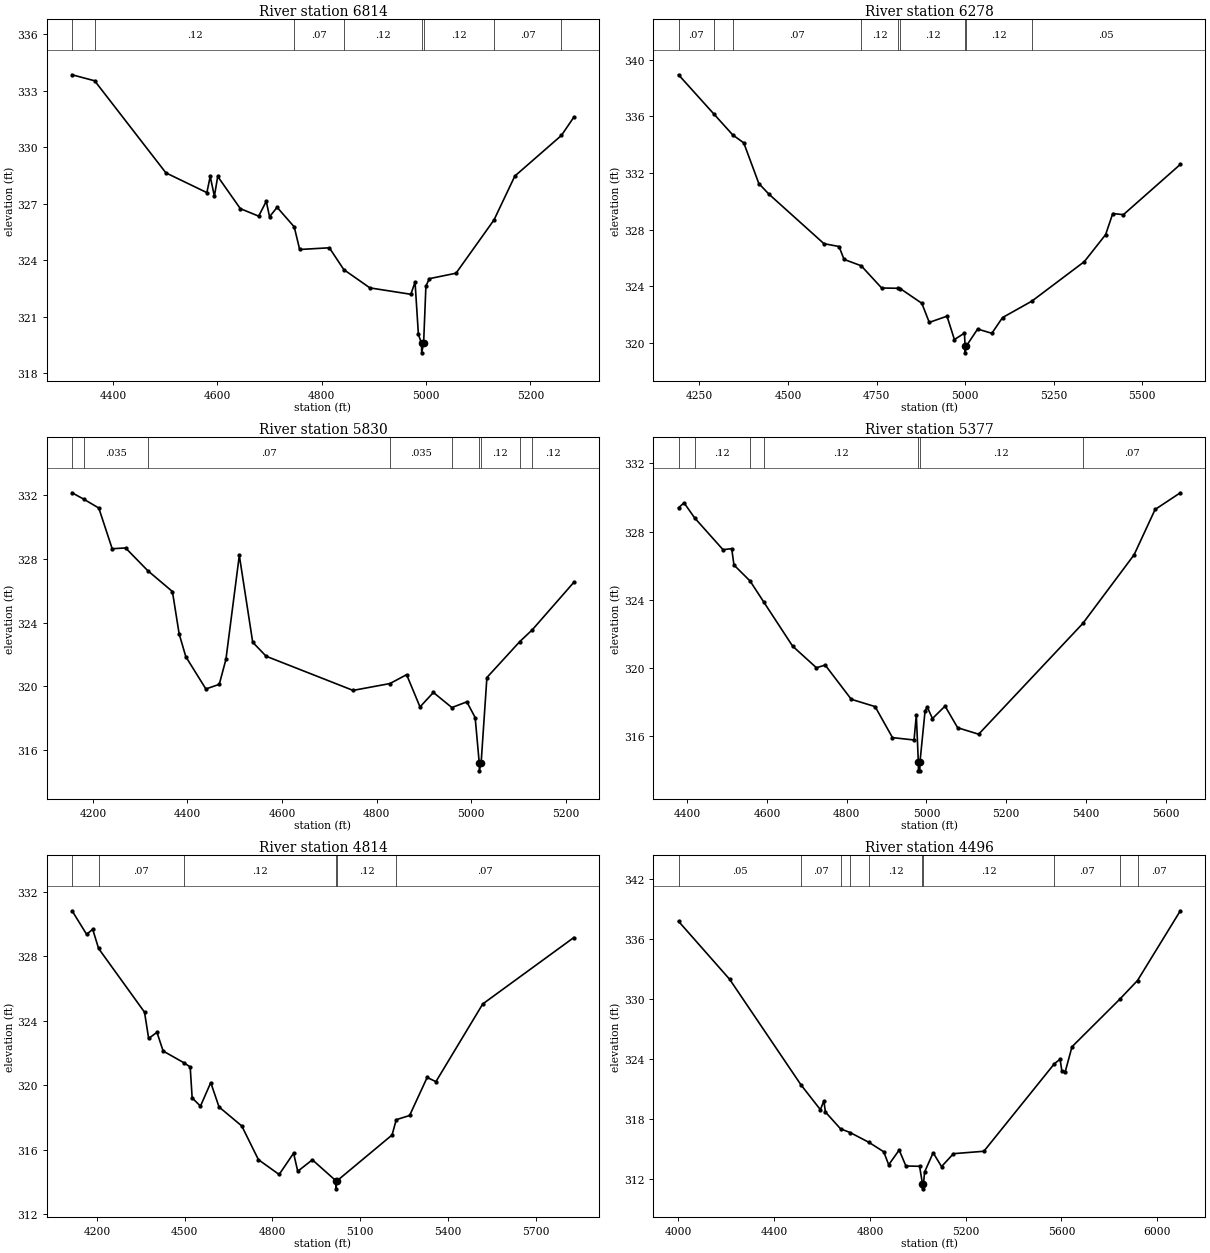
Type RM Length L Ch R = 1,6814,536,536,536
BEGIN DESCRIPTION:
Stream0366 13.0
END DESCRIPTION:
XS GIS Cut Line= 3
      2514741.81     13779360.89      2514265.23     13778761.56
      2514124.97     13778624.97
#Sta/Elev= 30
  4321.7  333.85  4365.0  333.53  4501.5  328.64  4580.0  327.59  4586.4  328.45
  4594.4  327.40  4600.8  328.45  4644.1  326.74  4679.3  326.34  4693.8  327.13
  4700.1  326.31  4714.6  326.81  4747.4  325.77  4757.8  324.57  4814.7  324.66
  4842.4  323.50  4892.4  322.53  4970.9  322.19  4978.9  322.84  4985.3  320.06
  4991.3  319.58  4991.6  319.08  4995.3  319.58  4999.7  322.63  5006.4  323.02
  5057.4  323.31  5130.2  326.14  5170.1  328.47  5259.4  330.63  5283.2  331.60
#Mann=8,-1,0
  4321.7    0.07       0  4365.0    0.12       0  4747.4    0.07       0
  4842.4    0.12       0  4991.3    0.05       0  4995.3    0.12       0
  5130.2    0.07       0  5259.4    0.05       0
Bank Sta=4991.3,4995.3
Exp/Cntr=0.3,0.1

Type RM Length L Ch R = 1,6278,448,448,448
BEGIN DESCRIPTION:
Stream0366 12.0
END DESCRIPTION:
XS GIS Cut Line= 3
      2515325.02     13779075.02      2514725.00     13778525.00
      2514124.95     13778475.00
#Sta/Elev= 30
  4191.3  338.94  4292.1  336.14  4344.4  334.69  4375.4  334.13  4417.9  331.26
  4446.3  330.51  4601.7  327.01  4644.2  326.81  4658.4  325.90  4706.8  325.45
  4764.5  323.88  4811.2  323.86  4817.5  323.83  4877.9  322.80  4898.9  321.45
  4948.9  321.89  4969.8  320.24  4998.2  320.69  4999.9  319.80  5000.1  319.30
  5003.9  319.80  5035.4  320.98  5075.5  320.68  5105.6  321.79  5188.3  322.95
  5336.4  325.74  5396.6  327.65  5416.7  329.14  5446.8  329.06  5607.4  332.61
#Mann=9,-1,0
  4191.3    0.07       0  4292.1   0.035       0  4344.4    0.07       0
  4706.8    0.12       0  4811.2    0.07       0  4817.5    0.12       0
  4999.9    0.05       0  5003.9    0.12       0  5188.3    0.05       0
Bank Sta=4999.9,5003.9
Exp/Cntr=0.3,0.1

Type RM Length L Ch R = 1,5830,453,453,453
BEGIN DESCRIPTION:
Stream0366 11.0
END DESCRIPTION:
XS GIS Cut Line= 3
      2515374.98     13778724.98      2514775.00     13778125.00
      2514625.03     13777975.03
#Sta/Elev= 30
  4156.1  332.17  4180.7  331.77  4212.6  331.21  4240.9  328.65  4269.2  328.70
  4316.1  327.27  4368.2  325.96  4382.4  323.30  4396.5  321.86  4438.9  319.83
  4467.2  320.12  4481.3  321.69  4509.6  328.23  4537.9  322.77  4566.2  321.89
  4750.0  319.74  4828.0  320.17  4863.2  320.73  4891.5  318.70  4919.8  319.61
  4958.9  318.66  4990.5  319.02  5008.1  318.03  5016.7  315.18  5017.0  314.68
  5020.7  315.18  5032.9  320.55  5102.1  322.80  5128.8  323.55  5216.7  326.54
#Mann=9,-1,0
  4156.1    0.07       0  4180.7   0.035       0  4316.1    0.07       0
  4828.0   0.035       0  4958.9    0.12       0  5016.7    0.05       0
  5020.7    0.12       0  5102.1   0.035       0  5128.8    0.12       0
Bank Sta=5016.7,5020.7
Exp/Cntr=0.3,0.1

Type RM Length L Ch R = 1,5377,563,563,563
BEGIN DESCRIPTION:
Stream0366 10.0
END DESCRIPTION:
XS GIS Cut Line= 3
      2515475.01     13778525.03      2515175.00     13777975.00
      2514574.99     13777775.00
#Sta/Elev= 30
  4378.1  329.40  4391.9  329.69  4418.7  328.80  4489.7  326.94  4511.5  327.00
  4517.2  326.04  4557.7  325.10  4591.6  323.88  4664.3  321.28  4724.1  320.01
  4746.0  320.17  4811.5  318.16  4871.3  317.73  4914.9  315.91  4969.0  315.77
  4974.7  317.23  4979.8  314.46  4980.1  313.96  4983.6  313.96  4983.8  314.46
  4996.6  317.46  5001.8  317.72  5015.2  317.03  5046.8  317.76  5078.4  316.49
  5131.1  316.11  5392.4  322.61  5521.1  326.64  5573.8  329.30  5637.1  330.28
#Mann=7,-1,0
  4378.1    0.07       0  4418.7    0.12       0  4557.7    0.07       0
  4591.6    0.12       0  4979.8    0.05       0  4983.8    0.12       0
  5392.4    0.07       0
Bank Sta=4979.8,4983.8
Exp/Cntr=0.3,0.1

Type RM Length L Ch R = 1,4814,318,318,318
BEGIN DESCRIPTION:
Stream0366 9.0
END DESCRIPTION:
XS GIS Cut Line= 3
      2515925.00     13778225.00      2515326.70     13777562.89
      2514503.52     13777548.45
#Sta/Elev= 30
  4115.0  330.83  4164.7  329.37  4185.6  329.68  4205.7  328.49  4362.7  324.54
  4376.9  322.91  4405.3  323.29  4426.3  322.13  4497.5  321.40  4518.9  321.14
  4525.6  319.22  4554.0  318.71  4589.2  320.17  4617.5  318.66  4695.3  317.48
  4752.1  315.39  4823.0  314.47  4872.4  315.79  4886.6  314.67  4936.6  315.38
  5017.1  314.08  5017.3  313.58  5021.1  314.08  5209.1  316.92  5223.5  317.87
  5269.1  318.13  5329.1  320.49  5359.1  320.23  5519.2  325.05  5830.7  329.17
#Mann=6,-1,0
  4115.0    0.12       0  4205.7    0.07       0  4497.5    0.12       0
  5017.1    0.05       0  5021.1    0.12       0  5223.5    0.07       0
Bank Sta=5017.1,5021.1
Exp/Cntr=0.3,0.1

Type RM Length L Ch R = 1,4496,444,444,444
BEGIN DESCRIPTION:
Stream0366 8.0
END DESCRIPTION:
XS GIS Cut Line= 3
      2516325.01     13777925.01      2515525.00     13777325.00
      2514725.00     13776575.00
#Sta/Elev= 30
  4000.2  337.74  4213.8  331.95  4512.0  321.41  4592.9  318.94  4607.5  319.82
  4613.8  318.71  4677.1  317.03  4717.0  316.66  4795.8  315.68  4857.5  314.74
  4878.3  313.44  4922.1  314.91  4950.2  313.32  5007.3  313.29  5019.4  311.54
  5019.7  311.04  5023.6  311.54  5028.3  312.72  5064.0  314.64  5099.1  313.26
  5148.9  314.55  5276.0  314.79  5571.0  323.54  5594.4  323.97  5601.7  322.83
  5615.9  322.73  5644.2  325.22  5844.8  329.99  5917.9  331.83  6096.8  338.79
#Mann=10,-1,0
  4000.2    0.05       0  4512.0    0.07       0  4677.1    0.12       0
  4717.0    0.07       0  4795.8    0.12       0  5019.4    0.05       0
  5023.6    0.12       0  5571.0    0.07       0  5844.8    0.12       0
  5917.9    0.07       0
Bank Sta=5019.4,5023.6
Exp/Cntr=0.3,0.1

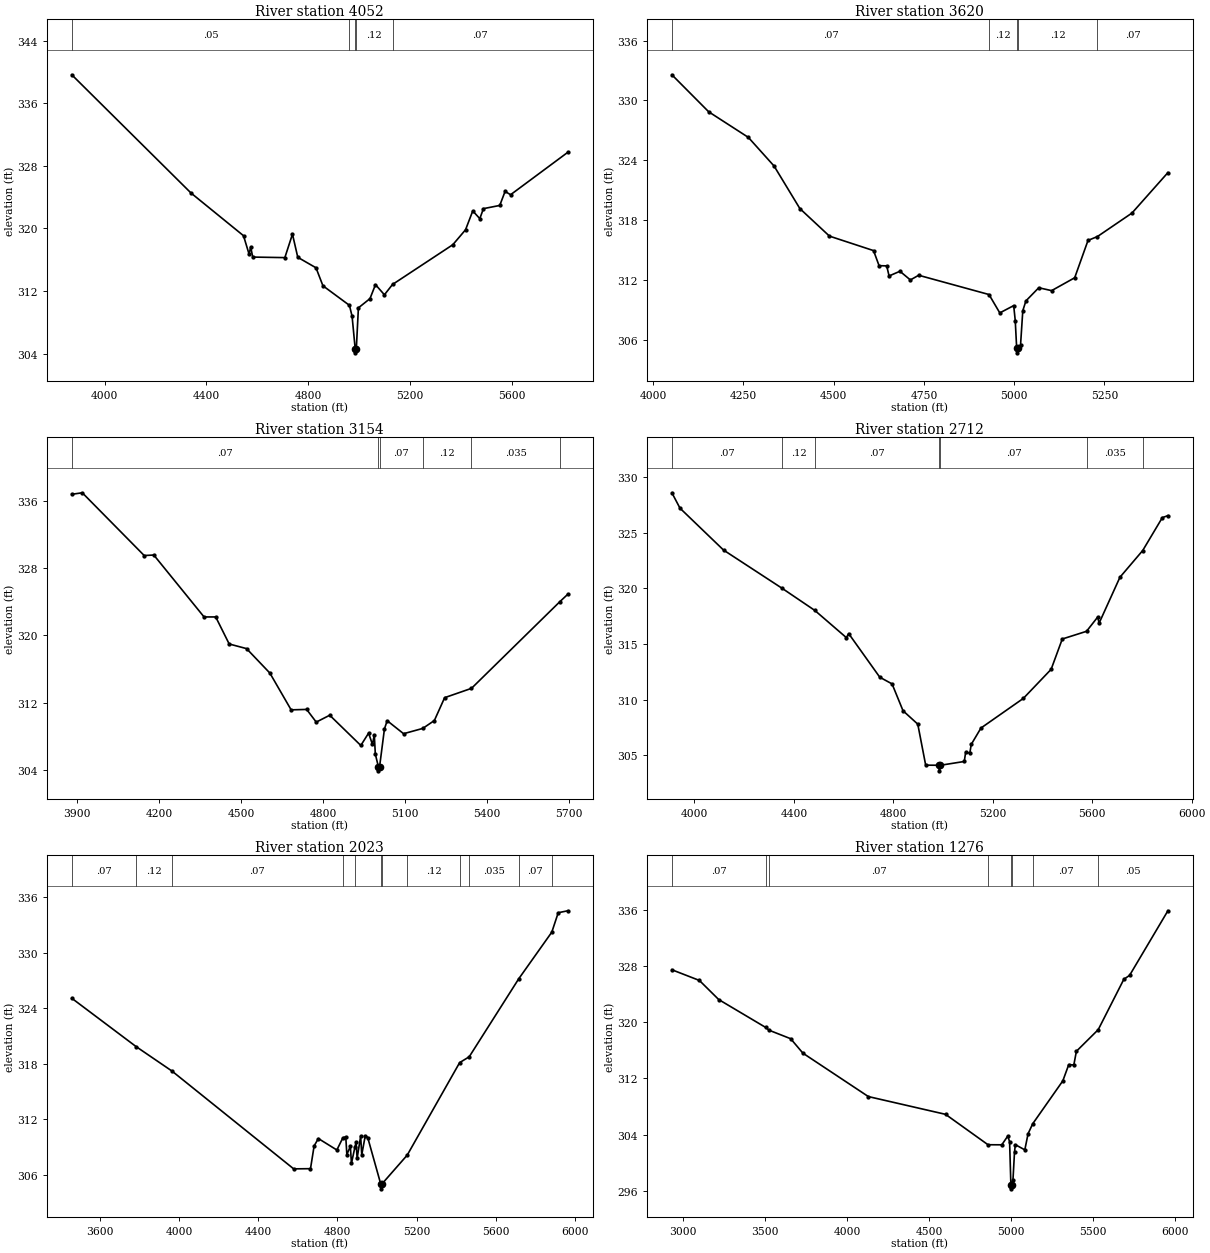
Type RM Length L Ch R = 1,4052,432,432,432
BEGIN DESCRIPTION:
Stream0366 7.0
END DESCRIPTION:
XS GIS Cut Line= 3
      2516496.46     13777844.49      2515775.00     13776975.00
      2515168.94     13776423.00
#Sta/Elev= 30
  3870.5  339.63  4339.4  324.51  4545.5  319.06  4567.3  316.71  4573.8  317.61
  4581.7  316.33  4708.0  316.26  4737.9  319.26  4758.8  316.30  4830.4  314.96
  4857.7  312.66  4961.9  310.16  4972.3  308.76  4984.5  304.59  4984.8  304.09
  4988.9  304.59  4997.1  309.84  5042.6  311.02  5064.2  312.81  5099.3  311.51
  5131.2  312.83  5368.2  317.91  5418.2  319.82  5446.6  322.23  5474.3  321.24
  5488.5  322.52  5552.7  322.93  5573.6  324.72  5595.3  324.30  5820.1  329.72
#Mann=5,-1,0
  3870.5    0.05       0  4961.9    0.12       0  4984.5    0.05       0
  4988.9    0.12       0  5131.2    0.07       0
Bank Sta=4984.5,4988.9
Exp/Cntr=0.3,0.1

Type RM Length L Ch R = 1,3620,466,466,466
BEGIN DESCRIPTION:
Stream0366 6.0
END DESCRIPTION:
XS GIS Cut Line= 3
      2516724.99     13777125.00      2515925.00     13776625.00
      2515575.01     13776375.00
#Sta/Elev= 30
  4052.1  332.57  4154.1  328.86  4263.8  326.30  4335.1  323.43  4406.5  319.17
  4488.4  316.41  4610.5  314.96  4625.8  313.45  4647.0  313.43  4653.5  312.42
  4683.6  312.89  4712.5  312.02  4735.5  312.49  4930.2  310.56  4960.1  308.72
  4998.6  309.45  5002.9  307.95  5006.8  305.22  5007.1  304.72  5011.2  305.22
  5017.6  305.52  5023.8  308.94  5032.4  309.92  5068.0  311.24  5103.6  310.95
  5167.5  312.24  5204.4  315.98  5230.6  316.37  5326.1  318.72  5425.6  322.77
#Mann=5,-1,0
  4052.1    0.07       0  4930.2    0.12       0  5006.8    0.05       0
  5011.2    0.12       0  5230.6    0.07       0
Bank Sta=5006.8,5011.2
Exp/Cntr=0.3,0.1

Type RM Length L Ch R = 1,3154,442,442,442
BEGIN DESCRIPTION:
Stream0366 5.0
END DESCRIPTION:
XS GIS Cut Line= 3
      2516958.61     13777115.19      2516225.00     13776275.00
      2515524.98     13776325.00
#Sta/Elev= 30
  3879.7  336.80  3918.2  336.98  4145.0  329.51  4180.2  329.57  4364.3  322.20
  4407.0  322.20  4456.4  318.98  4520.0  318.43  4605.4  315.52  4683.3  311.14
  4740.2  311.19  4775.3  309.68  4824.7  310.50  4938.6  306.90  4967.1  308.37
  4981.3  307.02  4988.0  308.15  4991.8  305.87  5002.9  304.38  5003.2  303.88
  5007.4  304.38  5025.2  308.87  5035.2  309.85  5095.3  308.30  5165.6  308.93
  5208.1  309.87  5245.7  312.59  5344.1  313.70  5667.3  324.00  5696.9  324.90
#Mann=6,-1,0
  3879.7    0.07       0  5002.9    0.05       0  5007.4    0.07       0
  5165.6    0.12       0  5344.1   0.035       0  5667.3    0.07       0
Bank Sta=5002.9,5007.4
Exp/Cntr=0.3,0.1

Type RM Length L Ch R = 1,2712,689,689,689
BEGIN DESCRIPTION:
Stream0366 4.0
END DESCRIPTION:
XS GIS Cut Line= 4
      2517052.51     13776602.55      2516763.17     13776141.27
      2516275.00     13775875.00      2515475.00     13776275.00
#Sta/Elev= 30
  3909.4  328.57  3941.9  327.19  4117.1  323.43  4353.3  319.99  4484.5  318.01
  4611.3  315.57  4620.3  315.94  4745.6  312.02  4795.0  311.42  4839.1  309.01
  4898.4  307.81  4930.2  304.13  4984.9  304.12  4985.2  303.62  4989.4  304.12
  5085.4  304.46  5091.0  305.29  5107.8  305.22  5113.4  305.99  5152.5  307.46
  5323.0  310.12  5434.8  312.73  5479.6  315.45  5577.1  316.14  5622.1  317.42
  5627.7  316.87  5711.5  320.99  5803.1  323.39  5882.0  326.34  5904.4  326.52
#Mann=7,-1,0
  3909.4    0.07       0  4353.3    0.12       0  4484.5    0.07       0
  4984.9    0.05       0  4989.4    0.07       0  5577.1   0.035       0
  5803.1    0.07       0
Bank Sta=4984.9,4989.4
Exp/Cntr=0.3,0.1

Type RM Length L Ch R = 1,2023,747,747,747
BEGIN DESCRIPTION:
Stream0366 3.0
END DESCRIPTION:
XS GIS Cut Line= 5
      2517074.14     13776385.89      2516294.00     13775469.61
      2516142.66     13775411.08      2515882.71     13775526.61
      2515068.37     13775786.04
#Sta/Elev= 30
  3458.2  325.06  3783.8  319.82  3964.0  317.19  4578.8  306.61  4663.7  306.63
  4682.0  309.09  4703.4  309.89  4796.8  308.65  4826.9  309.96  4841.8  310.08
  4847.3  308.16  4865.0  309.04  4870.5  307.21  4888.6  309.01  4893.8  309.48
  4899.2  307.75  4917.0  310.15  4922.5  308.13  4940.3  310.20  4952.6  310.00
  5018.7  304.95  5019.0  304.45  5023.3  304.95  5152.3  308.10  5416.9  318.10
  5465.2  318.73  5714.8  327.15  5882.3  332.21  5914.7  334.31  5963.0  334.52
#Mann=12,-1,0
  3458.2    0.07       0  3783.8    0.12       0  3964.0    0.07       0
  4826.9    0.12       0  4888.6    0.07       0  5018.7    0.05       0
  5023.3    0.07       0  5152.3    0.12       0  5416.9    0.07       0
  5465.2   0.035       0  5714.8    0.07       0  5882.3   0.035       0
Bank Sta=5018.7,5023.3
Exp/Cntr=0.3,0.1

Type RM Length L Ch R = 1,1276,799,799,799
BEGIN DESCRIPTION:
Stream0366 2.0
END DESCRIPTION:
XS GIS Cut Line= 3
      2517196.92     13776508.68      2516359.28     13774883.95
      2515198.32     13774595.52
#Sta/Elev= 30
  2930.3  327.48  3097.9  325.96  3215.7  323.24  3501.9  319.27  3522.8  318.87
  3654.5  317.66  3729.3  315.60  4128.2  309.42  4598.9  306.89  4857.7  302.56
  4941.8  302.55  4978.0  303.79  4989.3  303.00  4997.3  296.78  4997.6  296.28
  5002.1  296.78  5010.0  297.58  5019.3  301.52  5024.4  302.57  5082.1  301.83
  5102.0  304.13  5130.4  305.55  5313.9  311.66  5350.0  313.97  5380.9  313.92
  5396.6  315.87  5529.7  318.95  5686.0  326.13  5720.9  326.68  5954.5  335.88
#Mann=8,-1,0
  2930.3    0.07       0  3501.9    0.12       0  3522.8    0.07       0
  4857.7    0.12       0  4997.3    0.05       0  5002.1    0.12       0
  5130.4    0.07       0  5529.7    0.05       0
Bank Sta=4997.3,5002.1
Exp/Cntr=0.3,0.1

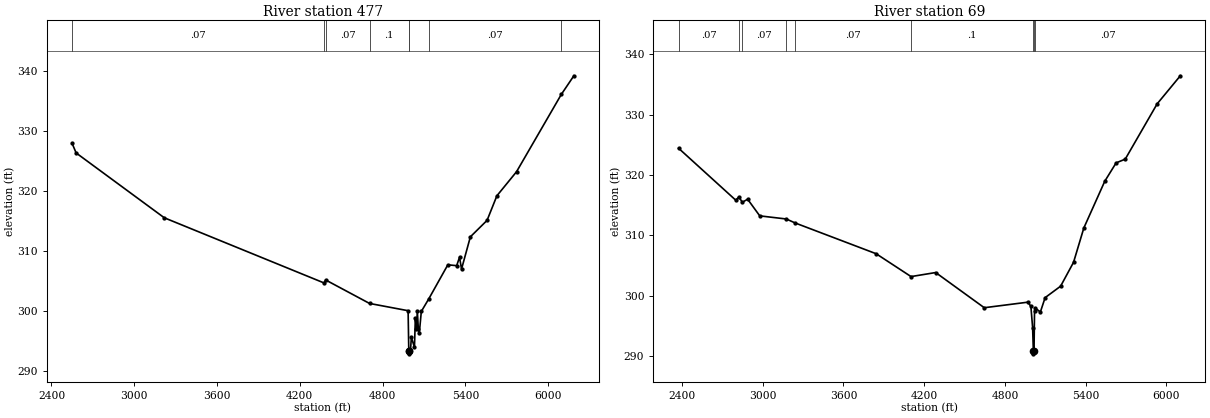
Type RM Length L Ch R = 1,477,408,408,408
BEGIN DESCRIPTION:
Stream0366 1.0
END DESCRIPTION:
XS GIS Cut Line= 3
      2517261.88     13776523.06      2516425.00     13774225.00
      2515492.78     13773483.11
#Sta/Elev= 30
  2549.3  327.97  2578.9  326.36  3217.7  315.57  4375.8  304.72  4387.2  305.22
  4705.4  301.31  4985.0  300.10  4989.9  293.42  4990.2  292.92  4994.8  293.42
  5002.2  293.48  5008.6  295.68  5031.0  293.99  5037.4  298.81  5045.5  297.11
  5051.9  300.06  5058.9  297.12  5066.3  296.41  5080.7  299.98  5134.0  302.04
  5272.9  307.74  5337.0  307.60  5357.8  309.01  5372.2  307.03  5436.3  312.40
  5557.3  315.14  5628.5  319.23  5771.0  323.24  6095.5  336.11  6186.4  339.21
#Mann=8,-1,0
  2549.3    0.07       0  4375.8     0.1       0  4387.2    0.07       0
  4705.4     0.1       0  4989.9    0.05       0  4994.8     0.1       0
  5134.0    0.07       0  6095.5    0.05       0
Bank Sta=4989.9,4994.8
Exp/Cntr=0.3,0.1

Type RM Length L Ch R = 1,69,0,0,0
BEGIN DESCRIPTION:
E20920
END DESCRIPTION:
XS GIS Cut Line= 6
      2517299.92     13776451.79      2516744.18     13774636.38
      2516707.14     13774133.57      2516675.38     13774022.43
      2516490.13     13773789.55      2515669.91     13773392.66
#Sta/Elev= 30
  2375.6  324.43  2801.0  315.81  2824.0  316.36  2849.5  315.47  2888.8  315.98
  2978.8  313.22  3176.7  312.70  3241.0  312.05  3843.0  306.95  4102.6  303.16
  4285.6  303.83  4646.5  298.00  4970.3  298.92  4992.7  298.23  5005.6  294.70
  5011.1  290.86  5011.4  290.36  5016.0  290.86  5019.9  297.45  5026.0  297.93
  5063.2  297.29  5098.4  299.67  5213.6  301.57  5309.6  305.53  5386.1  311.22
  5541.6  318.96  5625.8  322.00  5693.6  322.62  5930.6  331.78  6102.7  336.43
#Mann=9,-1,0
  2375.6    0.07       0  2824.0    0.12       0  2849.5    0.07       0
  3176.7     0.1       0  3241.0    0.07       0  4102.6     0.1       0
  5011.1    0.05       0  5016.0     0.1       0  5026.0    0.07       0
Bank Sta=5011.1,5016
Exp/Cntr=0.3,0.1

Chan Stop Cuts=-1