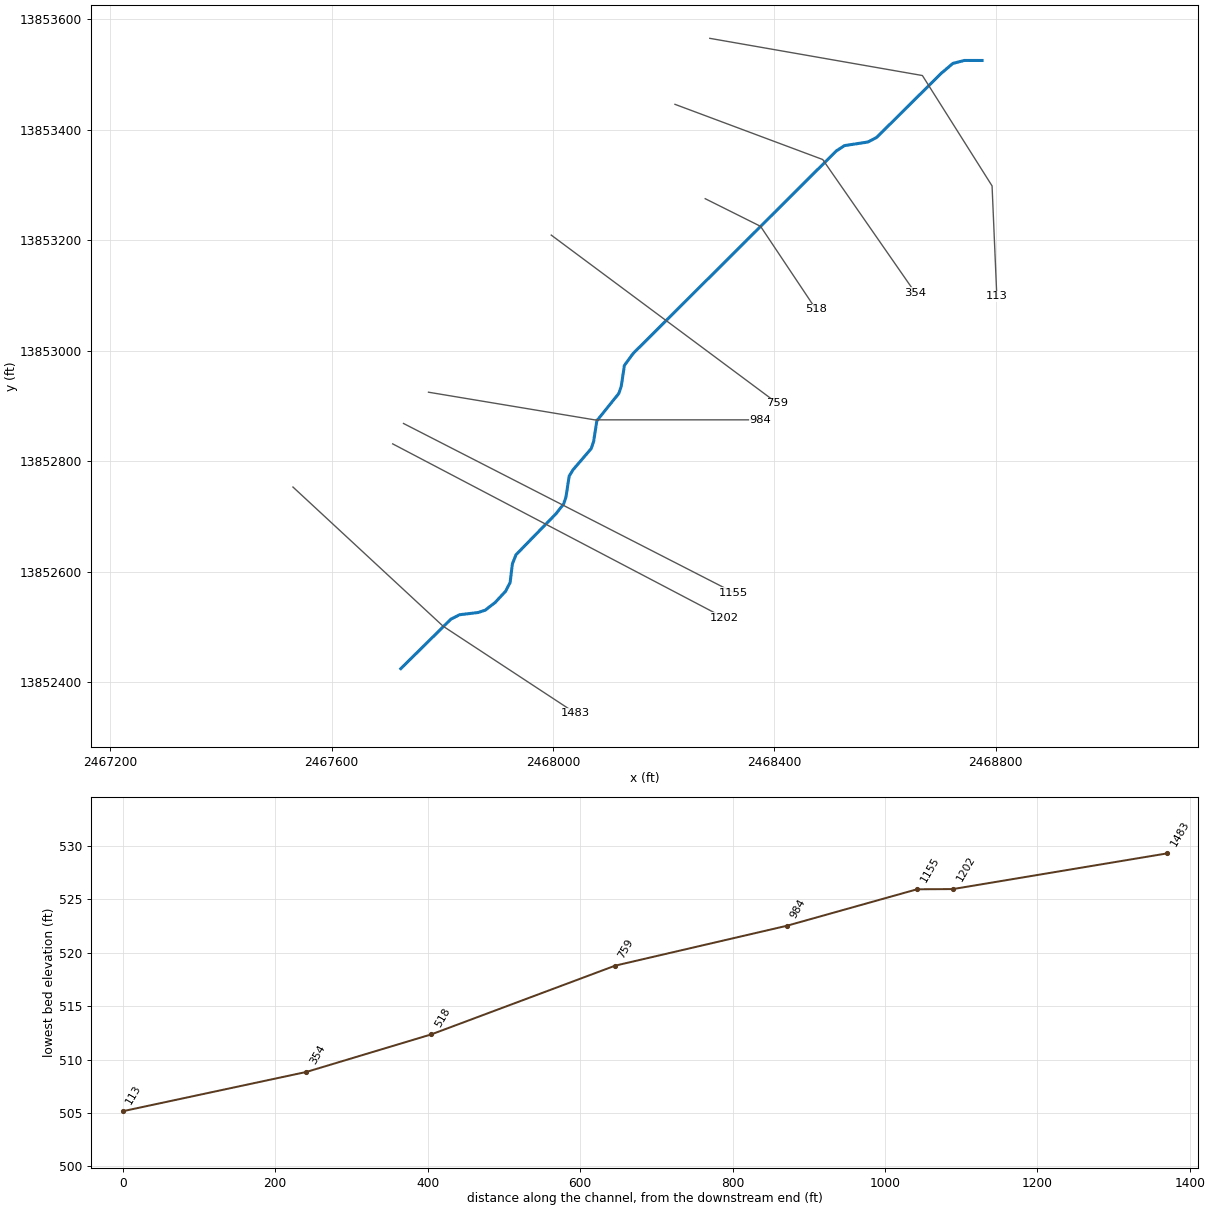
--- Stream0374.prj (project) ---

Proj Title=Stream0374 Base Level Engineering
Current Plan=p01
Default Exp/Contr=0.3,0.1
English Units
Geom File=g01
Flow File=f01
Plan File=p01
BEGIN DESCRIPTION:
Stream0374
END DESCRIPTION:

--- Stream0374.p01 (plan) ---

Plan Title=Multiple Run
Short Identifier=Multiple
Geom File=g01
Flow File=f01
Subcritical Flow
K Sum by GR= 0
Std Step Tol= 0.01
Critical Tol= 0.01
Num of Std Step Trials= 20
Max Error Tol= 0.3
Flow Tol Ratio= 0.001
Split Flow NTrial= 30
Split Flow Tol= 0.02
Split Flow Ratio= 0.02
Log Output Level= 0
Friction Slope Method= 1
Unsteady Friction Slope Method= 2
Unsteady Bridges Friction Slope Method= 1
Parabolic Critical Depth
Global Vel Dist=  1 , 1 , 1
Global Log Level= 0
CheckData=True
Encroach Param= -1, 0, 0, 0
BEGIN DESCRIPTION:
Multiple Run
END DESCRIPTION:

--- Stream0374.f01 (steady flow) ---

Flow Title=Multiple
Number of Profiles=7
Profile Names=10-year,25-year,50-year,1pct_min,100-year,1pct_plu,500-year
River Rch & RM= Stream0374,Reach-1,1483
     465     742     991     643    1283    2560    2125
Boundary for River Rch & Prof#=Stream0374,Reach-1,1
Up Type=0
Dn Type=3
Dn Slope=0.005
Boundary for River Rch & Prof#=Stream0374,Reach-1,2
Up Type=0
Dn Type=3
Dn Slope=0.005
Boundary for River Rch & Prof#=Stream0374,Reach-1,3
Up Type=0
Dn Type=3
Dn Slope=0.005
Boundary for River Rch & Prof#=Stream0374,Reach-1,4
Up Type=0
Dn Type=3
Dn Slope=0.005
Boundary for River Rch & Prof#=Stream0374,Reach-1,5
Up Type=0
Dn Type=3
Dn Slope=0.005
Boundary for River Rch & Prof#=Stream0374,Reach-1,6
Up Type=0
Dn Type=3
Dn Slope=0.005
Boundary for River Rch & Prof#=Stream0374,Reach-1,7
Up Type=0
Dn Type=3
Dn Slope=0.005

--- Stream0374.g01 (geometry) ---

Geom Title=Existing Conditions

River Reach=Stream0374,Reach-1
Reach XY= 30
      2467725.00     13852425.00      2467815.31     13852514.28
      2467831.08     13852522.46      2467864.52     13852526.47
      2467877.54     13852530.74      2467895.47     13852544.63
      2467914.35     13852565.00      2467922.54     13852580.87
      2467926.57     13852614.31      2467933.18     13852631.02
      2468005.18     13852704.93      2468019.15     13852722.71
      2468023.49     13852735.63      2468029.19     13852773.26
      2468036.10     13852784.54      2468068.92     13852822.80
      2468073.35     13852835.69      2468079.16     13852873.28
      2468118.90     13852922.81      2468123.30     13852935.70
      2468128.95     13852973.37      2468144.78     13852995.09
      2468511.79     13853361.37      2468526.65     13853371.02
      2468568.95     13853377.53      2468584.68     13853385.78
      2468701.55     13853501.96      2468722.48     13853519.69
      2468743.12     13853525.07      2468775.00     13853525.00

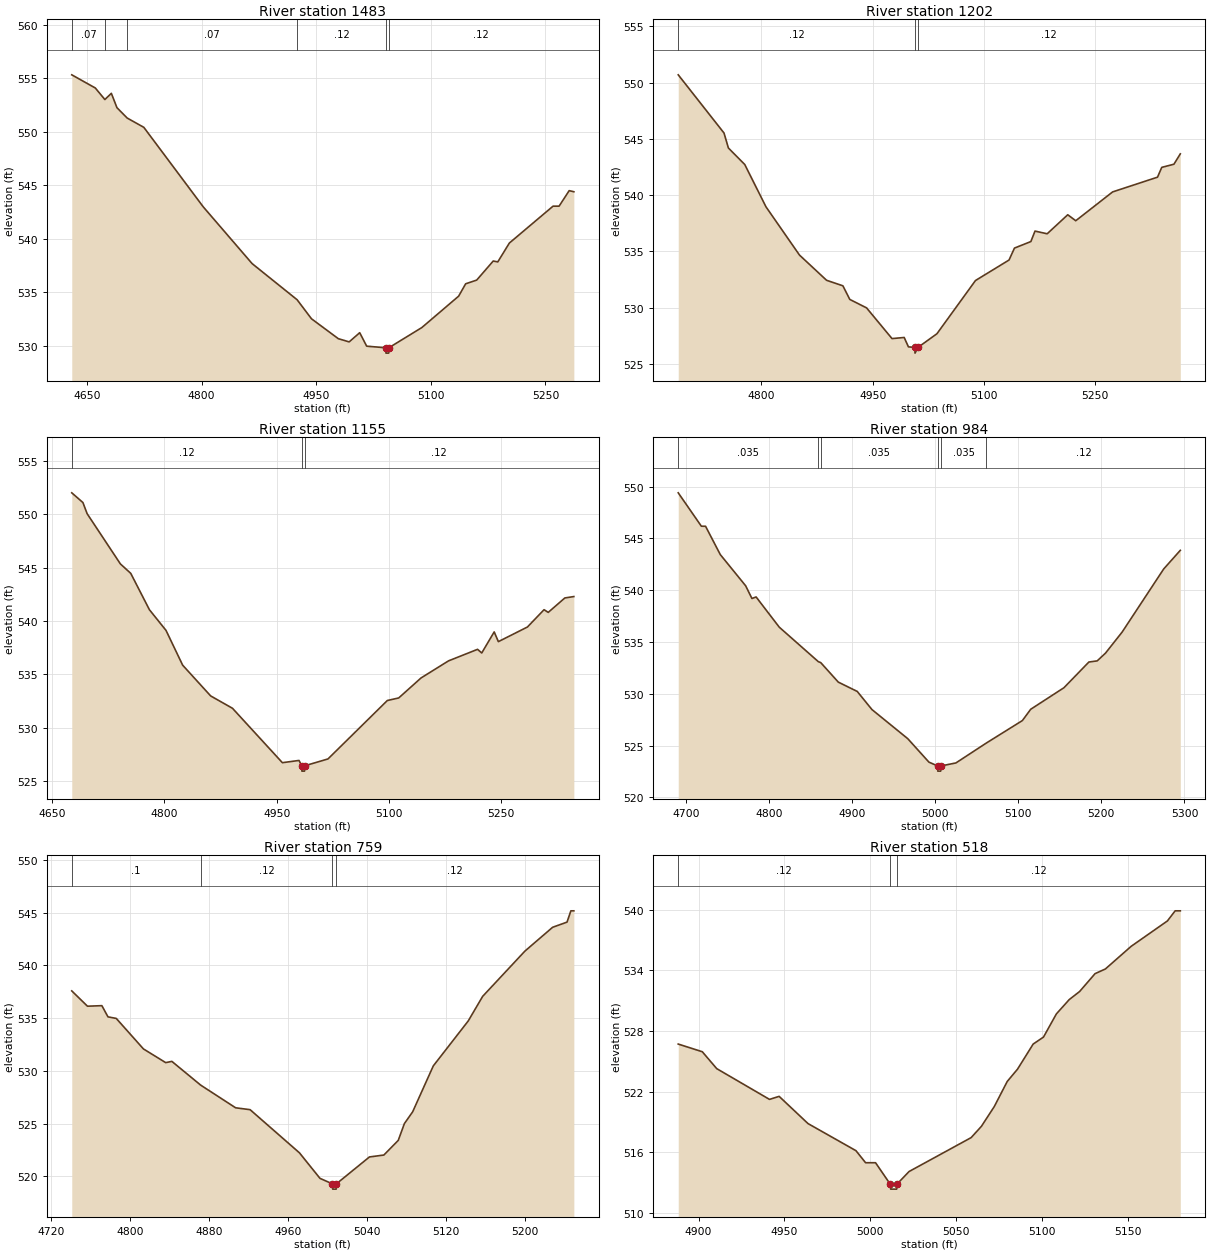
Type RM Length L Ch R = 1,1483,281,281,281
BEGIN DESCRIPTION:
Stream0374 3.0
END DESCRIPTION:
XS GIS Cut Line= 3
      2467530.17     13852753.46      2467801.48     13852501.69
      2468041.16     13852344.06
#Sta/Elev= 30
  4630.1  555.33  4660.9  554.10  4673.4  553.02  4681.9  553.60  4689.2  552.26
  4702.6  551.29  4724.4  550.42  4802.1  542.99  4866.1  537.68  4925.0  534.30
  4943.8  532.52  4978.9  530.66  4993.1  530.36  5006.9  531.22  5016.0  529.96
  5041.0  529.81  5041.3  529.31  5044.8  529.31  5045.0  529.81  5088.2  531.70
  5136.4  534.64  5145.5  535.79  5160.0  536.14  5181.6  537.92  5187.6  537.84
  5202.7  539.60  5259.9  543.05  5267.8  543.05  5281.0  544.50  5287.1  544.40
#Mann=6,-1,0
  4630.1    0.07       0  4673.4    0.12       0  4702.6    0.07       0
  4925.0    0.12       0  5041.0    0.05       0  5045.0    0.12       0
Bank Sta=5041,5045
Exp/Cntr=0.3,0.1

Type RM Length L Ch R = 1,1202,47,47,47
BEGIN DESCRIPTION:
XS6572
END DESCRIPTION:
XS GIS Cut Line= 2
      2467710.35     13852831.54      2468309.32     13852516.87
#Sta/Elev= 30
  4687.9  550.69  4749.6  545.52  4755.5  544.19  4777.6  542.72  4806.1  538.97
  4851.3  534.68  4887.8  532.44  4909.8  531.95  4919.1  530.74  4941.7  529.99
  4976.0  527.26  4992.4  527.36  4998.1  526.53  5006.8  526.47  5007.0  525.97
  5010.8  526.47  5036.5  527.69  5088.5  532.42  5133.7  534.24  5141.0  535.30
  5163.1  535.88  5168.7  536.81  5185.1  536.57  5212.8  538.26  5223.6  537.73
  5273.3  540.29  5333.8  541.60  5339.5  542.47  5355.9  542.75  5364.5  543.67
#Mann=3,-1,0
  4687.9    0.12       0  5006.8    0.05       0  5010.8    0.12       0
Bank Sta=5006.8,5010.8
Exp/Cntr=0.3,0.1

Type RM Length L Ch R = 1,1155,171,171,171
BEGIN DESCRIPTION:
XS6571
END DESCRIPTION:
XS GIS Cut Line= 2
      2467729.90     13852868.43      2468326.63     13852562.47
#Sta/Elev= 30
  4676.3  552.00  4691.2  551.09  4696.8  550.05  4741.2  545.35  4755.1  544.46
  4780.0  541.06  4802.2  539.12  4824.4  535.87  4861.8  532.99  4891.0  531.83
  4957.6  526.74  4979.8  526.95  4983.5  526.45  4983.7  525.95  4987.2  525.95
  4987.5  526.45  5018.5  527.09  5097.8  532.56  5113.0  532.80  5142.8  534.67
  5179.5  536.27  5218.3  537.35  5223.9  537.01  5240.5  538.98  5246.1  538.07
  5284.9  539.44  5307.1  541.06  5312.7  540.81  5334.9  542.16  5346.9  542.29
#Mann=3,-1,0
  4676.3    0.12       0  4983.5    0.05       0  4987.5    0.12       0
Bank Sta=4983.5,4987.5
Exp/Cntr=0.3,0.1

Type RM Length L Ch R = 1,984,225,225,225
BEGIN DESCRIPTION:
Stream0374 2.0
END DESCRIPTION:
XS GIS Cut Line= 3
      2467775.04     13852924.99      2468075.00     13852875.00
      2468375.00     13852875.00
#Sta/Elev= 30
  4690.9  549.39  4718.7  546.17  4723.8  546.16  4741.5  543.43  4772.0  540.42
  4779.6  539.19  4784.6  539.34  4812.5  536.42  4859.4  533.10  4862.4  533.00
  4883.5  531.12  4906.3  530.22  4924.0  528.47  4967.1  525.66  4992.5  523.40
  5003.0  523.03  5003.2  522.53  5006.7  522.53  5007.0  523.03  5025.0  523.32
  5061.8  525.25  5105.0  527.41  5115.0  528.50  5155.0  530.58  5185.0  533.06
  5195.0  533.17  5205.0  533.92  5225.0  535.95  5275.0  542.04  5295.0  543.84
#Mann=6,-1,0
  4690.9   0.035       0  4859.4    0.12       0  4862.4   0.035       0
  5003.0   0.035       0  5007.0   0.035       0  5061.8    0.12       0
Bank Sta=5003,5007
Exp/Cntr=0.3,0.1

Type RM Length L Ch R = 1,759,241,241,241
BEGIN DESCRIPTION:
XS6570
END DESCRIPTION:
XS GIS Cut Line= 2
      2467996.79     13853209.15      2468404.79     13852905.32
#Sta/Elev= 30
  4741.1  537.59  4757.0  536.14  4771.6  536.19  4777.8  535.13  4786.2  534.98
  4813.7  532.09  4836.3  530.79  4842.5  530.91  4871.7  528.66  4907.1  526.51
  4921.8  526.33  4971.8  522.24  4992.6  519.82  5005.2  519.30  5005.5  518.80
  5009.0  518.80  5009.2  519.30  5042.7  521.85  5057.3  522.03  5071.9  523.42
  5078.1  525.01  5086.5  526.13  5107.4  530.48  5142.8  534.74  5157.4  537.07
  5200.2  541.36  5228.3  543.62  5242.9  544.11  5246.8  545.18  5249.8  545.18
#Mann=4,-1,0
  4741.1     0.1       0  4871.7    0.12       0  5005.2    0.05       0
  5009.2    0.12       0
Bank Sta=5005.2,5009.2
Exp/Cntr=0.3,0.1

Type RM Length L Ch R = 1,518,164,164,164
BEGIN DESCRIPTION:
Stream0374 1.0
END DESCRIPTION:
XS GIS Cut Line= 3
      2468274.99     13853275.00      2468375.00     13853225.00
      2468475.01     13853074.99
#Sta/Elev= 30
  4888.2  526.71  4902.2  525.95  4910.6  524.28  4941.3  521.24  4946.9  521.54
  4963.7  518.85  4991.6  516.17  4997.2  514.98  5003.0  514.98  5011.5  512.87
  5011.8  512.37  5015.3  512.37  5015.5  512.87  5022.5  514.11  5058.6  517.46
  5064.6  518.58  5072.1  520.54  5079.6  523.01  5085.6  524.23  5094.7  526.71
  5100.7  527.40  5108.2  529.69  5115.7  531.11  5121.7  531.90  5130.7  533.67
  5136.7  534.13  5151.7  536.37  5172.8  538.88  5177.3  539.88  5180.3  539.88
#Mann=3,-1,0
  4888.2    0.12       0  5011.5    0.05       0  5015.5    0.12       0
Bank Sta=5011.5,5015.5
Exp/Cntr=0.3,0.1

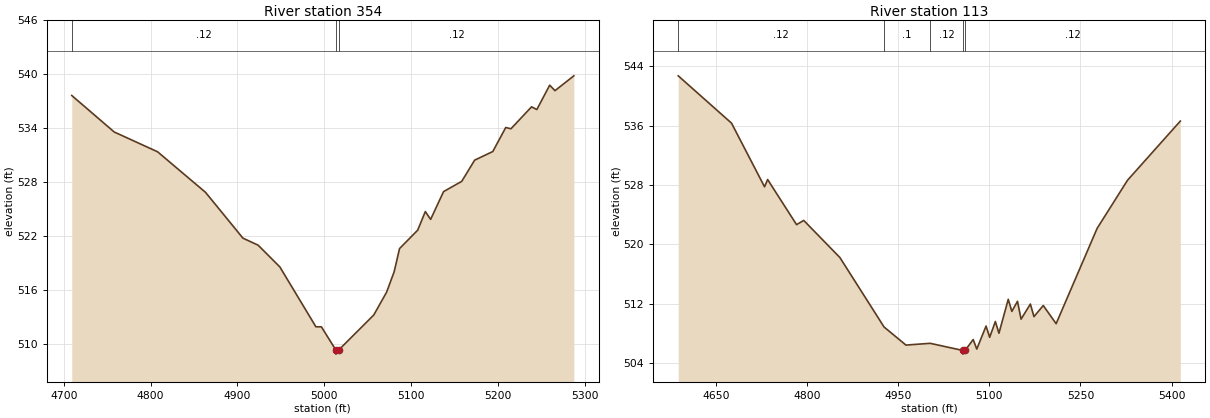
Type RM Length L Ch R = 1,354,241,241,241
BEGIN DESCRIPTION:
XS6569
END DESCRIPTION:
XS GIS Cut Line= 3
      2468220.34     13853445.69      2468487.24     13853345.88
      2468654.33     13853105.01
#Sta/Elev= 30
  4709.2  537.62  4758.1  533.56  4808.0  531.36  4863.2  526.85  4906.3  521.75
  4923.8  520.97  4948.8  518.55  4990.3  511.89  4996.6  511.89  5013.0  509.35
  5013.3  508.85  5017.0  509.35  5056.9  513.20  5071.7  515.74  5080.4  518.01
  5086.6  520.59  5107.5  522.64  5116.3  524.71  5122.4  523.84  5137.3  526.93
  5158.2  528.07  5173.1  530.43  5194.0  531.39  5208.9  534.06  5214.9  533.92
  5238.6  536.36  5244.7  536.06  5259.5  538.77  5265.6  538.16  5287.3  539.81
#Mann=3,-1,0
  4709.2    0.12       0  5013.0    0.05       0  5017.0    0.12       0
Bank Sta=5013,5017
Exp/Cntr=0.3,0.1

Type RM Length L Ch R = 1,113,0,0,0
BEGIN DESCRIPTION:
XS6568
END DESCRIPTION:
XS GIS Cut Line= 4
      2468283.27     13853565.06      2468667.36     13853497.79
      2468793.23     13853298.13      2468801.83     13853098.18
#Sta/Elev= 30
  4588.2  542.74  4675.9  536.35  4730.2  527.76  4735.3  528.74  4782.9  522.65
  4794.7  523.22  4854.2  518.21  4926.9  508.83  4962.9  506.39  5002.7  506.63
  5056.2  505.67  5056.4  505.17  5060.2  505.67  5073.5  507.14  5079.4  505.85
  5094.7  508.96  5100.6  507.44  5110.0  509.57  5115.9  507.99  5131.2  512.57
  5137.1  510.94  5146.4  512.30  5152.3  509.89  5167.6  511.93  5173.5  510.23
  5188.8  511.73  5210.0  509.28  5277.4  522.14  5327.4  528.64  5414.3  536.63
#Mann=5,-1,0
  4588.2    0.12       0  4926.9     0.1       0  5002.7    0.12       0
  5056.2    0.05       0  5060.2    0.12       0
Bank Sta=5056.2,5060.2
Exp/Cntr=0.3,0.1

Chan Stop Cuts=-1