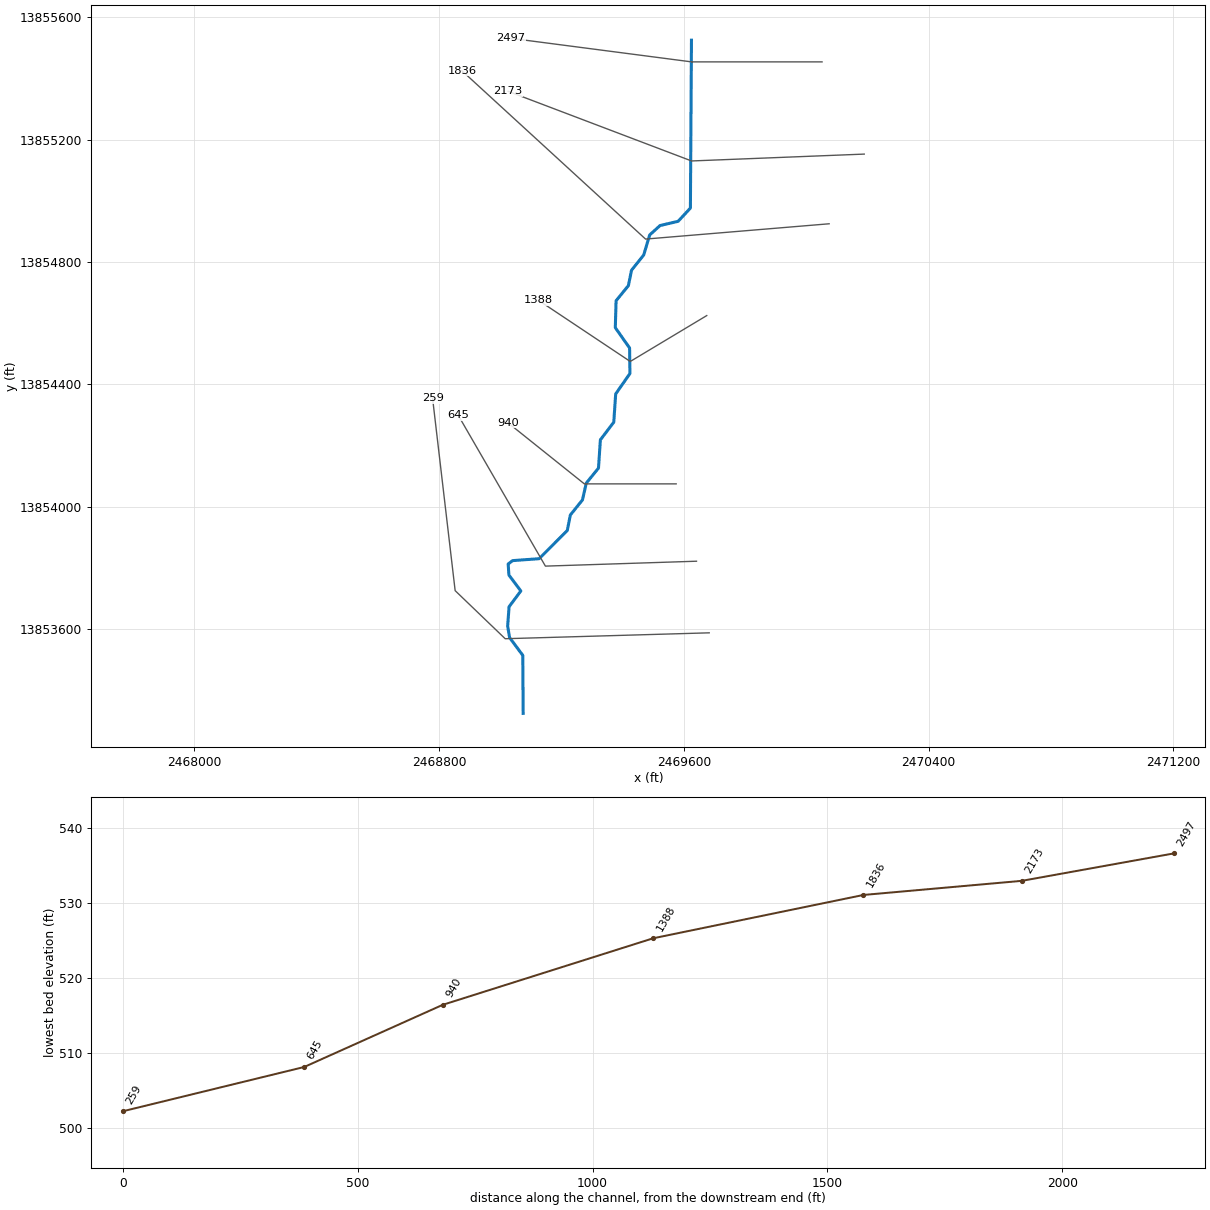
--- Stream0375.prj (project) ---

Proj Title=Stream0375 Base Level Engineering
Current Plan=p01
Default Exp/Contr=0.3,0.1
English Units
Geom File=g01
Flow File=f01
Plan File=p01
BEGIN DESCRIPTION:
Stream0375
END DESCRIPTION:

--- Stream0375.p01 (plan) ---

Plan Title=Multiple Run
Short Identifier=Multiple
Geom File=g01
Flow File=f01
Subcritical Flow
K Sum by GR= 0
Std Step Tol= 0.01
Critical Tol= 0.01
Num of Std Step Trials= 20
Max Error Tol= 0.3
Flow Tol Ratio= 0.001
Split Flow NTrial= 30
Split Flow Tol= 0.02
Split Flow Ratio= 0.02
Log Output Level= 0
Friction Slope Method= 1
Unsteady Friction Slope Method= 2
Unsteady Bridges Friction Slope Method= 1
Parabolic Critical Depth
Global Vel Dist=  1 , 1 , 1
Global Log Level= 0
CheckData=True
Encroach Param= -1, 0, 0, 0
BEGIN DESCRIPTION:
Multiple Run
END DESCRIPTION:

--- Stream0375.f01 (steady flow) ---

Flow Title=Multiple
Number of Profiles=7
Profile Names=10-year,25-year,50-year,1pct_min,100-year,1pct_plu,500-year
River Rch & RM= Stream0375,Reach-1,2497
     169     249     315     195     389     776     583
Boundary for River Rch & Prof#=Stream0375,Reach-1,1
Up Type=0
Dn Type=3
Dn Slope=0.005
Boundary for River Rch & Prof#=Stream0375,Reach-1,2
Up Type=0
Dn Type=3
Dn Slope=0.005
Boundary for River Rch & Prof#=Stream0375,Reach-1,3
Up Type=0
Dn Type=3
Dn Slope=0.005
Boundary for River Rch & Prof#=Stream0375,Reach-1,4
Up Type=0
Dn Type=3
Dn Slope=0.005
Boundary for River Rch & Prof#=Stream0375,Reach-1,5
Up Type=0
Dn Type=3
Dn Slope=0.005
Boundary for River Rch & Prof#=Stream0375,Reach-1,6
Up Type=0
Dn Type=3
Dn Slope=0.005
Boundary for River Rch & Prof#=Stream0375,Reach-1,7
Up Type=0
Dn Type=3
Dn Slope=0.005

--- Stream0375.g01 (geometry) ---

Geom Title=Existing Conditions

River Reach=Stream0375,Reach-1
Reach XY= 30
      2469625.00     13855525.00      2469621.55     13854976.25
      2469581.36     13854933.03      2469522.49     13854919.24
      2469488.48     13854888.56      2469468.89     13854822.84
      2469429.16     13854773.28      2469418.88     13854722.82
      2469378.67     13854673.42      2469376.11     13854585.55
      2469422.83     13854519.03      2469423.90     13854435.55
      2469377.36     13854369.03      2469371.15     13854276.60
      2469327.35     13854219.03      2469321.17     13854126.58
      2469281.12     13854077.18      2469268.92     13854022.80
      2469229.19     13853973.26      2469219.17     13853922.69
      2469127.37     13853830.54      2469040.33     13853824.19
      2469026.10     13853813.26      2469028.39     13853777.08
      2469067.39     13853725.04      2469028.94     13853673.50
      2469024.31     13853609.94      2469030.69     13853572.69
      2469073.79     13853514.50      2469075.00     13853325.00

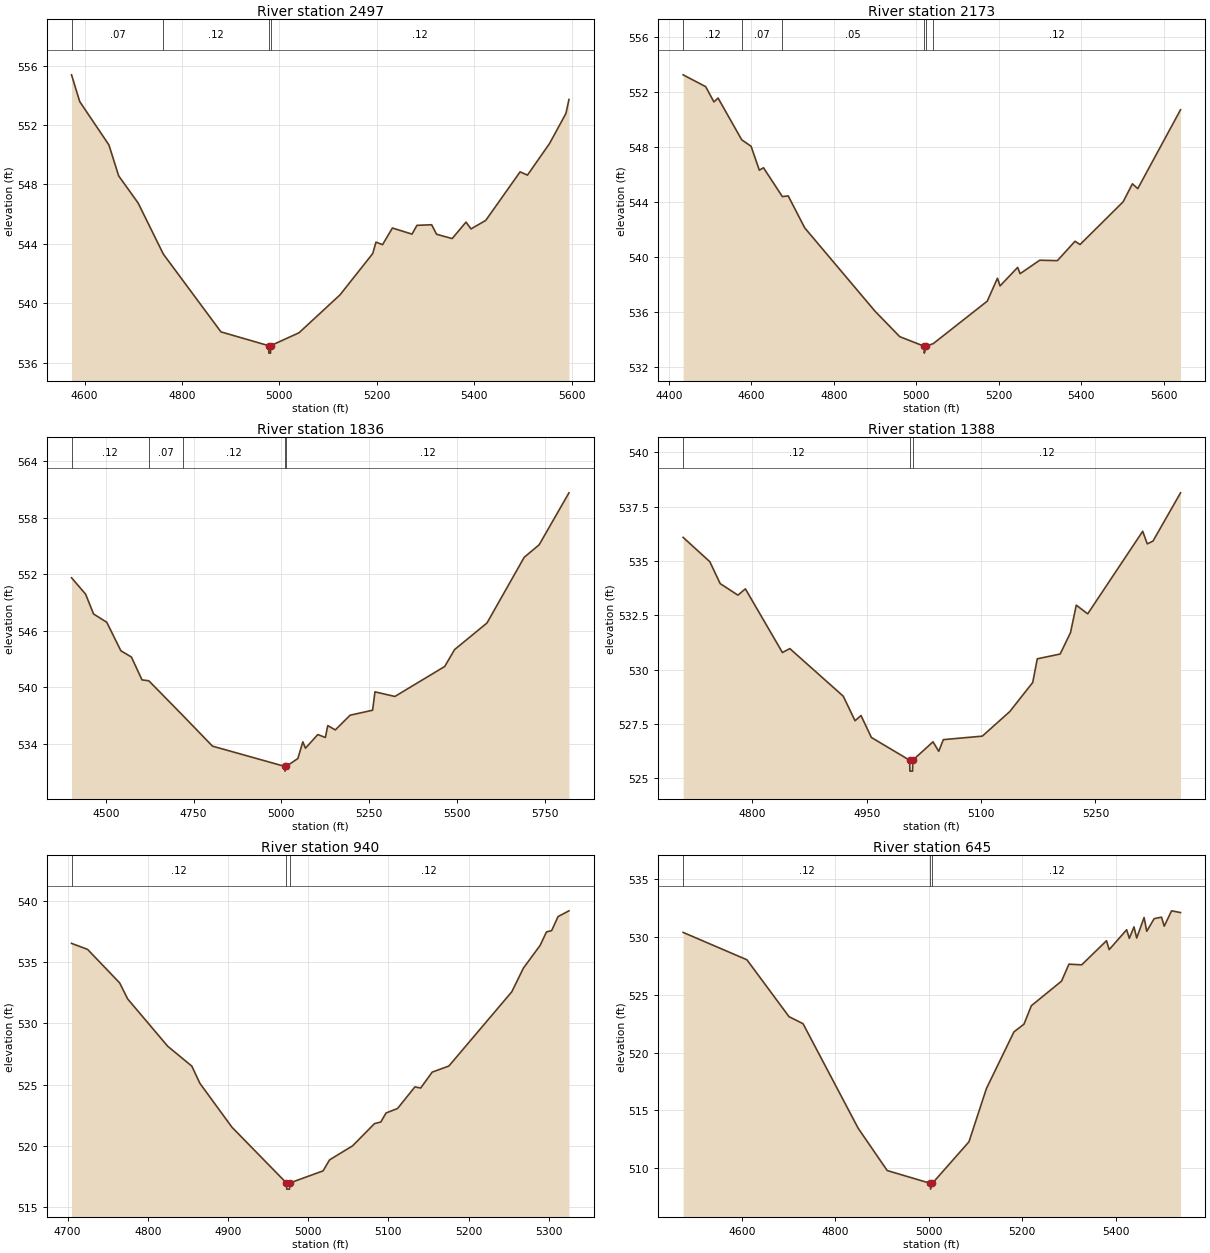
Type RM Length L Ch R = 1,2497,324,324,324
BEGIN DESCRIPTION:
Stream0375 5.0
END DESCRIPTION:
XS GIS Cut Line= 3
      2470051.80     13855454.08      2469625.39     13855454.08
      2469035.50     13855531.02
#Sta/Elev= 30
  4573.2  555.38  4590.0  553.58  4650.0  550.66  4670.0  548.58  4710.0  546.75
  4761.6  543.32  4880.0  538.08  4978.0  537.15  4978.3  536.65  4981.8  536.65
  4982.0  537.15  5040.3  538.02  5124.4  540.57  5191.6  543.35  5198.3  544.12
  5211.8  543.95  5232.0  545.07  5272.3  544.66  5282.4  545.25  5312.6  545.29
  5322.7  544.65  5354.7  544.36  5383.2  545.47  5393.3  545.01  5423.6  545.58
  5494.2  548.85  5509.3  548.63  5554.7  550.76  5588.3  552.78  5594.5  553.72
#Mann=4,-1,0
  4573.2    0.07       0  4761.6    0.12       0  4978.0    0.05       0
  4982.0    0.12       0
Bank Sta=4978,4982
Exp/Cntr=0.3,0.1

Type RM Length L Ch R = 1,2173,337,337,337
BEGIN DESCRIPTION:
XS6574
END DESCRIPTION:
XS GIS Cut Line= 3
      2470189.65     13855152.72      2469625.39     13855130.28
      2469025.85     13855357.91
#Sta/Elev= 30
  4434.9  553.24  4489.6  552.38  4509.6  551.27  4519.6  551.55  4577.0  548.51
  4599.7  548.04  4619.7  546.30  4629.7  546.48  4675.5  544.38  4689.7  544.43
  4729.8  542.10  4899.9  536.05  4960.0  534.19  5019.4  533.49  5019.7  532.99
  5023.4  533.49  5041.3  533.68  5172.2  536.77  5197.0  538.44  5203.3  537.88
  5246.0  539.23  5251.9  538.77  5299.5  539.75  5342.3  539.72  5385.1  541.13
  5397.2  540.89  5501.7  544.00  5524.2  545.31  5537.2  544.96  5640.9  550.70
#Mann=6,-1,0
  4434.9    0.12       0  4577.0    0.07       0  4675.5    0.05       0
  5019.4    0.05       0  5023.4    0.05       0  5041.3    0.12       0
Bank Sta=5019.4,5023.4
Exp/Cntr=0.3,0.1

Type RM Length L Ch R = 1,1836,448,448,448
BEGIN DESCRIPTION:
Stream0375 4.0
END DESCRIPTION:
XS GIS Cut Line= 3
      2470074.95     13854925.00      2469475.00     13854875.00
      2468874.98     13855425.02
#Sta/Elev= 30
  4402.7  551.62  4442.8  549.88  4465.4  547.78  4503.0  546.90  4543.1  543.88
  4573.2  543.21  4603.3  540.79  4622.8  540.69  4719.6  537.01  4804.0  533.76
  5009.8  531.61  5010.1  531.11  5013.8  531.61  5047.0  532.45  5061.2  534.22
  5068.6  533.54  5103.7  534.99  5125.3  534.68  5132.1  535.94  5153.6  535.48
  5195.6  537.04  5259.7  537.57  5266.5  539.52  5323.2  539.03  5465.0  542.21
  5493.1  544.00  5585.3  546.82  5691.3  553.79  5733.9  555.12  5818.7  560.63
#Mann=5,-1,0
  4402.7    0.12       0  4622.8    0.07       0  4719.6    0.12       0
  5009.8    0.05       0  5013.8    0.12       0
Bank Sta=5009.8,5013.8
Exp/Cntr=0.3,0.1

Type RM Length L Ch R = 1,1388,448,448,448
BEGIN DESCRIPTION:
Stream0375 3.0
END DESCRIPTION:
XS GIS Cut Line= 3
      2469674.98     13854624.99      2469425.00     13854475.00
      2469124.99     13854675.01
#Sta/Elev= 30
  4709.4  536.09  4744.4  534.97  4758.0  533.96  4781.3  533.43  4791.0  533.72
  4839.6  530.79  4849.3  530.97  4919.3  528.78  4934.8  527.65  4942.6  527.89
  4956.2  526.88  5006.4  525.83  5006.7  525.33  5010.2  525.33  5010.4  525.83
  5037.0  526.68  5044.5  526.24  5050.5  526.78  5101.6  526.94  5137.6  528.07
  5167.7  529.41  5173.7  530.50  5203.7  530.72  5217.3  531.71  5224.8  532.97
  5239.8  532.57  5311.9  536.37  5317.9  535.79  5325.4  535.92  5361.5  538.14
#Mann=3,-1,0
  4709.4    0.12       0  5006.4    0.05       0  5010.4    0.12       0
Bank Sta=5006.4,5010.4
Exp/Cntr=0.3,0.1

Type RM Length L Ch R = 1,940,295,295,295
BEGIN DESCRIPTION:
Stream0375 2.0
END DESCRIPTION:
XS GIS Cut Line= 3
      2469575.04     13854075.00      2469275.00     13854075.00
      2469025.00     13854275.00
#Sta/Elev= 30
  4705.0  536.54  4725.0  536.05  4765.0  533.31  4775.0  532.00  4825.0  528.13
  4855.0  526.51  4865.0  525.11  4905.0  521.52  4973.0  516.96  4973.3  516.46
  4976.8  516.46  4977.0  516.96  5018.6  517.95  5026.7  518.85  5055.5  520.00
  5082.7  521.81  5090.7  521.95  5097.1  522.68  5111.5  523.05  5133.1  524.81
  5140.3  524.72  5154.7  526.02  5175.5  526.52  5254.0  532.59  5268.4  534.52
  5289.2  536.37  5297.2  537.48  5303.6  537.58  5311.6  538.73  5325.2  539.20
#Mann=3,-1,0
  4705.0    0.12       0  4973.0    0.05       0  4977.0    0.12       0
Bank Sta=4973,4977
Exp/Cntr=0.3,0.1

Type RM Length L Ch R = 1,645,386,386,386
BEGIN DESCRIPTION:
Stream0375 1.0
END DESCRIPTION:
XS GIS Cut Line= 3
      2469641.46     13853822.25      2469147.70     13853806.22
      2468862.35     13854299.97
#Sta/Elev= 30
  4474.5  530.41  4611.0  528.04  4701.1  523.11  4731.1  522.50  4849.1  513.44
  4911.2  509.78  5003.7  508.67  5004.0  508.17  5007.7  508.67  5086.1  512.27
  5123.4  516.88  5182.3  521.79  5203.8  522.46  5219.6  524.06  5284.2  526.19
  5300.0  527.66  5327.3  527.60  5380.4  529.69  5386.1  528.92  5423.5  530.64
  5429.2  529.90  5439.2  530.89  5445.0  529.92  5460.8  531.70  5466.5  530.51
  5482.3  531.60  5498.1  531.73  5503.9  530.95  5519.6  532.28  5538.8  532.13
#Mann=3,-1,0
  4474.5    0.12       0  5003.7    0.05       0  5007.7    0.12       0
Bank Sta=5003.7,5007.7
Exp/Cntr=0.3,0.1

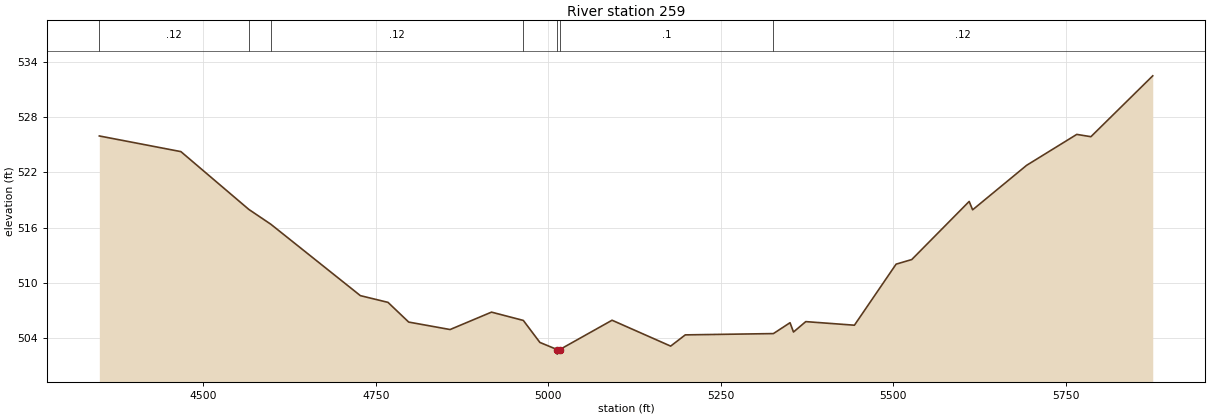
Type RM Length L Ch R = 1,259,0,0,0
BEGIN DESCRIPTION:
XS6573
END DESCRIPTION:
XS GIS Cut Line= 4
      2469683.10     13853588.22      2469016.26     13853568.98
      2468852.75     13853726.07      2468779.02     13854354.40
#Sta/Elev= 30
  4349.4  525.96  4467.6  524.26  4566.1  517.98  4598.0  516.37  4727.7  508.62
  4767.7  507.89  4797.7  505.75  4857.7  504.94  4917.7  506.83  4963.8  505.93
  4987.8  503.54  5012.7  502.77  5012.9  502.27  5016.7  502.77  5092.4  505.95
  5177.3  503.14  5198.5  504.36  5326.2  504.50  5350.3  505.68  5355.3  504.67
  5373.1  505.80  5443.6  505.41  5504.0  512.04  5526.7  512.54  5609.9  518.85
  5614.9  517.94  5693.1  522.77  5765.8  526.13  5786.3  525.88  5875.9  532.49
#Mann=7,-1,0
  4349.4    0.12       0  4566.1    0.07       0  4598.0    0.12       0
  4963.8     0.1       0  5012.7    0.05       0  5016.7     0.1       0
  5326.2    0.12       0
Bank Sta=5012.7,5016.7
Exp/Cntr=0.3,0.1

Chan Stop Cuts=-1