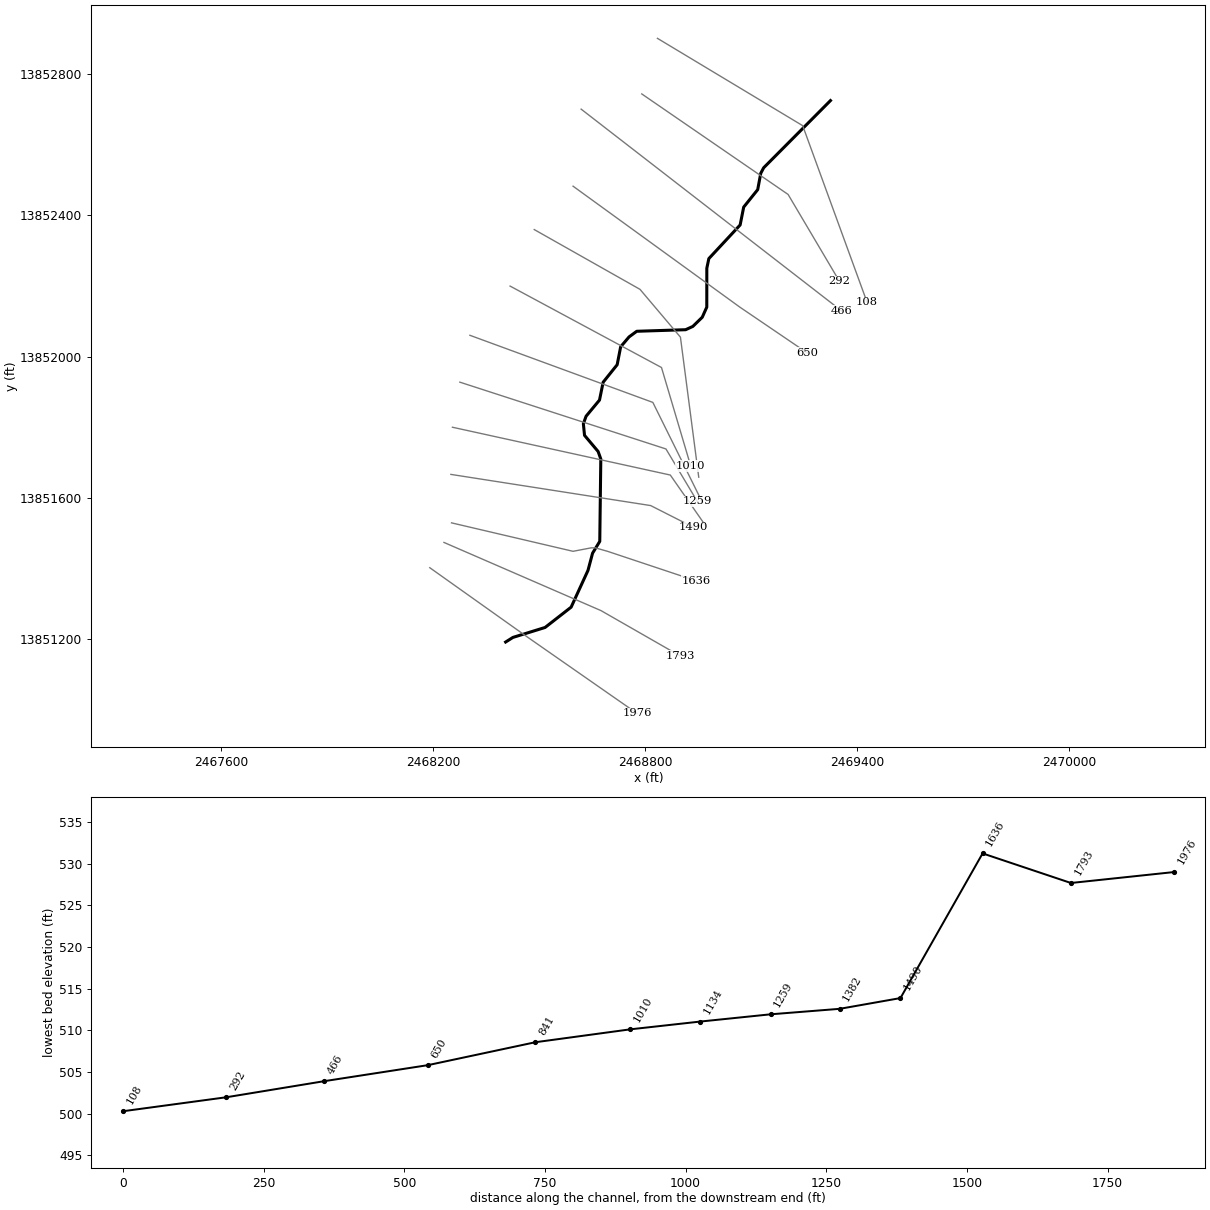
--- Stream0376.prj (project) ---

Proj Title=Stream0376 Base Level Engineering
Current Plan=p01
Default Exp/Contr=0.3,0.1
English Units
Geom File=g01
Flow File=f01
Plan File=p01
BEGIN DESCRIPTION:
Stream0376
END DESCRIPTION:

--- Stream0376.p01 (plan) ---

Plan Title=Multiple Run
Short Identifier=Multiple
Geom File=g01
Flow File=f01
Subcritical Flow
K Sum by GR= 0
Std Step Tol= 0.01
Critical Tol= 0.01
Num of Std Step Trials= 20
Max Error Tol= 0.3
Flow Tol Ratio= 0.001
Split Flow NTrial= 30
Split Flow Tol= 0.02
Split Flow Ratio= 0.02
Log Output Level= 0
Friction Slope Method= 1
Unsteady Friction Slope Method= 2
Unsteady Bridges Friction Slope Method= 1
Parabolic Critical Depth
Global Vel Dist=  1 , 1 , 1
Global Log Level= 0
CheckData=True
Encroach Param= -1, 0, 0, 0
BEGIN DESCRIPTION:
Multiple Run
END DESCRIPTION:

--- Stream0376.f01 (steady flow) ---

Flow Title=Multiple
Number of Profiles=7
Profile Names=10-year,25-year,50-year,1pct_min,100-year,1pct_plu,500-year
River Rch & RM= Stream0376,Reach-1,1976
     202     303     388     243     484     966     742
Boundary for River Rch & Prof#=Stream0376,Reach-1,1
Up Type=0
Dn Type=3
Dn Slope=0.005
Boundary for River Rch & Prof#=Stream0376,Reach-1,2
Up Type=0
Dn Type=3
Dn Slope=0.005
Boundary for River Rch & Prof#=Stream0376,Reach-1,3
Up Type=0
Dn Type=3
Dn Slope=0.005
Boundary for River Rch & Prof#=Stream0376,Reach-1,4
Up Type=0
Dn Type=3
Dn Slope=0.005
Boundary for River Rch & Prof#=Stream0376,Reach-1,5
Up Type=0
Dn Type=3
Dn Slope=0.005
Boundary for River Rch & Prof#=Stream0376,Reach-1,6
Up Type=0
Dn Type=3
Dn Slope=0.005
Boundary for River Rch & Prof#=Stream0376,Reach-1,7
Up Type=0
Dn Type=3
Dn Slope=0.005

--- Stream0376.g01 (geometry) ---

Geom Title=Existing Conditions

River Reach=Stream0376,Reach-1
Reach XY= 30
      2468404.87     13851191.33      2468425.49     13851204.36
      2468516.63     13851232.57      2468590.42     13851290.08
      2468638.16     13851394.24      2468651.18     13851443.07
      2468671.52     13851476.44      2468674.46     13851709.79
      2468666.81     13851731.08      2468628.37     13851776.74
      2468625.08     13851809.61      2468632.77     13851830.94
      2468670.78     13851876.72      2468681.07     13851927.20
      2468720.80     13851976.77      2468730.71     13852027.58
      2468754.45     13852055.55      2468776.25     13852071.55
      2468914.73     13852075.99      2468935.18     13852085.32
      2468961.80     13852111.26      2468974.66     13852140.02
      2468974.73     13852250.11      2468980.48     13852277.44
      2469069.15     13852372.71      2469079.19     13852423.27
      2469118.90     13852472.81      2469127.50     13852518.97
      2469135.76     13852534.68      2469325.00     13852725.00

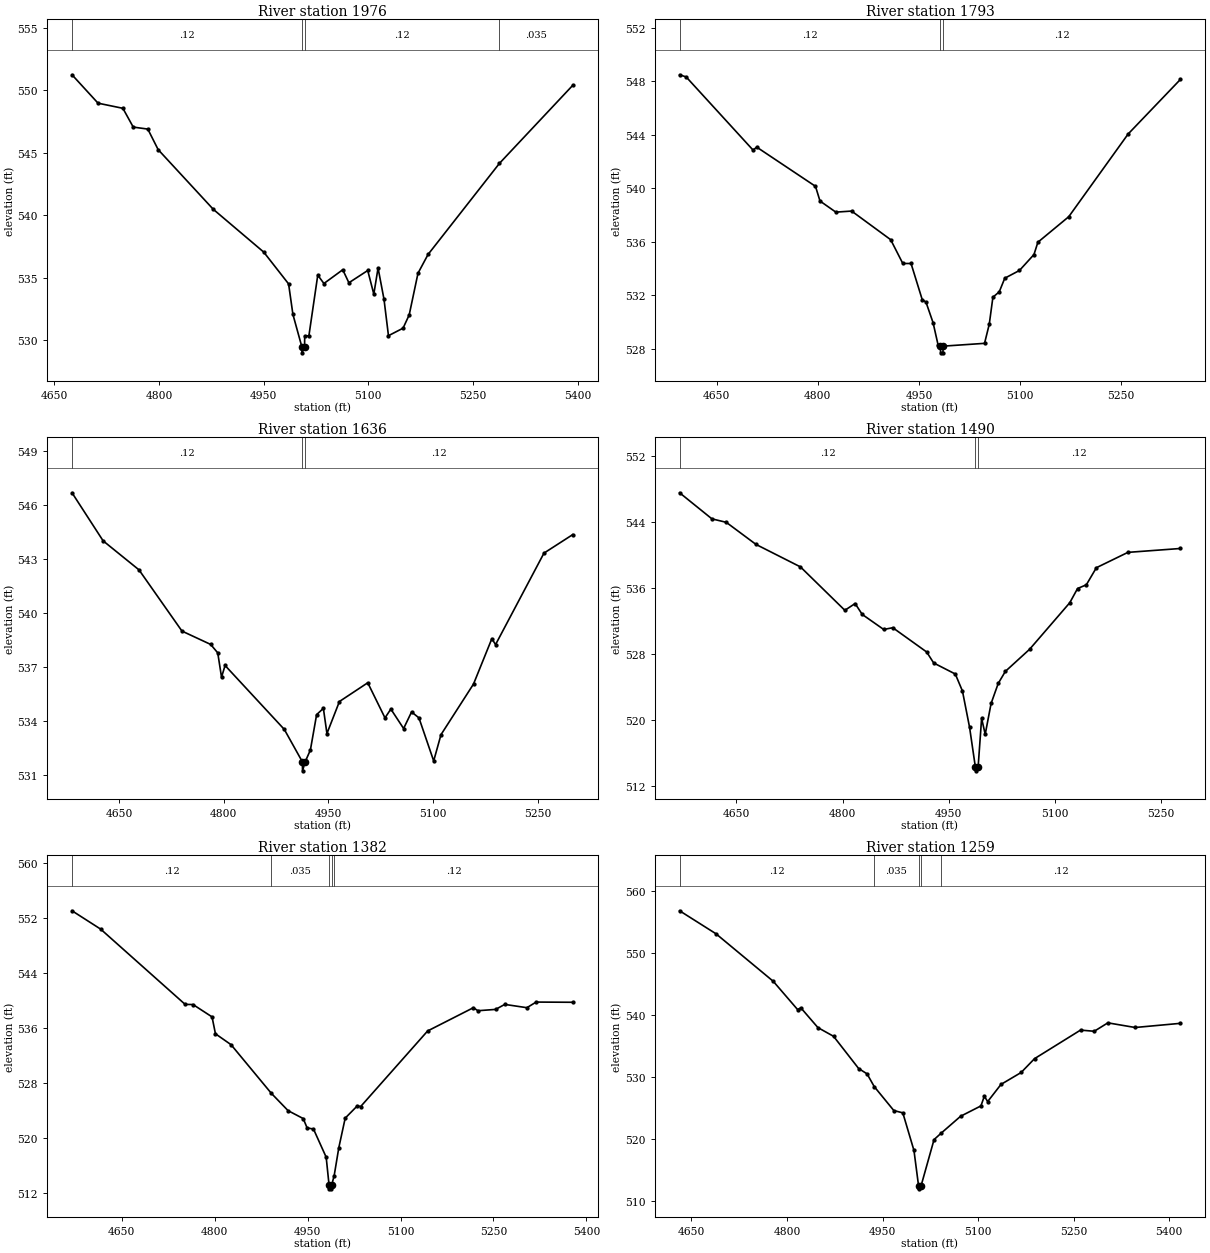
Type RM Length L Ch R = 1,1976,183,183,183
BEGIN DESCRIPTION:
Z21515
END DESCRIPTION:
XS GIS Cut Line= 3
      2468190.01     13851401.85      2468463.46     13851207.61
      2468776.99     13850989.23
#Sta/Elev= 30
  4675.4  551.23  4712.7  548.96  4748.3  548.55  4763.1  547.05  4784.0  546.89
  4798.8  545.25  4877.8  540.48  4950.1  537.06  4985.7  534.52  4991.9  532.08
  5004.6  529.51  5004.9  529.01  5008.6  529.51  5008.8  530.37  5014.8  530.37
  5027.5  535.22  5036.3  534.55  5063.3  535.65  5072.1  534.61  5099.1  535.59
  5107.8  533.70  5113.9  535.79  5122.4  533.29  5128.8  530.38  5149.7  530.98
  5158.5  532.04  5171.1  535.37  5185.5  536.87  5287.8  544.15  5392.9  550.39
#Mann=4,-1,0
  4675.4    0.12       0  5004.6    0.05       0  5008.6    0.12       0
  5287.8   0.035       0
Bank Sta=5004.6,5008.6
Exp/Cntr=0.3,0.1

Type RM Length L Ch R = 1,1793,157,157,157
BEGIN DESCRIPTION:
Z21515a
END DESCRIPTION:
XS GIS Cut Line= 3
      2468230.19     13851473.44      2468675.05     13851280.31
      2468898.60     13851152.26
#Sta/Elev= 30
  4595.0  548.49  4604.7  548.33  4703.9  542.86  4709.4  543.08  4796.5  540.15
  4803.2  539.05  4826.7  538.22  4850.1  538.30  4908.0  536.16  4926.0  534.38
  4938.2  534.38  4954.9  531.66  4960.3  531.50  4970.9  529.95  4978.3  528.29
  4981.8  528.20  4982.0  527.70  4985.5  527.70  4985.8  528.20  5047.2  528.41
  5054.2  529.84  5059.6  531.86  5069.0  532.26  5077.2  533.28  5099.0  533.86
  5120.5  535.05  5126.3  535.97  5172.1  537.88  5260.1  544.06  5337.6  548.14
#Mann=3,-1,0
  4595.0    0.12       0  4981.8    0.05       0  4985.8    0.12       0
Bank Sta=4981.8,4985.8
Exp/Cntr=0.3,0.1

Type RM Length L Ch R = 1,1636,146,146,146
BEGIN DESCRIPTION:
XS6580
END DESCRIPTION:
XS GIS Cut Line= 6
      2468251.57     13851528.90      2468595.84     13851448.28
      2468646.84     13851458.05      2468658.78     13851458.15
      2468693.50     13851448.28      2468944.20     13851364.71
#Sta/Elev= 30
  4582.7  546.69  4627.3  544.02  4678.7  542.41  4740.3  539.01  4781.4  538.27
  4791.6  537.80  4797.0  536.45  4802.1  537.10  4887.0  533.55  4912.9  531.75
  4913.1  531.25  4916.9  531.75  4924.4  532.41  4933.3  534.37  4943.0  534.72
  4948.1  533.32  4966.0  535.10  5006.6  536.14  5031.3  534.19  5039.7  534.68
  5058.0  533.60  5069.4  534.52  5080.0  534.19  5101.1  531.80  5111.6  533.26
  5158.2  536.07  5184.5  538.59  5189.8  538.26  5259.2  543.34  5300.5  544.37
#Mann=3,-1,0
  4582.7    0.12       0  4912.9    0.05       0  4916.9    0.12       0
Bank Sta=4912.9,4916.9
Exp/Cntr=0.3,0.1

Type RM Length L Ch R = 1,1490,108,108,108
BEGIN DESCRIPTION:
E20938
END DESCRIPTION:
XS GIS Cut Line= 3
      2468249.81     13851666.14      2468815.74     13851577.83
      2468936.50     13851516.55
#Sta/Elev= 30
  4569.6  547.58  4615.3  544.42  4635.6  544.00  4677.7  541.32  4740.5  538.60
  4803.3  533.34  4817.8  534.16  4827.9  532.84  4858.2  531.02  4871.1  531.23
  4919.0  528.29  4928.9  526.96  4959.5  525.62  4969.6  523.56  4979.7  519.15
  4987.8  514.39  4988.1  513.89  4991.8  514.39  4996.7  520.24  5001.8  518.32
  5010.1  522.05  5020.2  524.48  5030.3  525.94  5064.6  528.62  5121.4  534.26
  5132.4  535.98  5144.8  536.43  5159.0  538.50  5203.6  540.36  5277.8  540.83
#Mann=3,-1,0
  4569.6    0.12       0  4987.8    0.05       0  4991.8    0.12       0
Bank Sta=4987.8,4991.8
Exp/Cntr=0.3,0.1

Type RM Length L Ch R = 1,1382,123,123,123
BEGIN DESCRIPTION:
XS6579
END DESCRIPTION:
XS GIS Cut Line= 3
      2468254.18     13851799.74      2468871.35     13851664.32
      2468972.36     13851519.28
#Sta/Elev= 30
  4569.5  553.11  4615.7  550.44  4752.2  539.47  4764.9  539.45  4795.6  537.65
  4801.1  535.19  4826.3  533.60  4891.3  526.52  4918.4  523.99  4942.8  522.84
  4949.1  521.48  4959.4  521.31  4979.9  517.21  4984.6  513.10  4984.8  512.60
  4988.3  512.60  4988.6  513.10  4992.8  514.52  5000.3  518.60  5010.6  522.90
  5030.4  524.71  5035.5  524.58  5143.7  535.60  5217.6  538.99  5224.9  538.55
  5253.4  538.74  5268.3  539.47  5304.0  538.99  5318.9  539.81  5378.1  539.78
#Mann=5,-1,0
  4569.5    0.12       0  4891.3   0.035       0  4984.6    0.05       0
  4988.6   0.035       0  4992.8    0.12       0
Bank Sta=4984.6,4988.6
Exp/Cntr=0.3,0.1

Type RM Length L Ch R = 1,1259,125,125,125
BEGIN DESCRIPTION:
E20937
END DESCRIPTION:
XS GIS Cut Line= 3
      2468275.13     13851927.44      2468858.99     13851738.22
      2468947.29     13851590.45
#Sta/Elev= 30
  4631.5  556.80  4688.6  553.09  4778.5  545.42  4816.6  540.87  4821.8  541.14
  4848.6  537.95  4873.1  536.55  4912.5  531.35  4925.7  530.49  4936.9  528.44
  4967.7  524.57  4981.8  524.20  4999.3  518.13  5006.5  512.44  5006.7  511.94
  5010.5  512.44  5030.8  519.88  5041.4  520.87  5072.5  523.65  5104.4  525.32
  5109.7  526.87  5115.0  526.02  5135.9  528.79  5167.5  530.71  5188.5  532.94
  5260.7  537.55  5282.2  537.36  5303.6  538.72  5346.4  537.97  5417.4  538.64
#Mann=5,-1,0
  4631.5    0.12       0  4936.9   0.035       0  5006.5   0.035       0
  5010.5   0.035       0  5041.4    0.12       0
Bank Sta=5006.5,5010.5
Exp/Cntr=0.3,0.1

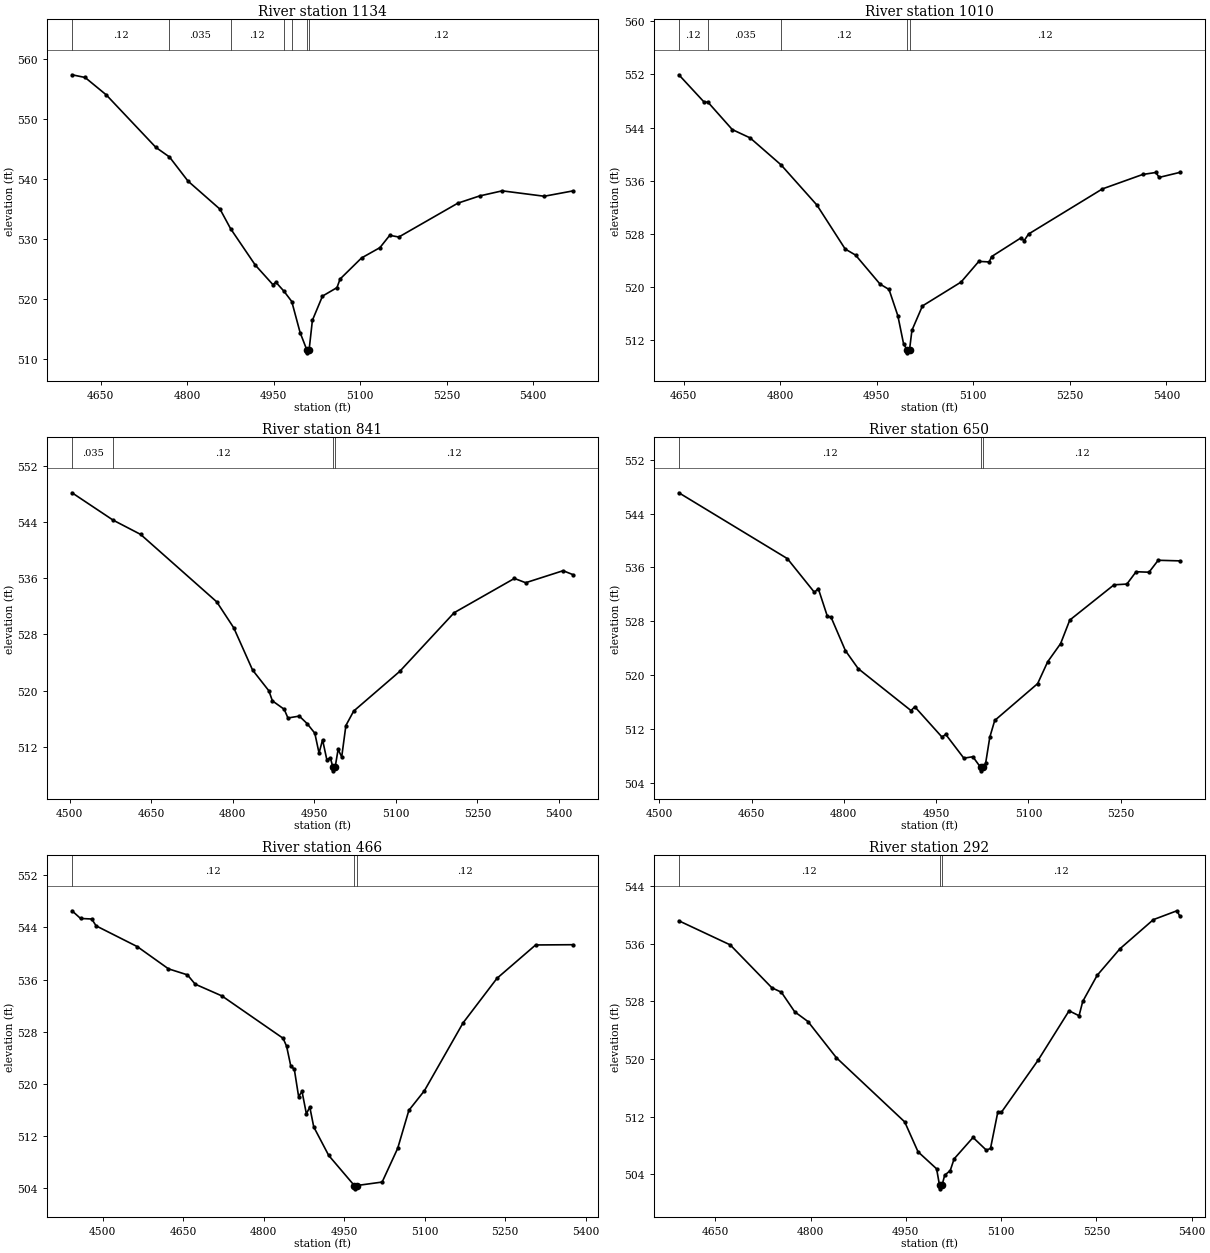
Type RM Length L Ch R = 1,1134,124,124,124
BEGIN DESCRIPTION:
XS6578
END DESCRIPTION:
XS GIS Cut Line= 3
      2468303.64     13852060.16      2468821.88     13851870.05
      2468962.51     13851586.18
#Sta/Elev= 30
  4600.3  557.38  4623.0  556.93  4659.6  554.04  4745.7  545.29  4769.3  543.69
  4801.4  539.68  4857.1  534.98  4875.3  531.75  4918.1  525.69  4948.6  522.44
  4953.9  522.83  4967.9  521.33  4981.4  519.62  4995.9  514.44  5007.5  511.57
  5007.8  511.07  5011.5  511.57  5017.2  516.49  5034.7  520.52  5059.8  521.93
  5065.2  523.36  5102.4  526.87  5134.3  528.59  5151.3  530.64  5167.1  530.36
  5269.5  536.00  5307.2  537.20  5346.4  538.05  5419.3  537.15  5469.1  538.04
#Mann=7,-1,0
  4600.3    0.12       0  4769.3   0.035       0  4875.3    0.12       0
  4967.9   0.035       0  4981.4    0.12       0  5007.5    0.05       0
  5011.5    0.12       0
Bank Sta=5007.5,5011.5
Exp/Cntr=0.3,0.1

Type RM Length L Ch R = 1,1010,169,169,169
BEGIN DESCRIPTION:
E20936
END DESCRIPTION:
XS GIS Cut Line= 3
      2468417.46     13852199.58      2468846.37     13851968.90
      2468929.22     13851689.74
#Sta/Elev= 30
  4642.5  551.95  4681.6  547.86  4687.7  547.83  4725.5  543.71  4753.2  542.46
  4801.3  538.40  4856.9  532.37  4900.9  525.75  4917.0  524.84  4955.1  520.47
  4969.0  519.67  4982.7  515.72  4991.7  511.45  4996.9  510.64  4997.2  510.14
  5000.9  510.64  5004.6  513.53  5020.9  517.19  5080.9  520.78  5108.5  523.89
  5124.7  523.81  5128.3  524.61  5173.7  527.41  5179.0  527.02  5185.7  528.00
  5300.5  534.79  5363.1  536.96  5383.5  537.26  5388.7  536.52  5420.7  537.27
#Mann=5,-1,0
  4642.5    0.12       0  4687.7   0.035       0  4801.3    0.12       0
  4996.9    0.05       0  5000.9    0.12       0
Bank Sta=4996.9,5000.9
Exp/Cntr=0.3,0.1

Type RM Length L Ch R = 1,841,191,191,191
BEGIN DESCRIPTION:
XS6577
END DESCRIPTION:
XS GIS Cut Line= 4
      2468485.93     13852359.64      2468785.42     13852190.36
      2468900.00     13852054.95      2468951.86     13851658.23
#Sta/Elev= 30
  4504.3  548.16  4579.8  544.27  4630.4  542.24  4770.5  532.64  4801.9  528.93
  4836.4  522.94  4866.4  519.98  4872.9  518.55  4894.6  517.35  4901.5  516.11
  4922.4  516.38  4936.7  515.32  4950.9  513.95  4958.7  511.12  4965.2  513.00
  4973.0  510.19  4979.5  510.44  4984.3  509.09  4984.6  508.59  4988.3  509.09
  4993.8  511.64  5000.4  510.57  5008.1  515.04  5022.4  517.09  5107.1  522.74
  5207.2  531.09  5318.1  535.97  5338.8  535.36  5407.7  537.07  5425.8  536.51
#Mann=4,-1,0
  4504.3   0.035       0  4579.8    0.12       0  4984.3    0.05       0
  4988.3    0.12       0
Bank Sta=4984.3,4988.3
Exp/Cntr=0.3,0.1

Type RM Length L Ch R = 1,650,184,184,184
BEGIN DESCRIPTION:
E20935
END DESCRIPTION:
XS GIS Cut Line= 3
      2468595.88     13852482.52      2469068.04     13852140.11
      2469259.09     13852010.34
#Sta/Elev= 30
  4531.8  547.08  4708.1  537.32  4752.2  532.31  4758.4  532.88  4773.1  528.78
  4779.3  528.60  4802.5  523.67  4823.3  521.00  4909.1  514.78  4915.3  515.34
  4959.4  510.86  4965.6  511.24  4995.0  507.72  5009.7  507.93  5022.4  506.34
  5022.6  505.84  5026.4  506.34  5030.5  507.00  5037.2  510.83  5045.2  513.31
  5115.0  518.78  5131.3  522.02  5152.3  524.71  5167.2  528.20  5239.1  533.43
  5260.0  533.54  5275.0  535.37  5296.0  535.30  5310.9  537.07  5346.0  536.98
#Mann=3,-1,0
  4531.8    0.12       0  5022.4    0.05       0  5026.4    0.12       0
Bank Sta=5022.4,5026.4
Exp/Cntr=0.3,0.1

Type RM Length L Ch R = 1,466,174,174,174
BEGIN DESCRIPTION:
XS6576
END DESCRIPTION:
XS GIS Cut Line= 2
      2468618.76     13852700.78      2469356.97     13852128.92
#Sta/Elev= 30
  4442.7  546.54  4458.6  545.36  4479.4  545.28  4487.6  544.23  4564.5  541.04
  4622.5  537.64  4657.8  536.72  4672.3  535.29  4722.1  533.49  4836.1  527.00
  4842.7  525.78  4850.6  522.70  4857.0  522.28  4865.1  518.06  4871.4  518.86
  4879.6  515.41  4885.9  516.46  4893.3  513.41  4921.2  509.04  4969.0  504.42
  4969.3  503.92  4973.0  504.42  5020.8  504.96  5049.8  510.13  5070.6  515.95
  5099.6  518.96  5171.6  529.35  5234.9  536.19  5306.9  541.30  5376.5  541.34
#Mann=3,-1,0
  4442.7    0.12       0  4969.0    0.05       0  4973.0    0.12       0
Bank Sta=4969,4973
Exp/Cntr=0.3,0.1

Type RM Length L Ch R = 1,292,184,184,184
BEGIN DESCRIPTION:
E20939
END DESCRIPTION:
XS GIS Cut Line= 3
      2468790.52     13852743.83      2469205.01     13852459.10
      2469350.48     13852213.05
#Sta/Elev= 30
  4592.6  539.19  4673.4  535.85  4739.1  529.89  4754.0  529.28  4775.0  526.56
  4795.9  525.21  4840.6  520.19  4948.2  511.28  4969.2  507.13  4998.4  504.77
  5003.0  502.49  5003.3  501.99  5007.0  502.49  5011.1  503.87  5019.9  504.53
  5026.0  506.15  5055.8  509.12  5076.7  507.36  5083.3  507.60  5094.7  512.61
  5100.4  512.61  5158.3  519.85  5207.0  526.70  5222.7  526.01  5228.5  528.00
  5251.2  531.62  5287.0  535.30  5339.7  539.35  5376.8  540.58  5381.3  539.85
#Mann=3,-1,0
  4592.6    0.12       0  5003.0    0.05       0  5007.0    0.12       0
Bank Sta=5003,5007
Exp/Cntr=0.3,0.1

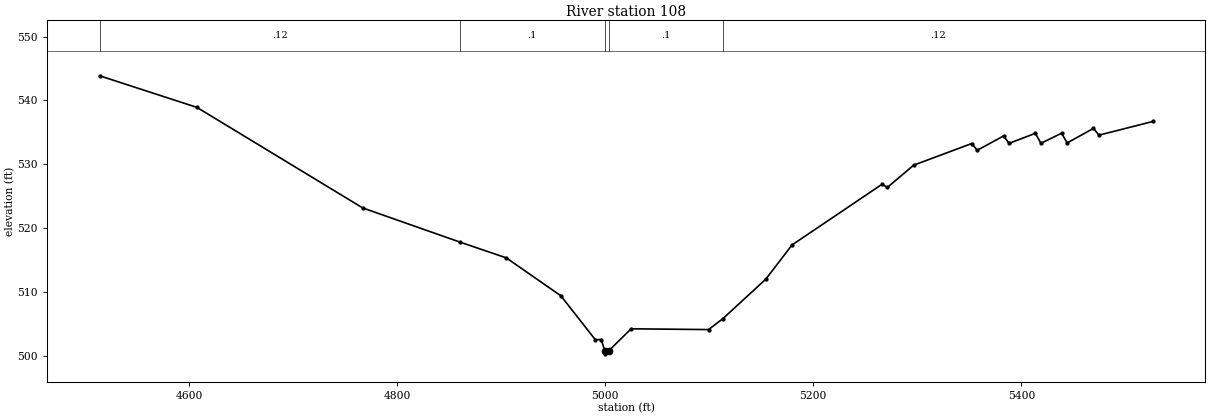
Type RM Length L Ch R = 1,108,0,0,0
BEGIN DESCRIPTION:
XS6575
END DESCRIPTION:
XS GIS Cut Line= 3
      2468834.87     13852901.32      2469246.35     13852653.91
      2469428.64     13852153.93
#Sta/Elev= 30
  4514.0  543.86  4607.5  538.91  4766.9  523.16  4860.0  517.83  4904.9  515.34
  4957.3  509.41  4990.4  502.54  4996.2  502.54  4999.5  500.81  4999.8  500.31
  5003.5  500.81  5024.9  504.23  5099.4  504.11  5113.2  505.84  5154.3  512.00
  5179.6  517.37  5266.0  526.86  5271.3  526.39  5296.5  529.86  5352.3  533.25
  5357.6  532.19  5382.9  534.44  5388.2  533.28  5413.5  534.85  5418.8  533.28
  5438.7  534.87  5444.0  533.34  5469.3  535.62  5474.6  534.56  5526.3  536.70
#Mann=5,-1,0
  4514.0    0.12       0  4860.0     0.1       0  4999.5    0.05       0
  5003.5     0.1       0  5113.2    0.12       0
Bank Sta=4999.5,5003.5
Exp/Cntr=0.3,0.1

Chan Stop Cuts=-1