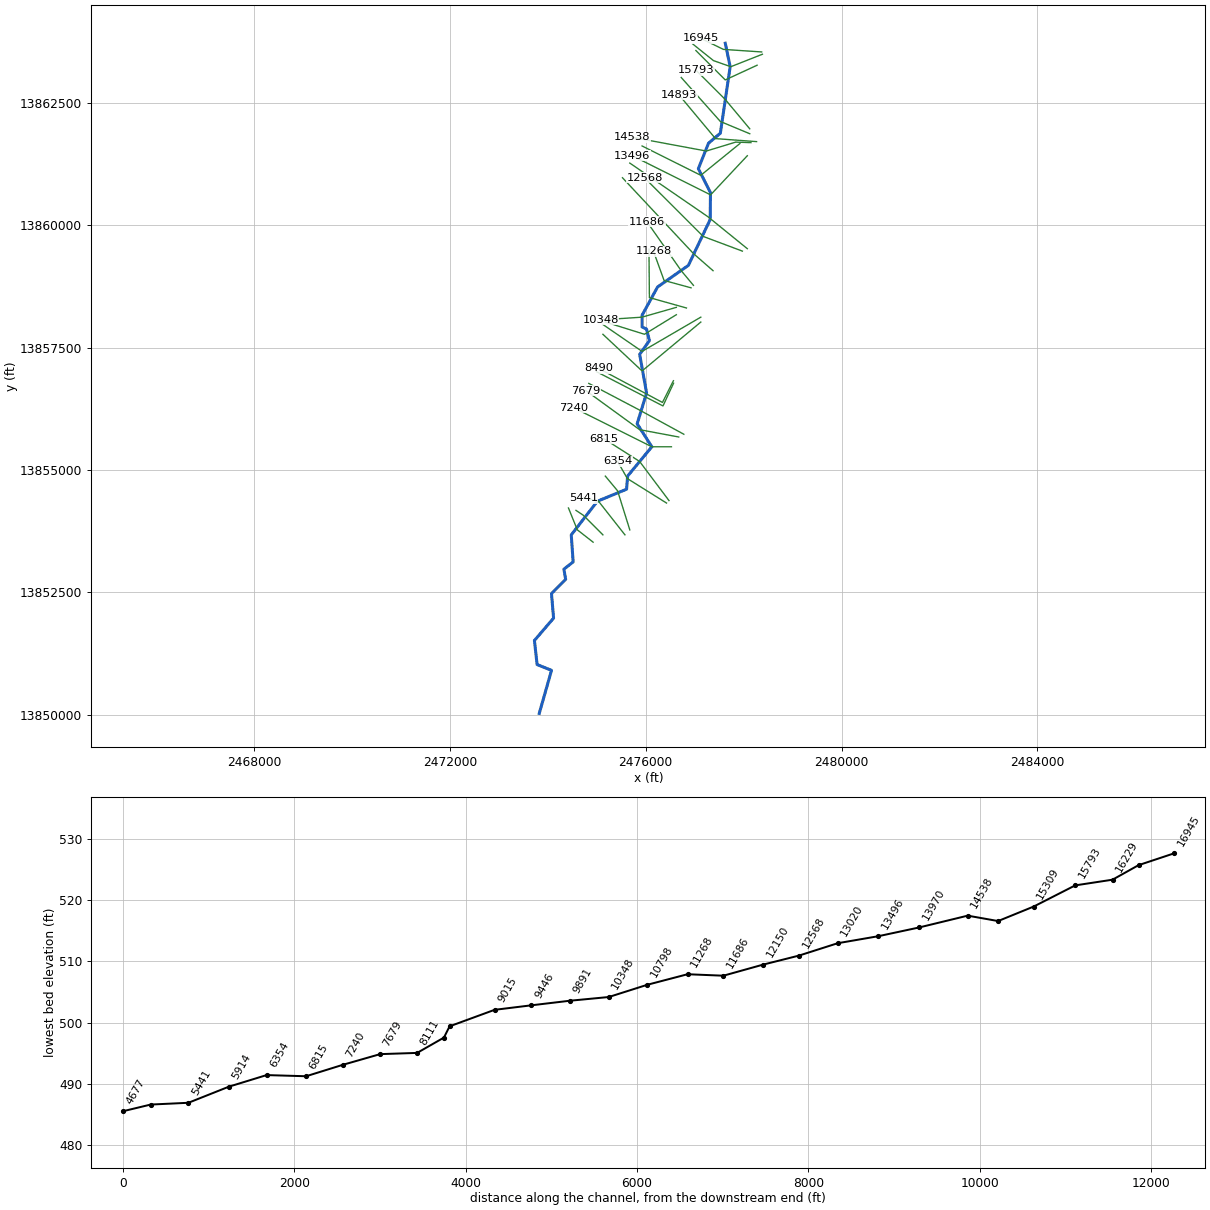
--- Stream0377.prj (project) ---

Proj Title=Stream0377 Base Level Engineering
Current Plan=p01
Default Exp/Contr=0.3,0.1
English Units
Geom File=g01
Flow File=f01
Plan File=p01
Y Axis Title=Elevation
X Axis Title(PF)=Main Channel Distance
X Axis Title(XS)=Station
BEGIN DESCRIPTION:
Stream0377
END DESCRIPTION:
DSS Export Rating Curves= 0
DSS Export Rating Curve Sorted= 0
DSS Export Volume Flow Curves= 0
DXF OffsetX= 0
DXF OffsetY= 0
DXF ScaleX= 1
DXF ScaleY= 10

--- Stream0377.p01 (plan) ---

Plan Title=Multiple Run
Short Identifier=Multiple
Geom File=g01
Flow File=f01
Subcritical Flow
K Sum by GR= 0
Std Step Tol= 0.01
Critical Tol= 0.01
Num of Std Step Trials= 20
Max Error Tol= 0.3
Flow Tol Ratio= 0.001
Split Flow NTrial= 30
Split Flow Tol= 0.02
Split Flow Ratio= 0.02
Log Output Level= 0
Friction Slope Method= 1
Unsteady Friction Slope Method= 2
Unsteady Bridges Friction Slope Method= 1
Parabolic Critical Depth
Global Vel Dist=  1 , 1 , 1
Global Log Level= 0
CheckData=True
Encroach Param= -1, 0, 0, 0
BEGIN DESCRIPTION:
Multiple Run
END DESCRIPTION:

--- Stream0377.f01 (steady flow) ---

Flow Title=Multiple
Number of Profiles=7
Profile Names=10-year,25-year,50-year,1pct_min,100-year,1pct_plu,500-year
River Rch & RM= Stream0377,Reach-1,16945
     502     791    1046     670    1337    2668    2162
River Rch & RM= Stream0377,Reach-1,14538
    1023    1693    2314    1530    3053    6092    5267
River Rch & RM= Stream0377,Reach-1,10348
    1553    2617    3622    2421    4830    9637    8513
River Rch & RM= Stream0377,Reach-1,8111
    1964    3337    4641    3114    6213   12397   11042
River Rch & RM= Stream0377,Reach-1,3782
    2238    3811    5307    3564    7111   14188   12656
Boundary for River Rch & Prof#=Stream0377,Reach-1,1
Up Type=0
Dn Type=3
Dn Slope=0.005
Boundary for River Rch & Prof#=Stream0377,Reach-1,2
Up Type=0
Dn Type=3
Dn Slope=0.005
Boundary for River Rch & Prof#=Stream0377,Reach-1,3
Up Type=0
Dn Type=3
Dn Slope=0.005
Boundary for River Rch & Prof#=Stream0377,Reach-1,4
Up Type=0
Dn Type=3
Dn Slope=0.005
Boundary for River Rch & Prof#=Stream0377,Reach-1,5
Up Type=0
Dn Type=3
Dn Slope=0.005
Boundary for River Rch & Prof#=Stream0377,Reach-1,6
Up Type=0
Dn Type=3
Dn Slope=0.005
Boundary for River Rch & Prof#=Stream0377,Reach-1,7
Up Type=0
Dn Type=3
Dn Slope=0.005

--- Stream0377.g01 (geometry) ---

Geom Title=Existing Conditions
Program Version=4.10

River Reach=Stream0377      ,Reach-1
Reach XY= 30
        2477625.       13863725.      2477725.21     13863245.21
      2477524.35     13861885.64      2477282.93      13861681.4
      2477075.09     13861159.61      2477322.94     13860669.15
      2477316.96     13860121.68      2476871.49     13859183.48
      2476241.65     13858741.67      2475925.81     13858164.29
        2475925.       13857925.      2476016.19     13857881.96
      2476075.37      13857645.2      2475876.05     13857364.57
      2476017.44       13856575.      2475825.06     13855945.03
        2476125.       13855475.      2475630.47     13854877.45
      2475608.73     13854607.85      2475011.79     13854361.37
      2474478.54     13853673.54      2474517.31     13853121.33
      2474328.52     13852973.54      2474364.03     13852764.62
        2474075.       13852475.      2474117.19     13851971.58
      2473726.05     13851514.57      2473780.82     13851022.68
      2474075.44       13850905.        2473825.       13850025.

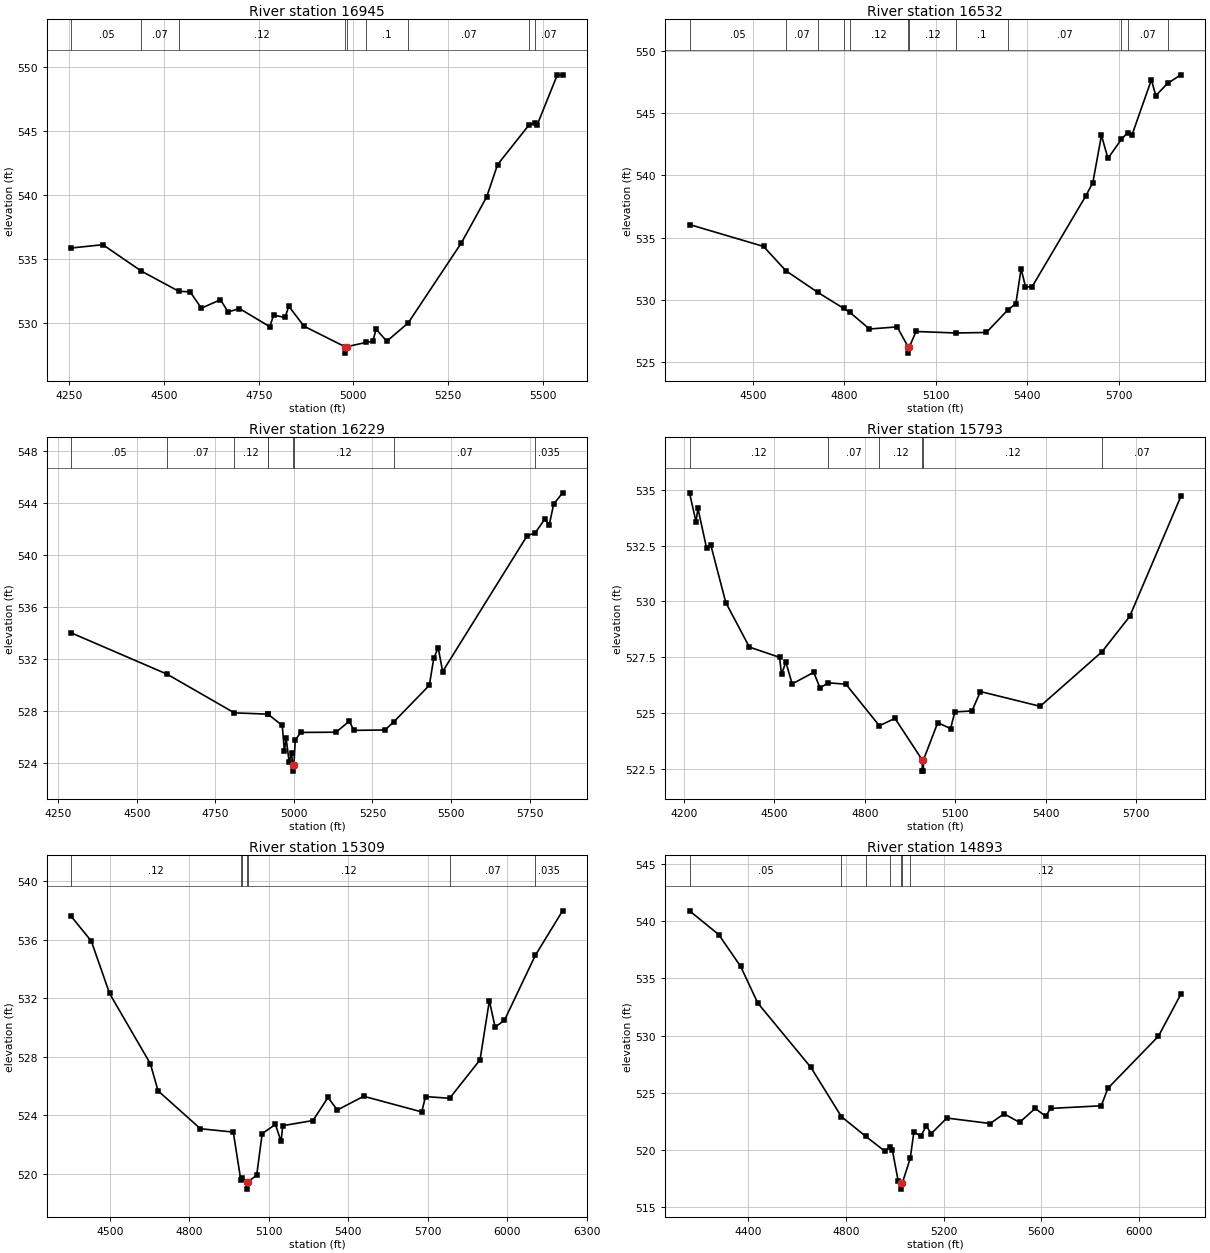
Type RM Length L Ch R = 1 ,16945   ,413,413,413
BEGIN DESCRIPTION:
Stream0377 34.0
END DESCRIPTION:
XS GIS Cut Line= 3
      2478368.18     13863546.83      2477586.98     13863598.91
      2477124.98     13863825.01
#Sta/Elev= 30
  4254.9  535.86  4338.3  536.12  4440.2  534.05  4539.1  532.47  4568.8  532.43
  4598.5  531.15    4649  531.81    4669  530.85  4699.1  531.12  4779.2   529.7
  4789.3  530.61  4819.3  530.42  4829.4   531.3  4869.4  529.74  4977.7  528.13
  4977.9  527.63  4981.7  528.13  5033.8  528.47  5051.2  528.56  5059.9   529.5
    5088  528.56  5144.5  529.99    5285  536.26  5351.8  539.86  5380.6  542.39
  5462.9  545.47  5478.3  545.68  5485.4  545.52  5538.1   549.4  5552.2  549.42
#Mann= 9 ,-1 , 0
  4254.9     .05       0  4440.2     .07       0  4539.1     .12       0
  4977.7     .05       0  4981.7     .12       0  5033.8      .1       0
  5144.5     .07       0  5462.9    .035       0  5478.3     .07       0
Bank Sta=4977.7,4981.7
XS Rating Curve= 0 ,0
Exp/Cntr=0.3,0.1

Type RM Length L Ch R = 1 ,16532   ,303,303,303
BEGIN DESCRIPTION:
XS6585
END DESCRIPTION:
XS GIS Cut Line= 4
      2478383.83     13863499.94      2477738.03     13863244.74
      2477383.86     13863369.74      2476961.98     13863708.29
#Sta/Elev= 30
  4292.1  536.05  4534.8  534.29  4608.3  532.33  4713.1  530.59  4798.1   529.3
  4817.8  528.99  4882.2  527.65  4972.9  527.82  5008.9  526.21  5009.2  525.71
  5012.9  526.21  5034.9  527.45  5165.2  527.33  5265.4  527.37    5336  529.19
  5362.1  529.69  5379.2  532.49  5393.6  531.06  5414.4  531.01    5592  538.38
  5614.4  539.42  5642.7  543.22    5664  541.37  5708.3  542.91  5728.2  543.43
  5742.4  543.22  5806.4  547.69  5820.8  546.42  5860.1  547.41    5903  548.09
#Mann= 12 ,-1 , 0
  4292.1     .05       0  4608.3     .07       0  4713.1     .12       0
  4798.1     .07       0  4817.8     .12       0  5008.9     .05       0
  5012.9     .12       0  5165.2      .1       0    5336     .07       0
  5708.3    .035       0  5728.2     .07       0  5860.1     .12       0
Bank Sta=5008.9,5012.9
XS Rating Curve= 0 ,0
Exp/Cntr=0.3,0.1

Type RM Length L Ch R = 1 ,16229   ,436,436,436
BEGIN DESCRIPTION:
Stream0377 33.0
END DESCRIPTION:
XS GIS Cut Line= 3
      2478274.96     13863274.98        2477625.       13862975.
      2477024.98     13863575.02
#Sta/Elev= 30
  4290.8  533.99  4595.9  530.81  4810.1  527.83    4916  527.73    4917  527.73
  4962.6  526.86  4969.5  524.88    4975  525.86  4984.6  524.07  4992.4  524.72
  4995.9  523.84  4996.2  523.34  4999.9  523.84  5003.9   525.7  5020.8  526.32
  5133.9  526.34  5176.3  527.19  5190.5  526.48  5289.5  526.51  5317.2  527.12
  5430.9  529.95    5445  532.02  5459.2  532.85  5473.3  531.01    5742  541.46
  5768.6  541.71  5798.6  542.76  5812.7  542.31  5826.9  543.91  5855.2  544.78
#Mann= 9 ,-1 , 0
  4290.8     .05       0  4595.9     .07       0  4810.1     .12       0
    4916     .05       0    4917     .12       0  4995.9     .05       0
  4999.9     .12       0  5317.2     .07       0  5768.6    .035       0
Bank Sta=4995.9,4999.9
XS Rating Curve= 0 ,0
Exp/Cntr=0.3,0.1

Type RM Length L Ch R = 1 ,15793   ,484,484,484
BEGIN DESCRIPTION:
Stream0377 32.0
END DESCRIPTION:
XS GIS Cut Line= 3
      2478124.98     13861975.02        2477625.       13862575.
      2477025.02     13863174.98
#Sta/Elev= 30
    4219  534.86  4240.5  533.57    4247  534.16  4275.6  532.39  4289.9  532.51
  4339.4  529.95  4417.5  527.96  4517.7   527.5  4524.2  526.74  4538.5  527.29
  4559.4  526.31    4631  526.83  4651.8  526.13  4678.3  526.36  4737.7   526.3
  4848.6  524.44  4900.4  524.77  4990.8  522.91  4991.1  522.41  4994.6  522.41
  4994.8  522.91  5042.4  524.58  5084.8  524.31    5099  525.06  5155.6   525.1
  5183.8  525.97  5381.8  525.31    5587  527.75  5678.8  529.33  5848.5   534.7
#Mann= 6 ,-1 , 0
    4219     .12       0  4678.3     .07       0  4848.6     .12       0
  4990.8     .05       0  4994.8     .12       0    5587     .07       0
Bank Sta=4990.8,4994.8
XS Rating Curve= 0 ,0
Exp/Cntr=0.3,0.1

Type RM Length L Ch R = 1 ,15309   ,416,416,416
BEGIN DESCRIPTION:
Stream0377 31.0
END DESCRIPTION:
XS GIS Cut Line= 3
      2478124.97     13861875.01        2477525.       13862125.
      2476725.02     13863024.98
#Sta/Elev= 30
  4354.2  537.61    4430  535.92  4498.8  532.34  4652.6  527.54  4681.9  525.68
  4841.7  523.09  4965.7  522.86  4993.9   519.6  4997.9  519.71    5016  519.46
  5016.2  518.96    5020  519.46  5053.9   519.9  5074.8  522.76  5124.6  523.38
  5145.9  522.23  5152.6   523.3  5266.3  523.65  5323.2  525.23  5358.3  524.37
  5457.8  525.31  5676.9  524.24  5691.1  525.29  5782.1  525.17  5896.8   527.8
    5932  531.84  5953.7  530.04  5988.8   530.5  6105.3  534.94  6208.3  537.99
#Mann= 7 ,-1 , 0
  4354.2     .12       0  4993.9     .15       0  4997.9     .12       0
    5016     .05       0    5020     .12       0  5782.1     .07       0
  6105.3    .035       0
Bank Sta=5016,5020
XS Rating Curve= 0 ,0
Exp/Cntr=0.3,0.1

Type RM Length L Ch R = 1 ,14893   ,355,355,355
BEGIN DESCRIPTION:
Stream0377 30.0
END DESCRIPTION:
XS GIS Cut Line= 3
      2478264.08     13861713.49        2477425.       13861775.
      2476674.98     13862675.02
#Sta/Elev= 30
    4159   540.9  4278.4  538.83  4368.6  536.04  4438.8  532.84  4656.4  527.22
  4781.4  522.92  4880.4  521.21  4960.2  519.89  4979.4  520.29  4990.3  519.97
    5014  517.29  5026.3  517.09  5026.6  516.59  5030.3  517.09  5063.2  519.27
  5078.4  521.61  5106.4   521.2  5128.6  522.11  5149.4  521.44  5213.2   522.8
  5390.8  522.32  5447.5  523.17  5511.3  522.42    5575  523.64    5618  522.96
  5638.8  523.64  5845.8  523.87  5873.1   525.4  6080.1  529.95  6171.9  533.62
#Mann= 7 ,-1 , 0
    4159     .05       0  4781.4     .07       0  4880.4     .12       0
  4979.4     .07       0  5026.3     .05       0  5030.3     .07       0
  5063.2     .12       0
Bank Sta=5026.3,5030.3
XS Rating Curve= 0 ,0
Exp/Cntr=0.3,0.1

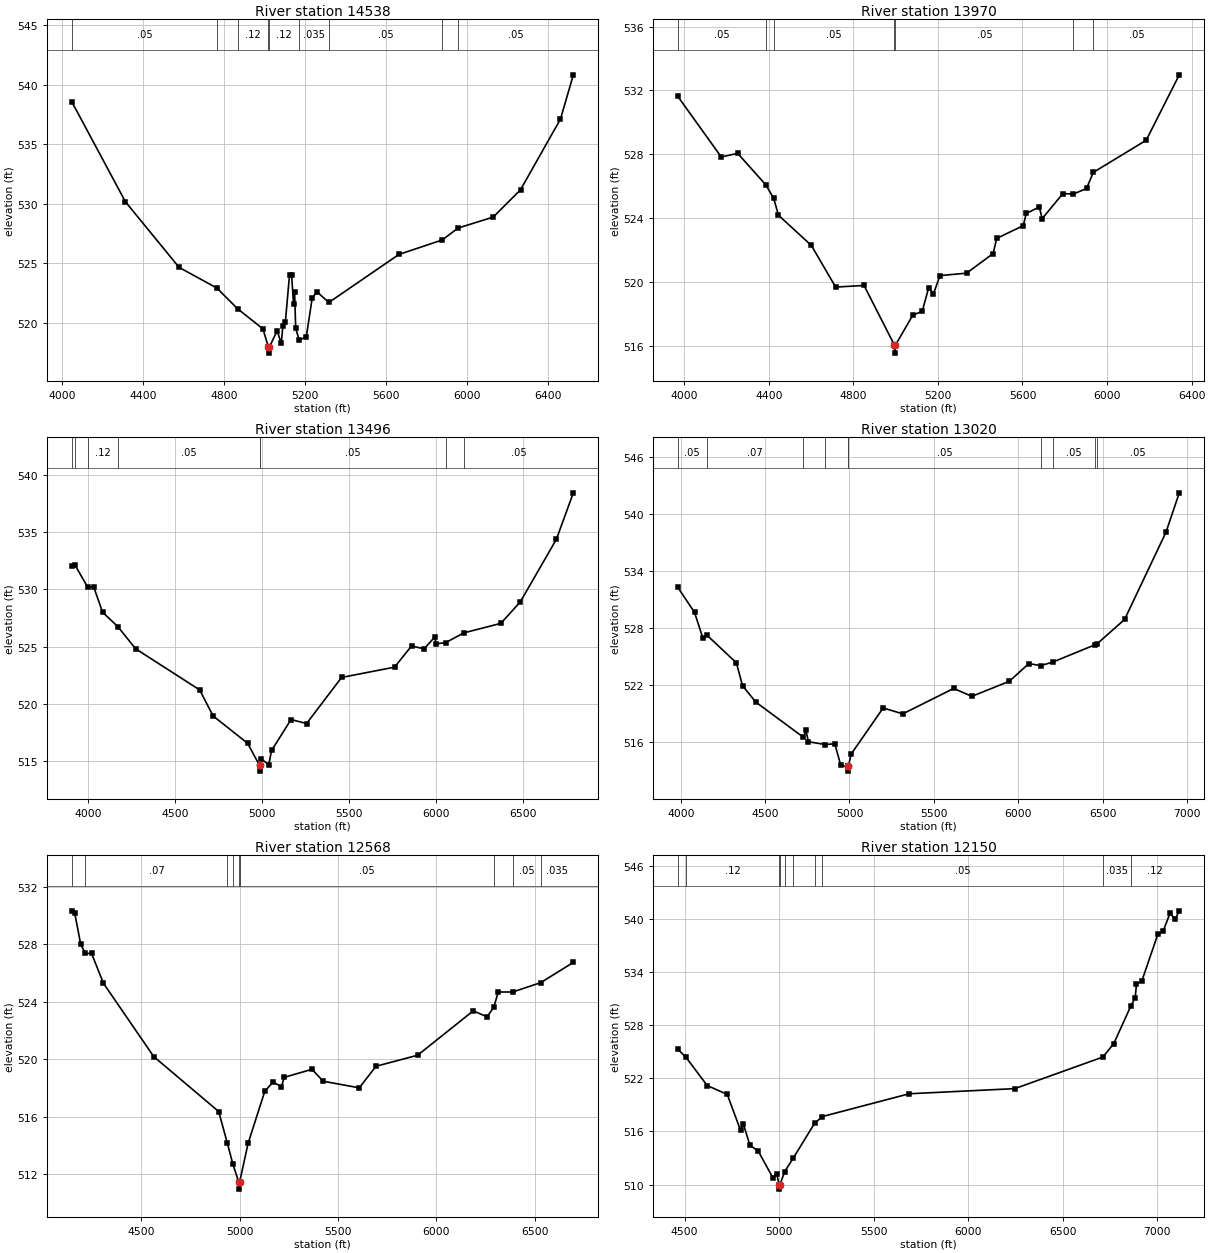
Type RM Length L Ch R = 1 ,14538   ,568,568,568
BEGIN DESCRIPTION:
XS6584
END DESCRIPTION:
XS GIS Cut Line= 4
      2478149.49     13861692.66      2477836.98     13861703.08
      2477238.03     13861520.79      2475728.83     13861801.81
#Sta/Elev= 30
  4048.7  538.58  4313.3  530.18  4577.9  524.67  4764.7  522.93  4866.8  521.19
  4991.5  519.51  5018.8  517.97  5019.1  517.47  5023.3  517.97  5061.7  519.35
  5082.1  518.28  5089.8  519.72  5102.4   520.1  5122.8  524.04    5133  524.06
  5142.5  521.61  5147.6  522.63  5153.3  519.54  5170.7  518.57  5205.5  518.84
  5234.7   522.1  5258.2  522.62  5316.6  521.72  5661.9  525.75    5876  526.97
  5954.3  527.97  6127.5  528.89    6262  531.18  6459.2  537.12  6522.6  540.83
#Mann= 9 ,-1 , 0
  4048.7     .05       0  4764.7     .07       0  4866.8     .12       0
  5018.8     .05       0  5023.3     .12       0  5170.7    .035       0
  5316.6     .05       0    5876    .035       0  5954.3     .05       0
Bank Sta=5018.8,5023.3
XS Rating Curve= 0 ,0
Exp/Cntr=0.3,0.1

Type RM Length L Ch R = 1 ,13970   ,474,474,474
BEGIN DESCRIPTION:
Stream0377 29.0
END DESCRIPTION:
XS GIS Cut Line= 3
      2477925.01     13861675.01        2477125.       13861025.
      2475925.03     13861624.98
#Sta/Elev= 30
  3969.2  531.64  4175.4  527.83  4252.9  528.06  4385.1   526.1    4423  525.25
    4446  524.18  4601.3  522.29  4716.3  519.68  4850.6  519.78  4994.4  516.04
  4994.8  515.54  4999.1  516.04  5081.1  517.92  5125.8  518.16  5156.5  519.65
  5178.9  519.25  5209.6   520.4  5335.4  520.55  5461.2  521.78    5478  522.73
  5603.7  523.53  5617.7  524.29  5679.2   524.7  5693.2  523.97    5791  525.54
  5841.2  525.51  5902.8  525.86  5935.3  526.87  6185.1  528.88  6341.6  532.98
#Mann= 7 ,-1 , 0
  3969.2     .05       0  4385.1     .12       0    4423     .05       0
  4994.4     .05       0  4999.1     .05       0  5841.2    .035       0
  5935.3     .05       0
Bank Sta=4994.4,4999.1
XS Rating Curve= 0 ,0
Exp/Cntr=0.3,0.1

Type RM Length L Ch R = 1 ,13496   ,476,476,476
BEGIN DESCRIPTION:
Stream0377 28.0
END DESCRIPTION:
XS GIS Cut Line= 3
      2478074.98     13861424.98        2477325.       13860625.
      2475725.01       13861425.
#Sta/Elev= 30
  3904.1  532.06  3923.8  532.11  3995.7   530.2  4031.3  530.19  4081.1  528.02
  4168.6  526.76  4272.1  524.81  4639.9  521.22  4717.6  518.94  4915.9  516.55
  4984.4  514.62  4984.7  514.12  4989.1  514.62  4993.6   515.2    5037  514.68
  5053.8  515.93  5165.6  518.63    5255  518.28  5456.3  522.31  5760.9  523.21
  5858.7  525.06  5931.4  524.81  5992.9  525.86  5998.5  525.24  6055.8  525.36
  6158.2   526.2    6373  527.04  6484.8  528.93  6691.7  534.38  6789.5  538.45
#Mann= 8 ,-1 , 0
  3904.1     .12       0  3923.8     .05       0  3995.7     .12       0
  4168.6     .05       0  4984.4     .05       0  4989.1     .05       0
  6055.8    .035       0  6158.2     .05       0
Bank Sta=4984.4,4989.1
XS Rating Curve= 0 ,0
Exp/Cntr=0.3,0.1

Type RM Length L Ch R = 1 ,13020   ,452,452,452
BEGIN DESCRIPTION:
Stream0377 27.0
END DESCRIPTION:
XS GIS Cut Line= 3
      2478074.99     13859525.01        2477275.       13860175.
      2475675.01     13861274.99
#Sta/Elev= 30
  3981.9  532.31  4081.7  529.65  4131.3  526.94  4154.7  527.27  4329.8  524.35
  4366.2  521.95  4444.5  520.23  4727.4  516.52  4742.1  517.25  4756.2  516.06
  4857.4  515.76  4912.8  515.85  4948.2  513.58  4988.7  513.47  4989.1  512.97
  4993.5  513.47  5009.4  514.75  5199.4  519.61  5315.8  518.99  5617.5  521.66
  5725.1  520.83  5947.1  522.41  6062.6  524.27  6133.8  524.06  6207.1  524.45
  6452.3  526.23  6467.3  526.35  6630.2  528.91  6875.2  538.07  6954.3  542.22
#Mann= 10 ,-1 , 0
  3981.9     .05       0  4154.7     .07       0  4727.4     .12       0
  4857.4     .05       0  4988.7     .05       0  4993.5     .05       0
  6133.8    .035       0  6207.1     .05       0  6452.3    .035       0
  6467.3     .05       0
Bank Sta=4988.7,4993.5
XS Rating Curve= 0 ,0
Exp/Cntr=0.3,0.1

Type RM Length L Ch R = 1 ,12568   ,418,418,418
BEGIN DESCRIPTION:
Stream0377 26.0
END DESCRIPTION:
XS GIS Cut Line= 3
      2477975.03     13859474.99        2477175.       13859775.
      2475974.99     13860975.01
#Sta/Elev= 30
  4145.6  530.32  4160.8  530.16    4191     528  4214.7  527.35  4246.2  527.36
  4306.7  525.28    4563  520.17  4893.2  516.35  4937.4  514.13  4965.4  512.68
  4994.9  511.45  4995.3  510.95  4999.8  511.45  5042.5  514.13  5127.3  517.75
  5169.7  518.41  5212.2  518.07  5226.3  518.73  5367.7  519.29  5424.3  518.46
  5608.1     518    5693   519.5  5905.1  520.27    6188  523.36  6258.7  522.94
  6292.4  523.62  6315.3  524.67  6388.2  524.67    6531  525.32  6697.1  526.73
#Mann= 9 ,-1 , 0
  4145.6     .05       0  4214.7     .07       0  4937.4     .12       0
  4965.4     .05       0  4994.9     .05       0  4999.8     .05       0
  6292.4    .035       0  6388.2     .05       0    6531    .035       0
Bank Sta=4994.9,4999.8
XS Rating Curve= 0 ,0
Exp/Cntr=0.3,0.1

Type RM Length L Ch R = 1 ,12150   ,464,464,464
BEGIN DESCRIPTION:
Stream0377 25.0
END DESCRIPTION:
XS GIS Cut Line= 3
      2477374.97     13859075.03        2476975.       13859425.
      2475524.98     13860975.02
#Sta/Elev= 30
  4463.4  525.29  4506.3   524.4  4619.5  521.18  4725.8  520.17    4796  516.12
  4810.3  516.85  4846.3  514.41  4888.6  513.81  4966.9  510.77  4987.7  511.24
  4999.5  509.98  4999.8  509.48  5004.5  509.98  5028.9  511.44  5075.8  513.01
  5187.9  516.92  5229.5  517.68  5688.3  520.25  6247.1  520.83  6713.6   524.4
  6770.8  525.92  6860.7  530.14  6884.1  531.08    6891  532.63  6919.3  532.99
  7004.3  538.29  7032.6  538.64  7067.8  540.61  7096.1  539.99  7117.4  540.91
#Mann= 10 ,-1 , 0
  4463.4     .07       0  4506.3     .12       0  4999.5     .05       0
  5004.5     .12       0  5028.9     .07       0  5075.8     .05       0
  5187.9     .07       0  5229.5     .05       0  6713.6    .035       0
  6860.7     .12       0
Bank Sta=4999.5,5004.5
XS Rating Curve= 0 ,0
Exp/Cntr=0.3,0.1

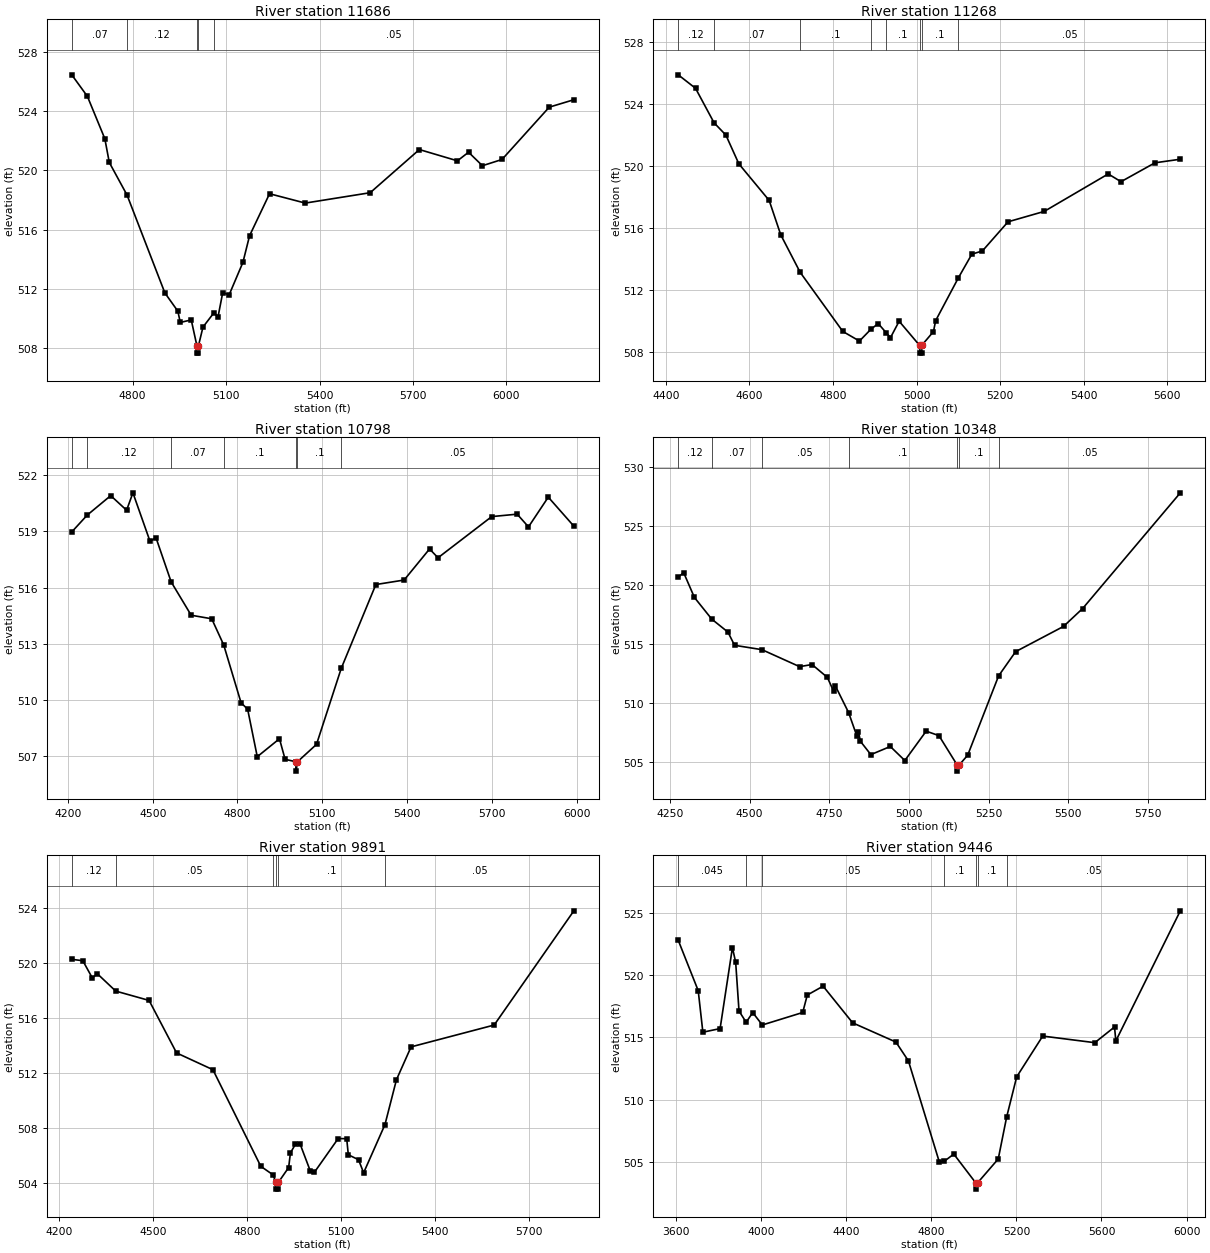
Type RM Length L Ch R = 1 ,11686   ,418,418,418
BEGIN DESCRIPTION:
Stream0377 24.0
END DESCRIPTION:
XS GIS Cut Line= 3
      2476975.02     13858774.98        2476725.       13859075.
        2476025.       13860075.
#Sta/Elev= 30
    4605  526.44  4655.1  524.99  4711.1  522.13  4725.4  520.53  4782.4  518.33
  4903.8  511.73  4945.4   510.5  4953.2  509.74  4988.4  509.91  5006.5  508.17
  5006.9  507.67  5011.2  507.67  5011.6  508.17  5026.1  509.43  5061.5   510.4
  5074.4  510.12  5089.3  511.74  5110.2  511.61  5154.2  513.79  5175.6  515.59
  5239.7  518.42  5354.3  517.79  5562.7  518.49  5720.5   521.4  5842.6  520.64
  5878.3  521.22  5922.8  520.31  5985.6  520.73  6137.3  524.26  6216.2  524.76
#Mann= 5 ,-1 , 0
    4605     .07       0  4782.4     .12       0  5006.5     .05       0
  5011.6     .12       0  5061.5     .05       0
Bank Sta=5006.5,5011.6
XS Rating Curve= 0 ,0
Exp/Cntr=0.3,0.1

Type RM Length L Ch R = 1 ,11268   ,470,470,470
BEGIN DESCRIPTION:
Stream0377 23.0
END DESCRIPTION:
XS GIS Cut Line= 3
      2476924.97     13858725.01        2476375.       13858875.
      2476159.94     13859468.59
#Sta/Elev= 30
  4429.7  525.88  4471.1  525.01  4515.5  522.78  4543.7  521.99  4574.8  520.13
  4647.3  517.77    4675  515.55  4721.4  513.13  4823.5  509.31  4863.3  508.69
  4890.3  509.44  4908.2  509.82  4927.2  509.23  4937.6  508.91  4958.3  509.97
  5007.2  508.41  5007.6  507.91  5011.9  507.91  5012.3  508.41  5040.4   509.3
  5045.7  510.01  5100.2  512.78  5132.3   514.3  5157.6  514.51  5218.9  516.39
  5305.4  517.06  5458.6  519.48  5489.2  518.98  5570.5   520.2  5631.1  520.43
#Mann= 8 ,-1 , 0
  4429.7     .12       0  4515.5     .07       0  4721.4      .1       0
  4890.3     .12       0  4927.2      .1       0  5007.2     .05       0
  5012.3      .1       0  5100.2     .05       0
Bank Sta=5007.2,5012.3
XS Rating Curve= 0 ,0
Exp/Cntr=0.3,0.1

Type RM Length L Ch R = 1 ,10798   ,450,450,450
BEGIN DESCRIPTION:
Stream0377 22.0
END DESCRIPTION:
XS GIS Cut Line= 3
      2476831.74     13858312.46        2476075.       13858525.
      2476066.15     13859515.54
#Sta/Elev= 30
  4213.6  518.97  4268.3  519.87  4351.4  520.91  4407.6  520.13    4430  521.06
  4490.7  518.46  4511.4  518.67  4565.3   516.3  4636.1  514.52  4708.8  514.33
  4751.3  512.93  4812.7  509.84  4835.9   509.5    4870  506.96  4948.5  507.92
  4968.5  506.82  5007.1  506.69  5007.5  506.19  5012.2  506.69  5079.6  507.62
  5167.1  511.68  5289.6  516.16  5389.6   516.4  5479.6  518.06  5509.6  517.59
  5699.6  519.79  5789.6  519.92  5829.7  519.24  5899.7  520.83  5990.2  519.28
#Mann= 7 ,-1 , 0
  4213.6    .045       0  4268.3     .12       0  4565.3     .07       0
  4751.3      .1       0  5007.1     .05       0  5012.2      .1       0
  5167.1     .05       0
Bank Sta=5007.1,5012.2
XS Rating Curve= 0 ,0
Exp/Cntr=0.3,0.1

Type RM Length L Ch R = 1 ,10348   ,457,457,457
BEGIN DESCRIPTION:
Stream0377 21.0
END DESCRIPTION:
XS GIS Cut Line= 3
      2476625.02     13858325.01        2475925.       13858125.
      2475079.19     13858068.91
#Sta/Elev= 30
    4276  520.63  4292.9  521.03  4326.7  518.92  4381.2  517.08    4432  515.98
  4452.8  514.86  4538.7  514.49  4656.9  513.05  4695.9  513.23    4744  512.14
  4763.5  510.97  4768.7  511.44  4810.6  509.16  4836.3  507.19  4841.5  507.52
    4848  506.71  4880.5  505.59  4941.6  506.28  4987.1  505.09  5054.1  507.58
  5094.2   507.2  5151.8  504.69  5152.2  504.19    5157  504.69  5184.4  505.54
  5281.5  512.27  5334.8  514.32  5485.1  516.46  5545.2  517.98  5851.7  527.79
#Mann= 7 ,-1 , 0
    4276     .12       0  4381.2     .07       0  4538.7     .05       0
  4810.6      .1       0  5151.8     .05       0    5157      .1       0
  5281.5     .05       0
Bank Sta=5151.8,5157
XS Rating Curve= 0 ,0
Exp/Cntr=0.3,0.1

Type RM Length L Ch R = 1 ,9891    ,445,445,445
BEGIN DESCRIPTION:
Stream0377 20.0
END DESCRIPTION:
XS GIS Cut Line= 3
      2476625.01       13858175.        2475975.       13857775.
      2475174.98     13858025.01
#Sta/Elev= 30
  4240.4   520.3  4275.6   520.2  4306.1  518.94  4321.5  519.26  4380.6  517.99
    4487  517.31  4574.7  513.49  4690.6  512.27  4843.3  505.24  4882.4  504.62
  4891.2  504.08  4891.7  503.58  4899.1  503.58  4899.6  504.08  4932.1  505.15
  4937.9  506.22  4953.4  506.83  4968.4  506.88  5000.7  504.93  5014.1   504.8
  5090.1  507.26  5117.3  507.25  5122.5  506.08    5155  505.72  5171.3  504.77
  5239.4  508.28    5276  511.54  5322.6  513.93  5587.7  515.52  5841.8  523.83
#Mann= 6 ,-1 , 0
  4240.4     .12       0  4380.6     .05       0  4882.4      .1       0
  4891.2     .05       0  4899.6      .1       0  5239.4     .05       0
Bank Sta=4891.2,4899.6
XS Rating Curve= 0 ,0
Exp/Cntr=0.3,0.1

Type RM Length L Ch R = 1 ,9446    ,431,431,431
BEGIN DESCRIPTION:
Stream0377 19.0
END DESCRIPTION:
XS GIS Cut Line= 3
        2477125.       13858125.        2475925.       13857425.
      2475124.98     13857975.01
#Sta/Elev= 30
  3610.5  522.79  3704.4  518.75  3726.3  515.42  3807.3  515.71  3865.2   522.2
  3880.5  521.02  3896.2  517.12  3929.6  516.22  3960.7  516.99  4005.8     516
  4195.6     517  4217.1   518.4  4291.5  519.11  4430.4  516.17  4633.8  514.63
  4692.5  513.12  4837.7  505.02  4860.7  505.07  4905.9  505.65  5009.1  503.34
  5009.6  502.84  5017.5  503.34  5114.8  505.26  5154.5  508.64  5201.4  511.84
  5323.8  515.11  5568.7  514.58  5661.4  515.84  5667.5  514.72  5970.6  525.15
#Mann= 7 ,-1 , 0
  3610.5    .045       0  3929.6     .12       0  4005.8     .05       0
  4860.7      .1       0  5009.1     .05       0  5017.5      .1       0
  5154.5     .05       0
Bank Sta=5009.1,5017.5
XS Rating Curve= 0 ,0
Exp/Cntr=0.3,0.1

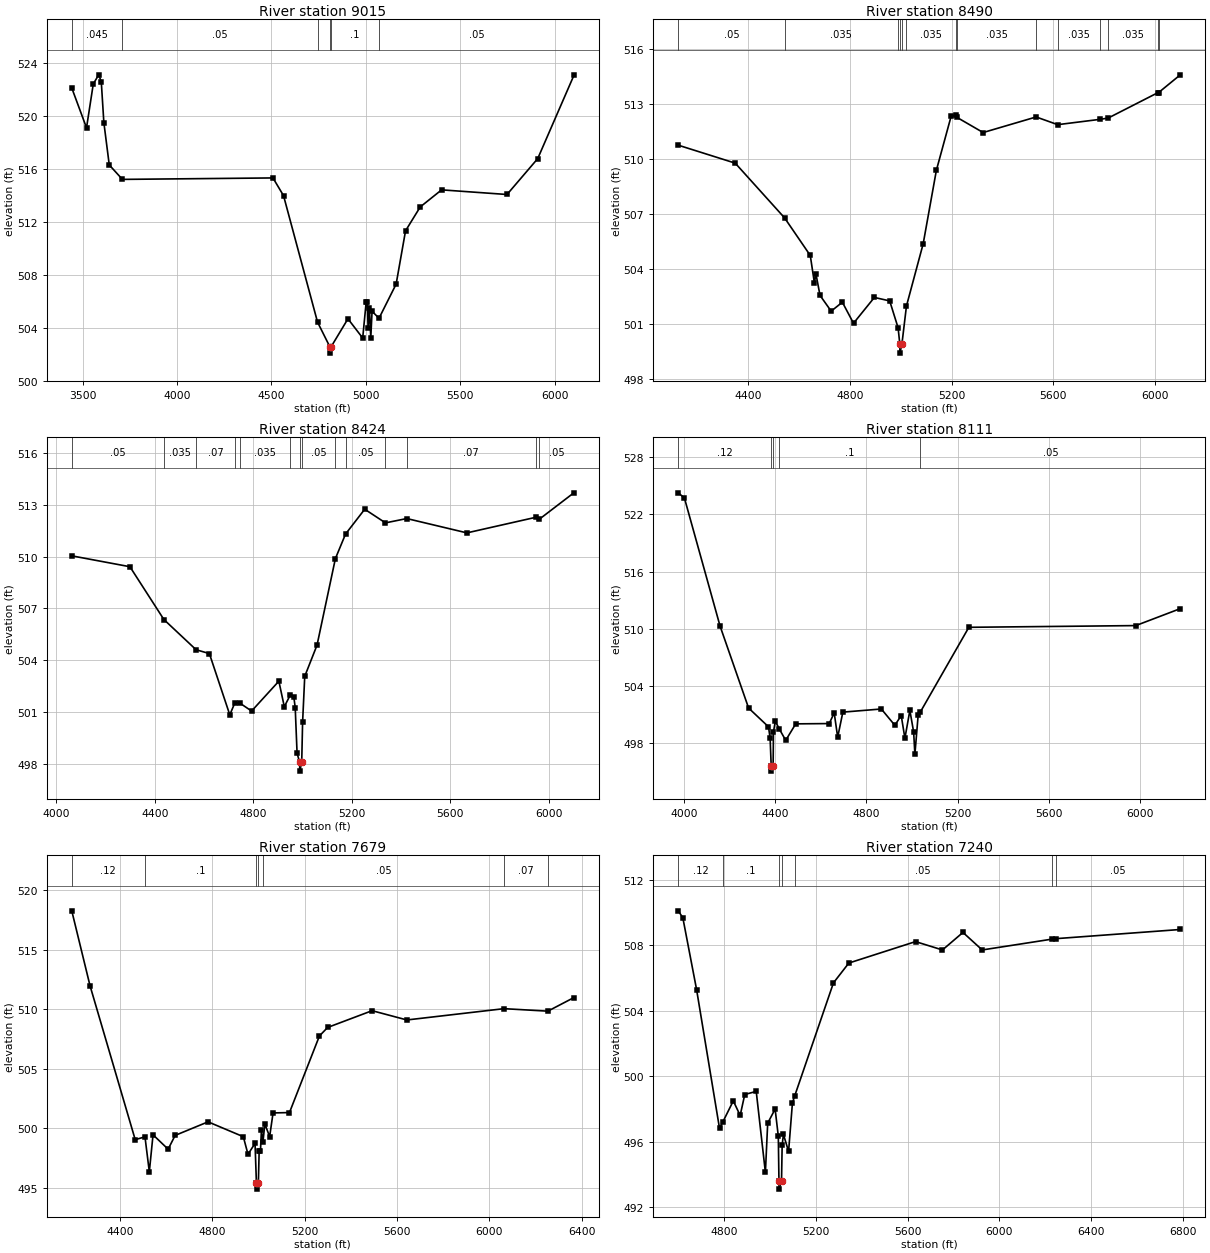
Type RM Length L Ch R = 1 ,9015    ,525,525,525
BEGIN DESCRIPTION:
Stream0377 18.0
END DESCRIPTION:
XS GIS Cut Line= 3
      2477124.98     13858024.99        2475925.       13857025.
      2475125.01     13857774.99
#Sta/Elev= 30
    3443  522.11  3521.1   519.1  3556.9  522.41  3585.5   523.1  3599.2  522.59
  3612.9   519.5  3641.5   516.3  3711.2  515.21  4508.4  515.32  4564.4  513.98
  4744.4  504.44  4808.8   502.6  4809.3   502.1  4817.2   502.6  4905.4  504.69
  4983.5  503.24  5001.8  505.93  5008.5  505.93  5012.1  503.97    5019  505.54
  5026.3  503.25  5033.1  505.26  5069.9  504.73  5160.6  507.31  5210.4  511.33
  5288.1  513.13  5401.4  514.42  5747.7  514.07  5910.4  516.78  6101.6  523.05
#Mann= 6 ,-1 , 0
    3443    .045       0  3711.2     .05       0  4744.4      .1       0
  4808.8     .05       0  4817.2      .1       0  5069.9     .05       0
Bank Sta=4808.8,4817.2
XS Rating Curve= 0 ,0
Exp/Cntr=0.3,0.1

Type RM Length L Ch R = 1 ,8490    ,66,66,66
BEGIN DESCRIPTION:
XS6583
END DESCRIPTION:
XS GIS Cut Line= 3
      2476565.64     13856825.16      2476341.77     13856380.98
      2475038.84     13857076.82
#Sta/Elev= 30
  4124.9  510.76    4349  509.78  4543.2  506.79  4644.2  504.74  4660.5  503.23
  4666.2  503.75  4682.5  502.56  4726.4   501.7  4770.3  502.19  4814.2  501.04
  4896.3  502.45  4956.5  502.26  4989.6  500.79  4996.2  499.91  4996.7  499.41
  5004.6  499.91  5022.4  501.98  5088.2  505.38  5140.1  509.39  5197.9  512.33
  5216.4   512.4  5220.7  512.28    5324  511.45  5532.4   512.3  5617.3  511.88
  5783.6  512.17  5815.6  512.24  6010.4  513.62  6013.9  513.63  6099.4   514.6
#Mann= 14 ,-1 , 0
  4124.9     .05       0  4543.2    .035       0  4989.6     .05       0
  4996.2     .05       0  5004.6     .05       0  5022.4    .035       0
  5216.4     .05       0  5220.7    .035       0  5532.4     .07       0
  5617.3    .035       0  5783.6     .07       0  5815.6    .035       0
  6010.4     .05       0  6013.9     .07       0
Bank Sta=4996.2,5004.6
XS Rating Curve= 0 ,0
Exp/Cntr=0.3,0.1

Type RM Length L Ch R = 1 ,8424    ,313,313,313
BEGIN DESCRIPTION:
XS6582
END DESCRIPTION:
XS GIS Cut Line= 3
      2476569.19     13856775.42      2476352.43     13856309.91
      2474995.09      13857009.9
#Sta/Elev= 30
  4062.2  510.04  4298.5  509.41  4436.7  506.35  4567.6   504.6  4621.5  504.38
  4704.5  500.83  4724.9  501.52  4745.4  501.51  4793.1  501.05  4903.9  502.78
  4926.1   501.3  4949.9  501.97  4964.8  501.86  4970.4  501.25  4977.9  498.62
  4988.4  498.07  4988.9  497.57  4996.8  498.07  5000.4   500.4  5009.1  503.06
  5059.1  504.87  5133.7  509.88  5174.9   511.3  5252.9  512.74  5337.2  511.95
  5423.9   512.2  5668.3  511.37  5947.5  512.27  5962.5  512.16  6102.9  513.69
#Mann= 14 ,-1 , 0
  4062.2     .05       0  4436.7    .035       0  4567.6     .07       0
  4724.9      .1       0  4745.4    .035       0  4949.9     .05       0
  4988.4     .05       0  4996.8     .05       0  5133.7    .035       0
  5174.9     .05       0  5337.2    .035       0  5423.9     .07       0
  5947.5    .035       0  5962.5     .05       0
Bank Sta=4988.4,4996.8
XS Rating Curve= 0 ,0
Exp/Cntr=0.3,0.1

Type RM Length L Ch R = 1 ,8111    ,432,432,432
BEGIN DESCRIPTION:
Stream0377 16.0
END DESCRIPTION:
XS GIS Cut Line= 3
      2476778.78     13855730.76        2475875.       13856225.
      2474836.98      13856770.9
#Sta/Elev= 30
  3974.5  524.27  4001.6  523.73    4158  510.29  4283.2  501.69  4370.5  499.72
  4377.7  498.52  4382.4  495.57  4382.9  495.07  4390.8  495.57  4392.3  499.18
  4400.5  500.31    4417  499.53  4446.1   498.3    4490  500.03    4637  500.06
  4658.8  501.18  4674.1  498.63  4696.8  501.26  4865.6  501.59  4924.8  499.88
  4952.9   500.9    4969  498.52  4990.8  501.44  5007.4  499.17  5012.8  496.82
  5027.2  500.95  5036.7  501.27  5249.6  510.16    5982  510.34  6177.4  512.12
#Mann= 5 ,-1 , 0
  3974.5     .12       0  4382.4     .05       0  4390.8     .12       0
    4417      .1       0  5036.7     .05       0
Bank Sta=4382.4,4390.8
XS Rating Curve= 0 ,0
Exp/Cntr=0.3,0.1

Type RM Length L Ch R = 1 ,7679    ,439,439,439
BEGIN DESCRIPTION:
Stream0377 15.0
END DESCRIPTION:
XS GIS Cut Line= 3
      2476675.04     13855674.99        2475875.       13855825.
      2474775.03     13856624.98
#Sta/Elev= 30
  4191.3  518.28  4270.2  511.99    4466  499.03  4508.3  499.27  4527.1  496.33
  4543.2  499.44  4608.5  498.23    4639  499.39  4781.5  500.53  4934.1  499.28
  4954.4   497.8  4984.9  498.72  4990.9  495.37  4991.4  494.87  4999.3  495.37
  5002.7  498.06  5008.4  498.06  5012.6  499.85  5019.2  498.84  5027.3  500.35
  5048.2  499.29  5062.9  501.28    5134  501.31  5263.8  507.76  5299.3  508.47
  5491.8  509.88  5642.5   509.1  6063.2  510.05  6252.8  509.84  6365.4  510.98
#Mann= 7 ,-1 , 0
  4191.3     .12       0  4508.3      .1       0  4990.9     .05       0
  4999.3      .1       0  5019.2     .05       0  6063.2     .07       0
  6252.8     .05       0
Bank Sta=4990.9,4999.3
XS Rating Curve= 0 ,0
Exp/Cntr=0.3,0.1

Type RM Length L Ch R = 1 ,7240    ,425,425,425
BEGIN DESCRIPTION:
Stream0377 14.0
END DESCRIPTION:
XS GIS Cut Line= 3
        2476525.       13855475.        2476125.       13855475.
      2474524.96     13856275.02
#Sta/Elev= 30
    4600  510.11    4620  509.69    4680   505.3    4780  496.82    4795  497.23
    4840   498.5    4870  497.61    4890  498.89    4940  499.08    4980  494.13
    4990  497.14  5022.4     498  5036.3  496.34  5039.1  493.61  5039.6  493.11
  5050.3  493.61  5053.1  495.82  5058.7  496.45  5081.1  495.41  5097.8  498.37
  5106.9  498.77  5276.7  505.71  5343.8  506.92  5634.5  508.23  5751.9  507.72
  5841.3  508.79  5925.2  507.72    6229  508.38  6246.9  508.41  6788.9  508.97
#Mann= 7 ,-1 , 0
    4600     .12       0    4795      .1       0  5039.1     .05       0
  5050.3      .1       0  5106.9     .05       0    6229    .035       0
  6246.9     .05       0
Bank Sta=5039.1,5050.3
XS Rating Curve= 0 ,0
Exp/Cntr=0.3,0.1

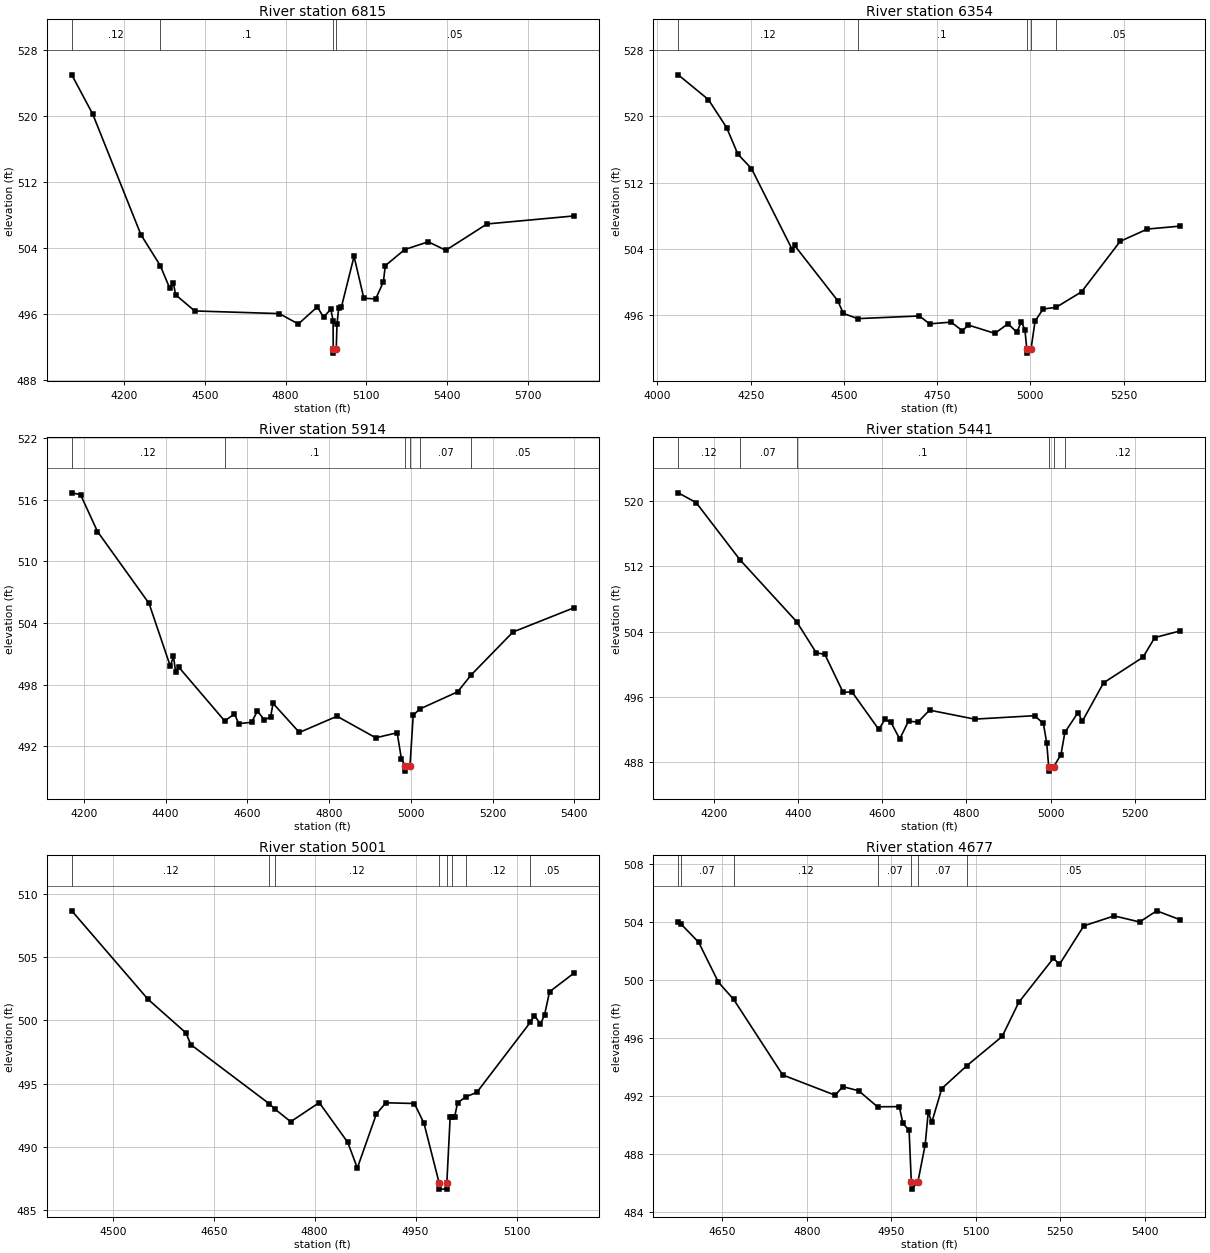
Type RM Length L Ch R = 1 ,6815    ,461,461,461
BEGIN DESCRIPTION:
Stream0377 13.0
END DESCRIPTION:
XS GIS Cut Line= 3
      2476474.99     13854375.02        2475875.       13855175.
      2475143.41     13855641.04
#Sta/Elev= 30
  4004.4  524.98  4082.5  520.21  4261.7   505.6  4333.5  501.87  4367.9  499.19
  4382.5   499.7  4390.8  498.32  4461.7  496.37  4776.3  496.05  4847.1  494.79
  4917.9  496.87  4940.8  495.61  4967.9  496.59  4976.3   495.2  4976.9  491.76
  4977.4  491.26  4988.1  491.76  4990.8  494.77  4997.1  496.67  5007.3  496.84
  5054.3  502.98  5090.7  497.91  5134.8  497.83  5163.5   499.9  5170.4  501.85
  5242.2   503.8  5330.3  504.75  5395.6  503.72  5548.7  506.91  5871.8  507.88
#Mann= 4 ,-1 , 0
  4004.4     .12       0  4333.5      .1       0  4976.9     .05       0
  4988.1     .05       0
Bank Sta=4976.9,4988.1
XS Rating Curve= 0 ,0
Exp/Cntr=0.3,0.1

Type RM Length L Ch R = 1 ,6354    ,440,440,440
BEGIN DESCRIPTION:
Stream0377 12.0
END DESCRIPTION:
XS GIS Cut Line= 3
      2476425.04     13854324.98        2475625.       13854825.
      2475424.98     13855175.04
#Sta/Elev= 30
  4055.7  525.01  4136.5  522.03  4185.5  518.65  4215.5  515.45  4252.1  513.71
  4361.8  503.91  4367.7  504.44  4483.2  497.79  4498.6  496.24    4537  495.61
  4702.6  495.93  4729.7  494.98  4787.5  495.19  4818.1  494.14  4833.5  494.84
  4904.8  493.83  4940.2  494.99  4963.8  493.98  4976.1  495.24  4985.6  494.23
  4990.5  491.95    4991  491.45  5001.9  491.95  5012.8  495.32  5034.4  496.77
    5069  496.97  5137.4  498.84    5241  504.93  5313.7  506.41  5402.3  506.77
#Mann= 5 ,-1 , 0
  4055.7     .12       0    4537      .1       0  4990.5     .05       0
  5001.9      .1       0    5069     .05       0
Bank Sta=4990.5,5001.9
XS Rating Curve= 0 ,0
Exp/Cntr=0.3,0.1

Type RM Length L Ch R = 1 ,5914    ,473,473,473
BEGIN DESCRIPTION:
Stream0377 11.0
END DESCRIPTION:
XS GIS Cut Line= 3
      2475675.01     13853774.96        2475425.       13854575.
        2475175.       13854875.
#Sta/Elev= 30
  4170.2  516.69  4191.7  516.51  4233.1  512.92  4359.3  505.91  4411.2   499.8
  4419.1  500.74  4424.3  499.24  4432.2  499.69  4544.3  494.46  4568.4  495.12
  4578.8  494.19  4610.3  494.32  4624.4  495.42  4641.7  494.55  4656.9  494.85
  4662.7  496.17  4727.1  493.33  4819.3  494.91  4914.1  492.81  4966.5   493.3
    4977  490.72  4986.4  490.06  4986.9  489.56  4997.9  490.06  5005.8  495.02
  5022.1  495.62  5114.5  497.29  5147.2  498.92  5249.9  503.12  5398.9  505.48
#Mann= 6 ,-1 , 0
  4170.2     .12       0  4544.3      .1       0  4986.4     .05       0
  4997.9      .1       0  5022.1     .07       0  5147.2     .05       0
Bank Sta=4986.4,4997.9
XS Rating Curve= 0 ,0
Exp/Cntr=0.3,0.1

Type RM Length L Ch R = 1 ,5441    ,440,440,440
BEGIN DESCRIPTION:
Stream0377 10.0
END DESCRIPTION:
XS GIS Cut Line= 3
      2475575.03     13853674.97        2475025.       13854375.
        2474725.       13854425.
#Sta/Elev= 30
  4114.3  521.02  4156.8  519.83  4260.8  512.84  4395.9  505.24  4442.4  501.44
  4463.2  501.22  4506.6  496.57  4527.4  496.65  4591.5  492.03    4606  493.27
  4620.4  492.91  4641.2  490.86  4662.1  493.06  4684.6  492.93  4712.1   494.4
  4819.3   493.3  4962.1  493.72  4982.9  492.77    4991  490.36  4995.6  487.43
  4996.1  486.93  5007.1  487.43  5024.8  488.96  5034.1  491.68  5065.4  494.11
  5075.5  493.03  5126.2  497.75    5220  500.88  5247.9  503.29  5308.7  504.11
#Mann= 6 ,-1 , 0
  4114.3     .12       0  4260.8     .07       0  4395.9      .1       0
  4995.6     .05       0  5007.1      .1       0  5034.1     .12       0
Bank Sta=4995.6,5007.1
XS Rating Curve= 0 ,0
Exp/Cntr=0.3,0.1

Type RM Length L Ch R = 1 ,5001    ,324,324,324
BEGIN DESCRIPTION:
Stream0377 9.0
END DESCRIPTION:
XS GIS Cut Line= 3
      2475125.01     13853674.99        2474725.       13854075.
      2474574.98     13854175.01
#Sta/Elev= 30
  4439.1  508.68  4552.3  501.68  4608.8  499.01  4615.9  498.09  4732.8  493.39
  4741.4  492.96  4764.4  491.98  4806.8  493.49  4849.2  490.34  4863.4  488.31
  4891.7  492.59  4905.8  493.48  4948.2  493.42  4962.4  491.86  4984.9  487.14
  4985.4  486.64  4995.9  486.64  4996.4  487.14  5001.3  492.32  5003.4  492.32
  5007.8  492.32  5012.3  493.47  5024.5  493.95  5040.9   494.3  5120.4  499.85
  5126.5  500.39  5135.5  499.72  5141.5  500.42    5149  502.27  5185.1  503.74
#Mann= 8 ,-1 , 0
  4439.1     .12       0  4732.8      .1       0  4741.4     .12       0
  4984.9     .05       0  4996.4     .12       0  5003.4     .05       0
  5024.5     .12       0  5120.4     .05       0
Bank Sta=4984.9,4996.4
XS Rating Curve= 0 ,0
Exp/Cntr=0.3,0.1

Type RM Length L Ch R = 1 ,4677    ,395,395,395
BEGIN DESCRIPTION:
Stream0377 8.0
END DESCRIPTION:
XS GIS Cut Line= 3
      2474925.02     13853524.99      2474602.31     13853777.62
      2474421.63     13854223.79
#Sta/Elev= 30
  4571.7  504.02  4576.1  503.89  4607.9  502.61  4643.1  499.84  4669.9  498.67
  4757.1  493.44  4850.2  492.04  4863.8  492.63  4891.8  492.35  4925.4  491.24
  4964.1  491.25  4970.5  490.09  4981.5  489.61  4985.4  486.05  4985.9  485.55
  4997.1  486.05    5010  488.61  5015.4  490.85  5021.9  490.18  5039.5   492.5
    5084  494.08  5146.7   496.1  5176.2  498.46  5237.6   501.5  5248.4  501.08
  5291.6  503.74  5345.5  504.43  5390.7  504.01    5421  504.78  5462.9  504.16
#Mann= 7 ,-1 , 0
  4571.7     .12       0  4576.1     .07       0  4669.9     .12       0
  4925.4     .07       0  4985.4     .05       0  4997.1     .07       0
    5084     .05       0
Bank Sta=4985.4,4997.1
XS Rating Curve= 0 ,0
Exp/Cntr=0.3,0.1