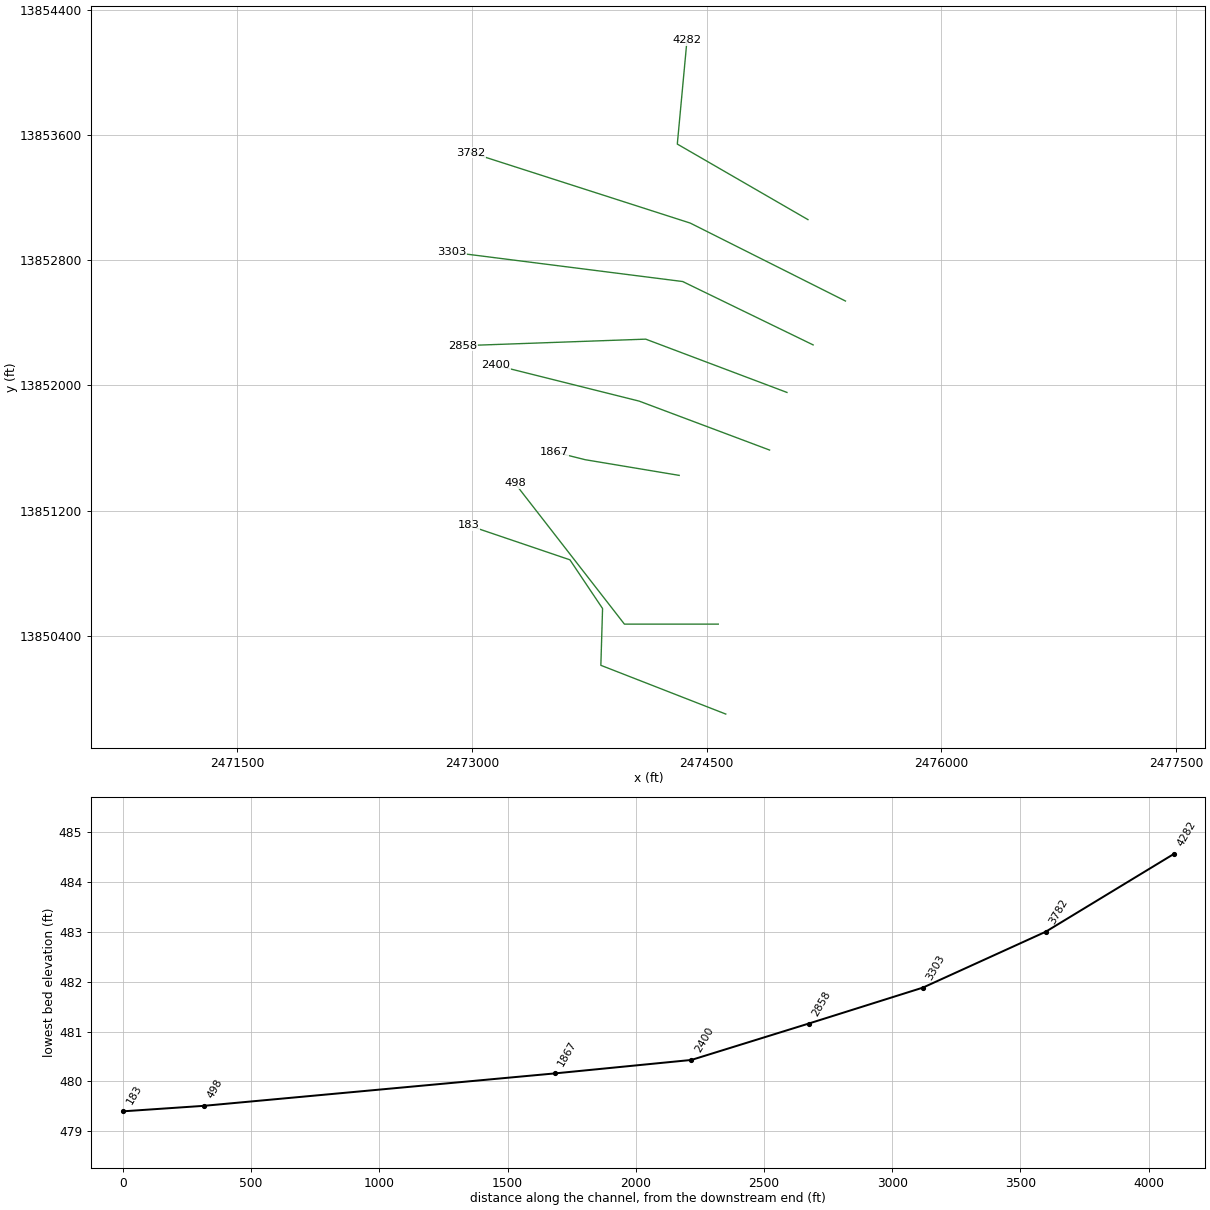
HEC-RAS study Stream0377.prj: Stream0377 Base Level Engineering

--- Stream0377.g01 (geometry) --- (continued)

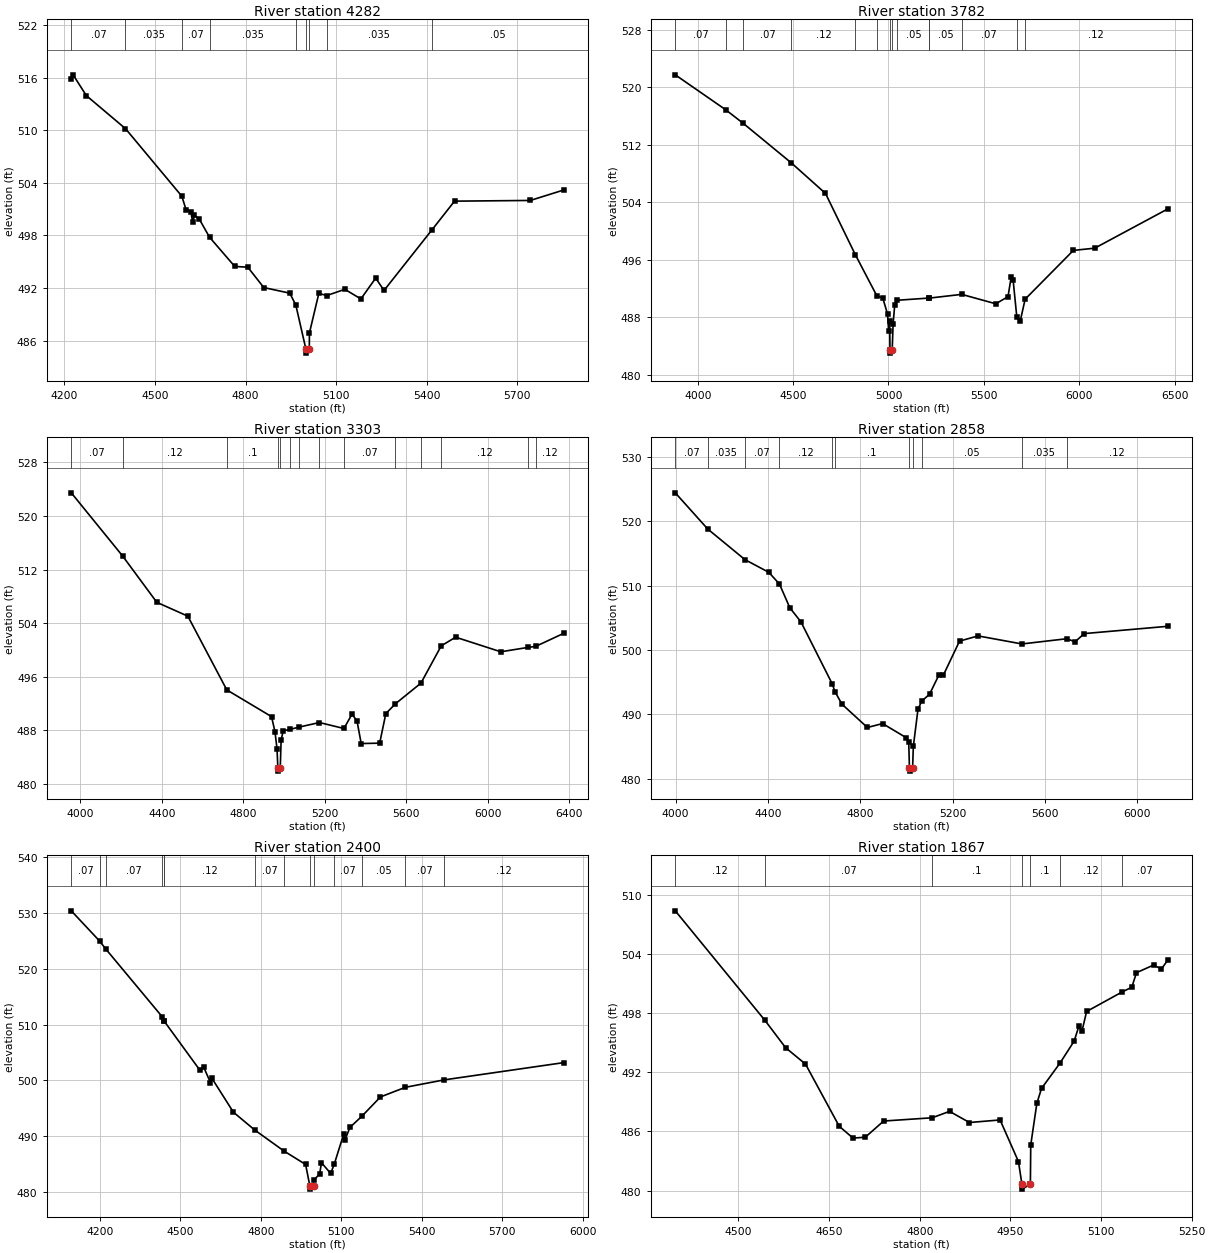
Type RM Length L Ch R = 1 ,4282    ,500,500,500
BEGIN DESCRIPTION:
Stream0377 7.0
END DESCRIPTION:
XS GIS Cut Line= 3
      2475148.09     13853058.53       2474313.1     13853541.02
      2474375.03     13854204.87
#Sta/Elev= 30
  4222.6  515.92  4228.7  516.35  4272.4  513.98  4402.2   510.2  4588.7  502.49
  4603.4  500.89  4618.9  500.67    4625   499.5  4630.7   500.3  4646.5  499.88
  4680.6   497.8  4764.2  494.46  4807.3  494.38  4860.4  492.05  4946.5  491.41
  4966.5  490.05  4999.6  485.06  5000.1  484.56  5011.3  485.06  5011.5  486.85
  5042.7  491.38  5069.3  491.14  5128.9  491.85    5182  490.75  5231.1  493.13
  5258.7  491.72  5417.5  498.64  5492.3  501.92  5743.4     502  5853.7  503.19
#Mann= 9 ,-1 , 0
  4222.6     .07       0  4402.2    .035       0  4588.7     .07       0
  4680.6    .035       0  4966.5     .05       0  4999.6     .05       0
  5011.3     .05       0  5069.3    .035       0  5417.5     .05       0
Bank Sta=4999.6,5011.3
XS Rating Curve= 0 ,0
Exp/Cntr=0.3,0.1

Type RM Length L Ch R = 1 ,3782    ,479,479,479
BEGIN DESCRIPTION:
Stream0377 6.0
END DESCRIPTION:
XS GIS Cut Line= 3
       2475387.8     13852538.57       2474395.8     13853036.41
      2472994.47     13853486.31
#Sta/Elev= 30
  3882.1  521.74  4145.8  516.89  4238.7  514.98  4491.2  509.47  4669.8  505.23
  4826.7  496.68  4938.6     491  4970.5  490.65  4995.1  488.44  5000.9  486.13
  5006.2  487.47    5008   483.5  5008.5     483  5019.7   483.5  5024.4   487.1
    5033  489.74  5046.5  490.36  5214.3  490.67  5214.6  490.66  5384.1  491.18
  5562.6  489.87  5626.8  490.86    5644  493.65  5653.7  493.18  5673.1  488.01
    5691  487.46  5716.7  490.51  5969.6   497.3  6081.6  497.61  6463.8  503.06
#Mann= 14 ,-1 , 0
  3882.1     .07       0  4145.8    .035       0  4238.7     .07       0
  4491.2     .12       0  4826.7      .1       0  4938.6     .12       0
    5008     .05       0  5019.7     .12       0  5046.5     .05       0
  5214.3     .07       0  5214.6     .05       0  5384.1     .07       0
  5673.1    .035       0  5716.7     .12       0
Bank Sta=5008,5019.7
XS Rating Curve= 0 ,0
Exp/Cntr=0.3,0.1

Type RM Length L Ch R = 1 ,3303    ,445,445,445
BEGIN DESCRIPTION:
Stream0377 5.0
END DESCRIPTION:
XS GIS Cut Line= 3
      2475181.28     13852258.32      2474347.25     13852663.16
      2472869.07     13852850.53
#Sta/Elev= 30
  3955.7  523.46  4207.8  514.02  4375.6   507.1    4528  505.03  4719.1  494.02
  4938.9  490.02  4955.6  487.78  4965.7  485.23  4969.9  482.38  4970.4  481.88
  4981.7  482.38  4985.9  486.49  4995.9   487.9  5030.3  488.12  5074.3  488.46
    5174  489.14  5294.2  488.25  5334.2   490.4  5358.8  489.33    5379     486
  5469.7  486.06  5499.9  490.47  5546.6  491.93  5672.4  495.03    5772   500.6
  5842.7  501.89  6064.4  499.71  6197.1  500.36  6235.9  500.52  6372.8  502.46
#Mann= 14 ,-1 , 0
  3955.7     .07       0  4207.8     .12       0  4719.1      .1       0
  4969.9     .05       0  4981.7      .1       0  5030.3     .05       0
  5074.3     .07       0    5174     .05       0  5294.2     .07       0
  5546.6     .05       0  5672.4    .035       0    5772     .12       0
  6197.1     .07       0  6235.9     .12       0
Bank Sta=4969.9,4981.7
XS Rating Curve= 0 ,0
Exp/Cntr=0.3,0.1

Type RM Length L Ch R = 1 ,2858    ,458,458,458
BEGIN DESCRIPTION:
Stream0377 4.0
END DESCRIPTION:
XS GIS Cut Line= 3
      2475013.94     13851954.82      2474111.14      13852295.1
      2472944.48     13852253.44
#Sta/Elev= 30
    3999   524.4  4139.7  518.77  4300.8  514.02    4404  512.05  4450.2  510.23
  4495.2  506.53  4542.9  504.37  4679.4  494.67  4690.2  493.53  4720.9  491.56
    4831  487.94  4896.8  488.55    5000  486.34    5010  485.71  5013.1  481.66
  5013.6  481.16  5026.9  481.66    5030     485    5050  490.74  5065.8  492.02
    5100   493.1  5140.1  496.04  5160.1  496.08  5230.1  501.36  5310.2  502.17
  5500.3  500.92  5694.5  501.73  5730.4  501.26  5770.5  502.53  6131.2  503.66
#Mann= 11 ,-1 , 0
    3999     .07       0  4139.7    .035       0  4300.8     .07       0
  4450.2     .12       0  4679.4     .07       0  4690.2      .1       0
  5013.1     .05       0  5026.9      .1       0  5065.8     .05       0
  5500.3    .035       0  5694.5     .12       0
Bank Sta=5013.1,5026.9
XS Rating Curve= 0 ,0
Exp/Cntr=0.3,0.1

Type RM Length L Ch R = 1 ,2400    ,533,533,533
BEGIN DESCRIPTION:
Stream0377 3.0
END DESCRIPTION:
XS GIS Cut Line= 3
       2474902.8     13851586.77      2474069.47     13851899.27
      2473152.78     13852128.44
#Sta/Elev= 30
  4093.9  530.42  4199.3     525    4222  523.59  4433.8  511.33  4439.5   510.7
  4440.8  510.56  4572.2  501.86  4587.7  502.31  4612.6  499.57    4618  500.34
  4698.1  494.25  4777.5  491.05  4887.1  487.26  4967.3  484.86  4983.3  480.93
  4983.8  480.43  4997.2  480.93  4998.8  482.11  5019.4  483.14  5026.4  485.17
  5060.7  483.25  5074.1  484.94  5108.8  490.25    5114   489.3  5132.8  491.54
  5176.4   493.5  5246.2  496.99    5339  498.72  5483.2  500.05  5928.8  503.15
#Mann= 14 ,-1 , 0
  4093.9     .07       0  4199.3    .035       0    4222     .07       0
  4433.8    .035       0  4439.5     .07       0  4440.8     .12       0
  4777.5     .07       0  4887.1      .1       0  4983.3     .05       0
  4997.2      .1       0  5074.1     .07       0  5176.4     .05       0
    5339     .07       0  5483.2     .12       0
Bank Sta=4983.3,4997.2
XS Rating Curve= 0 ,0
Exp/Cntr=0.3,0.1

Type RM Length L Ch R = 1 ,1867    ,1369,1369,1369
BEGIN DESCRIPTION:
Stream0377 2.0
END DESCRIPTION:
XS GIS Cut Line= 3
      2474325.01       13851425.        2473725.       13851525.
      2473525.04     13851574.99
#Sta/Elev= 30
  4395.7  508.36  4543.9  497.27  4578.2  494.49  4611.1  492.83  4666.9  486.53
  4689.7  485.33    4710  485.42  4740.4  487.06  4820.7  487.39  4849.4  488.04
  4882.3  486.91    4933  487.17  4963.4  482.95  4969.1  480.66  4969.6  480.16
  4983.1  480.66  4983.7  484.63  4993.8  488.85  5001.5  490.36  5032.3  492.95
  5055.5  495.16  5063.3  496.66  5068.4  496.15  5076.1  498.16  5134.6  500.13
  5150.9  500.62  5158.6  502.09    5187  502.87  5199.8  502.45  5210.1  503.35
#Mann= 7 ,-1 , 0
  4395.7     .12       0  4543.9     .07       0  4820.7      .1       0
  4969.1     .05       0  4983.1      .1       0  5032.3     .12       0
  5134.6     .07       0
Bank Sta=4969.1,4983.1
XS Rating Curve= 0 ,0
Exp/Cntr=0.3,0.1

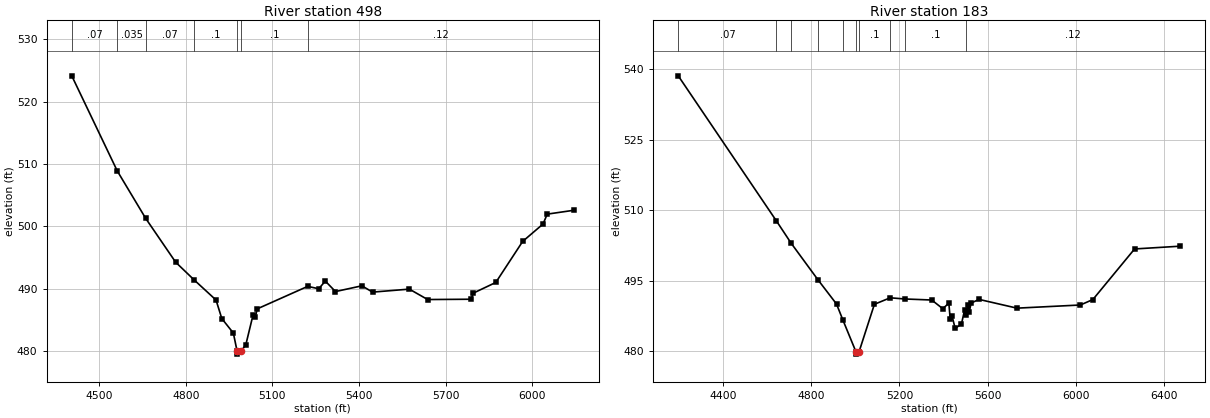
Type RM Length L Ch R = 1 ,498     ,315,315,315
BEGIN DESCRIPTION:
Stream0377 1.0
END DESCRIPTION:
XS GIS Cut Line= 3
      2474574.96       13850475.        2473975.       13850475.
      2473275.02     13851374.98
#Sta/Elev= 30
  4404.7  524.12  4562.4  508.87  4660.9  501.27  4764.7  494.25    4828  491.44
  4904.7  488.18  4924.7  485.21  4964.7  482.89  4977.6  480.01  4978.1  479.51
  4991.7  480.01  5007.8  480.99  5032.7  485.74  5040.9  485.43  5047.2  486.76
  5222.3  490.37  5260.7  489.99  5283.4  491.22  5318.7  489.54  5410.1  490.46
  5447.2  489.45  5574.7  489.93  5638.1  488.26  5789.2  488.31  5795.5  489.27
  5874.3     491  5967.5  497.58  6038.1  500.37  6052.5  501.95  6144.8  502.57
#Mann= 7 ,-1 , 0
  4404.7     .07       0  4562.4    .035       0  4660.9     .07       0
    4828      .1       0  4977.6     .05       0  4991.7      .1       0
  5222.3     .12       0
Bank Sta=4977.6,4991.7
XS Rating Curve= 0 ,0
Exp/Cntr=0.3,0.1

Type RM Length L Ch R = 1 ,183     ,0,0,0
BEGIN DESCRIPTION:
E20940
END DESCRIPTION:
XS GIS Cut Line= 5
      2474622.77     13849900.61      2473824.42     13850211.89
       2473835.4     13850574.45      2473626.66     13850885.74
      2472979.26      13851105.2
#Sta/Elev= 30
  4196.6  538.54    4642  507.71  4708.9  502.97  4829.7  495.25  4914.7  490.05
  4944.4  486.57  5002.9   479.9  5003.4   479.4    5017   479.9  5086.6  489.99
  5158.3  491.37  5224.3  491.12  5346.7   490.9  5396.8  489.06  5424.4  490.22
  5430.4  486.96  5439.4   487.4    5453  484.89  5481.4  485.77  5496.4  488.88
  5502.7  487.64  5511.4  489.83  5517.5  488.45  5525.2  490.25  5561.4  491.03
  5733.5  489.17  6021.1  489.84  6077.9     491  6267.1  501.75  6474.6  502.34
#Mann= 10 ,-1 , 0
  4196.6     .07       0    4642    .035       0  4708.9     .07       0
  4829.7     .12       0  4944.4      .1       0  5002.9     .05       0
    5017      .1       0  5158.3     .12       0  5224.3      .1       0
  5502.7     .12       0
Bank Sta=5002.9,5017
XS Rating Curve= 0 ,0
Exp/Cntr=0.3,0.1

Chan Stop Cuts=-1
Use User Specified Reach Order=0
Composite Channel Slope=5