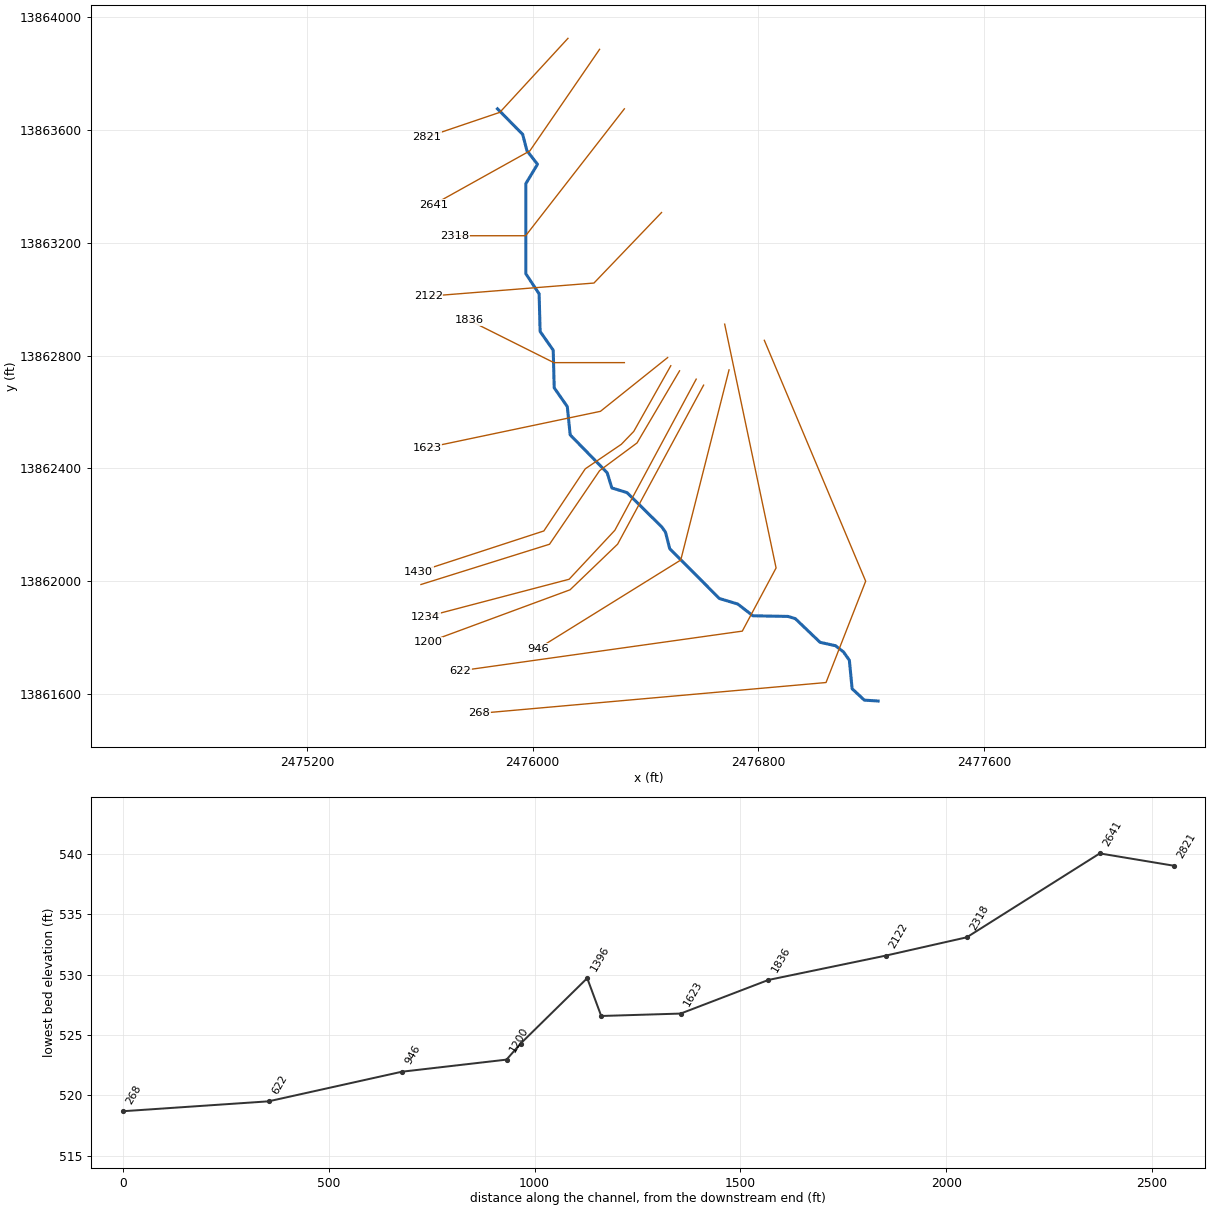
--- Stream0378.prj (project) ---

Proj Title=Stream0378 Base Level Engineering
Current Plan=p01
Default Exp/Contr=0.3,0.1
English Units
Geom File=g01
Flow File=f01
Plan File=p01
Y Axis Title=Elevation
X Axis Title(PF)=Main Channel Distance
X Axis Title(XS)=Station
BEGIN DESCRIPTION:
Stream0378
END DESCRIPTION:
DSS Export Rating Curves= 0
DSS Export Rating Curve Sorted= 0
DSS Export Volume Flow Curves= 0
DXF OffsetX= 0
DXF OffsetY= 0
DXF ScaleX= 1
DXF ScaleY= 10

--- Stream0378.p01 (plan) ---

Plan Title=Multiple Run
Short Identifier=Multiple
Geom File=g01
Flow File=f01
Subcritical Flow
K Sum by GR= 0
Std Step Tol= 0.01
Critical Tol= 0.01
Num of Std Step Trials= 20
Max Error Tol= 0.3
Flow Tol Ratio= 0.001
Split Flow NTrial= 30
Split Flow Tol= 0.02
Split Flow Ratio= 0.02
Log Output Level= 0
Friction Slope Method= 1
Unsteady Friction Slope Method= 2
Unsteady Bridges Friction Slope Method= 1
Parabolic Critical Depth
Global Vel Dist=  1 , 1 , 1
Global Log Level= 0
CheckData=True
Encroach Param= -1, 0, 0, 0
BEGIN DESCRIPTION:
Multiple Run
END DESCRIPTION:

--- Stream0378.f01 (steady flow) ---

Flow Title=Multiple
Number of Profiles=7
Profile Names=10-year,25-year,50-year,1pct_min,100-year,1pct_plu,500-year
River Rch & RM= Stream0378,Reach-1,2821
     430     676     894     574    1146    2286    1859
Boundary for River Rch & Prof#=Stream0378,Reach-1,1
Up Type=0
Dn Type=3
Dn Slope=0.005
Boundary for River Rch & Prof#=Stream0378,Reach-1,2
Up Type=0
Dn Type=3
Dn Slope=0.005
Boundary for River Rch & Prof#=Stream0378,Reach-1,3
Up Type=0
Dn Type=3
Dn Slope=0.005
Boundary for River Rch & Prof#=Stream0378,Reach-1,4
Up Type=0
Dn Type=3
Dn Slope=0.005
Boundary for River Rch & Prof#=Stream0378,Reach-1,5
Up Type=0
Dn Type=3
Dn Slope=0.005
Boundary for River Rch & Prof#=Stream0378,Reach-1,6
Up Type=0
Dn Type=3
Dn Slope=0.005
Boundary for River Rch & Prof#=Stream0378,Reach-1,7
Up Type=0
Dn Type=3
Dn Slope=0.005

--- Stream0378.g01 (geometry) ---

Geom Title=Existing Conditions
Program Version=4.10

River Reach=Stream0378      ,Reach-1
Reach XY= 30
        2475875.       13863675.      2475964.32      13863584.7
      2475979.45     13863526.65      2476016.96     13863478.32
      2475975.66     13863409.84      2475975.52     13863090.22
      2476022.73     13863019.06      2476026.23     13862885.51
      2476072.73     13862819.06      2476076.23     13862685.51
      2476122.64     13862619.02      2476132.86     13862518.83
      2476264.11     13862384.42      2476280.62     13862330.62
      2476334.42     13862314.11      2476458.35     13862191.67
      2476471.02     13862173.35      2476485.78     13862115.32
      2476661.78     13861938.62      2476727.17     13861918.86
      2476780.93     13861877.25      2476905.01     13861875.02
      2476931.18     13861867.17      2477018.98     13861783.19
       2477073.6     13861771.13      2477102.28     13861748.89
      2477122.93     13861719.29      2477132.64     13861618.56
      2477175.99     13861578.12        2477225.       13861575.

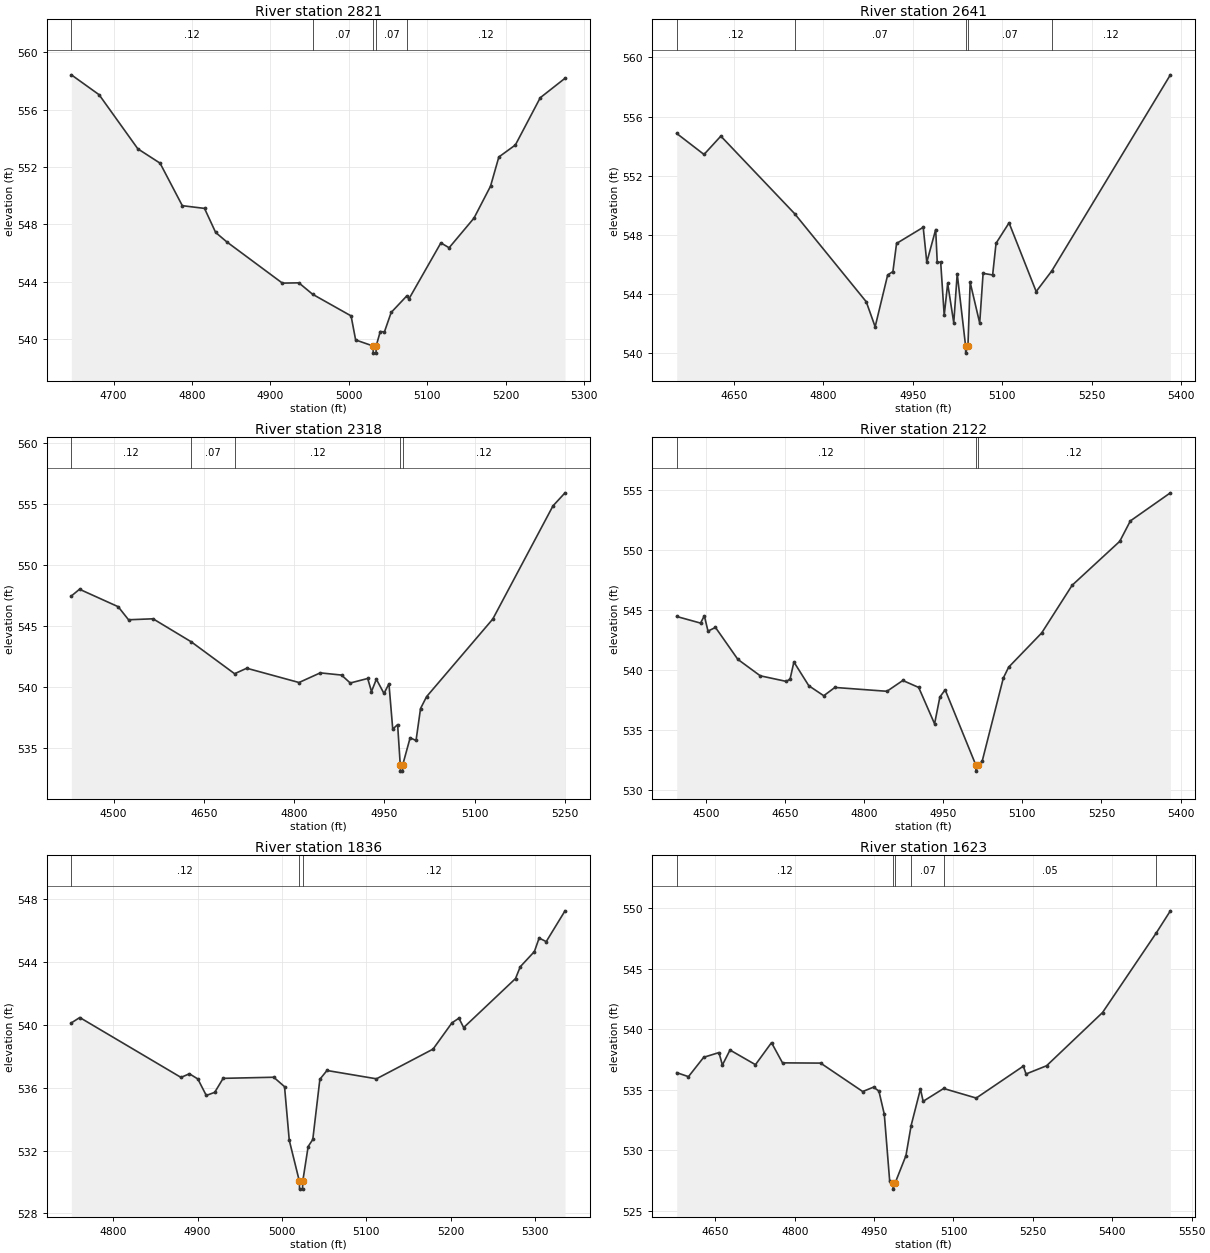
Type RM Length L Ch R = 1 ,2821    ,180,180,180
BEGIN DESCRIPTION:
Stream0378 5.0
END DESCRIPTION:
XS GIS Cut Line= 3
      2476124.99     13863924.99      2475883.42     13863662.54
      2475625.04     13863575.01
#Sta/Elev= 30
  4646.2  558.44  4681.6  557.05    4731  553.27  4759.3  552.27  4787.7   549.3
    4816  549.11  4830.2  547.43  4844.4  546.77  4915.3  543.89  4936.3  543.91
  4953.9  543.11  5002.9   541.6  5008.7  539.92  5030.9   539.5  5031.2     539
  5034.7     539  5034.9   539.5  5040.1  540.51  5045.4  540.48    5054  541.84
  5073.8  542.99  5076.8   542.8  5117.4   546.7  5127.9  546.36  5159.6  548.43
  5180.7  550.66  5191.3   552.7  5212.4  553.54  5244.1  556.84  5275.7   558.2
#Mann= 5 ,-1 , 0
  4646.2     .12       0  4953.9     .07       0  5030.9     .05       0
  5034.9     .07       0  5073.8     .12       0
Bank Sta=5030.9,5034.9
XS Rating Curve= 0 ,0
Exp/Cntr=0.3,0.1

Type RM Length L Ch R = 1 ,2641    ,323,323,323
BEGIN DESCRIPTION:
XS6592
END DESCRIPTION:
XS GIS Cut Line= 3
      2476237.13     13863886.03      2475989.76     13863525.82
       2475648.4      13863335.7
#Sta/Elev= 30
  4554.3  554.86  4600.1  553.44  4628.3  554.68  4751.8  549.45  4872.1  543.49
    4887   541.8    4908   545.3  4916.8  545.53  4922.9  547.43  4967.6  548.52
  4973.6  546.16  4988.5  548.37  4991.1  546.16  4996.9  546.16  5002.8  542.57
  5008.6  544.73  5018.8  542.07  5024.6  545.38  5038.6  540.52  5038.8  540.02
  5042.6  540.52  5046.3   544.8  5062.3  542.05    5068  545.41    5084   545.3
  5089.7  547.44  5111.5  548.82    5157  544.18  5183.1  545.57    5382  558.82
#Mann= 5 ,-1 , 0
  4554.3     .12       0  4751.8     .07       0  5038.6     .05       0
  5042.6     .07       0  5183.1     .12       0
Bank Sta=5038.6,5042.6
XS Rating Curve= 0 ,0
Exp/Cntr=0.3,0.1

Type RM Length L Ch R = 1 ,2318    ,196,196,196
BEGIN DESCRIPTION:
Stream0378 4.0
END DESCRIPTION:
XS GIS Cut Line= 3
        2476325.     13863674.99        2475975.       13863225.
      2475724.98       13863225.
#Sta/Elev= 30
  4429.9  547.43  4443.5  547.98  4507.7  546.55  4524.9  545.48  4565.6  545.56
  4629.2  543.67  4701.1  541.06  4721.3  541.51  4808.1  540.34  4843.4  541.13
  4878.7  540.95  4893.2   540.3  4922.2  540.67  4928.5   539.6  4936.6  540.61
  4949.3  539.44  4957.5  540.24  4963.8  536.52  4971.9  536.89  4976.3  533.58
  4976.5  533.08    4980  533.08  4980.3  533.58  4992.7  535.81  5002.5  535.59
    5010  538.21    5020  539.18    5130  545.54    5230  554.81    5250  555.88
#Mann= 5 ,-1 , 0
  4429.9     .12       0  4629.2     .07       0  4701.1     .12       0
  4976.3     .05       0  4980.3     .12       0
Bank Sta=4976.3,4980.3
XS Rating Curve= 0 ,0
Exp/Cntr=0.3,0.1

Type RM Length L Ch R = 1 ,2122    ,286,286,286
BEGIN DESCRIPTION:
XS6588
END DESCRIPTION:
XS GIS Cut Line= 3
      2476456.78     13863307.25      2476217.19     13863057.24
      2475629.33     13863010.42
#Sta/Elev= 30
  4444.8  544.45    4490   543.9  4497.2  544.51  4504.1  543.23  4518.3  543.54
  4560.7  540.88  4603.2  539.51  4652.9  539.04  4659.8  539.25    4667  540.66
  4695.3  538.68  4723.6  537.85  4744.7  538.54  4843.4  538.22  4873.5  539.12
  4903.6  538.54  4933.7  535.51  4943.8  537.75  4953.8  538.34    5012  532.07
  5012.2  531.57    5016  532.07    5024   532.4  5064.1  539.33  5074.2  540.23
  5136.8  543.08  5194.5  547.05  5284.8  550.71  5304.9  552.41  5380.8  554.75
#Mann= 3 ,-1 , 0
  4444.8     .12       0    5012     .05       0    5016     .12       0
Bank Sta=5012,5016
XS Rating Curve= 0 ,0
Exp/Cntr=0.3,0.1

Type RM Length L Ch R = 1 ,1836    ,213,213,213
BEGIN DESCRIPTION:
Stream0378 3.0
END DESCRIPTION:
XS GIS Cut Line= 3
      2476325.01       13862775.        2476075.       13862775.
      2475775.02     13862924.99
#Sta/Elev= 30
  4750.3  540.13  4760.3  540.47  4880.3  536.66  4890.3  536.89  4900.3  536.56
  4910.3  535.51  4920.3  535.71  4930.3   536.6  4990.3  536.67  5003.1  536.07
  5008.7  532.66  5020.7  530.05  5020.9  529.55  5024.4  529.55  5024.7  530.05
  5031.1  532.26  5036.6  532.71    5045  536.54  5053.4   537.1  5112.1  536.57
  5179.2  538.46  5201.6  540.13  5209.9  540.43  5215.5  539.83    5277  542.95
  5282.6   543.7  5299.4  544.67    5305  545.53  5313.4   545.3  5335.7  547.26
#Mann= 3 ,-1 , 0
  4750.3     .12       0  5020.7     .05       0  5024.7     .12       0
Bank Sta=5020.7,5024.7
XS Rating Curve= 0 ,0
Exp/Cntr=0.3,0.1

Type RM Length L Ch R = 1 ,1623    ,193,193,193
BEGIN DESCRIPTION:
E20941
END DESCRIPTION:
XS GIS Cut Line= 3
      2476478.49     13862792.97      2476240.15      13862602.3
      2475626.07     13862473.32
#Sta/Elev= 30
  4577.1   536.4  4599.3  536.07  4628.1  537.67  4656.9  538.06  4663.4  537.03
  4677.8  538.27  4725.9  537.06  4756.2  538.88    4777  537.21    4849  537.19
  4928.5  534.84  4948.9   535.2  4959.1  534.88  4969.3  532.96  4979.5  527.42
  4985.7  527.27    4986  526.77  4989.7  527.27  5010.2  529.54    5020  532.03
  5037.6  535.05  5042.7  534.03  5081.4  535.09    5143   534.3    5232  536.94
  5237.1  536.29  5275.9  536.97  5381.6  541.37  5483.1  547.95  5509.8  549.78
#Mann= 6 ,-1 , 0
  4577.1     .12       0  4985.7     .05       0  4989.7     .12       0
    5020     .07       0  5081.4     .05       0  5483.1     .12       0
Bank Sta=4985.7,4989.7
XS Rating Curve= 0 ,0
Exp/Cntr=0.3,0.1

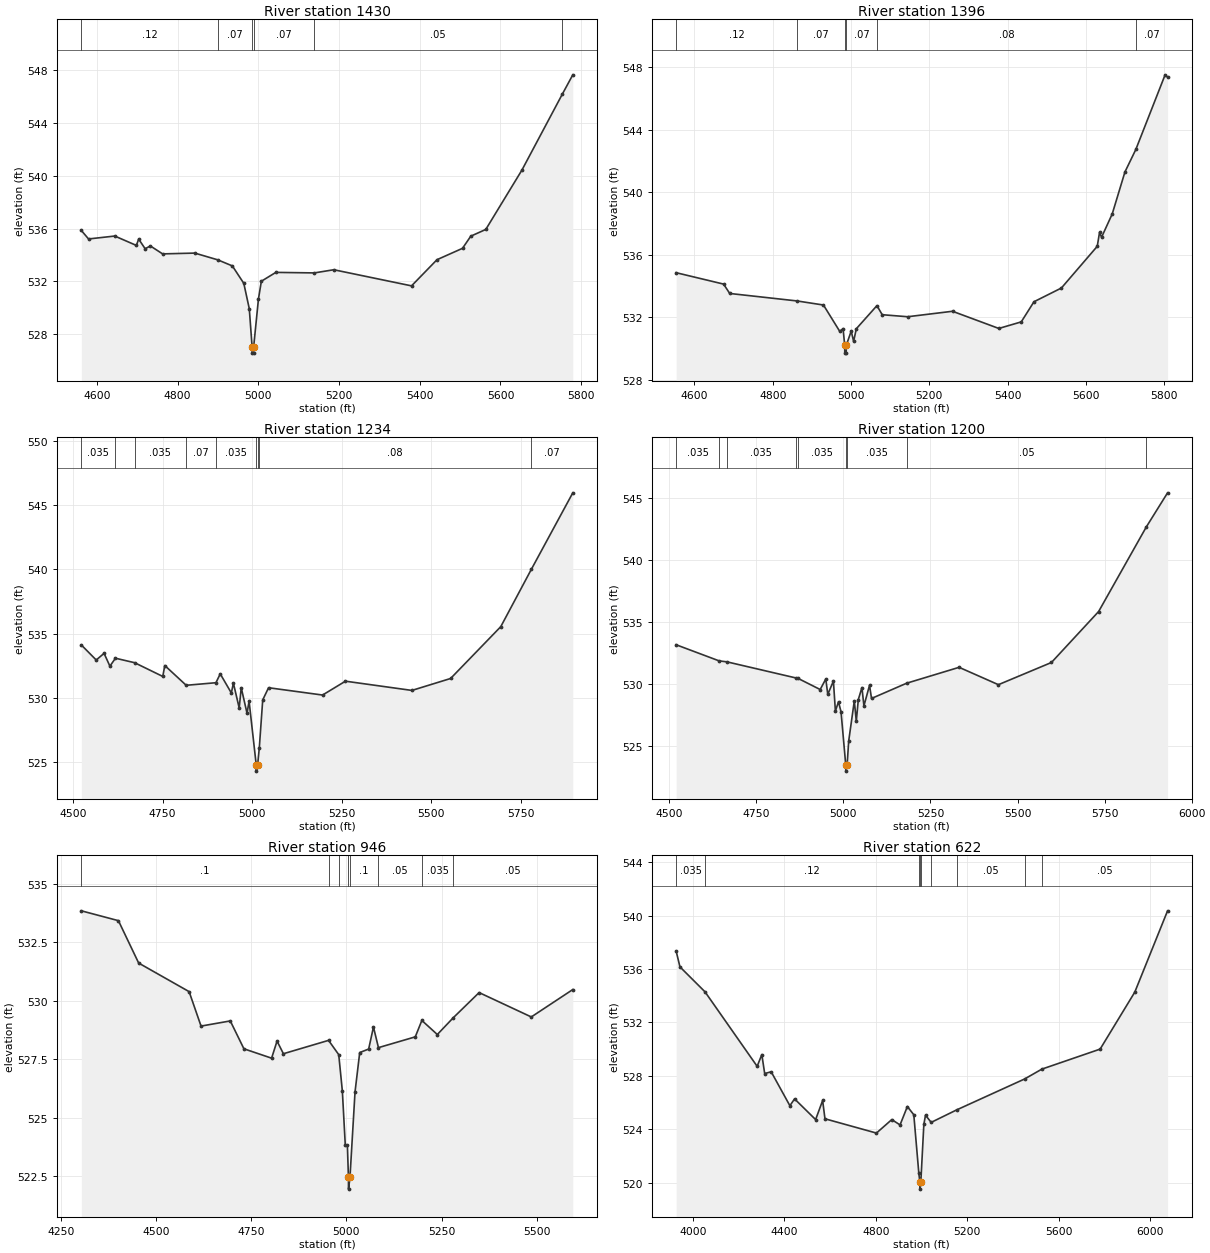
Type RM Length L Ch R = 1 ,1430    ,34,34,34
BEGIN DESCRIPTION:
XS6589
END DESCRIPTION:
XS GIS Cut Line= 6
       2476489.6     13862763.97      2476358.47     13862531.23
      2476314.22     13862485.33      2476186.36     13862398.45
      2476039.44     13862178.08      2475595.15     13862033.05
#Sta/Elev= 30
  4561.6  535.85  4579.4  535.21  4644.4  535.43  4697.9  534.72  4703.6   535.2
  4719.6  534.47  4732.6  534.68  4762.9  534.08  4842.6  534.14  4899.5  533.63
  4935.7  533.17  4964.1  531.85  4977.7  529.93  4984.6  527.07  4984.8  526.57
  4988.3  526.57  4988.6  527.07  5000.4  530.67  5007.6  532.01  5043.5  532.68
  5138.8  532.64  5187.1  532.88  5379.7  531.66  5442.8  533.64    5506   534.5
  5526.5  535.42  5563.7  535.93  5653.2  540.42  5753.2  546.16  5779.3  547.63
#Mann= 6 ,-1 , 0
  4561.6     .12       0  4899.5     .07       0  4984.6     .05       0
  4988.6     .07       0  5138.8     .05       0  5753.2     .07       0
Bank Sta=4984.6,4988.6
XS Rating Curve= 0 ,0
Exp/Cntr=0.3,0.1

Type RM Length L Ch R = 1 ,1396    ,162,162,162
BEGIN DESCRIPTION:
Stream0378 2.0
END DESCRIPTION:
XS GIS Cut Line= 5
      2476520.74     13862745.94      2476369.95     13862490.25
      2476237.17      13862391.9      2476059.57     13862130.95
      2475603.63      13861988.2
#Sta/Elev= 30
  4553.1  534.85  4674.4  534.12    4690  533.52  4862.4  533.04  4929.5  532.78
  4971.2  531.09  4979.6  531.27  4983.8   530.2    4984   529.7  4987.5   529.7
  4987.8   530.2  5000.4  531.11  5006.6  530.45  5013.4  531.26  5066.1  532.74
  5079.6  532.16  5144.5  532.03  5259.2  532.38  5377.5  531.28  5434.8   531.7
  5467.3  532.99  5537.4  533.87    5629  536.54  5634.8  537.43    5640  537.12
  5667.2  538.61  5699.7   541.3  5727.5  542.74  5802.3  547.52  5808.6  547.37
#Mann= 6 ,-1 , 0
  4553.1     .12       0  4862.4     .07       0  4983.8     .07       0
  4987.8     .07       0  5066.1     .08       0  5727.5     .07       0
Bank Sta=4983.8,4987.8
XS Rating Curve= 0 ,0
Exp/Cntr=0.3,0.1

Type RM Length L Ch R = 1 ,1234    ,34,34,34
BEGIN DESCRIPTION:
XS6590
END DESCRIPTION:
XS GIS Cut Line= 4
      2476579.76     13862716.45      2476291.27     13862180.44
      2476129.09     13862006.79      2475620.45     13861873.23
#Sta/Elev= 30
  4523.2  534.11  4564.7  532.94  4586.6  533.46  4602.9  532.46  4618.4  533.08
  4671.9  532.73  4750.5  531.66  4756.2  532.51  4815.9  530.97  4898.9  531.17
    4911  531.86    4942  530.37  4947.7  531.14  4963.9   529.2  4969.6  530.78
  4985.8  528.79  4991.5  529.74  5011.4  524.78  5011.7  524.28  5015.4  524.78
  5020.1  526.11  5029.6  529.83  5045.9  530.78  5196.7  530.21  5260.6  531.29
  5446.1  530.57  5554.2   531.5  5694.3  535.54  5779.5     540  5895.4  545.97
#Mann= 9 ,-1 , 0
  4523.2    .035       0  4618.4     .12       0  4671.9    .035       0
  4815.9     .07       0  4898.9    .035       0  5011.4    .035       0
  5015.4    .035       0  5020.1     .08       0  5779.5     .07       0
Bank Sta=5011.4,5015.4
XS Rating Curve= 0 ,0
Exp/Cntr=0.3,0.1

Type RM Length L Ch R = 1 ,1200    ,254,254,254
BEGIN DESCRIPTION:
XS6591
END DESCRIPTION:
XS GIS Cut Line= 4
      2476605.97     13862695.11       2476301.1     13862131.26
      2476132.59     13861969.49      2475629.38     13861783.69
#Sta/Elev= 30
  4519.8  533.15  4643.2  531.85  4665.9  531.77  4862.7  530.48  4870.4  530.43
  4933.4  529.54  4949.5  530.39  4955.2  529.15  4971.4  530.22  4977.1   527.8
    4986  528.56  4993.3  527.74  5006.8  523.46    5007  522.96  5010.8  523.46
  5015.2  525.37  5031.4  528.63  5037.1  526.98  5042.9  528.73  5053.3   529.7
    5059  528.22  5075.1  529.88  5080.8  528.82  5181.8  530.05  5332.3  531.33
  5445.1  529.93  5597.4  531.72  5732.9  535.83    5870  542.66  5930.8   545.4
#Mann= 9 ,-1 , 0
  4519.8    .035       0  4643.2     .12       0  4665.9    .035       0
  4862.7     .07       0  4870.4    .035       0  5006.8    .035       0
  5010.8    .035       0  5181.8     .05       0    5870     .07       0
Bank Sta=5006.8,5010.8
XS Rating Curve= 0 ,0
Exp/Cntr=0.3,0.1

Type RM Length L Ch R = 1 ,946     ,324,324,324
BEGIN DESCRIPTION:
Stream0378 1.0
END DESCRIPTION:
XS GIS Cut Line= 3
      2476696.16     13862749.29        2476525.       13862075.
      2476019.62     13861761.09
#Sta/Elev= 30
  4304.1  533.84  4401.4  533.42  4454.6  531.61  4587.1  530.39  4618.4  528.92
  4695.2  529.14    4731  527.95  4803.7  527.55    4818  528.28  4834.7  527.74
  4953.3  528.31    4980   527.7  4989.5  526.15  4997.2  523.84  5002.7  523.84
  5005.5  522.46  5005.7  521.96  5009.5  522.46  5022.8  526.11  5035.1  527.79
  5058.6  527.94  5071.2  528.88  5084.3     528    5181  528.46  5198.3  529.16
  5238.9  528.56  5280.4  529.27  5348.7  530.35  5485.7  529.31  5594.7  530.48
#Mann= 8 ,-1 , 0
  4304.1      .1       0  4953.3    .035       0    4980      .1       0
  5005.5     .06       0  5009.5      .1       0  5084.3     .05       0
  5198.3    .035       0  5280.4     .05       0
Bank Sta=5005.5,5009.5
XS Rating Curve= 0 ,0
Exp/Cntr=0.3,0.1

Type RM Length L Ch R = 1 ,622     ,354,354,354
BEGIN DESCRIPTION:
XS6587
END DESCRIPTION:
XS GIS Cut Line= 4
      2476680.73     13862911.45      2476863.03     13862046.83
      2476743.23     13861822.87      2475743.19     13861682.24
#Sta/Elev= 30
  3927.3  537.35  3944.1  536.16  4053.6  534.29  4281.4  528.71  4301.8  529.59
  4314.3  528.17  4342.7   528.3  4424.4  525.76  4444.9  526.27  4536.9  524.72
  4567.5  526.15  4577.7  524.78  4802.6  523.71  4869.7  524.72  4905.8  524.32
  4937.8   525.7  4965.9  525.08  4987.7  520.73  4992.5  520.01  4992.7  519.51
  4996.5  520.01  5009.8  524.36  5017.1  525.05  5041.8  524.51  5152.5  525.44
  5449.8  527.76  5525.4   528.5  5780.1     530  5931.6  534.27  6074.8  540.36
#Mann= 9 ,-1 , 0
  3927.3    .035       0  4053.6     .12       0  4987.7    .035       0
  4992.5    .035       0  4996.5    .035       0  5041.8     .12       0
  5152.5     .05       0  5449.8    .035       0  5525.4     .05       0
Bank Sta=4992.5,4996.5
XS Rating Curve= 0 ,0
Exp/Cntr=0.3,0.1

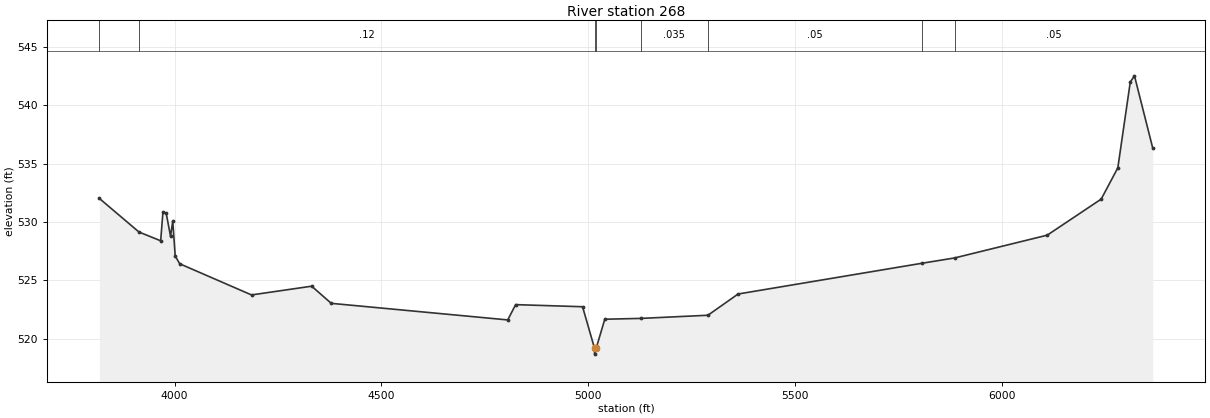
Type RM Length L Ch R = 1 ,268     ,0,0,0
BEGIN DESCRIPTION:
XS6586
END DESCRIPTION:
XS GIS Cut Line= 4
      2476821.37     13862854.09      2477180.73     13861999.95
      2477040.11     13861640.58      2475810.93      13861531.2
#Sta/Elev= 30
  3818.1  532.03  3913.9  529.15  3966.4   528.4  3971.8  530.83  3979.8  530.75
  3990.2  528.79  3995.6  530.08  4001.5   527.1  4012.4  526.43    4186  523.76
  4331.4  524.51  4378.8  523.04  4805.4  521.62  4824.5  522.93  4986.3  522.75
  5015.2  519.19  5015.4  518.69  5019.2  519.19    5040  521.68  5126.8  521.75
  5289.3  522.02  5362.3  523.84    5806  526.47  5885.8  526.93  6109.6  528.88
  6240.1  531.97  6280.3  534.65  6310.4     542  6320.5  542.53  6364.7  536.34
#Mann= 8 ,-1 , 0
  3818.1     .07       0  3913.9     .12       0  5015.2     .05       0
  5019.2     .12       0  5126.8    .035       0  5289.3     .05       0
    5806    .035       0  5885.8     .05       0
Bank Sta=5015.2,5019.2
XS Rating Curve= 0 ,0
Exp/Cntr=0.3,0.1

Chan Stop Cuts=-1
Use User Specified Reach Order=0
Composite Channel Slope=5