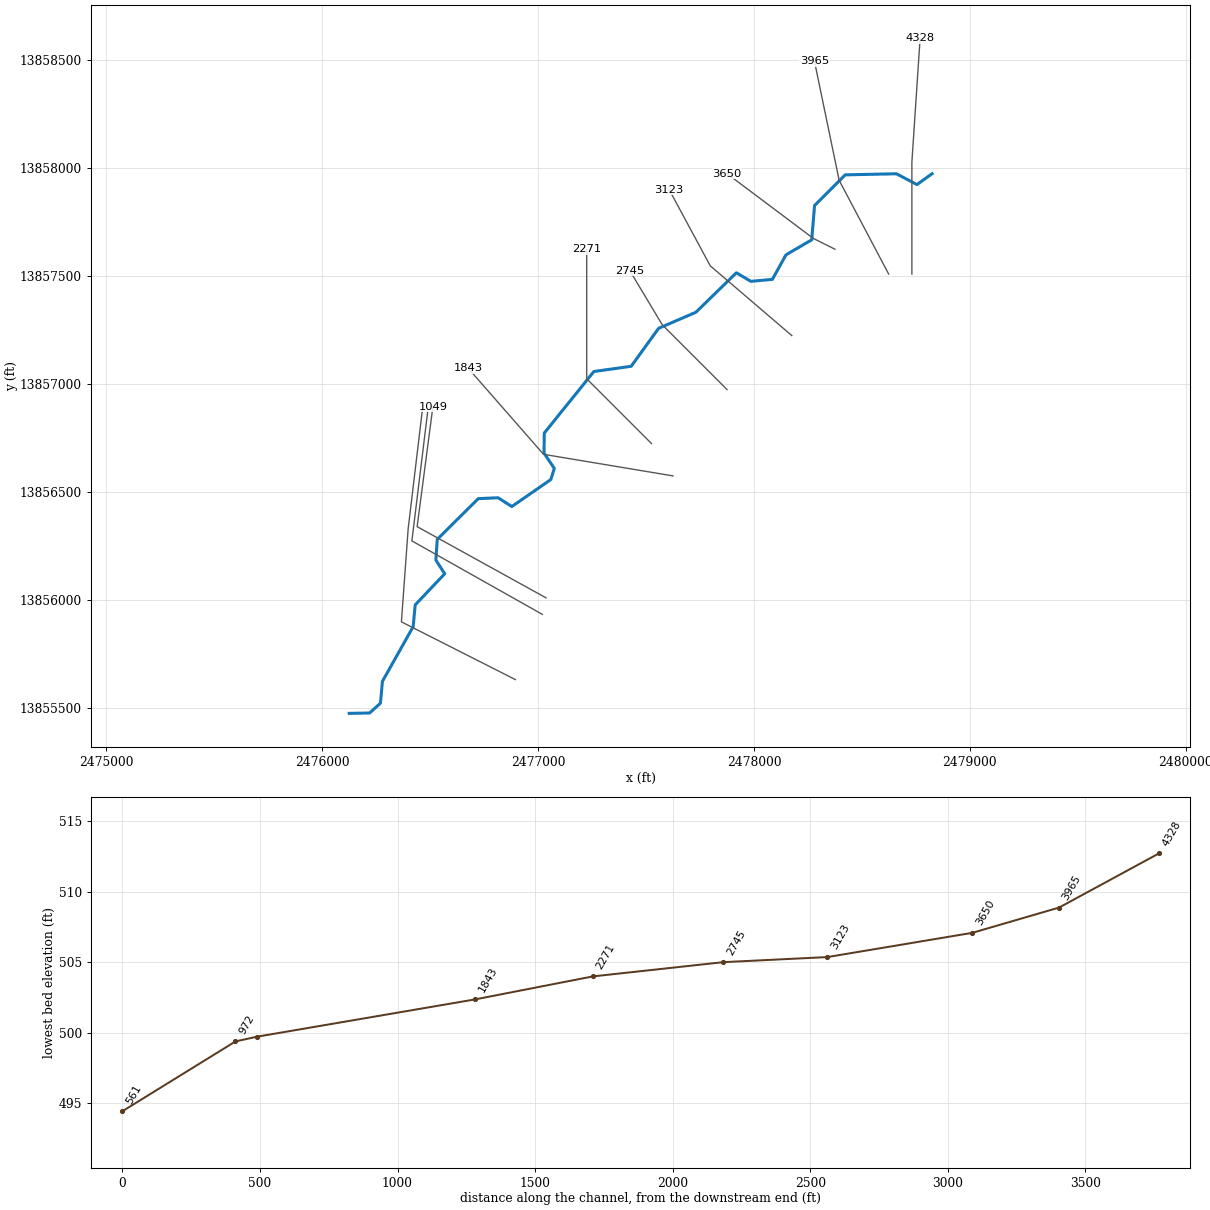
--- Stream0381.prj (project) ---

Proj Title=Stream0381 Base Level Engineering
Current Plan=p01
Default Exp/Contr=0.3,0.1
English Units
Geom File=g01
Flow File=f01
Plan File=p01
BEGIN DESCRIPTION:
Stream0381
END DESCRIPTION:

--- Stream0381.p01 (plan) ---

Plan Title=Multiple Run
Short Identifier=Multiple
Geom File=g01
Flow File=f01
Subcritical Flow
K Sum by GR= 0
Std Step Tol= 0.01
Critical Tol= 0.01
Num of Std Step Trials= 20
Max Error Tol= 0.3
Flow Tol Ratio= 0.001
Split Flow NTrial= 30
Split Flow Tol= 0.02
Split Flow Ratio= 0.02
Log Output Level= 0
Friction Slope Method= 1
Unsteady Friction Slope Method= 2
Unsteady Bridges Friction Slope Method= 1
Parabolic Critical Depth
Global Vel Dist=  1 , 1 , 1
Global Log Level= 0
CheckData=True
Encroach Param= -1, 0, 0, 0
BEGIN DESCRIPTION:
Multiple Run
END DESCRIPTION:

--- Stream0381.f01 (steady flow) ---

Flow Title=Multiple
Number of Profiles=7
Profile Names=10-year,25-year,50-year,1pct_min,100-year,1pct_plu,500-year
River Rch & RM= Stream0381,Reach-1,4328
     662    1064    1425     925    1845    3681    3062
River Rch & RM= Stream0381,Reach-1,1049
     650    1039    1388     897    1789    3570    2946
Boundary for River Rch & Prof#=Stream0381,Reach-1,1
Up Type=0
Dn Type=3
Dn Slope=0.005
Boundary for River Rch & Prof#=Stream0381,Reach-1,2
Up Type=0
Dn Type=3
Dn Slope=0.005
Boundary for River Rch & Prof#=Stream0381,Reach-1,3
Up Type=0
Dn Type=3
Dn Slope=0.005
Boundary for River Rch & Prof#=Stream0381,Reach-1,4
Up Type=0
Dn Type=3
Dn Slope=0.005
Boundary for River Rch & Prof#=Stream0381,Reach-1,5
Up Type=0
Dn Type=3
Dn Slope=0.005
Boundary for River Rch & Prof#=Stream0381,Reach-1,6
Up Type=0
Dn Type=3
Dn Slope=0.005
Boundary for River Rch & Prof#=Stream0381,Reach-1,7
Up Type=0
Dn Type=3
Dn Slope=0.005

--- Stream0381.g01 (geometry) ---

Geom Title=Existing Conditions

River Reach=Stream0381,Reach-1
Reach XY= 30
      2478825.00     13857975.00      2478754.79     13857924.45
      2478659.79     13857974.47      2478422.55     13857969.54
      2478280.47     13857827.45      2478267.30     13857668.53
      2478147.87     13857598.83      2478085.10     13857485.31
      2477985.49     13857476.27      2477918.26     13857515.87
      2477731.06     13857333.14      2477557.95     13857258.51
      2477431.21     13857082.81      2477258.23     13857058.57
      2477028.47     13856773.50      2477027.19     13856680.97
      2477074.97     13856609.58      2477058.80     13856558.29
      2476878.32     13856433.04      2476814.51     13856473.74
      2476722.57     13856469.60      2476532.76     13856281.17
      2476526.27     13856185.48      2476567.20     13856121.58
      2476430.52     13855977.43      2476421.17     13855876.59
      2476278.83     13855623.41      2476269.61     13855522.29
      2476219.47     13855476.76      2476125.00     13855475.00

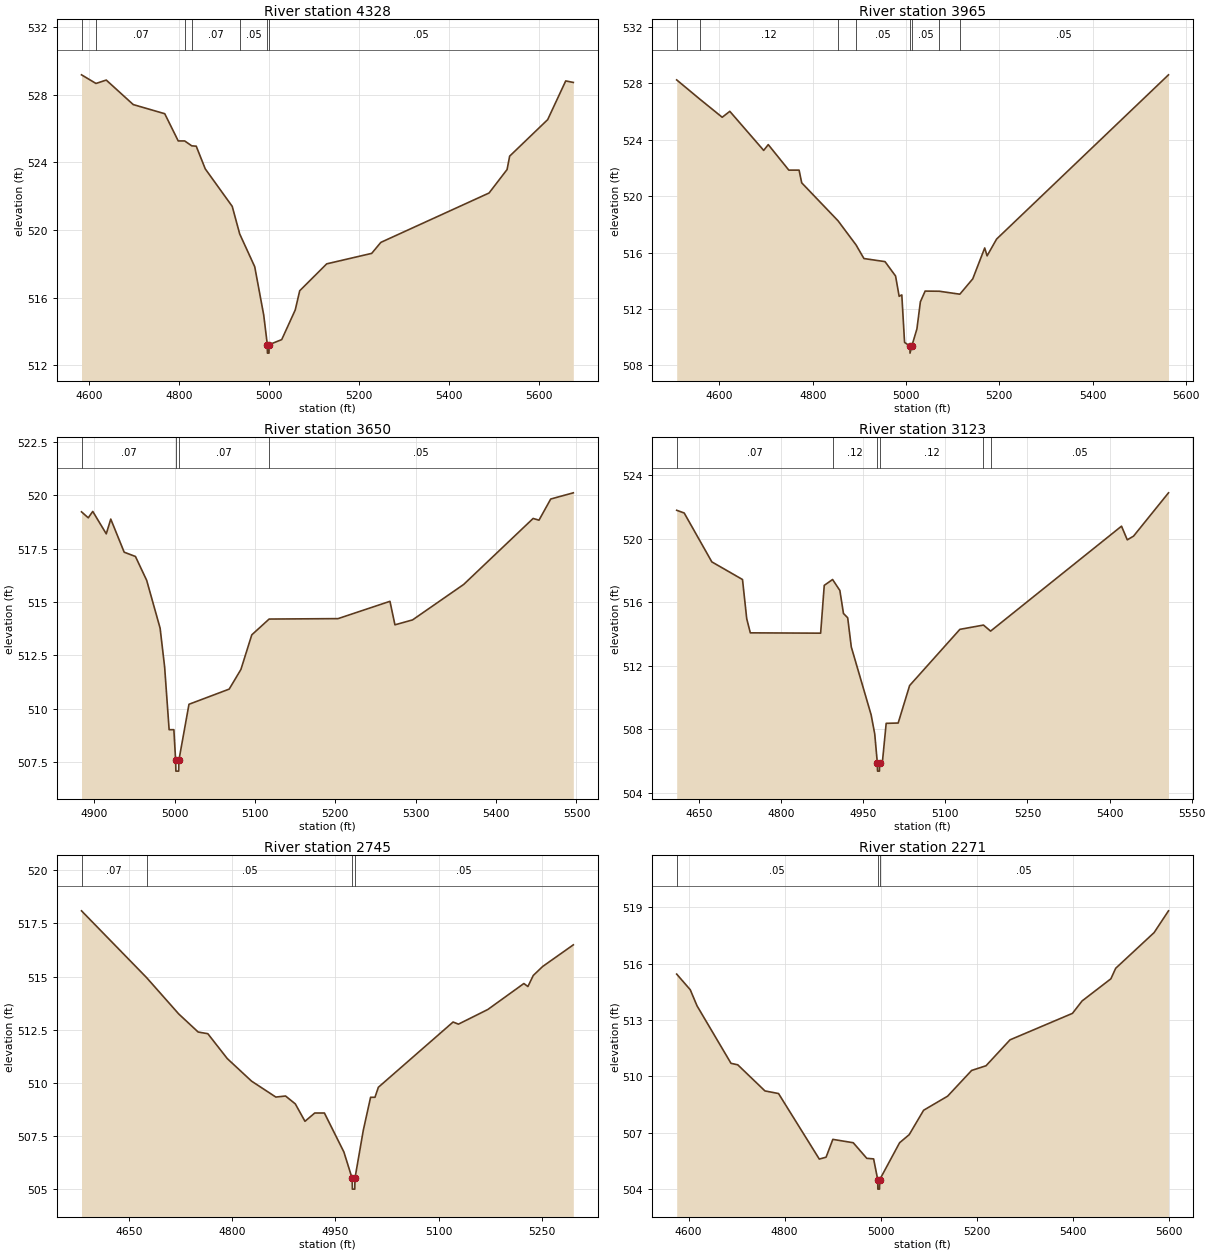
Type RM Length L Ch R = 1,4328,363,363,363
BEGIN DESCRIPTION:
XS6607
END DESCRIPTION:
XS GIS Cut Line= 3
      2478731.25     13857510.02      2478731.25     13858027.43
      2478769.31     13858601.86
#Sta/Elev= 30
  4583.3  529.17  4615.5  528.66  4638.3  528.86  4698.3  527.41  4768.3  526.87
  4798.3  525.26  4812.6  525.26  4828.3  524.97  4838.3  524.95  4858.3  523.61
  4918.3  521.39  4934.9  519.76  4968.3  517.82  4988.3  514.96  4996.3  513.21
  4996.5  512.71  5000.0  512.71  5000.3  513.21  5028.3  513.51  5058.3  515.26
  5068.3  516.40  5128.3  517.99  5228.3  518.61  5248.6  519.26  5489.1  522.18
  5529.2  523.57  5534.9  524.36  5619.4  526.52  5659.5  528.81  5676.4  528.72
#Mann=7,-1,0
  4583.3    0.05       0  4615.5    0.07       0  4812.6    0.12       0
  4828.3    0.07       0  4934.9    0.05       0  4996.3    0.05       0
  5000.3    0.05       0
Bank Sta=4996.3,5000.3
Exp/Cntr=0.3,0.1

Type RM Length L Ch R = 1,3965,315,315,315
BEGIN DESCRIPTION:
Stream0381 7.0
END DESCRIPTION:
XS GIS Cut Line= 3
      2478623.61     13857510.06      2478394.44     13857944.10
      2478279.94     13858495.82
#Sta/Elev= 30
  4508.3  528.25  4557.4  526.90  4605.9  525.60  4622.2  526.02  4694.8  523.25
  4704.6  523.66  4748.7  521.85  4770.7  521.85  4776.3  520.95  4854.1  518.26
  4892.7  516.55  4909.7  515.58  4954.9  515.36  4977.5  514.34  4985.2  512.90
  4990.9  513.00  4996.8  509.63  5008.3  509.37  5008.5  508.87  5012.3  509.37
  5023.3  510.59  5030.7  512.51  5040.9  513.27  5071.2  513.26  5115.3  513.05
  5143.0  514.14  5168.6  516.33  5173.7  515.77  5194.1  516.96  5562.6  528.61
#Mann=8,-1,0
  4508.3    0.05       0  4557.4    0.12       0  4854.1    0.07       0
  4892.7    0.05       0  5008.3    0.05       0  5012.3    0.05       0
  5071.2    0.07       0  5115.3    0.05       0
Bank Sta=5008.3,5012.3
Exp/Cntr=0.3,0.1

Type RM Length L Ch R = 1,3650,527,527,527
BEGIN DESCRIPTION:
Stream0381 6.0
END DESCRIPTION:
XS GIS Cut Line= 3
      2478375.02     13857624.99      2478275.00     13857675.00
      2477875.02     13857974.99
#Sta/Elev= 30
  4884.3  519.22  4892.7  518.94  4898.3  519.24  4915.1  518.19  4920.7  518.88
  4937.4  517.33  4951.4  517.13  4965.4  516.01  4982.1  513.77  4987.7  511.96
  4993.3  509.02  4999.2  509.02  5001.4  507.58  5001.7  507.08  5005.2  507.08
  5005.4  507.58  5018.0  510.21  5068.0  510.92  5082.6  511.84  5096.1  513.46
  5117.7  514.20  5203.4  514.22  5268.0  515.03  5274.2  513.93  5296.1  514.16
  5359.7  515.82  5446.1  518.91  5453.4  518.83  5468.0  519.82  5496.1  520.11
#Mann=4,-1,0
  4884.3    0.07       0  5001.4    0.05       0  5005.4    0.07       0
  5117.7    0.05       0
Bank Sta=5001.4,5005.4
Exp/Cntr=0.3,0.1

Type RM Length L Ch R = 1,3123,378,378,378
BEGIN DESCRIPTION:
Stream0381 5.0
END DESCRIPTION:
XS GIS Cut Line= 3
      2478175.01     13857224.99      2477797.22     13857548.26
      2477606.91     13857901.21
#Sta/Elev= 30
  4609.5  521.79  4623.2  521.62  4673.7  518.54  4729.7  517.43  4737.4  514.96
  4744.0  514.07  4872.4  514.05  4879.0  517.06  4894.2  517.43  4907.5  516.74
  4914.1  515.29  4921.8  515.02  4928.4  513.18  4964.6  508.91  4971.2  507.70
  4976.0  505.86  4976.3  505.36  4979.8  505.36  4980.0  505.86  4985.5  506.04
  4992.1  508.37  5014.0  508.39  5034.9  510.75  5126.7  514.29  5169.8  514.56
  5182.8  514.18  5421.9  520.79  5432.4  519.93  5443.8  520.16  5507.7  522.89
#Mann=6,-1,0
  4609.5    0.07       0  4894.2    0.12       0  4976.0    0.05       0
  4980.0    0.12       0  5169.8    0.07       0  5182.8    0.05       0
Bank Sta=4976,4980
Exp/Cntr=0.3,0.1

Type RM Length L Ch R = 1,2745,474,474,474
BEGIN DESCRIPTION:
Stream0381 4.0
END DESCRIPTION:
XS GIS Cut Line= 3
      2477875.04     13856974.96      2477575.00     13857275.00
      2477424.98     13857525.03
#Sta/Elev= 30
  4580.3  518.09  4675.0  514.95  4721.8  513.24  4750.1  512.39  4764.2  512.31
  4792.5  511.14  4827.8  510.08  4863.2  509.33  4877.3  509.38  4891.5  509.01
  4905.6  508.19  4919.8  508.58  4933.9  508.58  4962.2  506.75  4974.3  505.50
  4974.6  505.00  4978.1  505.00  4978.3  505.50  4990.5  507.77  5001.1  509.32
  5007.5  509.32  5012.4  509.79  5121.2  512.86  5129.0  512.76  5171.8  513.45
  5224.2  514.67  5230.1  514.53  5237.9  515.05  5251.5  515.47  5296.2  516.49
#Mann=4,-1,0
  4580.3    0.07       0  4675.0    0.05       0  4974.3    0.05       0
  4978.3    0.05       0
Bank Sta=4974.3,4978.3
Exp/Cntr=0.3,0.1

Type RM Length L Ch R = 1,2271,428,428,428
BEGIN DESCRIPTION:
Stream0381 3.0
END DESCRIPTION:
XS GIS Cut Line= 3
      2477524.98     13856725.02      2477225.00     13857025.00
      2477225.00     13857624.97
#Sta/Elev= 30
  4575.4  515.44  4603.6  514.61  4617.8  513.75  4688.5  510.69  4702.6  510.61
  4759.2  509.22  4787.5  509.08  4872.4  505.59  4886.5  505.69  4900.6  506.64
  4943.1  506.46  4971.3  505.63  4985.5  505.60  4994.1  504.49  4994.3  503.99
  4997.8  503.99  4998.1  504.49  5039.6  506.46  5059.6  506.89  5089.6  508.19
  5139.6  508.94  5189.6  510.31  5219.6  510.56  5269.6  511.94  5399.6  513.35
  5419.6  514.01  5479.6  515.19  5489.6  515.75  5569.6  517.65  5599.6  518.81
#Mann=3,-1,0
  4575.4    0.05       0  4994.1    0.05       0  4998.1    0.05       0
Bank Sta=4994.1,4998.1
Exp/Cntr=0.3,0.1

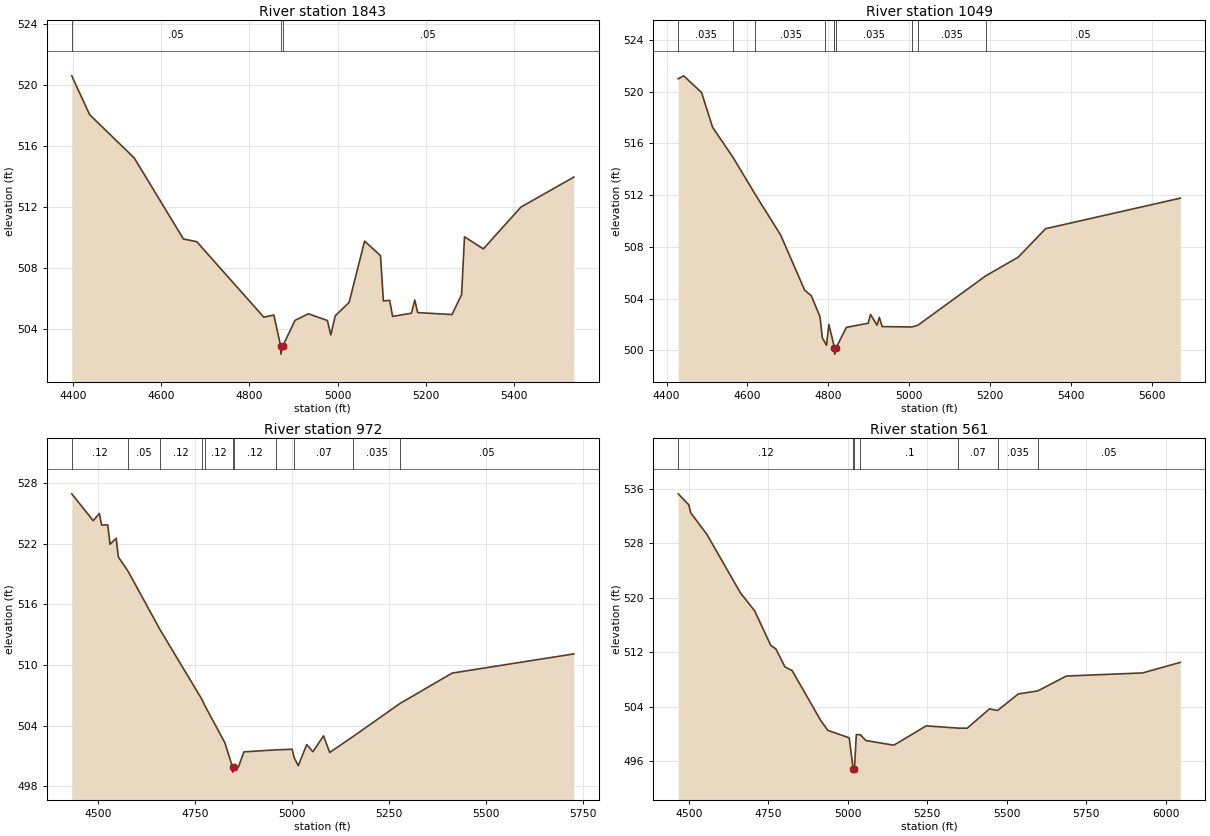
Type RM Length L Ch R = 1,1843,794,794,794
BEGIN DESCRIPTION:
Stream0381 2.0
END DESCRIPTION:
XS GIS Cut Line= 3
      2477624.95     13856575.01      2477025.00     13856675.00
      2476675.02     13857074.97
#Sta/Elev= 30
  4396.8  520.58  4437.3  518.04  4538.7  515.20  4650.2  509.90  4680.6  509.72
  4832.7  504.78  4855.5  504.92  4871.2  502.86  4871.5  502.36  4875.2  502.86
  4903.6  504.57  4934.1  505.00  4977.1  504.56  4984.8  503.62  4994.9  504.87
  5026.4  505.75  5061.5  509.76  5097.6  508.81  5104.2  505.84  5118.4  505.88
  5125.1  504.83  5167.8  505.04  5175.4  505.90  5182.0  505.08  5259.9  504.95
  5281.7  506.26  5288.3  510.04  5331.1  509.25  5416.5  511.99  5536.5  513.95
#Mann=3,-1,0
  4396.8    0.05       0  4871.2    0.05       0  4875.2    0.05       0
Bank Sta=4871.2,4875.2
Exp/Cntr=0.3,0.1

Type RM Length L Ch R = 1,1049,77,77,77
BEGIN DESCRIPTION:
XS6606
END DESCRIPTION:
XS GIS Cut Line= 3
      2477036.77     13856010.09      2476439.58     13856339.93
      2476512.49     13856895.44
#Sta/Elev= 30
  4428.7  521.00  4442.2  521.23  4486.4  519.94  4513.8  517.25  4564.2  514.93
  4619.9  512.03  4682.2  508.92  4741.8  504.64  4757.9  504.24  4779.6  502.59
  4785.4  500.96  4792.9  500.55  4795.7  500.40  4801.4  502.01  4813.5  500.45
  4815.4  500.21  4815.7  499.71  4819.5  500.21  4844.9  501.78  4898.8  502.10
  4904.5  502.78  4920.6  501.95  4926.3  502.56  4933.4  501.84  5007.0  501.81
  5021.6  501.94  5189.6  505.76  5270.1  507.21  5337.9  509.41  5671.2  511.77
#Mann=10,-1,0
  4428.7   0.035       0  4564.2    0.05       0  4619.9   0.035       0
  4792.9    0.12       0  4813.5   0.035       0  4815.4   0.035       0
  4819.5   0.035       0  5007.0    0.07       0  5021.6   0.035       0
  5189.6    0.05       0
Bank Sta=4815.4,4819.5
Exp/Cntr=0.3,0.1

Type RM Length L Ch R = 1,972,411,411,411
BEGIN DESCRIPTION:
Stream0381 1.0
END DESCRIPTION:
XS GIS Cut Line= 3
      2477019.47     13855933.66      2476415.28     13856273.96
      2476488.12     13856870.59
#Sta/Elev= 30
  4431.7  526.97  4486.9  524.31  4502.9  525.02  4508.6  523.88  4524.5  523.89
  4530.3  521.97  4546.2  522.56  4551.9  520.71  4576.7  519.31  4660.1  513.45
  4767.6  506.57  4775.0  505.96  4826.5  502.29  4846.2  499.88  4846.4  499.38
  4850.3  499.88  4861.5  499.90  4875.6  501.39  4958.4  501.59  4999.9  501.65
  5004.9  500.83  5015.8  500.02  5037.5  502.11  5053.4  501.40  5080.8  502.98
  5096.7  501.33  5157.7  502.93  5277.7  506.18  5412.5  509.20  5726.2  511.10
#Mann=11,-1,0
  4431.7    0.12       0  4576.7    0.05       0  4660.1    0.12       0
  4767.6   0.035       0  4775.0    0.12       0  4846.2   0.035       0
  4850.3    0.12       0  4958.4   0.035       0  5004.9    0.07       0
  5157.7   0.035       0  5277.7    0.05       0
Bank Sta=4846.2,4850.3
Exp/Cntr=0.3,0.1

Type RM Length L Ch R = 1,561,0,0,0
BEGIN DESCRIPTION:
XS6605
END DESCRIPTION:
XS GIS Cut Line= 4
      2476894.44     13855631.60      2476366.67     13855898.96
      2476397.92     13856329.51      2476463.79     13856880.77
#Sta/Elev= 30
  4467.1  535.23  4500.1  533.63  4506.8  532.41  4556.9  529.31  4662.7  520.71
  4707.2  518.09  4757.9  513.02  4774.1  512.49  4802.8  509.85  4825.2  509.32
  4914.9  502.02  4937.3  500.56  5004.6  499.46  5017.0  494.93  5017.3  494.43
  5021.2  494.93  5027.0  499.93  5039.6  499.92  5056.9  499.06  5145.0  498.38
  5246.6  501.21  5347.8  500.88  5375.6  500.87  5445.8  503.70  5471.1  503.47
  5536.2  505.89  5597.8  506.34  5687.3  508.52  5926.7  508.97  6045.6  510.52
#Mann=7,-1,0
  4467.1    0.12       0  5017.0    0.05       0  5021.2    0.12       0
  5039.6     0.1       0  5347.8    0.07       0  5471.1   0.035       0
  5597.8    0.05       0
Bank Sta=5017,5021.2
Exp/Cntr=0.3,0.1

Chan Stop Cuts=-1