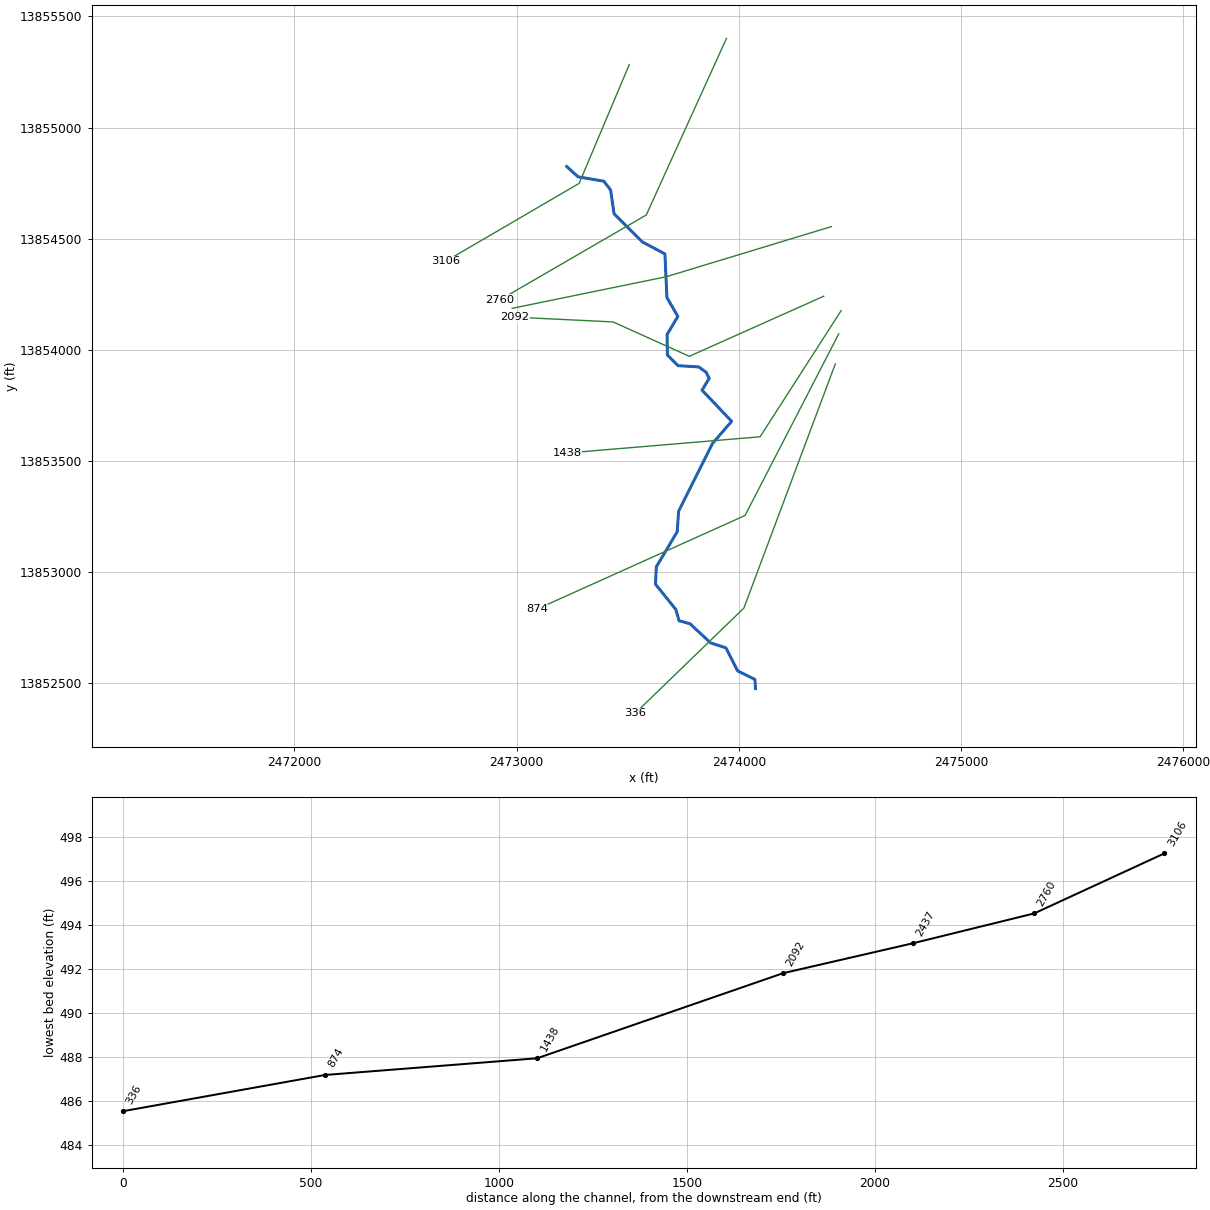
--- Stream0382.prj (project) ---

Proj Title=Stream0382 Base Level Engineering
Current Plan=p01
Default Exp/Contr=0.3,0.1
English Units
Geom File=g01
Flow File=f01
Plan File=p01
BEGIN DESCRIPTION:
Stream0382
END DESCRIPTION:

--- Stream0382.p01 (plan) ---

Plan Title=Multiple Run
Short Identifier=Multiple
Geom File=g01
Flow File=f01
Subcritical Flow
K Sum by GR= 0
Std Step Tol= 0.01
Critical Tol= 0.01
Num of Std Step Trials= 20
Max Error Tol= 0.3
Flow Tol Ratio= 0.001
Split Flow NTrial= 30
Split Flow Tol= 0.02
Split Flow Ratio= 0.02
Log Output Level= 0
Friction Slope Method= 1
Unsteady Friction Slope Method= 2
Unsteady Bridges Friction Slope Method= 1
Parabolic Critical Depth
Global Vel Dist=  1 , 1 , 1
Global Log Level= 0
CheckData=True
Encroach Param= -1, 0, 0, 0
BEGIN DESCRIPTION:
Multiple Run
END DESCRIPTION:

--- Stream0382.f01 (steady flow) ---

Flow Title=Multiple
Number of Profiles=7
Profile Names=10-year,25-year,50-year,1pct_min,100-year,1pct_plu,500-year
River Rch & RM= Stream0382,Reach-1,3106
     771    1259    1705    1120    2234    4457    3794
River Rch & RM= Stream0382,Reach-1,1438
     794    1295    1753    1150    2294    4577    3885
Boundary for River Rch & Prof#=Stream0382,Reach-1,1
Up Type=0
Dn Type=3
Dn Slope=0.005
Boundary for River Rch & Prof#=Stream0382,Reach-1,2
Up Type=0
Dn Type=3
Dn Slope=0.005
Boundary for River Rch & Prof#=Stream0382,Reach-1,3
Up Type=0
Dn Type=3
Dn Slope=0.005
Boundary for River Rch & Prof#=Stream0382,Reach-1,4
Up Type=0
Dn Type=3
Dn Slope=0.005
Boundary for River Rch & Prof#=Stream0382,Reach-1,5
Up Type=0
Dn Type=3
Dn Slope=0.005
Boundary for River Rch & Prof#=Stream0382,Reach-1,6
Up Type=0
Dn Type=3
Dn Slope=0.005
Boundary for River Rch & Prof#=Stream0382,Reach-1,7
Up Type=0
Dn Type=3
Dn Slope=0.005

--- Stream0382.g01 (geometry) ---

Geom Title=Existing Conditions

River Reach=Stream0382,Reach-1
Reach XY= 30
      2473225.00     13854825.00      2473276.41     13854778.39
      2473392.21     13854758.74      2473422.93     13854719.31
      2473438.40     13854611.70      2473565.34     13854485.79
      2473667.31     13854431.48      2473676.24     13854235.50
      2473725.40     13854150.00      2473677.19     13854069.03
      2473678.36     13853976.25      2473726.25     13853928.51
      2473819.50     13853922.85      2473852.68     13853898.82
      2473866.93     13853871.87      2473834.31     13853818.34
      2473967.40     13853678.34      2473880.86     13853577.30
      2473728.83     13853273.42      2473722.67     13853180.97
      2473628.67     13853023.41      2473624.79     13852945.05
      2473716.70     13852830.74      2473730.62     13852780.62
      2473780.74     13852766.70      2473872.74     13852680.88
      2473942.05     13852658.50      2473994.67     13852554.54
      2474072.34     13852516.55      2474075.00     13852475.00

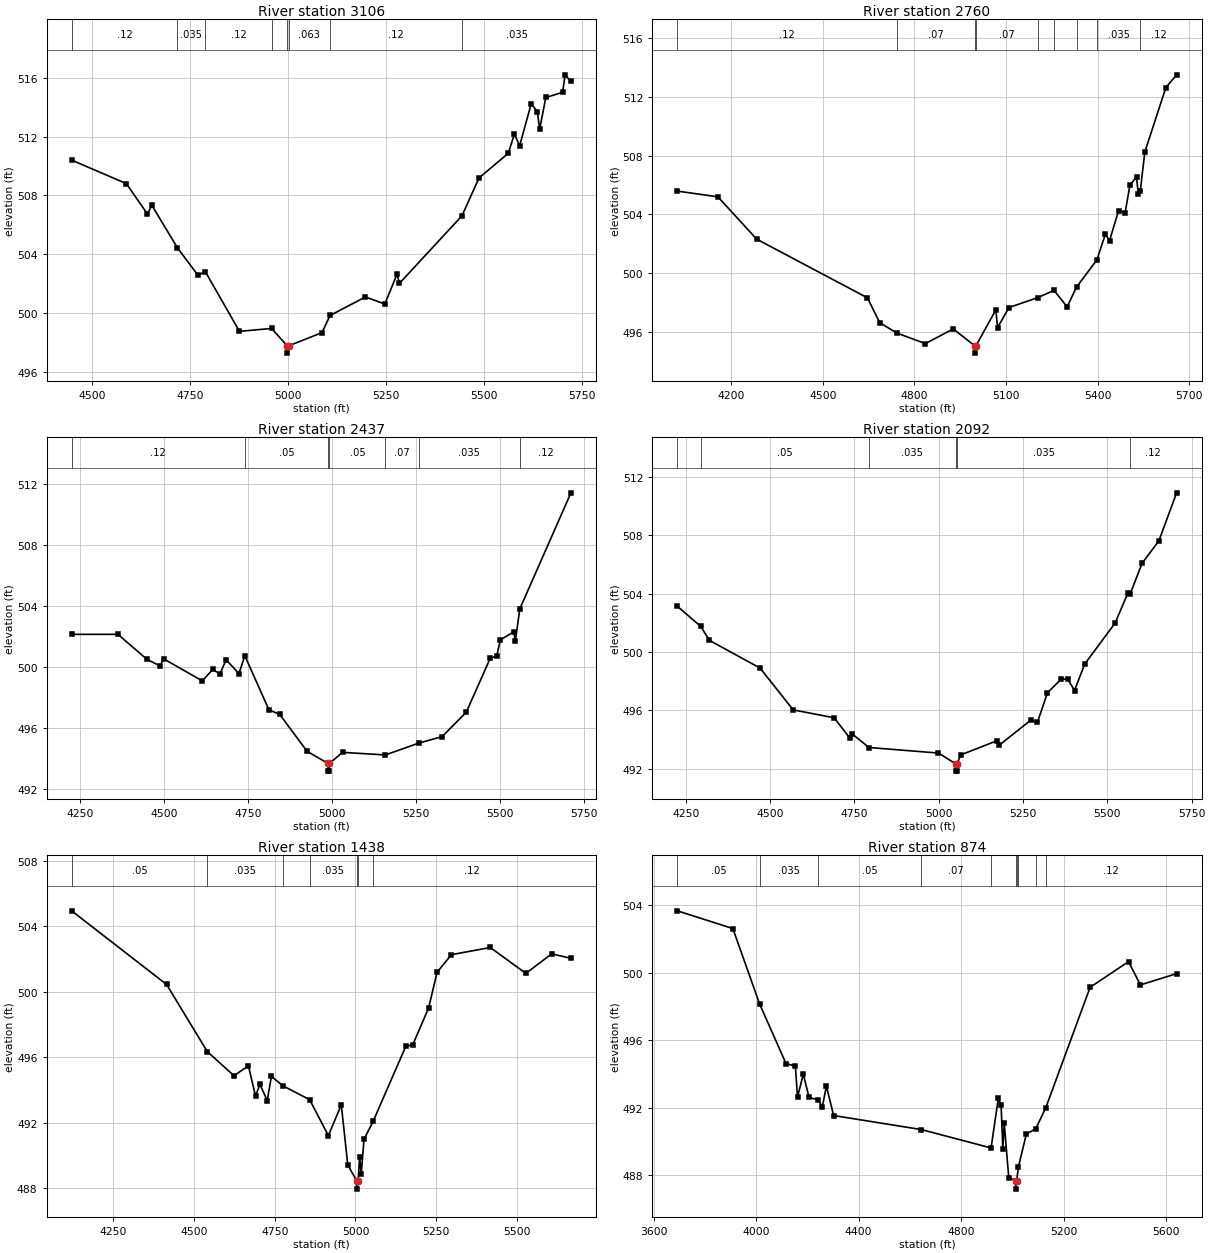
Type RM Length L Ch R = 1,3106,346,346,346
BEGIN DESCRIPTION:
XS6608
END DESCRIPTION:
XS GIS Cut Line= 3
      2473506.94     13855283.67      2473281.25     13854748.96
      2472682.08     13854399.15
#Sta/Elev= 30
  4448.3  510.40  4588.0  508.80  4641.5  506.74  4653.1  507.32  4718.4  504.43
  4770.9  502.56  4789.3  502.82  4876.6  498.75  4958.5  498.95  4998.4  497.77
  4998.7  497.27  5002.4  497.77  5087.1  498.66  5107.7  499.83  5198.0  501.09
  5247.5  500.61  5278.9  502.65  5284.7  502.01  5444.4  506.61  5488.1  509.19
  5562.5  510.86  5578.2  512.16  5591.7  511.38  5621.2  514.24  5636.9  513.68
  5642.7  512.50  5658.4  514.66  5701.4  515.01  5707.5  516.20  5722.5  515.75
#Mann=8,-1,0
  4448.3    0.12       0  4718.4   0.035       0  4789.3    0.12       0
  4958.5   0.063       0  4998.4    0.05       0  5002.4   0.063       0
  5107.7    0.12       0  5444.4   0.035       0
Bank Sta=4998.4,5002.4
Exp/Cntr=0.3,0.1

Type RM Length L Ch R = 1,2760,323,323,323
BEGIN DESCRIPTION:
Stream0382 3.0
END DESCRIPTION:
XS GIS Cut Line= 3
      2473944.44     13855401.72      2473583.33     13854606.60
      2472925.01     13854225.00
#Sta/Elev= 30
  4024.2  505.59  4156.9  505.20  4284.2  502.31  4646.6  498.31  4686.5  496.62
  4742.8  495.91  4835.9  495.19  4927.5  496.19  4997.6  495.04  4997.8  494.54
  5001.6  495.04  5066.7  497.49  5072.4  496.28  5109.7  497.65  5203.3  498.32
  5257.1  498.82  5300.1  497.70  5330.9  499.05  5397.5  500.90  5425.3  502.66
  5438.8  502.21  5468.3  504.25  5489.9  504.13  5505.6  506.01  5527.1  506.54
  5532.9  505.41  5539.4  505.59  5554.4  508.26  5623.2  512.65  5658.4  513.52
#Mann=9,-1,0
  4024.2    0.12       0  4742.8    0.07       0  4997.6    0.05       0
  5001.6    0.07       0  5203.3   0.063       0  5257.1   0.035       0
  5330.9   0.063       0  5397.5   0.035       0  5539.4    0.12       0
Bank Sta=4997.6,5001.6
Exp/Cntr=0.3,0.1

Type RM Length L Ch R = 1,2437,345,345,345
BEGIN DESCRIPTION:
Stream0382 2.0
END DESCRIPTION:
XS GIS Cut Line= 3
      2474416.70     13854554.53      2473673.61     13854328.82
      2472979.56     13854186.54
#Sta/Elev= 30
  4224.9  502.14  4362.5  502.14  4449.1  500.50  4488.0  500.07  4498.4  500.54
  4613.4  499.09  4644.7  499.84  4665.6  499.54  4684.5  500.47  4722.6  499.57
  4740.0  500.74  4811.9  497.19  4843.3  496.91  4925.2  494.48  4987.6  493.68
  4987.9  493.18  4991.4  493.18  4991.6  493.68  5030.7  494.41  5158.0  494.24
  5258.0  495.02  5326.8  495.44  5398.7  497.04  5469.7  500.56  5489.3  500.73
  5500.3  501.78  5539.7  502.30  5544.8  501.73  5558.0  503.81  5710.0  511.41
#Mann=7,-1,0
  4224.9    0.12       0  4740.0    0.05       0  4987.6    0.05       0
  4991.6    0.05       0  5158.0    0.07       0  5258.0   0.035       0
  5558.0    0.12       0
Bank Sta=4987.6,4991.6
Exp/Cntr=0.3,0.1

Type RM Length L Ch R = 1,2092,654,654,654
BEGIN DESCRIPTION:
Stream0382 1.0
END DESCRIPTION:
XS GIS Cut Line= 4
      2474381.99     13854241.07      2473777.08     13853970.64
      2473433.68     13854125.44      2472992.48     13854146.79
#Sta/Elev= 30
  4224.5  503.13  4293.8  501.75  4319.7  500.79  4469.9  498.89  4568.2  496.02
  4689.7  495.48  4736.0  494.09  4741.6  494.40  4793.0  493.44  4999.1  493.06
  5050.2  492.32  5050.4  491.82  5053.9  491.82  5054.2  492.32  5064.9  492.93
  5173.3  493.91  5178.8  493.59  5272.5  495.31  5292.5  495.16  5322.5  497.20
  5362.9  498.13  5382.6  498.13  5402.6  497.35  5432.7  499.16  5522.8  501.97
  5561.4  504.06  5567.2  503.94  5602.9  506.07  5652.9  507.62  5705.5  510.91
#Mann=6,-1,0
  4224.5    0.07       0  4293.8    0.05       0  4793.0   0.035       0
  5050.2   0.035       0  5054.2   0.035       0  5567.2    0.12       0
Bank Sta=5050.2,5054.2
Exp/Cntr=0.3,0.1

Type RM Length L Ch R = 1,1438,564,564,564
BEGIN DESCRIPTION:
E20945
END DESCRIPTION:
XS GIS Cut Line= 3
      2474460.19     13854176.02      2474095.62     13853608.33
      2473225.83     13853535.42
#Sta/Elev= 30
  4120.3  504.95  4414.7  500.45  4540.8  496.35  4623.5  494.88  4668.2  495.48
  4690.2  493.64  4703.9  494.35  4726.5  493.36  4739.5  494.84  4774.5  494.27
  4858.1  493.41  4916.0  491.22  4956.1  493.10  4976.2  489.42  5004.3  488.45
  5004.5  487.95  5008.4  488.45  5012.9  489.93  5017.9  488.87  5026.4  490.99
  5055.4  492.12  5156.8  496.71  5176.9  496.73  5227.1  499.04  5253.0  501.20
  5297.3  502.27  5417.8  502.71  5528.1  501.13  5608.2  502.32  5667.8  502.05
#Mann=7,-1,0
  4120.3    0.05       0  4540.8   0.035       0  4774.5    0.05       0
  4858.1   0.035       0  5004.3   0.035       0  5008.4   0.035       0
  5055.4    0.12       0
Bank Sta=5004.3,5008.4
Exp/Cntr=0.3,0.1

Type RM Length L Ch R = 1,874,538,538,538
BEGIN DESCRIPTION:
E20944
END DESCRIPTION:
XS GIS Cut Line= 3
      2474449.76     13854071.83      2474027.91     13853254.17
      2473090.43     13852832.30
#Sta/Elev= 30
  3692.4  503.68  3909.1  502.63  4013.2  498.17  4116.4  494.63  4152.9  494.48
  4161.4  492.65  4183.9  494.00  4206.4  492.62  4242.2  492.48  4258.0  492.05
  4274.0  493.30  4302.3  491.55  4644.2  490.72  4916.6  489.63  4944.8  492.57
  4955.6  492.19  4962.4  489.59  4967.9  491.08  4985.6  487.87  5012.2  487.69
  5012.4  487.19  5016.3  487.69  5023.3  488.51  5054.3  490.46  5090.6  490.76
  5130.0  492.01  5303.0  499.15  5452.9  500.67  5499.2  499.29  5640.5  499.96
#Mann=10,-1,0
  3692.4    0.05       0  4013.2   0.035       0  4242.2    0.05       0
  4644.2    0.07       0  4916.6   0.035       0  5012.2   0.035       0
  5016.3   0.035       0  5023.3    0.12       0  5090.6   0.035       0
  5130.0    0.12       0
Bank Sta=5012.2,5016.3
Exp/Cntr=0.3,0.1

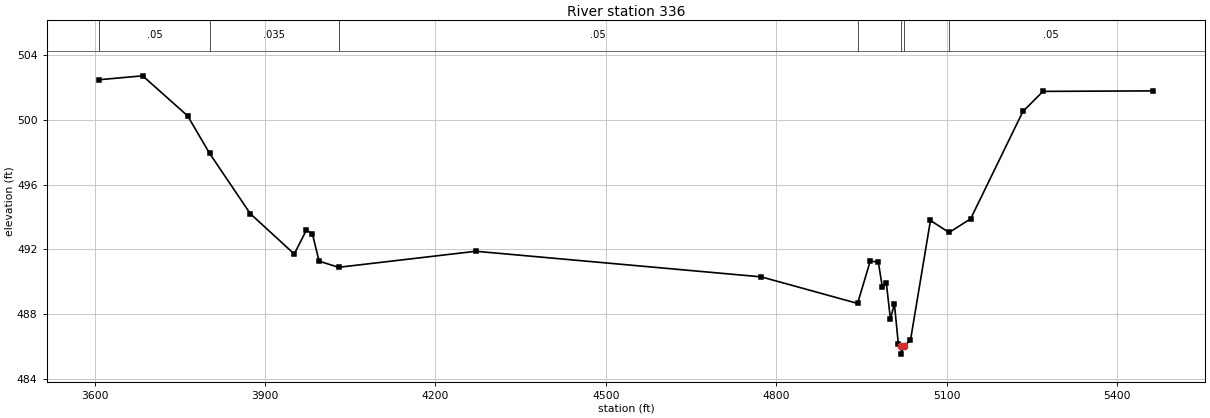
Type RM Length L Ch R = 1,336,0,0,0
BEGIN DESCRIPTION:
E20943
END DESCRIPTION:
XS GIS Cut Line= 3
      2474434.14     13853936.42      2474022.70     13852837.50
      2473533.14     13852363.56
#Sta/Elev= 30
  3608.1  502.48  3684.4  502.72  3763.5  500.25  3802.3  497.93  3873.9  494.21
  3951.3  491.72  3972.7  493.20  3983.3  492.96  3995.0  491.28  4029.3  490.90
  4271.1  491.89  4773.5  490.31  4943.2  488.67  4965.5  491.29  4979.7  491.22
  4986.9  489.66  4993.8  489.94  5001.0  487.71  5008.0  488.64  5014.9  486.19
  5020.0  486.04  5020.3  485.54  5024.3  486.04  5036.3  486.39  5071.5  493.79
  5104.3  493.05  5142.2  493.89  5234.3  500.52  5269.6  501.76  5462.9  501.79
#Mann=7,-1,0
  3608.1    0.05       0  3802.3   0.035       0  4029.3    0.05       0
  4943.2    0.07       0  5020.0    0.05       0  5024.3    0.07       0
  5104.3    0.05       0
Bank Sta=5020,5024.3
Exp/Cntr=0.3,0.1

Chan Stop Cuts=-1