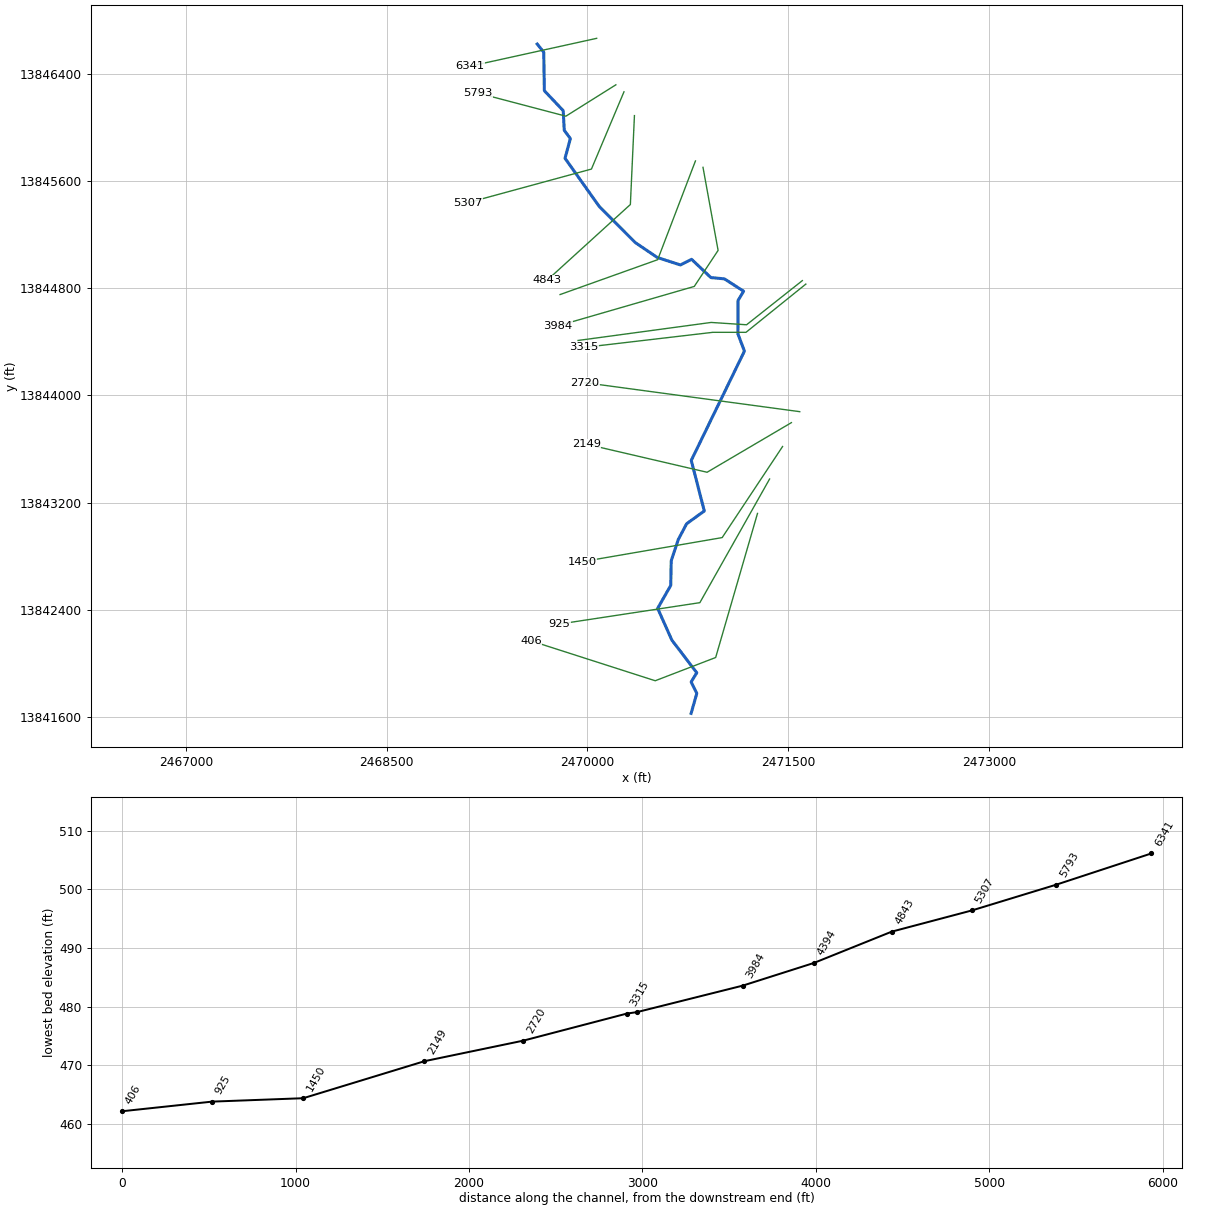
--- Stream0384.prj (project) ---

Proj Title=Stream0384 Base Level Engineering
Current Plan=p01
Default Exp/Contr=0.3,0.1
English Units
Geom File=g01
Flow File=f01
Plan File=p01
Y Axis Title=Elevation
X Axis Title(PF)=Main Channel Distance
X Axis Title(XS)=Station
BEGIN DESCRIPTION:
Stream0384
END DESCRIPTION:
DSS Export Rating Curves= 0
DSS Export Rating Curve Sorted= 0
DSS Export Volume Flow Curves= 0
DXF OffsetX= 0
DXF OffsetY= 0
DXF ScaleX= 1
DXF ScaleY= 10

--- Stream0384.p01 (plan) ---

Plan Title=Multiple Run
Short Identifier=Multiple
Geom File=g01
Flow File=f01
Subcritical Flow
K Sum by GR= 0
Std Step Tol= 0.01
Critical Tol= 0.01
Num of Std Step Trials= 20
Max Error Tol= 0.3
Flow Tol Ratio= 0.001
Split Flow NTrial= 30
Split Flow Tol= 0.02
Split Flow Ratio= 0.02
Log Output Level= 0
Friction Slope Method= 1
Unsteady Friction Slope Method= 2
Unsteady Bridges Friction Slope Method= 1
Parabolic Critical Depth
Global Vel Dist=  1 , 1 , 1
Global Log Level= 0
CheckData=True
Encroach Param= -1, 0, 0, 0
BEGIN DESCRIPTION:
Multiple Run
END DESCRIPTION:

--- Stream0384.f01 (steady flow) ---

Flow Title=Multiple
Number of Profiles=7
Profile Names=10-year,25-year,50-year,1pct_min,100-year,1pct_plu,500-year
River Rch & RM= Stream0384,Reach-1,6341
     273     415     537     338     674    1345    1047
River Rch & RM= Stream0384,Reach-1,3375
     625    1002    1341     870    1736    3463    2876
Boundary for River Rch & Prof#=Stream0384,Reach-1,1
Up Type=0
Dn Type=3
Dn Slope=0.005
Boundary for River Rch & Prof#=Stream0384,Reach-1,2
Up Type=0
Dn Type=3
Dn Slope=0.005
Boundary for River Rch & Prof#=Stream0384,Reach-1,3
Up Type=0
Dn Type=3
Dn Slope=0.005
Boundary for River Rch & Prof#=Stream0384,Reach-1,4
Up Type=0
Dn Type=3
Dn Slope=0.005
Boundary for River Rch & Prof#=Stream0384,Reach-1,5
Up Type=0
Dn Type=3
Dn Slope=0.005
Boundary for River Rch & Prof#=Stream0384,Reach-1,6
Up Type=0
Dn Type=3
Dn Slope=0.005
Boundary for River Rch & Prof#=Stream0384,Reach-1,7
Up Type=0
Dn Type=3
Dn Slope=0.005

--- Stream0384.g01 (geometry) ---

Geom Title=Existing Conditions
Program Version=4.10

River Reach=Stream0384      ,Reach-1
Reach XY= 30
        2469625.       13846625.      2469674.04      13846564.6
      2469678.54     13846276.46      2469819.53     13846127.45
      2469827.27     13845980.94      2469872.83     13845919.02
      2469833.04     13845771.68      2470088.63     13845411.79
      2470358.33     13845141.65      2470522.58     13845030.54
      2470695.21     13844974.79      2470778.41     13845017.18
      2470922.57     13844880.52      2471023.42     13844871.17
      2471167.31     13844778.67      2471125.67     13844709.85
      2471124.58     13844459.82      2471173.18     13844331.12
      2470776.09     13843514.46      2470873.49     13843136.87
      2470741.63     13843041.71      2470678.82     13842923.42
      2470626.22      13842764.5      2470622.76     13842580.93
      2470525.07     13842409.61      2470630.85     13842172.71
      2470817.17      13841928.4      2470775.29     13841859.64
      2470817.46     13841775.01        2470775.       13841625.

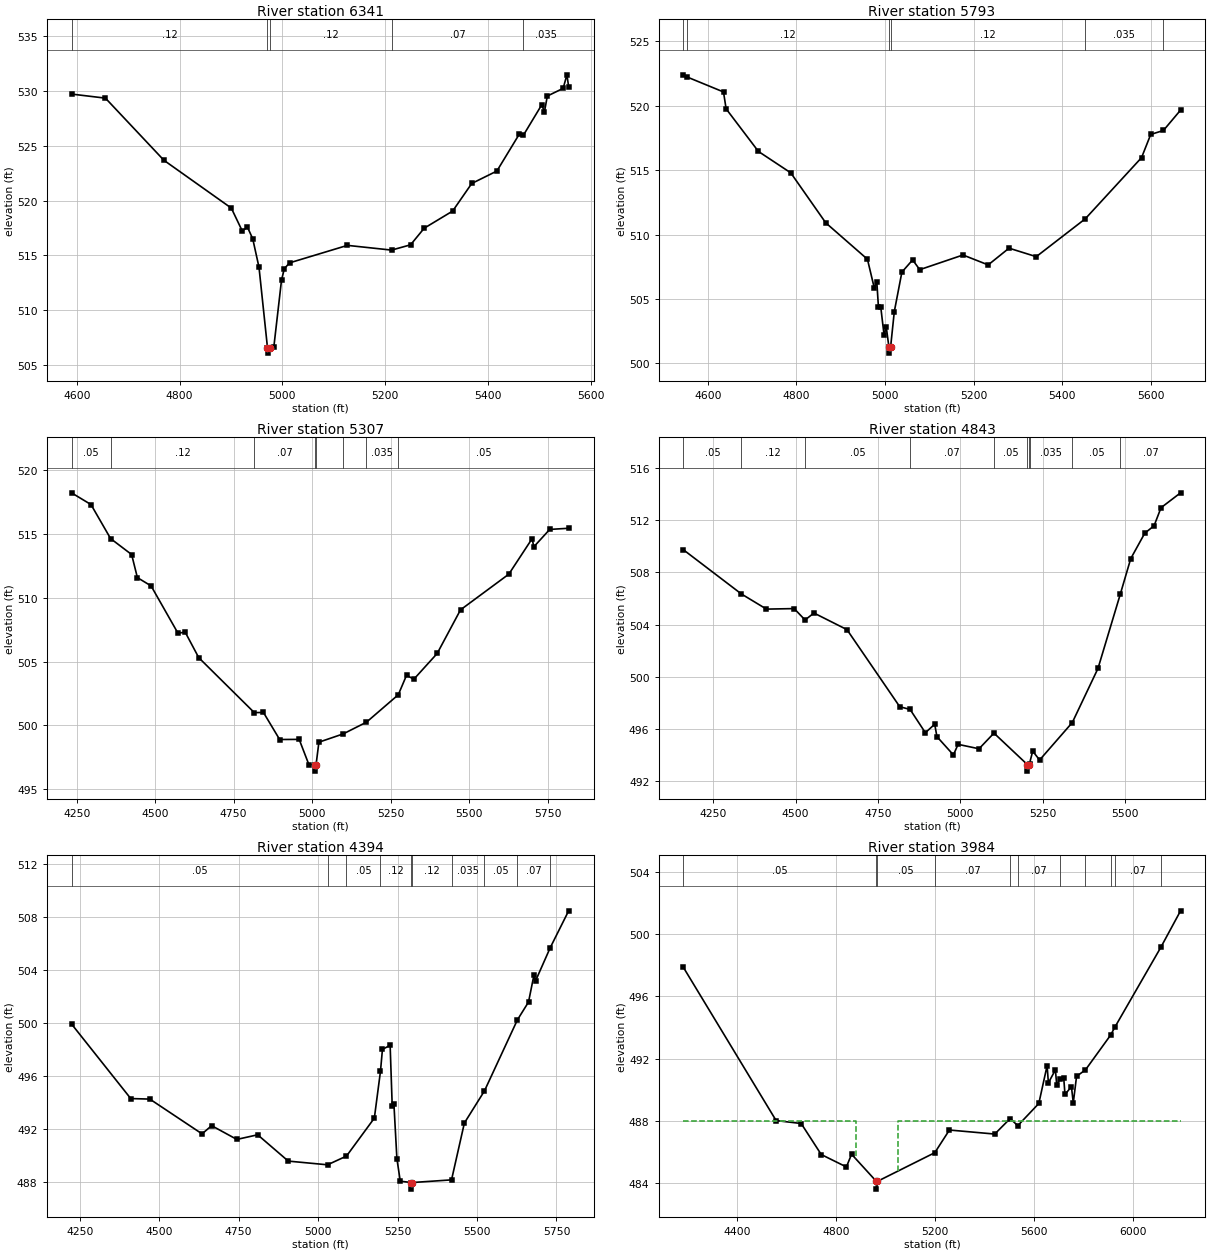
Type RM Length L Ch R = 1 ,6341    ,548,548,548
BEGIN DESCRIPTION:
XS6621
END DESCRIPTION:
XS GIS Cut Line= 2
      2470069.47      13846667.8       2469124.5     13846459.73
#Sta/Elev= 30
  4589.6  529.68  4655.6  529.31  4769.4  523.66  4900.6  519.31  4921.8  517.24
  4932.1  517.57  4942.3  516.52  4954.5  513.93    4971  506.62  4971.3  506.12
    4975  506.62  4983.3  506.65  4998.3  512.75  5003.8   513.8    5014  514.33
  5126.6  515.92  5212.5  515.49  5249.5  515.97    5276  517.48  5331.4  519.04
  5368.6  521.55  5417.5  522.68  5461.2  526.04  5468.9  525.92  5504.9  528.71
    5510  528.05  5515.7   529.5  5546.5   530.2  5553.8  531.43  5557.2  530.36
#Mann= 5 ,-1 , 0
  4589.6     .12       0    4971     .05       0    4975     .12       0
  5212.5     .07       0  5468.9    .035       0
Bank Sta=4971,4975
XS Rating Curve= 0 ,0
Exp/Cntr=0.3,0.1

Type RM Length L Ch R = 1 ,5793    ,486,486,486
BEGIN DESCRIPTION:
XS6620
END DESCRIPTION:
XS GIS Cut Line= 3
      2470212.67     13846320.57      2469839.41      13846086.2
      2469179.81     13846259.78
#Sta/Elev= 30
  4544.8  522.41  4553.2  522.24  4635.3  521.08  4641.2  519.77  4714.2  516.46
  4787.2   514.8  4866.2  510.92  4960.4  508.09  4975.7  505.88  4981.6  506.31
  4985.2   504.4  4990.4   504.4  4997.9  502.22    5003   502.8  5008.8   501.3
    5009   500.8  5012.8   501.3  5021.1  504.03  5038.2  507.09  5062.5  508.04
  5078.5  507.28  5176.2  508.42  5233.1  507.65  5280.2  508.95  5341.7  508.29
  5452.4  511.23  5579.5  515.98  5600.2  517.78  5628.9  518.09  5667.6  519.67
#Mann= 6 ,-1 , 0
  4544.8     .05       0  4553.2     .12       0  5008.8     .05       0
  5012.8     .12       0  5452.4    .035       0  5628.9     .07       0
Bank Sta=5008.8,5012.8
XS Rating Curve= 0 ,0
Exp/Cntr=0.3,0.1

Type RM Length L Ch R = 1 ,5307    ,464,464,464
BEGIN DESCRIPTION:
XS6619
END DESCRIPTION:
XS GIS Cut Line= 3
      2470273.45     13846268.52      2470030.38     13845691.23
      2469106.78     13845439.74
#Sta/Elev= 30
  4233.6  518.24  4295.6  517.32  4358.1  514.65  4425.1   513.4  4443.4  511.59
    4487  510.94  4572.9  507.22  4595.5  507.32  4638.9  505.31  4815.8     501
    4845  501.01  4896.6  498.89  4958.8   498.9  4989.9  496.91  5008.6  496.91
  5008.9  496.41  5012.6  496.91  5021.6  498.68    5099  499.33  5173.2  500.25
  5274.5   502.4  5300.8  503.93  5324.1  503.62  5398.4  505.64  5472.7  509.06
  5626.6  511.86  5700.9  514.65  5706.1     514  5756.9  515.37  5817.2  515.46
#Mann= 8 ,-1 , 0
  4233.6     .05       0  4358.1     .12       0  4815.8     .07       0
  5008.6     .05       0  5012.6     .07       0    5099     .05       0
  5173.2    .035       0  5274.5     .05       0
Bank Sta=5008.6,5012.6
XS Rating Curve= 0 ,0
Exp/Cntr=0.3,0.1

Type RM Length L Ch R = 1 ,4843    ,449,449,449
BEGIN DESCRIPTION:
XS6618
END DESCRIPTION:
XS GIS Cut Line= 3
      2470351.56     13846090.54      2470321.18     13845426.48
      2469697.36     13844858.97
#Sta/Elev= 30
  4159.9  509.72  4335.7  506.34  4411.8  505.18  4495.8  505.22  4528.8  504.35
  4555.9  504.88    4656  503.61  4816.1  497.71  4847.5   497.5  4893.8  495.72
  4922.2  496.37  4928.9  495.42  4978.9  494.02  4993.1  494.83  5056.6  494.49
  5101.9  495.69  5203.3  493.28  5203.5  492.78  5207.3  493.28  5209.8  493.36
  5219.5  494.31  5240.4  493.63  5339.6   496.5  5417.5  500.64  5485.5  506.35
  5516.8  509.04  5559.4  510.99  5587.7  511.56  5608.7  512.94    5668  514.08
#Mann= 10 ,-1 , 0
  4159.9     .05       0  4335.7     .12       0  4528.8     .05       0
  4847.5     .07       0  5101.9     .05       0  5203.3     .05       0
  5207.3     .05       0  5209.8    .035       0  5339.6     .05       0
  5485.5     .07       0
Bank Sta=5203.3,5207.3
XS Rating Curve= 0 ,0
Exp/Cntr=0.3,0.1

Type RM Length L Ch R = 1 ,4394    ,410,410,410
BEGIN DESCRIPTION:
XS6617
END DESCRIPTION:
XS GIS Cut Line= 3
       2470807.3     13845752.02      2470525.17     13845014.15
      2469796.04     13844753.75
#Sta/Elev= 30
  4224.2  499.93  4410.5  494.29  4470.6  494.25  4634.9  491.62    4665  492.24
  4744.4   491.2  4809.9  491.55  4906.2  489.56  5029.7  489.28  5089.4  489.94
    5177  492.81  5196.3  496.35  5202.5  498.01  5226.7  498.32  5233.3  493.69
  5238.6  493.88    5248  489.74  5258.6  488.04  5292.9  487.94  5293.2  487.44
  5296.9  487.94  5419.9  488.14  5460.3  492.44  5523.5  494.87  5627.1  500.24
  5662.1  501.59  5679.3  503.64  5684.6  503.21  5730.6  505.71  5788.4  508.49
#Mann= 10 ,-1 , 0
  4224.2     .05       0  5029.7     .07       0  5089.4     .05       0
  5196.3     .12       0  5292.9     .05       0  5296.9     .12       0
  5419.9    .035       0  5523.5     .05       0  5627.1     .07       0
  5730.6     .12       0
Bank Sta=5292.9,5296.9
XS Rating Curve= 0 ,0
Exp/Cntr=0.3,0.1

Type RM Length L Ch R = 1 ,3984    ,609,609,609
BEGIN DESCRIPTION:
XS6616
END DESCRIPTION:
XS GIS Cut Line= 4
      2470863.72     13845704.23      2470976.56     13845083.59
      2470798.61      13844814.5      2469780.41     13844519.87
#Sta/Elev= 30
  4181.2  497.87  4556.6     488  4658.1  487.81  4739.4  485.81  4841.2  485.01
  4862.2  485.83  4962.6  484.08  4962.8  483.58  4966.6  484.08  5199.3  485.93
  5258.4  487.39    5442  487.13  5504.5  488.13  5535.3  487.67  5620.5   489.1
  5654.1  491.54  5659.3  490.43  5687.7  491.27  5692.9  490.32  5707.9  490.69
  5721.3  490.77  5726.5  489.68  5752.6  490.19  5760.1  489.14  5773.4  490.85
  5809.6  491.27  5911.4  493.51  5927.8     494  6114.8  499.17  6194.6  501.52
#Mann= 11 ,-1 , 0
  4181.2     .05       0  4962.6     .05       0  4966.6     .05       0
  5199.3     .07       0  5504.5     .12       0  5535.3     .07       0
  5707.9    .035       0  5809.6     .07       0  5911.4     .05       0
  5927.8     .07       0  6114.8     .12       0
#XS Ineff= 2 , 0
       0    4880     488    5050       0     488
Permanent Ineff=
       F       F
Bank Sta=4962.6,4966.6
XS Rating Curve= 0 ,0
Exp/Cntr=0.3,0.1

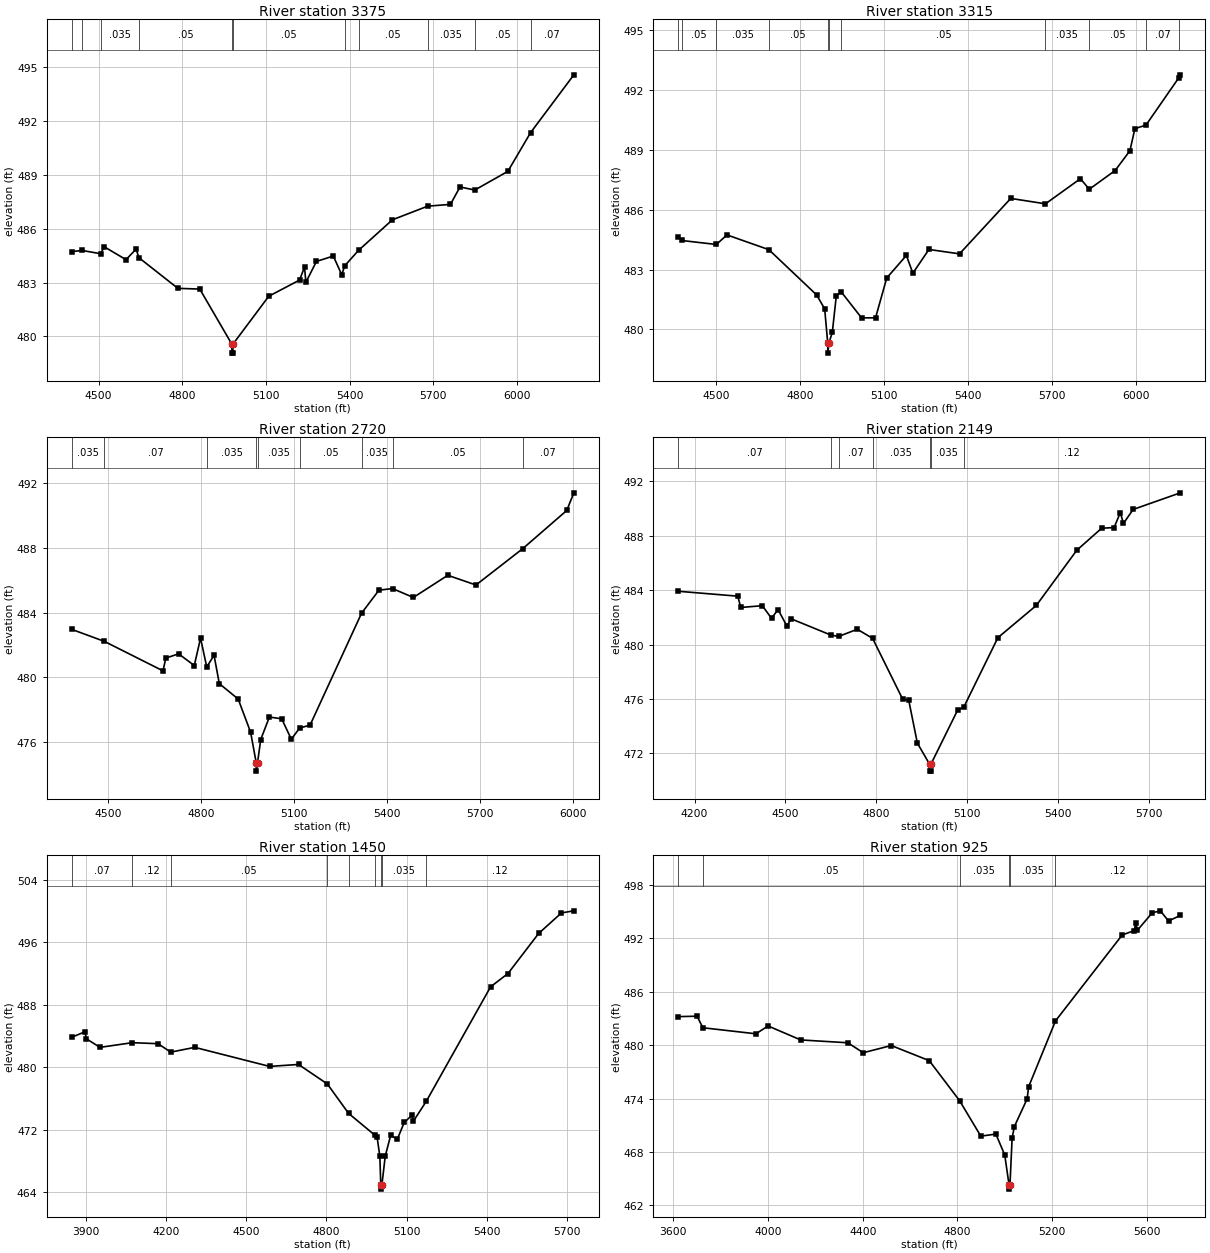
Type RM Length L Ch R = 1 ,3375    ,60,60,60
BEGIN DESCRIPTION:
XS6615
END DESCRIPTION:
XS GIS Cut Line= 4
      2471605.92     13844857.91      2471189.24     13844528.04
      2470924.48      13844545.4      2469930.52     13844410.85
#Sta/Elev= 30
  4404.1  484.73  4441.7  484.79  4507.7  484.61  4520.1     485  4598.5  484.28
  4634.8  484.87  4644.6  484.39  4784.5  482.68    4863  482.64  4977.9  479.57
  4978.1  479.07  4981.6  479.07  4981.9  479.57  5110.2  482.24  5220.5  483.14
  5238.4  483.86  5243.4  483.02  5281.1  484.18  5341.6  484.48  5371.9  483.44
  5382.7  483.94  5432.3   484.8  5553.5   486.5  5679.8  487.26  5761.7  487.36
  5795.7  488.33  5848.9  488.16  5967.3   489.2  6048.9  491.36  6203.9  494.58
#Mann= 11 ,-1 , 0
  4404.1    .035       0  4441.7     .05       0  4507.7    .035       0
  4644.6     .05       0  4977.9     .05       0  4981.9     .05       0
  5382.7     .07       0  5432.3     .05       0  5679.8    .035       0
  5848.9     .05       0  6048.9     .07       0
Bank Sta=4977.9,4981.9
XS Rating Curve= 0 ,0
Exp/Cntr=0.3,0.1

Type RM Length L Ch R = 1 ,3315    ,595,595,595
BEGIN DESCRIPTION:
XS6614
END DESCRIPTION:
XS GIS Cut Line= 4
      2471631.98     13844831.89       2471184.9     13844471.61
       2470937.5     13844471.61      2469973.96     13844358.77
#Sta/Elev= 30
  4365.5  484.65  4377.8  484.46  4501.5  484.26  4539.4  484.74  4688.9     484
  4859.3  481.73  4888.1  481.03    4899  479.31  4899.3  478.81    4903  479.31
  4915.3  479.85  4929.7   481.7  4947.3  481.88  5019.6  480.58  5069.6  480.58
  5109.6  482.58  5179.6  483.71  5202.8  482.82  5260.1  484.01  5369.3  483.79
  5552.1  486.57  5676.1   486.3  5800.7  487.56  5832.3  487.03  5924.6  487.97
  5977.3  488.96  5995.1  490.07  6034.8  490.25  6151.2  492.61  6157.2  492.77
#Mann= 11 ,-1 , 0
  4365.5     .07       0  4377.8     .05       0  4501.5    .035       0
  4688.9     .05       0    4899     .05       0    4903     .05       0
  4947.3     .05       0  5676.1    .035       0  5832.3     .05       0
  6034.8     .07       0  6151.2     .12       0
Bank Sta=4899,4903
XS Rating Curve= 0 ,0
Exp/Cntr=0.3,0.1

Type RM Length L Ch R = 1 ,2720    ,571,571,571
BEGIN DESCRIPTION:
XS6613
END DESCRIPTION:
XS GIS Cut Line= 2
      2471586.42     13843878.89      2469982.27      13844095.4
#Sta/Elev= 30
  4384.1  482.96  4489.1  482.22  4678.2   480.4  4687.3  481.19  4728.6  481.45
  4779.1  480.73  4799.3  482.42  4819.2  480.64  4842.8  481.36  4859.8  479.61
  4920.6  478.66  4960.7  476.61  4978.9  474.71  4979.1  474.21  4982.9  474.71
  4993.3  476.16  5021.2  477.55  5060.9  477.44  5091.9  476.18  5118.8  476.87
  5152.4  477.05  5318.4  483.96  5374.4  485.38  5418.2  485.48  5485.4  484.93
  5596.4   486.3  5687.2   485.7  5837.8  487.94  5979.9   490.3  6002.8  491.39
#Mann= 9 ,-1 , 0
  4384.1    .035       0  4489.1     .07       0  4819.2    .035       0
  4978.9    .035       0  4982.9    .035       0  5118.8     .05       0
  5318.4    .035       0  5418.2     .05       0  5837.8     .07       0
Bank Sta=4978.9,4982.9
XS Rating Curve= 0 ,0
Exp/Cntr=0.3,0.1

Type RM Length L Ch R = 1 ,2149    ,699,699,699
BEGIN DESCRIPTION:
XS6612
END DESCRIPTION:
XS GIS Cut Line= 3
      2471524.14     13843796.89      2470894.26     13843426.18
      2469992.14     13843636.13
#Sta/Elev= 30
  4146.1  483.91  4342.6  483.55  4352.5  482.72  4423.6  482.85    4454  481.92
  4475.5  482.57  4504.8  481.35  4518.4  481.89  4649.2   480.7  4675.2  480.59
  4737.1  481.12  4787.6  480.45  4886.5     476    4907  475.89  4935.3  472.76
  4975.9   471.2  4976.2   470.7  4979.7   470.7  4979.9   471.2  5068.2  475.18
  5088.6   475.4  5201.1   480.5    5328  482.87  5461.4  486.92  5543.6  488.54
  5584.7  488.59  5605.2  489.69  5615.5  488.89  5647.6  489.92  5803.2  491.14
#Mann= 7 ,-1 , 0
  4146.1     .07       0  4649.2     .12       0  4675.2     .07       0
  4787.6    .035       0  4975.9    .035       0  4979.9    .035       0
  5088.6     .12       0
Bank Sta=4975.9,4979.9
XS Rating Curve= 0 ,0
Exp/Cntr=0.3,0.1

Type RM Length L Ch R = 1 ,1450    ,525,525,525
BEGIN DESCRIPTION:
XS6611
END DESCRIPTION:
XS GIS Cut Line= 3
      2471458.31     13843618.72      2471006.94     13842938.19
      2469959.17     13842757.78
#Sta/Elev= 30
  3846.5  483.84  3895.3  484.54  3901.3  483.65    3952  482.55  4073.4  483.15
    4169  483.02  4217.4  481.94  4306.9  482.55  4587.1  480.11  4695.5  480.36
  4803.4  477.86  4882.8   474.1  4982.3  471.27  4989.8  471.02  4999.9  468.61
  5003.5  464.89  5003.8  464.39  5007.5  464.89  5020.2  468.63  5040.5  471.28
  5065.4  470.78  5091.3  472.94  5120.3  473.85  5125.3  473.08  5173.8  475.64
  5414.7  490.31  5479.7  492.01  5594.5  497.14  5679.8  499.77  5726.3  500.04
#Mann= 9 ,-1 , 0
  3846.5     .07       0  4073.4     .12       0  4217.4     .05       0
  4803.4    .035       0  4882.8    .063       0  4982.3    .035       0
  5003.5    .035       0  5007.5    .035       0  5173.8     .12       0
Bank Sta=5003.5,5007.5
XS Rating Curve= 0 ,0
Exp/Cntr=0.3,0.1

Type RM Length L Ch R = 1 ,925     ,519,519,519
BEGIN DESCRIPTION:
XS6610
END DESCRIPTION:
XS GIS Cut Line= 3
      2471361.12     13843375.71      2470840.28     13842452.08
      2469791.63     13842292.36
#Sta/Elev= 30
  3620.4  483.21    3700  483.26  3724.3  481.96  3948.4  481.28  4000.1  482.16
  4137.8  480.59    4337  480.27    4402  479.15  4520.4  479.96  4680.8  478.26
  4808.7  473.77  4898.7  469.77  4962.3     470  4999.7  467.66  5017.9  464.31
  5018.2  463.81  5021.9  464.31  5030.9  469.51  5040.1  470.83  5094.4  473.96
  5100.8  475.33  5214.2  482.73  5495.9  492.39  5545.9  492.88  5554.4  493.77
  5559.5   492.9    5623  494.89  5657.2  495.11  5691.7  493.97  5741.5  494.59
#Mann= 6 ,-1 , 0
  3620.4     .12       0  3724.3     .05       0  4808.7    .035       0
  5017.9    .035       0  5021.9    .035       0  5214.2     .12       0
Bank Sta=5017.9,5021.9
XS Rating Curve= 0 ,0
Exp/Cntr=0.3,0.1

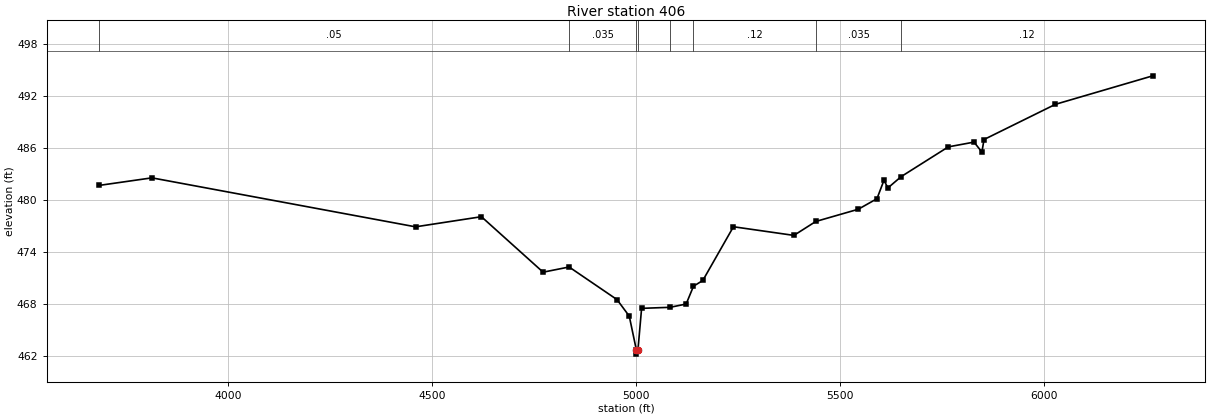
Type RM Length L Ch R = 1 ,406     ,0,0,0
BEGIN DESCRIPTION:
XS6609
END DESCRIPTION:
XS GIS Cut Line= 4
      2471270.83     13843118.73      2470958.33     13842042.36
      2470506.94     13841868.75      2469578.23     13842166.77
#Sta/Elev= 30
  3685.4  481.67  3814.2  482.54  4459.8  476.88  4621.1  478.05  4772.2  471.64
  4835.9  472.24  4953.2  468.47  4983.2  466.56  5000.5  462.67  5000.8  462.17
  5004.5  462.67  5013.4  467.46  5083.2  467.58  5122.5  467.96  5140.5  470.02
  5163.3  470.68  5238.3  476.89  5386.4  475.89    5440   477.5  5543.9  478.91
  5589.8  480.13  5606.9  482.25  5616.7  481.38    5649  482.68  5764.5  486.12
  5827.5  486.67  5846.8  485.52    5852  486.97    6027  491.04  6265.2  494.33
#Mann= 8 ,-1 , 0
  3685.4     .05       0  4835.9    .035       0  5000.5    .035       0
  5004.5    .035       0  5083.2     .05       0  5140.5     .12       0
    5440    .035       0    5649     .12       0
Bank Sta=5000.5,5004.5
XS Rating Curve= 0 ,0
Exp/Cntr=0.3,0.1

Chan Stop Cuts=-1
Use User Specified Reach Order=0
Composite Channel Slope=5