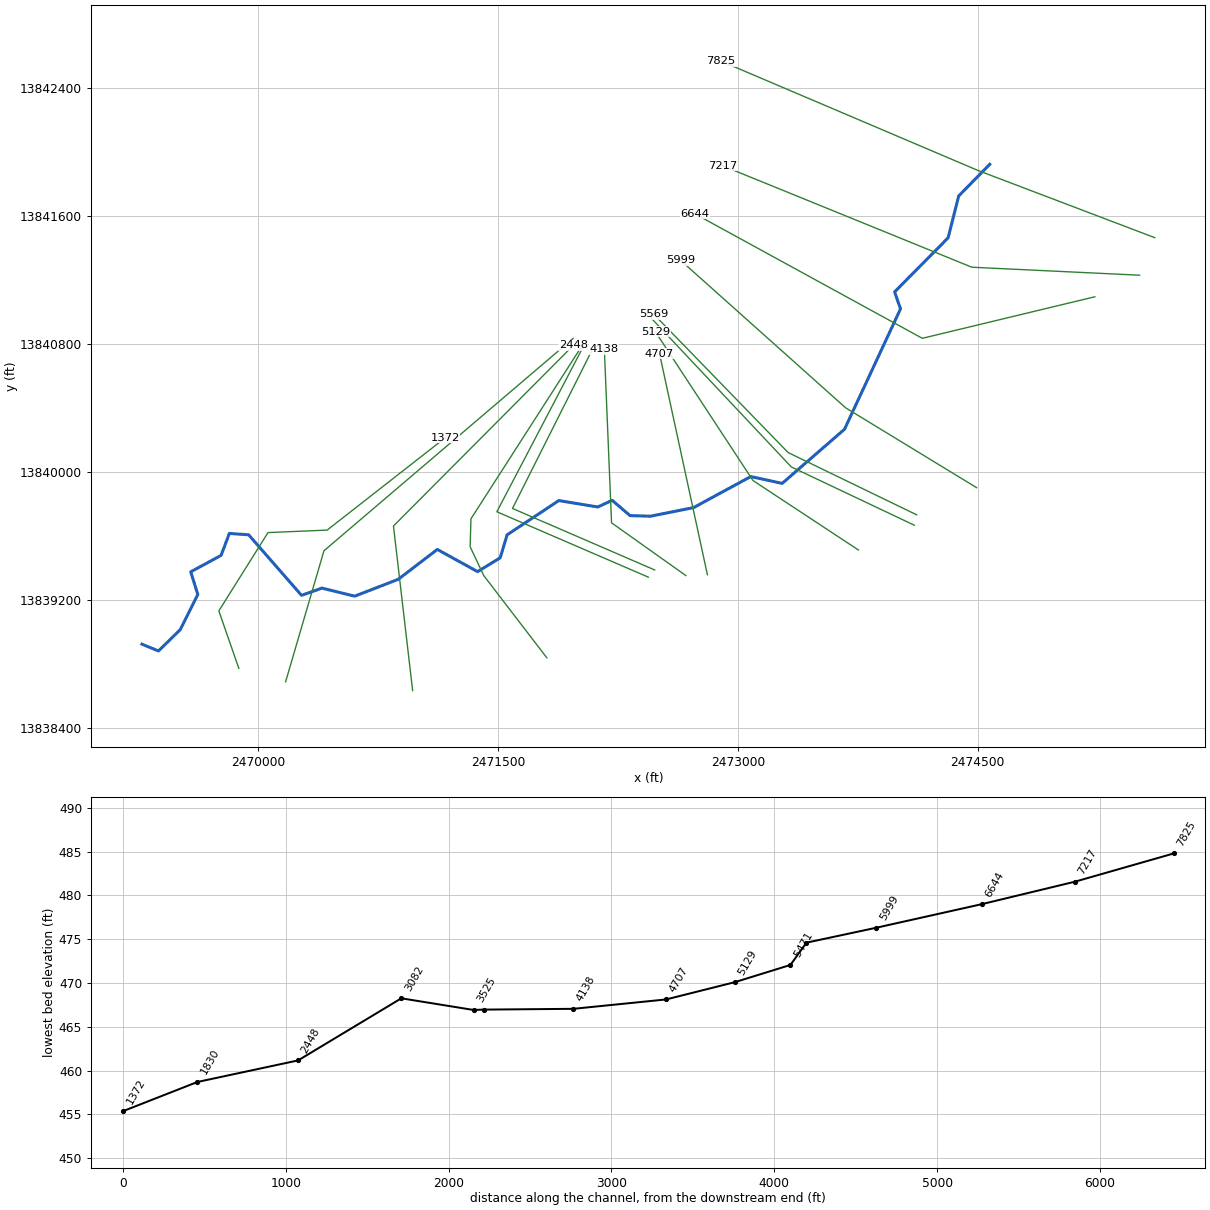
--- Stream0385.prj (project) ---

Proj Title=Stream0385 Base Level Engineering
Current Plan=p01
Default Exp/Contr=0.3,0.1
English Units
Geom File=g01
Flow File=f01
Plan File=p01
BEGIN DESCRIPTION:
Stream0385
END DESCRIPTION:

--- Stream0385.p01 (plan) ---

Plan Title=Multiple Run
Short Identifier=Multiple
Geom File=g01
Flow File=f01
Subcritical Flow
K Sum by GR= 0
Std Step Tol= 0.01
Critical Tol= 0.01
Num of Std Step Trials= 20
Max Error Tol= 0.3
Flow Tol Ratio= 0.001
Split Flow NTrial= 30
Split Flow Tol= 0.02
Split Flow Ratio= 0.02
Log Output Level= 0
Friction Slope Method= 1
Unsteady Friction Slope Method= 2
Unsteady Bridges Friction Slope Method= 1
Parabolic Critical Depth
Global Vel Dist=  1 , 1 , 1
Global Log Level= 0
CheckData=True
Encroach Param= -1, 0, 0, 0
BEGIN DESCRIPTION:
Multiple Run
END DESCRIPTION:

--- Stream0385.f01 (steady flow) ---

Flow Title=Multiple
Number of Profiles=7
Profile Names=10-year,25-year,50-year,1pct_min,100-year,1pct_plu,500-year
River Rch & RM= Stream0385,Reach-1,7825
     722    1162    1559    1013    2021    4033    3362
River Rch & RM= Stream0385,Reach-1,4707
     814    1317    1772    1153    2301    4590    3841
Boundary for River Rch & Prof#=Stream0385,Reach-1,1
Up Type=0
Dn Type=3
Dn Slope=0.005
Boundary for River Rch & Prof#=Stream0385,Reach-1,2
Up Type=0
Dn Type=3
Dn Slope=0.005
Boundary for River Rch & Prof#=Stream0385,Reach-1,3
Up Type=0
Dn Type=3
Dn Slope=0.005
Boundary for River Rch & Prof#=Stream0385,Reach-1,4
Up Type=0
Dn Type=3
Dn Slope=0.005
Boundary for River Rch & Prof#=Stream0385,Reach-1,5
Up Type=0
Dn Type=3
Dn Slope=0.005
Boundary for River Rch & Prof#=Stream0385,Reach-1,6
Up Type=0
Dn Type=3
Dn Slope=0.005
Boundary for River Rch & Prof#=Stream0385,Reach-1,7
Up Type=0
Dn Type=3
Dn Slope=0.005

--- Stream0385.g01 (geometry) ---

Geom Title=Existing Conditions

River Reach=Stream0385,Reach-1
Reach XY= 30
      2474575.00     13841925.00      2474380.84     13841727.29
      2474314.52     13841465.20      2473980.12     13841127.29
      2474017.16     13841021.60      2473667.14     13840268.83
      2473277.29     13839930.10      2473080.97     13839972.86
      2472723.45     13839778.75      2472454.96     13839725.05
      2472326.47     13839728.54      2472214.36     13839824.35
      2472125.01     13839782.59      2471880.93     13839822.76
      2471557.87     13839608.54      2471514.61     13839464.90
      2471373.27     13839378.31      2471121.60     13839517.22
      2470877.42     13839330.54      2470604.97     13839225.04
      2470400.00     13839275.39      2470272.70     13839230.09
      2469942.04     13839608.77      2469821.39     13839617.13
      2469769.89     13839480.12      2469580.09     13839377.31
      2469624.25     13839235.69      2469514.24     13839015.32
      2469378.39     13838882.59      2469275.00     13838925.00

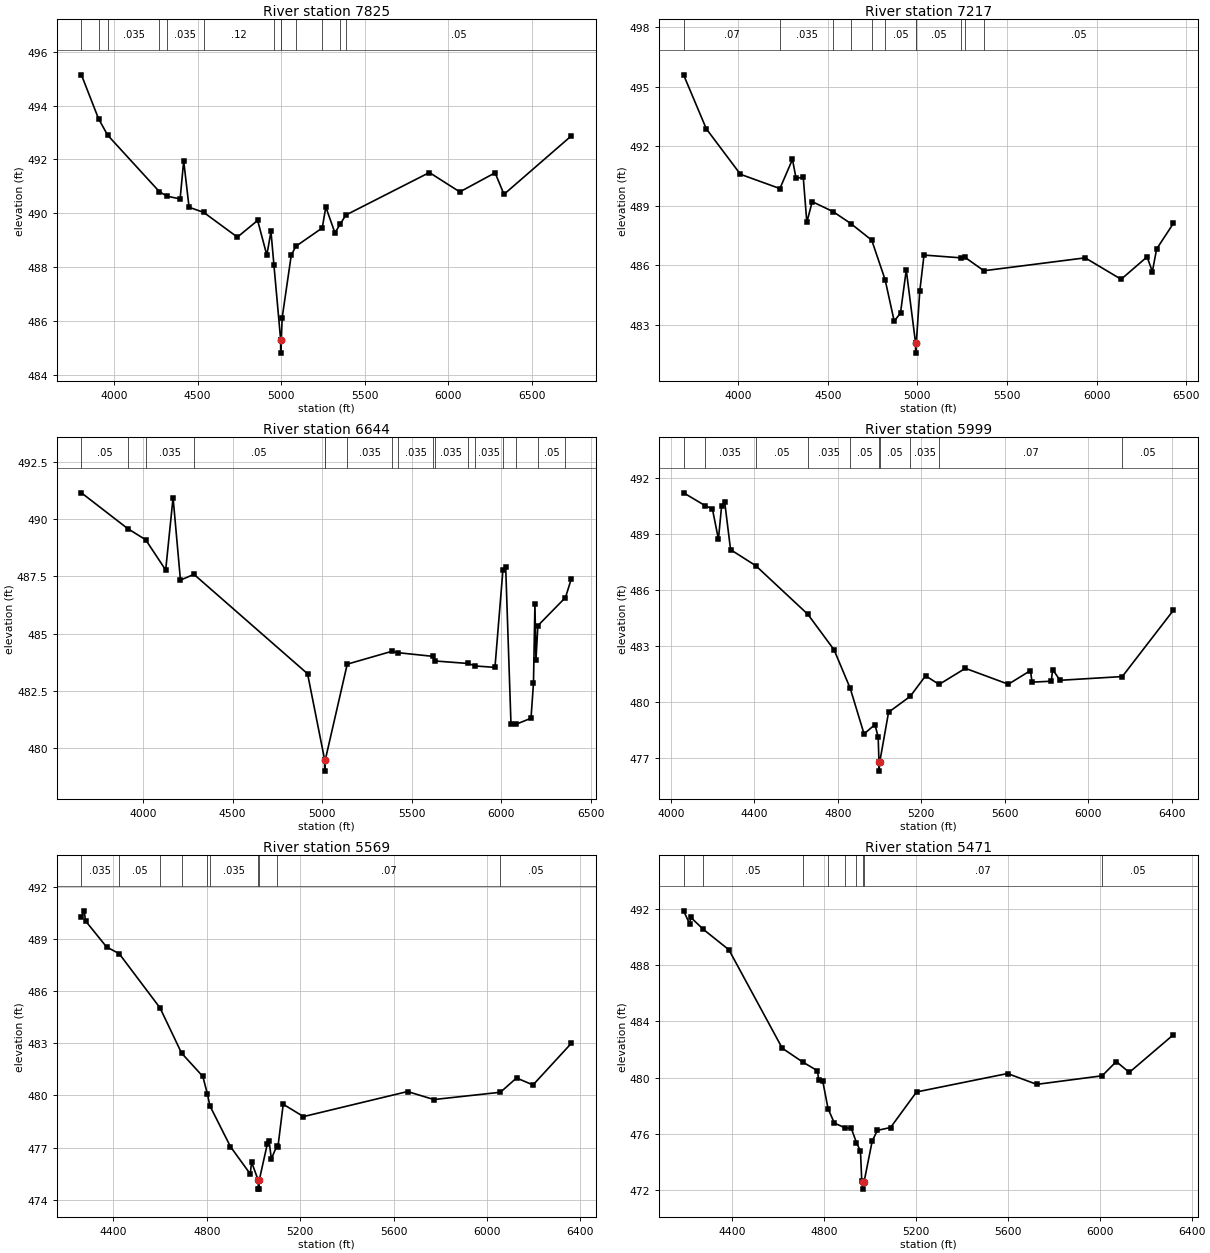
Type RM Length L Ch R = 1,7825,608,608,608
BEGIN DESCRIPTION:
XS6635
END DESCRIPTION:
XS GIS Cut Line= 3
      2475606.49     13841466.40      2474502.85     13841885.89
      2472894.91     13842570.01
#Sta/Elev= 30
  3806.0  495.14  3908.3  493.51  3962.6  492.90  4271.8  490.80  4317.8  490.63
  4396.0  490.53  4417.4  491.94  4449.5  490.22  4536.8  490.03  4738.3  489.11
  4859.4  489.73  4914.3  488.44  4939.1  489.32  4956.5  488.09  4996.9  485.30
  4997.2  484.80  5000.9  485.30  5006.1  486.12  5060.4  488.44  5087.8  488.77
  5245.6  489.45  5266.9  490.23  5321.2  489.27  5353.9  489.60  5386.5  489.93
  5886.0  491.51  6067.8  490.79  6278.7  491.50  6331.9  490.70  6734.1  492.87
#Mann=13,-1,0
  3806.0   0.035       0  3908.3    0.05       0  3962.6   0.035       0
  4271.8    0.07       0  4317.8   0.035       0  4536.8    0.12       0
  4956.5    0.12       0  4996.9    0.05       0  5000.9    0.12       0
  5087.8    0.12       0  5245.6    0.07       0  5353.9   0.035       0
  5386.5    0.05       0
Bank Sta=4996.9,5000.9
Exp/Cntr=0.3,0.1

Type RM Length L Ch R = 1,7217,573,573,573
BEGIN DESCRIPTION:
XS6634
END DESCRIPTION:
XS GIS Cut Line= 3
      2475511.65     13841231.69      2474462.90     13841281.63
      2472904.78     13841915.87
#Sta/Elev= 30
  3695.9  495.59  3822.7  492.87  4012.9  490.58  4233.1  489.86  4303.2  491.33
  4323.3  490.37  4363.3  490.44  4383.3  488.16  4413.4  489.20  4529.4  488.70
  4628.2  488.10  4745.3  487.26  4819.9  485.27  4870.9  483.17  4905.8  483.60
  4937.9  485.76  4989.9  482.07  4990.1  481.57  4993.9  482.07  5013.5  484.71
  5036.9  486.51  5243.3  486.37  5263.3  486.41  5370.9  485.72  5935.9  486.37
  6136.3  485.29  6281.0  486.42  6310.5  485.68  6334.5  486.82  6428.1  488.11
#Mann=11,-1,0
  3695.9    0.07       0  4233.1   0.035       0  4529.4    0.07       0
  4628.2    0.05       0  4745.3    0.07       0  4819.9    0.05       0
  4989.9    0.05       0  4993.9    0.05       0  5243.3    0.12       0
  5263.3   0.035       0  5370.9    0.05       0
Bank Sta=4989.9,4993.9
Exp/Cntr=0.3,0.1

Type RM Length L Ch R = 1,6644,645,645,645
BEGIN DESCRIPTION:
XS6633
END DESCRIPTION:
XS GIS Cut Line= 3
      2475231.98     13841096.87      2474153.28     13840837.18
      2472730.06     13841616.20
#Sta/Elev= 30
  3657.2  491.15  3915.0  489.59  4015.7  489.10  4127.2  487.78  4168.4  490.94
  4209.5  487.34  4284.9  487.59  4918.5  483.25  5013.6  479.50  5013.8  479.00
  5017.6  479.50  5139.7  483.67  5388.2  484.23  5423.7  484.17  5618.5  484.01
  5626.7  483.81  5813.3  483.70  5854.9  483.59  5963.6  483.53  6008.1  487.79
  6023.3  487.93  6053.0  481.05  6083.0  481.05  6164.6  481.31  6178.4  482.84
  6186.5  486.29  6192.2  483.84  6202.9  485.35  6356.8  486.58  6389.2  487.39
#Mann=17,-1,0
  3657.2    0.05       0  3915.0    0.07       0  4015.7   0.035       0
  4284.9    0.05       0  5013.6    0.05       0  5017.6    0.05       0
  5139.7   0.035       0  5388.2    0.05       0  5423.7   0.035       0
  5618.5    0.05       0  5626.7   0.035       0  5813.3    0.05       0
  5854.9   0.035       0  6008.1    0.05       0  6083.0   0.035       0
  6202.9    0.05       0  6356.8   0.035       0
Bank Sta=5013.6,5017.6
Exp/Cntr=0.3,0.1

Type RM Length L Ch R = 1,5999,430,430,430
BEGIN DESCRIPTION:
XS6632
END DESCRIPTION:
XS GIS Cut Line= 3
      2474492.83     13839903.34      2473673.87     13840402.71
      2472640.14     13841326.57
#Sta/Elev= 30
  4061.6  491.21  4164.0  490.53  4199.6  490.35  4228.5  488.73  4243.9  490.53
  4258.2  490.74  4286.6  488.17  4407.4  487.31  4656.7  484.71  4782.2  482.81
  4859.5  480.75  4925.8  478.31  4977.8  478.81  4993.3  478.15  4997.1  476.82
  4997.4  476.32  5001.1  476.82  5043.1  479.47  5146.8  480.32  5220.3  481.42
  5285.2  480.96  5410.9  481.82  5616.6  480.97  5722.7  481.70  5730.1  481.08
  5822.2  481.13  5828.9  481.75  5864.2  481.18  6162.3  481.38  6407.2  484.93
#Mann=10,-1,0
  4061.6    0.05       0  4164.0   0.035       0  4407.4    0.05       0
  4656.7   0.035       0  4859.5    0.05       0  4997.1    0.05       0
  5001.1    0.05       0  5146.8   0.035       0  5285.2    0.07       0
  6162.3    0.05       0
Bank Sta=4997.1,5001.1
Exp/Cntr=0.3,0.1

Type RM Length L Ch R = 1,5569,98,98,98
BEGIN DESCRIPTION:
XS6631
END DESCRIPTION:
XS GIS Cut Line= 3
      2474118.28     13839733.55      2473314.31     13840123.06
      2472475.36     13840986.97
#Sta/Elev= 30
  4263.3  490.26  4275.3  490.61  4280.9  490.03  4371.2  488.53  4424.9  488.15
  4599.9  485.03  4692.2  482.43  4783.2  481.09  4803.2  480.06  4813.1  479.41
  4901.6  477.05  4986.4  475.48  4991.9  476.17  5020.5  475.11  5020.8  474.61
  5024.3  474.61  5024.6  475.11  5059.7  477.23  5067.0  477.36  5076.7  476.35
  5099.3  477.07  5104.8  477.04  5127.4  479.49  5214.2  478.78  5659.7  480.22
  5772.7  479.76  6057.6  480.18  6126.4  481.00  6197.1  480.60  6360.9  482.99
#Mann=10,-1,0
  4263.3   0.035       0  4424.9    0.05       0  4599.9   0.035       0
  4692.2    0.05       0  4803.2    0.07       0  4813.1   0.035       0
  5020.5   0.035       0  5024.6   0.035       0  5099.3    0.07       0
  6057.6    0.05       0
Bank Sta=5020.5,5024.6
Exp/Cntr=0.3,0.1

Type RM Length L Ch R = 1,5471,342,342,342
BEGIN DESCRIPTION:
XS6630
END DESCRIPTION:
XS GIS Cut Line= 3
      2474103.34     13839668.61      2473334.28     13840033.17
      2472455.36     13840967.02
#Sta/Elev= 30
  4187.2  491.86  4213.4  490.94  4218.9  491.39  4273.4  490.54  4384.6  489.09
  4617.0  482.09  4705.9  481.11  4770.2  480.49  4775.8  479.82  4793.0  479.78
  4816.4  477.79  4844.0  476.77  4888.2  476.44  4917.7  476.39  4940.1  475.38
  4957.7  474.77  4963.2  472.63  4969.0  472.57  4969.3  472.07  4973.1  472.57
  5008.7  475.49  5031.4  476.25  5088.6  476.45  5201.9  478.98  5598.0  480.29
  5725.4  479.52  6010.2  480.13  6071.8  481.14  6128.4  480.37  6320.7  483.05
#Mann=9,-1,0
  4187.2   0.035       0  4273.4    0.05       0  4705.9    0.07       0
  4816.4    0.12       0  4888.2   0.035       0  4940.1    0.07       0
  4969.0    0.05       0  4973.1    0.07       0  6010.2    0.05       0
Bank Sta=4969,4973.1
Exp/Cntr=0.3,0.1

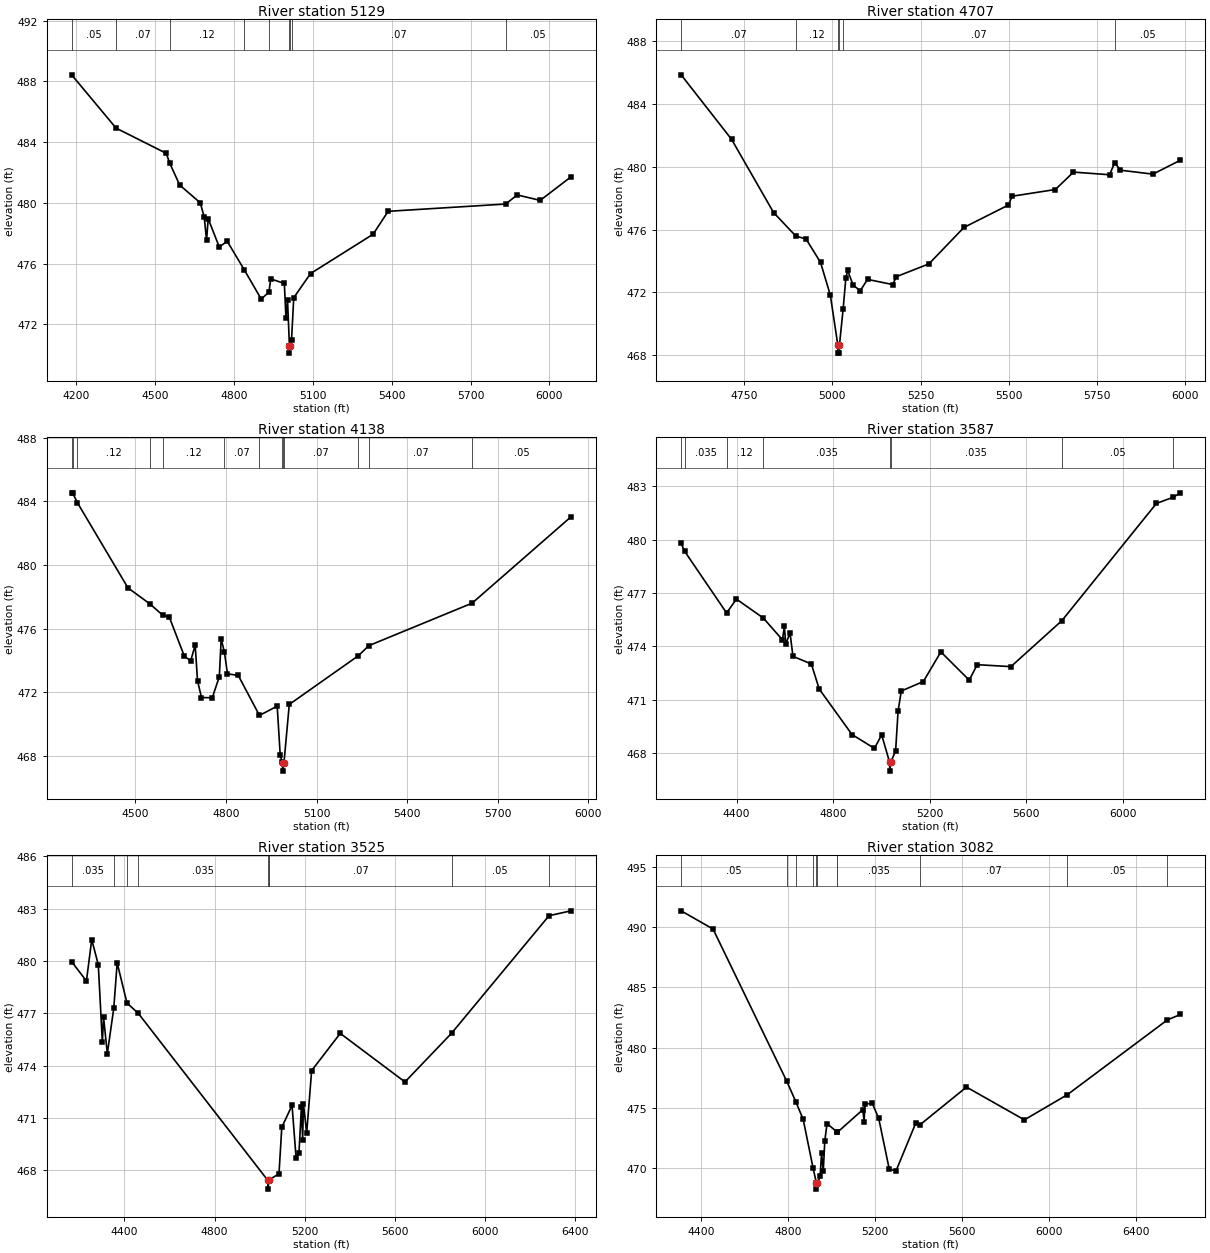
Type RM Length L Ch R = 1,5129,422,422,422
BEGIN DESCRIPTION:
XS6629
END DESCRIPTION:
XS GIS Cut Line= 3
      2473753.74     13839513.82      2473094.58     13839948.27
      2472485.32     13840877.14
#Sta/Elev= 30
  4182.0  488.43  4351.2  484.92  4542.1  483.26  4554.8  482.63  4593.3  481.17
  4671.6  480.00  4686.7  479.06  4695.5  477.53  4701.7  478.95  4743.9  477.09
  4774.0  477.47  4839.3  475.58  4903.5  473.66  4932.9  474.12  4939.6  474.99
  4991.5  474.69  4997.7  472.40  5003.7  473.59  5010.8  470.60  5011.0  470.10
  5014.9  470.60  5018.9  470.96  5027.3  473.75  5091.2  475.34  5329.3  477.93
  5386.5  479.44  5833.8  479.92  5877.8  480.52  5965.3  480.16  6082.3  481.71
#Mann=9,-1,0
  4182.0    0.05       0  4351.2    0.07       0  4554.8    0.12       0
  4839.3    0.07       0  4932.9    0.12       0  5010.8    0.05       0
  5014.9    0.12       0  5018.9    0.07       0  5833.8    0.05       0
Bank Sta=5010.8,5014.9
Exp/Cntr=0.3,0.1

Type RM Length L Ch R = 1,4707,569,569,569
BEGIN DESCRIPTION:
XS6628
END DESCRIPTION:
XS GIS Cut Line= 2
      2472809.92     13839359.02      2472510.54     13840741.17
#Sta/Elev= 30
  4572.0  485.87  4714.8  481.76  4833.9  477.09  4896.5  475.60  4926.0  475.40
  4966.9  473.91  4994.6  471.82  5015.9  468.63  5016.2  468.13  5020.0  468.13
  5020.3  468.63  5030.8  470.93  5038.6  472.94  5043.8  473.40  5059.0  472.46
  5079.5  472.11  5099.9  472.83  5171.6  472.50  5181.2  473.00  5273.9  473.82
  5372.9  476.14  5499.0  477.57  5509.2  478.13  5632.0  478.56  5683.2  479.67
  5785.5  479.50  5800.0  480.28  5816.2  479.79  5908.3  479.54  5986.2  480.43
#Mann=6,-1,0
  4572.0    0.07       0  4896.5    0.12       0  5015.9    0.05       0
  5020.3    0.12       0  5030.8    0.07       0  5800.0    0.05       0
Bank Sta=5015.9,5020.3
Exp/Cntr=0.3,0.1

Type RM Length L Ch R = 1,4138,551,551,551
BEGIN DESCRIPTION:
XS6627
END DESCRIPTION:
XS GIS Cut Line= 3
      2472675.05     13839354.03      2472210.66     13839683.60
      2472165.72     13840767.31
#Sta/Elev= 30
  4288.7  484.54  4291.9  484.54  4307.5  483.93  4475.3  478.57  4548.2  477.56
  4590.7  476.85  4611.9  476.75  4662.3  474.27  4683.2  473.99  4698.0  474.98
  4705.7  472.74  4718.9  471.68  4754.7  471.67  4778.0  473.00  4784.1  475.37
  4794.8  474.53  4805.0  473.17  4840.7  473.07  4910.9  470.56  4969.7  471.14
  4979.7  468.05  4985.9  467.65  4987.3  467.56  4987.6  467.06  4992.0  467.56
  5009.7  471.25  5238.7  474.31  5273.1  474.94  5615.3  477.61  5942.8  483.03
#Mann=13,-1,0
  4288.7    0.05       0  4291.9    0.07       0  4307.5    0.12       0
  4548.2   0.035       0  4590.7    0.12       0  4794.8    0.07       0
  4910.9    0.12       0  4985.9    0.07       0  4987.3    0.05       0
  4992.0    0.07       0  5238.7   0.035       0  5273.1    0.07       0
  5615.3    0.05       0
Bank Sta=4987.3,4992
Exp/Cntr=0.3,0.1

Type RM Length L Ch R = 1,3587,62,62,62
BEGIN DESCRIPTION:
XS6625
END DESCRIPTION:
XS GIS Cut Line= 3
      2472480.30     13839388.97      2471591.42     13839773.48
      2472085.81     13840757.26
#Sta/Elev= 30
  4169.8  479.78  4184.8  479.33  4358.2  475.87  4399.0  476.65  4510.8  475.58
  4589.6  474.36  4597.8  475.11  4603.3  474.13  4621.3  474.74  4633.2  473.43
  4709.5  473.00  4742.1  471.59  4878.0  469.03  4971.0  468.25  5000.9  469.01
  5033.9  467.47  5034.3  466.97  5038.7  467.47  5058.8  468.12  5069.0  470.35
  5082.2  471.48  5173.6  472.01  5246.4  473.68  5363.8  472.09  5397.1  472.96
  5536.6  472.85  5748.1  475.44  6139.5  482.03  6210.4  482.39  6239.3  482.63
#Mann=8,-1,0
  4169.8    0.12       0  4184.8   0.035       0  4358.2    0.12       0
  4510.8   0.035       0  5033.9   0.035       0  5038.7   0.035       0
  5748.1    0.05       0  6210.4    0.12       0
Bank Sta=5033.9,5038.7
Exp/Cntr=0.3,0.1

Type RM Length L Ch R = 1,3525,443,443,443
BEGIN DESCRIPTION:
XS6626
END DESCRIPTION:
XS GIS Cut Line= 3
      2472440.35     13839344.02      2471493.67     13839752.79
      2472042.03     13840800.50
#Sta/Elev= 30
  4166.2  479.96  4231.8  478.85  4255.3  481.22  4284.3  479.79  4302.4  475.36
  4307.8  476.77  4324.5  474.69  4353.0  477.29  4368.1  479.89  4411.5  477.59
  4461.6  477.00  5036.1  467.43  5036.4  466.93  5040.9  467.43  5042.7  467.47
  5085.5  467.81  5097.9  470.47  5143.4  471.73  5161.4  468.70  5174.1  469.00
  5185.0  471.65  5190.4  469.77  5193.9  471.80  5208.3  470.15  5230.3  473.72
  5357.1  475.85  5644.0  473.07  5850.7  475.86  6282.7  482.59  6379.9  482.87
#Mann=9,-1,0
  4166.2   0.035       0  4353.0    0.07       0  4411.5    0.12       0
  4461.6   0.035       0  5036.1   0.035       0  5040.9   0.035       0
  5042.7    0.07       0  5850.7    0.05       0  6282.7    0.12       0
Bank Sta=5036.1,5040.9
Exp/Cntr=0.3,0.1

Type RM Length L Ch R = 1,3082,634,634,634
BEGIN DESCRIPTION:
XS6624
END DESCRIPTION:
XS GIS Cut Line= 5
      2471806.14     13838839.66      2471411.64     13839354.00
      2471326.75     13839533.78      2471331.74     13839708.56
      2472019.71     13840780.40
#Sta/Elev= 30
  4308.5  491.36  4455.1  489.85  4793.5  477.24  4835.7  475.52  4869.7  474.04
  4914.8  470.04  4930.4  468.76  4930.8  468.26  4935.3  468.76  4947.3  469.31
  4954.2  471.24  4961.9  469.74  4968.9  472.25  4979.2  473.69  5025.5  473.01
  5027.0  472.98  5144.1  474.86  5149.6  473.87  5153.4  475.30  5186.8  475.40
  5216.8  474.14  5265.6  469.89  5296.8  469.79  5387.1  473.74  5405.2  473.58
  5620.3  476.73  5886.6  474.01  6084.1  476.10  6543.5  482.30  6604.0  482.76
#Mann=11,-1,0
  4308.5    0.05       0  4793.5   0.035       0  4835.7    0.07       0
  4914.8   0.035       0  4930.4   0.035       0  4935.3   0.035       0
  5025.5    0.07       0  5027.0   0.035       0  5405.2    0.07       0
  6084.1    0.05       0  6543.5    0.12       0
Bank Sta=4930.4,4935.3
Exp/Cntr=0.3,0.1

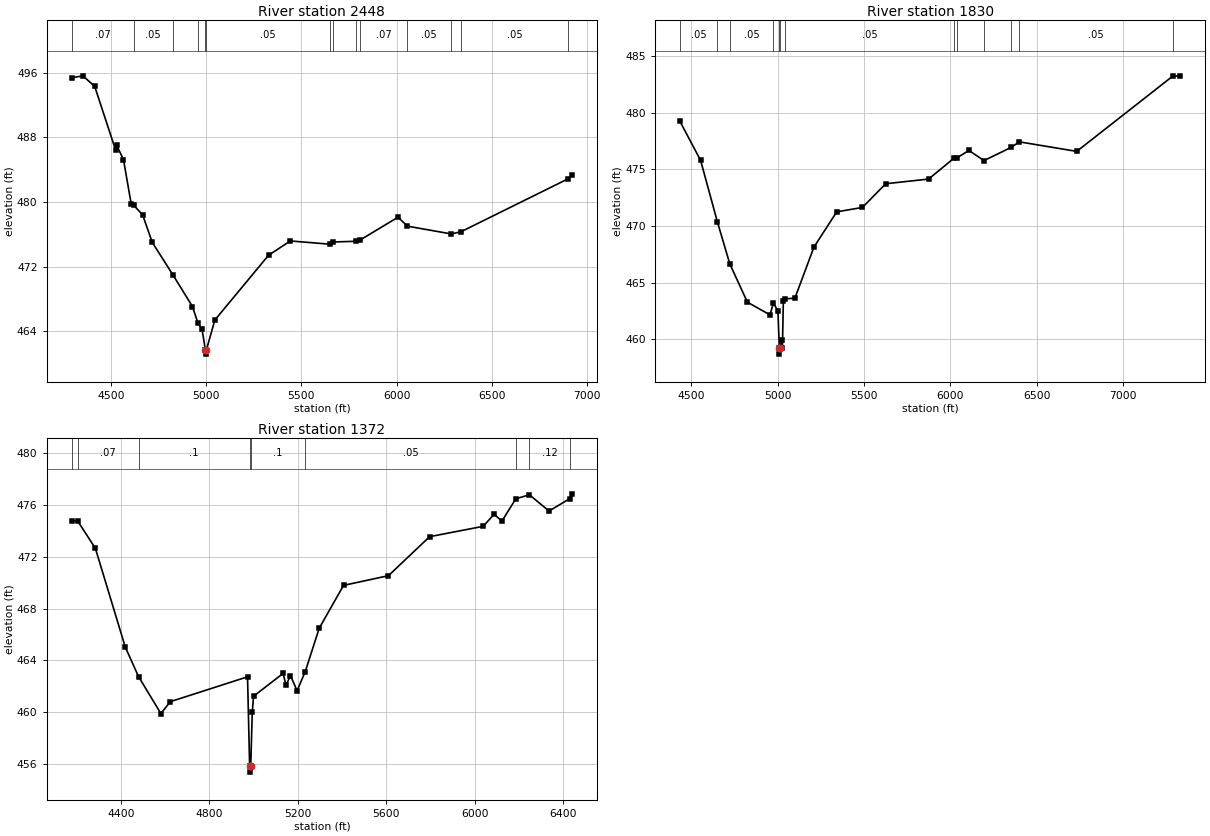
Type RM Length L Ch R = 1,2448,618,618,618
BEGIN DESCRIPTION:
XS6623
END DESCRIPTION:
XS GIS Cut Line= 3
      2470967.19     13838634.87      2470847.34     13839663.62
      2471970.97     13840792.25
#Sta/Elev= 30
  4294.0  495.38  4352.8  495.62  4414.9  494.31  4524.8  486.41  4529.8  487.03
  4566.0  485.25  4606.2  479.81  4618.8  479.62  4666.6  478.41  4717.0  475.01
  4825.4  470.99  4928.4  467.06  4956.1  465.07  4978.7  464.22  4996.4  461.67
  4996.8  461.17  5001.3  461.67  5045.8  465.39  5327.9  473.41  5442.2  475.18
  5649.8  474.78  5664.8  475.05  5785.6  475.14  5807.6  475.28  6007.9  478.12
  6057.1  477.01  6287.1  476.05  6337.6  476.31  6900.8  482.87  6922.3  483.31
#Mann=14,-1,0
  4294.0    0.07       0  4618.8    0.05       0  4825.4    0.07       0
  4956.1    0.05       0  4996.4    0.05       0  5001.3    0.05       0
  5649.8    0.12       0  5664.8    0.05       0  5785.6   0.035       0
  5807.6    0.07       0  6057.1    0.05       0  6287.1    0.07       0
  6337.6    0.05       0  6900.8    0.12       0
Bank Sta=4996.4,5001.3
Exp/Cntr=0.3,0.1

Type RM Length L Ch R = 1,1830,458,458,458
BEGIN DESCRIPTION:
XS6622
END DESCRIPTION:
XS GIS Cut Line= 3
      2470173.17     13838689.82      2470412.87     13839508.81
      2471970.48     13840836.77
#Sta/Elev= 30
  4433.0  479.23  4553.0  475.78  4650.0  470.37  4722.1  466.66  4823.9  463.29
  4954.9  462.17  4974.8  463.21  5001.0  462.52  5009.0  459.21  5009.4  458.71
  5014.0  459.21  5021.8  459.97  5027.0  459.24  5032.3  463.42  5041.5  463.58
  5099.1  463.64  5209.8  468.15  5341.7  471.25  5490.7  471.64  5625.8  473.73
  5873.9  474.14  6021.1  475.98  6038.3  476.01  6107.8  476.66  6195.2  475.77
  6352.0  476.93  6400.2  477.42  6732.6  476.58  7287.8  483.20  7333.2  483.24
#Mann=13,-1,0
  4433.0    0.05       0  4650.0    0.07       0  4722.1    0.05       0
  4974.8     0.1       0  5009.0    0.05       0  5014.0     0.1       0
  5041.5    0.05       0  6021.1    0.12       0  6038.3   0.035       0
  6195.2    0.12       0  6352.0    0.07       0  6400.2    0.05       0
  7287.8    0.12       0
Bank Sta=5009,5014
Exp/Cntr=0.3,0.1

Type RM Length L Ch R = 1,1372,0,0,0
BEGIN DESCRIPTION:
E20948
END DESCRIPTION:
XS GIS Cut Line= 5
      2469880.72     13838773.62      2469755.73     13839132.96
      2470063.02     13839622.54      2470432.81     13839638.16
      2471171.19     13840215.35
#Sta/Elev= 30
  4176.1  474.80  4203.6  474.75  4283.4  472.65  4418.8  465.02  4478.7  462.75
  4580.0  459.89  4622.5  460.81  4972.2  462.73  4981.7  455.87  4982.0  455.37
  4986.7  455.87  4993.6  459.98  4999.5  461.23  5133.1  462.99  5146.6  462.08
  5166.6  462.83  5196.6  461.65  5233.4  463.13  5296.7  466.48  5406.8  469.79
  5610.2  470.54  5796.5  473.55  6038.9  474.35  6088.6  475.28  6123.9  474.75
  6186.4  476.47  6248.1  476.79  6337.3  475.53  6431.1  476.49  6441.9  476.86
#Mann=9,-1,0
  4176.1    0.05       0  4203.6    0.07       0  4478.7     0.1       0
  4981.7    0.05       0  4986.7     0.1       0  5233.4    0.05       0
  6186.4   0.035       0  6248.1    0.12       0  6431.1    0.07       0
Bank Sta=4981.7,4986.7
Exp/Cntr=0.3,0.1

Chan Stop Cuts=-1