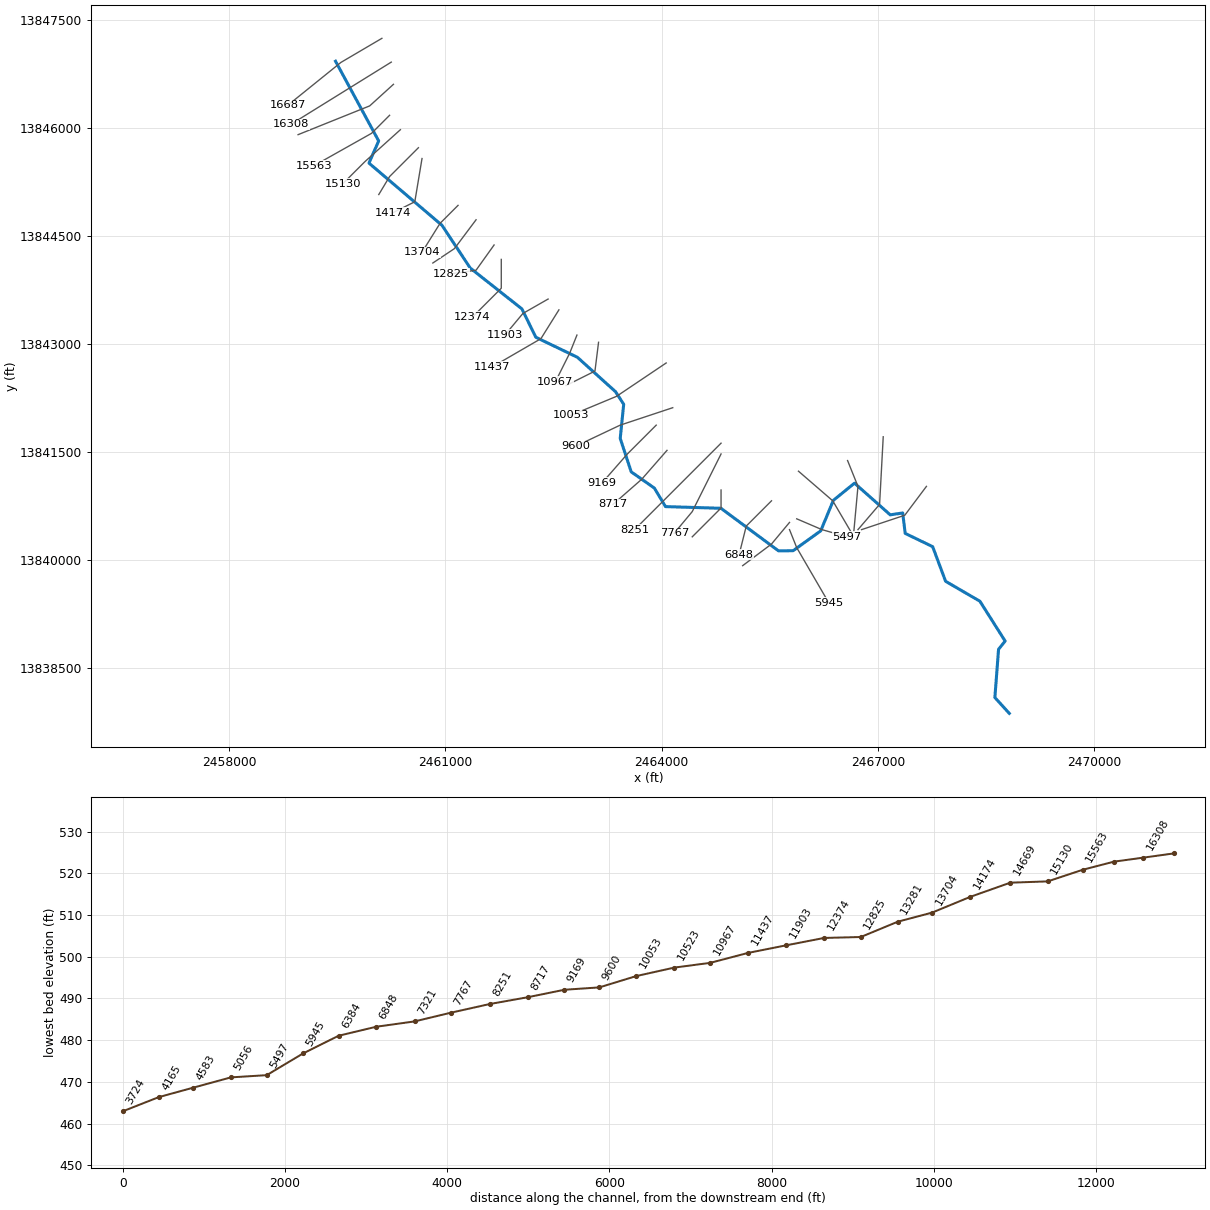
--- Stream0386.prj (project) ---

Proj Title=Stream0386 Base Level Engineering
Current Plan=p01
Default Exp/Contr=0.3,0.1
English Units
Geom File=g01
Flow File=f01
Plan File=p01
Y Axis Title=Elevation
X Axis Title(PF)=Main Channel Distance
X Axis Title(XS)=Station
BEGIN DESCRIPTION:
Stream0386
END DESCRIPTION:
DSS Export Rating Curves= 0
DSS Export Rating Curve Sorted= 0
DSS Export Volume Flow Curves= 0
DXF OffsetX= 0
DXF OffsetY= 0
DXF ScaleX= 1
DXF ScaleY= 10

--- Stream0386.p01 (plan) ---

Plan Title=Multiple Run
Short Identifier=Multiple
Geom File=g01
Flow File=f01
Subcritical Flow
K Sum by GR= 0
Std Step Tol= 0.01
Critical Tol= 0.01
Num of Std Step Trials= 20
Max Error Tol= 0.3
Flow Tol Ratio= 0.001
Split Flow NTrial= 30
Split Flow Tol= 0.02
Split Flow Ratio= 0.02
Log Output Level= 0
Friction Slope Method= 1
Unsteady Friction Slope Method= 2
Unsteady Bridges Friction Slope Method= 1
Parabolic Critical Depth
Global Vel Dist=  1 , 1 , 1
Global Log Level= 0
CheckData=True
Encroach Param= -1, 0, 0, 0
BEGIN DESCRIPTION:
Multiple Run
END DESCRIPTION:

--- Stream0386.f01 (steady flow) ---

Flow Title=Multiple
Number of Profiles=7
Profile Names=10-year,25-year,50-year,1pct_min,100-year,1pct_plu,500-year
River Rch & RM= Stream0386,Reach-1,16687
    1068    1786    2459    1640    3272    6529    5737
River Rch & RM= Stream0386,Reach-1,16308
    1281    2138    2937    1951    3893    7767    6774
River Rch & RM= Stream0386,Reach-1,9600
    1409    2356    3242    2155    4301    8581    7498
River Rch & RM= Stream0386,Reach-1,4165
    2309    3954    5529    3729    7441   14846   13357
Boundary for River Rch & Prof#=Stream0386,Reach-1,1
Up Type=0
Dn Type=3
Dn Slope=0.005
Boundary for River Rch & Prof#=Stream0386,Reach-1,2
Up Type=0
Dn Type=3
Dn Slope=0.005
Boundary for River Rch & Prof#=Stream0386,Reach-1,3
Up Type=0
Dn Type=3
Dn Slope=0.005
Boundary for River Rch & Prof#=Stream0386,Reach-1,4
Up Type=0
Dn Type=3
Dn Slope=0.005
Boundary for River Rch & Prof#=Stream0386,Reach-1,5
Up Type=0
Dn Type=3
Dn Slope=0.005
Boundary for River Rch & Prof#=Stream0386,Reach-1,6
Up Type=0
Dn Type=3
Dn Slope=0.005
Boundary for River Rch & Prof#=Stream0386,Reach-1,7
Up Type=0
Dn Type=3
Dn Slope=0.005

--- Stream0386.g01 (geometry) ---

Geom Title=Existing Conditions
Program Version=4.10

River Reach=Stream0386      ,Reach-1
Reach XY= 30
        2459475.       13846925.      2460073.42     13845818.95
      2459938.63     13845511.64      2460952.01     13844648.52
      2461344.63     13844054.53      2462061.38     13843488.21
      2462254.43     13843094.58      2462831.05     13842816.84
      2463361.37     13842338.21      2463473.95     13842164.56
      2463425.51     13841690.21      2463578.53     13841226.45
      2463898.84     13841001.92      2464054.46     13840744.47
      2464823.42     13840721.18      2465622.71     13840130.11
      2465825.08     13840132.36      2466208.36     13840408.32
      2466383.14     13840831.06      2466677.28     13841069.92
      2467172.48     13840630.31      2467345.54     13840655.95
      2467380.46     13840372.55      2467761.56     13840188.64
      2467941.26     13839707.78      2468416.99     13839431.38
       2468767.4     13838878.34      2468676.05     13838764.56
      2468624.74     13838094.95        2468825.       13837875.

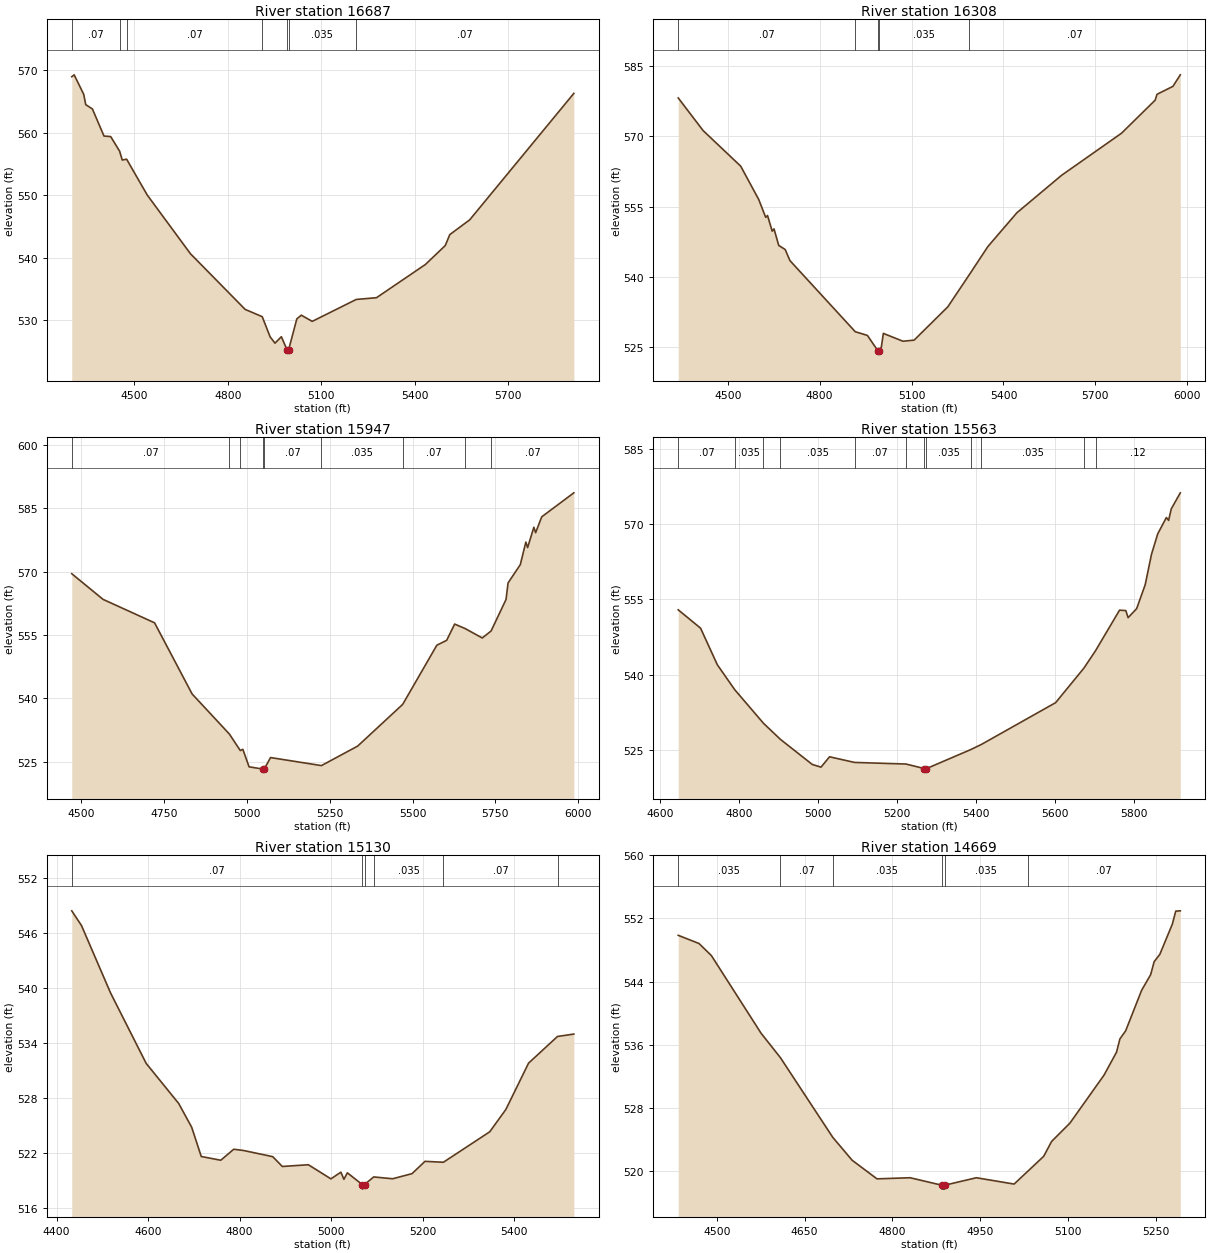
Type RM Length L Ch R = 1 ,16687   ,379,379,379
BEGIN DESCRIPTION:
Stream0386 34.0
END DESCRIPTION:
XS GIS Cut Line= 3
      2460118.17     13847242.98      2459549.56     13846908.76
      2458808.84     13846310.98
#Sta/Elev= 30
    4299   568.9  4306.7  569.21  4337.5  566.08  4343.8  564.45  4365.3  563.76
  4402.4  559.44  4423.9  559.35  4452.6  557.02    4461  555.61  4475.1  555.74
  4541.1  550.03  4679.7  540.66  4855.5  531.76  4910.3   530.6  4935.6  527.38
  4951.3  526.37  4971.7   527.4  4990.1  525.28  4990.5  524.78  4994.8  525.28
  5021.3  530.24  5035.6  530.84  5070.8  529.85  5212.1  533.35  5277.1  533.63
  5433.9  538.93  5497.8  541.96  5512.2   543.7  5576.2  546.06  5910.4  566.25
#Mann= 7 ,-1 , 0
    4299     .07       0  4452.6    .035       0  4475.1     .07       0
  4910.3    .035       0  4990.1    .035       0  4994.8    .035       0
  5212.1     .07       0
Bank Sta=4990.1,4994.8
XS Rating Curve= 0 ,0
Exp/Cntr=0.3,0.1

Type RM Length L Ch R = 1 ,16308   ,361,361,361
BEGIN DESCRIPTION:
XS6636
END DESCRIPTION:
XS GIS Cut Line= 2
      2460248.33     13846913.09      2458855.64     13846049.71
#Sta/Elev= 30
  4338.5  578.21  4419.6  571.25  4542.4  563.65  4601.3  556.53    4624  552.73
  4629.9  553.13  4645.2  549.78  4651.1  550.27  4666.5  546.74  4687.7  545.86
  4703.1   543.5  4916.2  528.33  4955.9  527.54  4990.1  524.26  4990.4  523.76
    4995  524.26  5001.3  525.03  5007.9  527.97  5071.9   526.3  5108.3  526.53
  5218.2  533.63  5287.5   540.4  5349.3  546.52  5443.8  553.71  5589.6   561.7
  5785.2  570.68  5895.1  577.74    5901  578.98    5953  580.68  5977.1  583.14
#Mann= 5 ,-1 , 0
  4338.5     .07       0  4916.2    .035       0  4990.1    .035       0
    4995    .035       0  5287.5     .07       0
Bank Sta=4990.1,4995
XS Rating Curve= 0 ,0
Exp/Cntr=0.3,0.1

Type RM Length L Ch R = 1 ,15947   ,384,384,384
BEGIN DESCRIPTION:
Stream0386 33.0
END DESCRIPTION:
XS GIS Cut Line= 3
       2460278.7     13846604.92      2459948.87     13846305.46
      2458954.97     13845906.17
#Sta/Elev= 30
  4470.7  569.53  4565.4  563.45  4720.8  557.91  4834.3  541.06  4946.6   531.6
  4979.7  527.68  4987.5  527.96  5006.3  523.82  5047.2   523.3  5047.6   522.8
  5052.1   523.3  5071.2  526.01  5224.9  524.11  5334.2  528.72  5470.3   538.6
  5573.5  552.61  5603.1  553.76  5627.3  557.61  5659.2  556.54  5710.6  554.32
  5737.3  555.97  5782.5  563.44  5788.6  567.35  5825.6  571.68  5842.3  577.02
  5847.7  575.72  5866.5  580.53  5871.9  579.25  5890.3     583  5987.3  588.68
#Mann= 9 ,-1 , 0
  4470.7     .07       0  4946.6    .035       0  4979.7     .07       0
  5047.2     .05       0  5052.1     .07       0  5224.9    .035       0
  5470.3     .07       0  5659.2     .12       0  5737.3     .07       0
Bank Sta=5047.2,5052.1
XS Rating Curve= 0 ,0
Exp/Cntr=0.3,0.1

Type RM Length L Ch R = 1 ,15563   ,433,433,433
BEGIN DESCRIPTION:
Stream0386 32.0
END DESCRIPTION:
XS GIS Cut Line= 3
        2460225.       13846175.        2459975.       13845925.
      2459175.03     13845475.02
#Sta/Elev= 30
  4646.2  552.93  4702.8  549.28  4745.2  542.01  4789.1  537.07  4862.1  530.37
  4904.9  527.18  4985.6  522.19  5007.7  521.65  5029.4  523.71  5092.6  522.59
    5223  522.27  5269.7  521.36  5270.1  520.86  5274.7  521.36  5386.3  525.12
    5414  526.17  5601.8  534.47  5673.4  541.33    5703  544.81  5763.7  552.86
  5779.6  552.78  5785.4  551.37    5807  553.16  5828.7  557.92  5844.6  563.96
  5860.3  568.01  5882.3  571.28    5888  570.71  5894.7     573  5917.6  576.19
#Mann= 12 ,-1 , 0
  4646.2     .07       0  4789.1    .035       0  4862.1     .07       0
  4904.9    .035       0  5092.6     .07       0    5223    .035       0
  5269.7    .035       0  5274.7    .035       0  5386.3     .07       0
    5414    .035       0  5673.4     .07       0    5703     .12       0
Bank Sta=5269.7,5274.7
XS Rating Curve= 0 ,0
Exp/Cntr=0.3,0.1

Type RM Length L Ch R = 1 ,15130   ,461,461,461
BEGIN DESCRIPTION:
Stream0386 31.0
END DESCRIPTION:
XS GIS Cut Line= 3
      2460375.01     13845975.01      2459883.76     13845532.89
      2459575.03     13845225.03
#Sta/Elev= 30
  4433.3  548.42  4454.6  546.81  4518.1  539.46  4595.9  531.78  4666.9  527.41
  4695.3  524.82  4716.2  521.63  4758.8  521.22  4787.2  522.42  4808.9  522.28
  4872.4  521.61  4893.3  520.54  4950.2  520.73  4999.5  519.19  5021.2  519.92
  5027.9  519.14  5035.4  519.85  5067.9  518.57  5068.3  518.07    5073  518.57
  5092.9   519.4  5134.3   519.2  5176.7  519.76    5205   521.1  5245.2     521
  5346.4  524.32  5381.7  526.76  5431.3  531.81  5494.5  534.72  5530.2  534.98
#Mann= 6 ,-1 , 0
  4433.3     .07       0  5067.9     .05       0    5073     .07       0
  5092.9    .035       0  5245.2     .07       0  5494.5    .035       0
Bank Sta=5067.9,5073
XS Rating Curve= 0 ,0
Exp/Cntr=0.3,0.1

Type RM Length L Ch R = 1 ,14669   ,495,495,495
BEGIN DESCRIPTION:
Stream0386 30.0
END DESCRIPTION:
XS GIS Cut Line= 3
      2460625.02     13845725.02        2460225.       13845325.
      2460074.98     13845074.97
#Sta/Elev= 30
  4434.3  549.87  4469.7  548.84  4490.9  547.31  4575.8  537.48  4608.8  534.39
  4698.2  524.31  4731.3  521.41  4773.7  519.06  4830.3   519.2  4884.2  518.26
  4884.6  517.76  4889.1  517.76  4889.5  518.26  4943.4   519.2  5007.8   518.4
  5031.3  520.03  5058.3  521.91  5071.9   523.8    5103   526.1  5161.3  532.18
  5182.7  535.09  5188.5  536.77  5198.3  537.79  5225.5  542.91    5241   544.9
  5246.9  546.53  5256.6  547.46    5278  551.29  5283.8  552.93  5291.6  552.97
#Mann= 6 ,-1 , 0
  4434.3    .035       0  4608.8     .07       0  4698.2    .035       0
  4884.2    .035       0  4889.5    .035       0  5031.3     .07       0
Bank Sta=4884.2,4889.5
XS Rating Curve= 0 ,0
Exp/Cntr=0.3,0.1

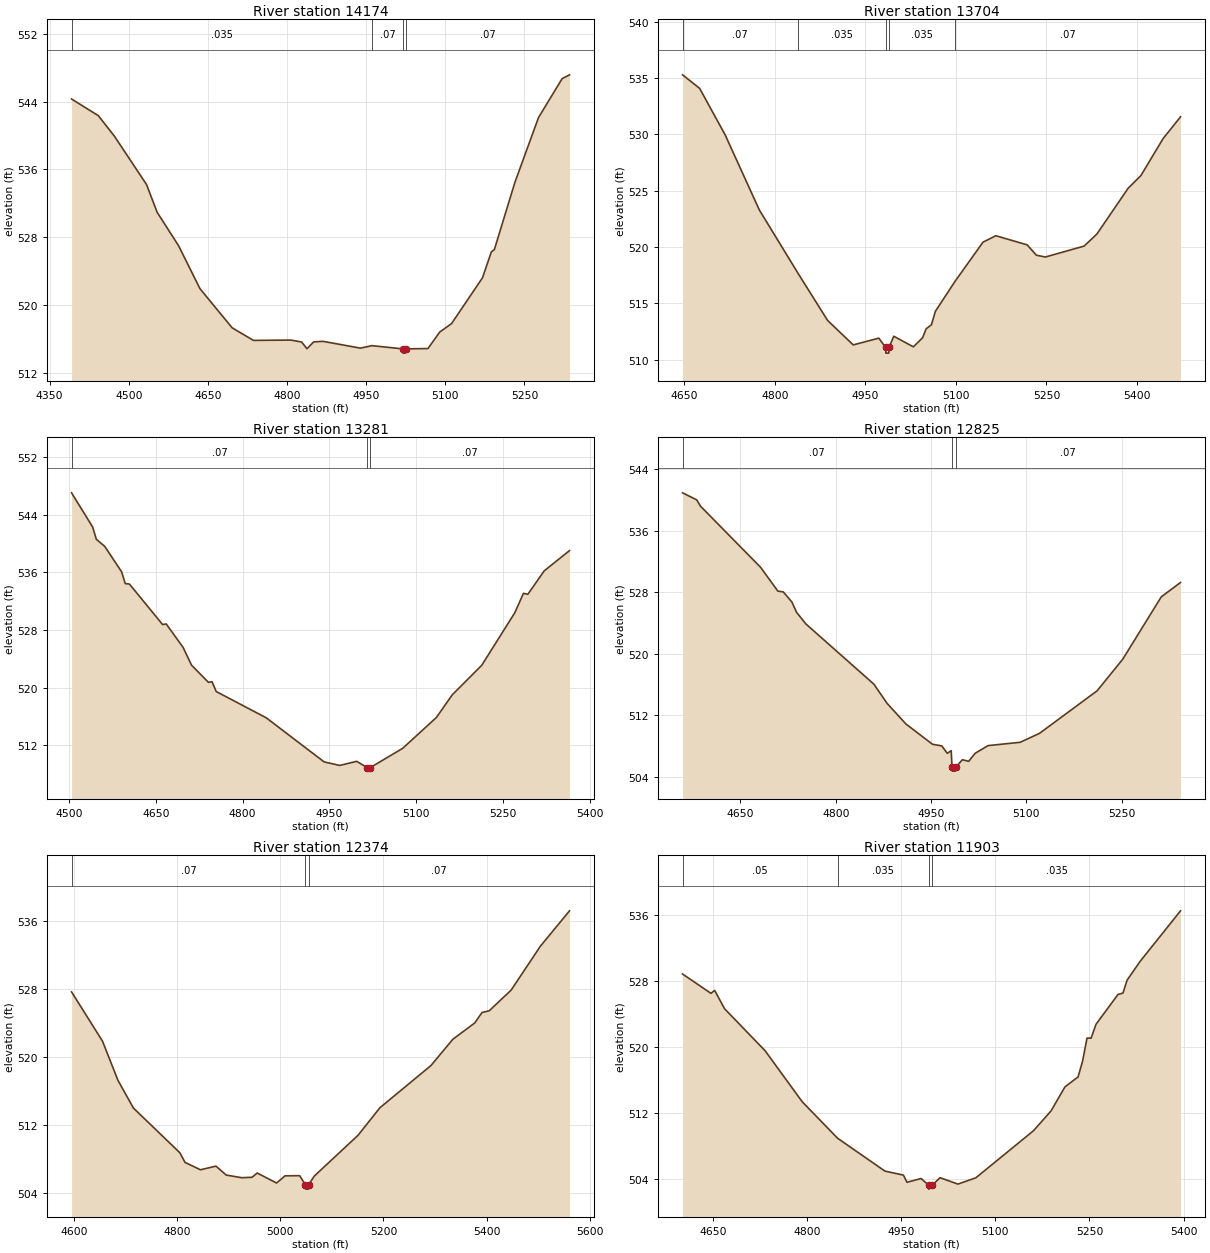
Type RM Length L Ch R = 1 ,14174   ,470,470,470
BEGIN DESCRIPTION:
Stream0386 29.0
END DESCRIPTION:
XS GIS Cut Line= 3
        2460675.     13845575.02        2460575.       13844975.
      2460275.01       13844825.
#Sta/Elev= 30
  4391.7   544.3  4442.4  542.34  4472.8  539.93  4533.7  534.23  4553.9  530.95
  4594.5  527.01    4635  521.95  4695.9  517.34  4736.4  515.85  4807.4  515.89
  4827.7  515.66  4837.8  514.87  4850.5  515.67  4868.2  515.74  4939.2  514.94
  4960.9  515.23  5019.7  514.85  5020.1  514.35  5024.6  514.35    5025  514.85
  5067.1  514.89  5089.4  516.83  5111.8  517.83  5170.5  523.23  5187.3  526.29
  5192.9  526.54    5232   534.5  5276.7  542.12  5321.4   546.7  5335.4  547.15
#Mann= 4 ,-1 , 0
  4391.7    .035       0  4960.9     .07       0  5019.7     .05       0
    5025     .07       0
Bank Sta=5019.7,5025
XS Rating Curve= 0 ,0
Exp/Cntr=0.3,0.1

Type RM Length L Ch R = 1 ,13704   ,423,423,423
BEGIN DESCRIPTION:
Stream0386 28.0
END DESCRIPTION:
XS GIS Cut Line= 3
      2461175.01     13844925.01        2460925.       13844675.
      2460674.98     13844274.97
#Sta/Elev= 30
  4646.9  535.28  4675.2  534.08  4717.6  529.94  4774.2  523.28    4838  517.69
  4887.3  513.48  4929.8  511.31  4972.2  511.91  4983.5  511.08  4983.9  510.58
  4988.7  510.58  4989.2  511.08  4996.9  512.08  5029.4  511.14  5044.7  511.94
  5050.6  512.74  5059.4   513.1  5065.9  514.29  5098.5  516.95  5144.9  520.43
  5166.1     521    5218  520.19  5233.4  519.27  5248.1  519.11  5312.4  520.08
  5333.6  521.15  5385.5  525.22  5406.7  526.35  5443.3  529.62  5472.2  531.55
#Mann= 5 ,-1 , 0
  4646.9     .07       0    4838    .035       0  4983.5    .035       0
  4989.2    .035       0  5098.5     .07       0
Bank Sta=4983.5,4989.2
XS Rating Curve= 0 ,0
Exp/Cntr=0.3,0.1

Type RM Length L Ch R = 1 ,13281   ,456,456,456
BEGIN DESCRIPTION:
Stream0386 27.0
END DESCRIPTION:
XS GIS Cut Line= 3
      2461425.03     13844725.04        2461125.       13844325.
        2460825.       13844125.
#Sta/Elev= 30
  4504.5  547.03    4541  542.28  4547.3  540.58  4561.8   539.6    4591  536.07
  4597.3  534.43  4604.5  534.37  4661.8  528.75  4668.1  528.83  4697.3  525.57
  4711.8  523.11    4741  520.73  4747.3  520.81  4754.5  519.45    4841   515.8
    4941  509.68  4968.1  509.19  4997.3  509.76  5015.2   508.9  5015.7   508.4
  5020.9   508.9  5076.7  511.56  5135.2  515.86  5162.3  518.98  5213.4  523.09
  5270.5  530.38  5285.5  533.08    5293  532.94  5321.5  536.21  5365.1  539.01
#Mann= 3 ,-1 , 0
  4504.5     .07       0  5015.2     .05       0  5020.9     .07       0
Bank Sta=5015.2,5020.9
XS Rating Curve= 0 ,0
Exp/Cntr=0.3,0.1

Type RM Length L Ch R = 1 ,12825   ,451,451,451
BEGIN DESCRIPTION:
Stream0386 26.0
END DESCRIPTION:
XS GIS Cut Line= 3
      2461675.03     13844375.04        2461425.       13844025.
      2461075.02       13843975.
#Sta/Elev= 30
  4558.9  540.95  4581.1  540.04  4587.2  539.21  4681.8  531.25  4708.9  528.16
  4717.5  528.05    4731  526.74  4738.4  525.39  4753.1  523.88    4860  516.05
  4880.9  513.54  4910.4  510.87  4952.2  508.23  4966.9  508.01  4975.5  507.05
  4981.7  507.39    4983  505.23  4983.5  504.73  4988.5  504.73    4989  505.23
  4999.2  506.21  5009.3  506.01  5019.4  507.05  5039.6  508.05  5090.1  508.48
  5120.4  509.63  5211.3  515.18  5251.7   519.3  5312.3  527.41  5342.6  529.28
#Mann= 3 ,-1 , 0
  4558.9     .07       0    4983     .05       0    4989     .07       0
Bank Sta=4983,4989
XS Rating Curve= 0 ,0
Exp/Cntr=0.3,0.1

Type RM Length L Ch R = 1 ,12374   ,471,471,471
BEGIN DESCRIPTION:
Stream0386 25.0
END DESCRIPTION:
XS GIS Cut Line= 3
        2461775.     13844174.99        2461775.       13843775.
      2461374.98     13843374.98
#Sta/Elev= 30
  4595.2  527.65  4655.2  521.87  4685.2  517.27  4715.2  514.02  4805.2  508.78
  4815.2  507.65  4845.2  506.78  4875.2  507.21  4895.2  506.16  4925.2  505.85
  4945.2   505.9  4955.2   506.4  4992.7  505.23  5009.3  506.07  5037.6  506.09
  5048.8  505.01  5049.3  504.51  5054.3  504.51  5054.8  505.01  5065.9  506.04
  5150.8  510.83  5193.2  514.06  5292.2  519.01  5334.6  522.09    5377     524
  5391.2  525.23  5405.3  525.44  5447.7  527.86  5504.3     533  5560.9  537.16
#Mann= 3 ,-1 , 0
  4595.2     .07       0  5048.8     .05       0  5054.8     .07       0
Bank Sta=5048.8,5054.8
XS Rating Curve= 0 ,0
Exp/Cntr=0.3,0.1

Type RM Length L Ch R = 1 ,11903   ,466,466,466
BEGIN DESCRIPTION:
Stream0386 24.0
END DESCRIPTION:
XS GIS Cut Line= 3
        2462425.       13843625.        2462075.       13843425.
      2461825.02     13843125.02
#Sta/Elev= 30
  4601.5  528.85  4646.8   526.5  4652.6  526.86  4668.4  524.64  4733.2  519.52
  4792.3  513.33  4848.6  508.91    4924  504.92  4953.5  504.43  4959.3  503.56
  4981.6  504.02  4993.5  503.23    4994  502.73  4999.8  503.23  5011.8  504.12
  5040.4  503.34    5069  504.11  5160.8  509.82  5188.8  512.23  5210.9  515.14
  5231.8  516.35  5238.9  518.22  5246.1  521.07  5252.6  521.06  5260.4  522.74
  5295.5  526.37  5303.4  526.53  5309.9  528.09  5330.7  530.38  5395.1  536.52
#Mann= 4 ,-1 , 0
  4601.5     .05       0  4848.6    .035       0  4993.5    .035       0
  4999.8    .035       0
Bank Sta=4993.5,4999.8
XS Rating Curve= 0 ,0
Exp/Cntr=0.3,0.1

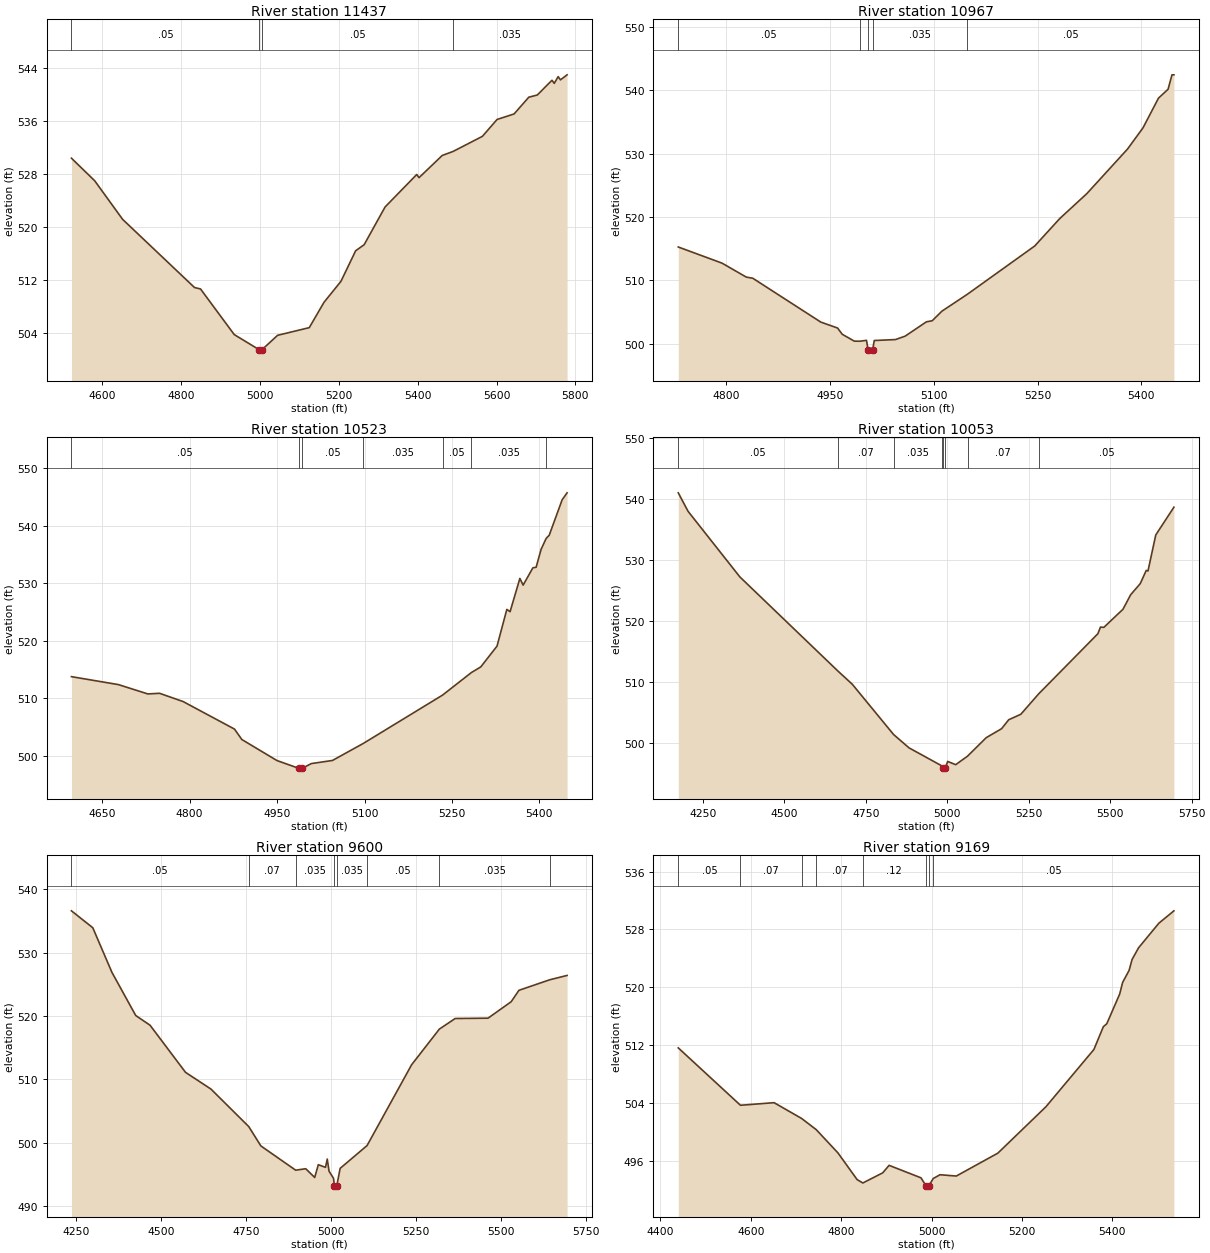
Type RM Length L Ch R = 1 ,11437   ,470,470,470
BEGIN DESCRIPTION:
Stream0386 23.0
END DESCRIPTION:
XS GIS Cut Line= 3
      2462575.02     13843475.03        2462325.       13843075.
       2461645.9     13842681.32
#Sta/Elev= 30
  4522.2  530.37  4581.2  526.96    4652  521.13  4834.2  510.84  4849.5  510.62
    4935  503.73  4998.6  501.43  4999.1  500.93    5005  501.43  5044.9  503.62
  5125.2  504.78  5162.5   508.6  5205.5  511.77  5242.8  516.39  5264.3   517.3
  5317.4     523  5397.7  527.91  5403.5  527.43  5462.3  530.78  5489.9  531.39
  5564.2  533.67  5601.4  536.22  5644.5  537.05  5681.8  539.58  5703.3  539.91
  5740.6  542.14  5746.3  541.67  5756.3  542.69  5762.1   542.2  5778.9  542.96
#Mann= 4 ,-1 , 0
  4522.2     .05       0  4998.6     .05       0    5005     .05       0
  5489.9    .035       0
Bank Sta=4998.6,5005
XS Rating Curve= 0 ,0
Exp/Cntr=0.3,0.1

Type RM Length L Ch R = 1 ,10967   ,444,444,444
BEGIN DESCRIPTION:
Stream0386 22.0
END DESCRIPTION:
XS GIS Cut Line= 3
      2462825.02     13843125.04        2462725.       13842875.
      2462525.01     13842475.01
#Sta/Elev= 30
  4730.7  515.28    4794  512.73    4829  510.53  4838.4  510.35  4936.7  503.43
    4961  502.49  4967.7  501.51  4985.2  500.42  4993.5  500.41  5002.8  500.55
  5005.1  499.03  5005.6  498.53  5011.2  498.53  5011.7  499.03    5014  500.52
  5044.7  500.67  5058.7  501.21  5089.4  503.47  5097.8  503.64  5111.8  505.15
  5148.5  507.81    5246  515.44  5282.3  519.78  5321.4  523.71  5380.1  530.73
  5402.5  534.08  5424.9  538.77  5438.8  540.18  5444.4  542.45  5447.2  542.45
#Mann= 5 ,-1 , 0
  4730.7     .05       0  4993.5    .035       0  5005.1    .035       0
  5011.7    .035       0  5148.5     .05       0
Bank Sta=5005.1,5011.7
XS Rating Curve= 0 ,0
Exp/Cntr=0.3,0.1

Type RM Length L Ch R = 1 ,10523   ,470,470,470
BEGIN DESCRIPTION:
Stream0386 21.0
END DESCRIPTION:
XS GIS Cut Line= 3
        2463125.       13843025.        2463075.       13842625.
      2462675.02     13842425.01
#Sta/Elev= 30
  4597.2  513.79  4677.8  512.41  4728.2  510.79  4748.4   510.9  4788.7  509.47
  4876.9  504.69  4889.5  502.88  4949.9  499.22  4986.9  497.89  4987.4  497.39
    4993  497.39  4993.5  497.89  5008.7   498.7    5045  499.24  5098.1  502.21
  5233.9  510.59  5283.3   514.5  5299.4  515.48  5327.3  519.09  5344.1  525.46
  5349.7  525.07  5366.5  530.84  5372.1  529.68  5388.8  532.68  5394.4  532.78
  5402.8  535.86  5411.6  537.79  5416.8  538.33  5439.1  544.51  5447.5   545.7
#Mann= 7 ,-1 , 0
  4597.2     .05       0  4986.9     .05       0  4993.5     .05       0
  5098.1    .035       0  5233.9     .05       0  5283.3    .035       0
  5411.6     .05       0
Bank Sta=4986.9,4993.5
XS Rating Curve= 0 ,0
Exp/Cntr=0.3,0.1

Type RM Length L Ch R = 1 ,10053   ,453,453,453
BEGIN DESCRIPTION:
Stream0386 20.0
END DESCRIPTION:
XS GIS Cut Line= 3
      2464063.41     13842737.73        2463375.       13842275.
      2462736.99     13842009.28
#Sta/Elev= 30
    4175  541.05    4205  538.02    4364  527.24  4664.5   511.8    4709  509.61
  4835.6  501.36    4883  499.17    4983  496.23  4987.5  495.85    4988  495.35
  4993.9  495.35  4994.4  495.85  5001.5  496.94  5026.1  496.41  5062.5  497.81
  5119.9  500.85    5167  502.32  5188.6  503.78    5226  504.69  5280.9  508.05
  5462.3  517.91  5470.3     519  5480.7  518.96  5539.2  521.92    5563  524.32
  5592.3  526.14  5610.7  528.31  5616.1  528.22  5639.9  534.13  5695.6  538.69
#Mann= 8 ,-1 , 0
    4175     .05       0  4664.5     .07       0  4835.6    .035       0
    4983     .05       0  4987.5     .05       0  4994.4     .05       0
  5062.5     .07       0  5280.9     .05       0
Bank Sta=4987.5,4994.4
XS Rating Curve= 0 ,0
Exp/Cntr=0.3,0.1

Type RM Length L Ch R = 1 ,9600    ,431,431,431
BEGIN DESCRIPTION:
Stream0386 19.0
END DESCRIPTION:
XS GIS Cut Line= 3
      2464154.57     13842117.08        2463425.       13841875.
      2462801.59     13841579.45
#Sta/Elev= 30
  4237.1  536.59  4299.9  533.92  4356.3  526.87  4426.3  520.06  4468.4  518.53
  4572.8  511.09  4647.6  508.45  4758.8  502.53  4794.6  499.47    4897  495.64
  4926.6  495.87    4953  494.49  4963.6  496.51  4984.7  496.09  4989.9   497.4
  4995.2  495.48  5008.5  494.34  5010.9  493.15  5011.4  492.65  5017.8  493.15
  5027.9  495.93  5107.1  499.53  5238.2  512.29  5319.9  517.92  5366.5  519.59
    5463  519.64  5531.2  522.24    5554  524.04    5645  525.71  5695.7  526.39
#Mann= 8 ,-1 , 0
  4237.1     .05       0  4758.8     .07       0    4897    .035       0
  5010.9    .035       0  5017.8    .035       0  5107.1     .05       0
  5319.9    .035       0    5645     .05       0
Bank Sta=5010.9,5017.8
XS Rating Curve= 0 ,0
Exp/Cntr=0.3,0.1

Type RM Length L Ch R = 1 ,9169    ,452,452,452
BEGIN DESCRIPTION:
Stream0386 18.0
END DESCRIPTION:
XS GIS Cut Line= 3
      2463924.97     13841874.97        2463525.       13841475.
      2463174.97     13841074.97
#Sta/Elev= 30
  4439.4  511.62  4577.1  503.68  4651.5  504.04  4712.6  501.85  4744.8  500.31
  4792.9  497.09  4835.3   493.4    4848  492.93  4891.9  494.33  4906.1  495.37
  4976.8  493.64  4987.3  492.58  4987.8  492.08    4994  492.08  4994.5  492.58
  5003.8  493.55  5018.8  494.07  5054.9  493.89  5146.9  497.06  5253.2  503.47
  5359.5   511.4  5380.4  514.55    5388  514.96  5416.5  519.06  5423.1  520.68
  5437.4  522.34    5444  523.85  5458.3  525.46  5503.3  528.87  5536.6  530.58
#Mann= 8 ,-1 , 0
  4439.4     .05       0  4577.1     .07       0  4712.6     .05       0
  4744.8     .07       0    4848     .12       0  4987.3     .05       0
  4994.5     .12       0  5003.8     .05       0
Bank Sta=4987.3,4994.5
XS Rating Curve= 0 ,0
Exp/Cntr=0.3,0.1

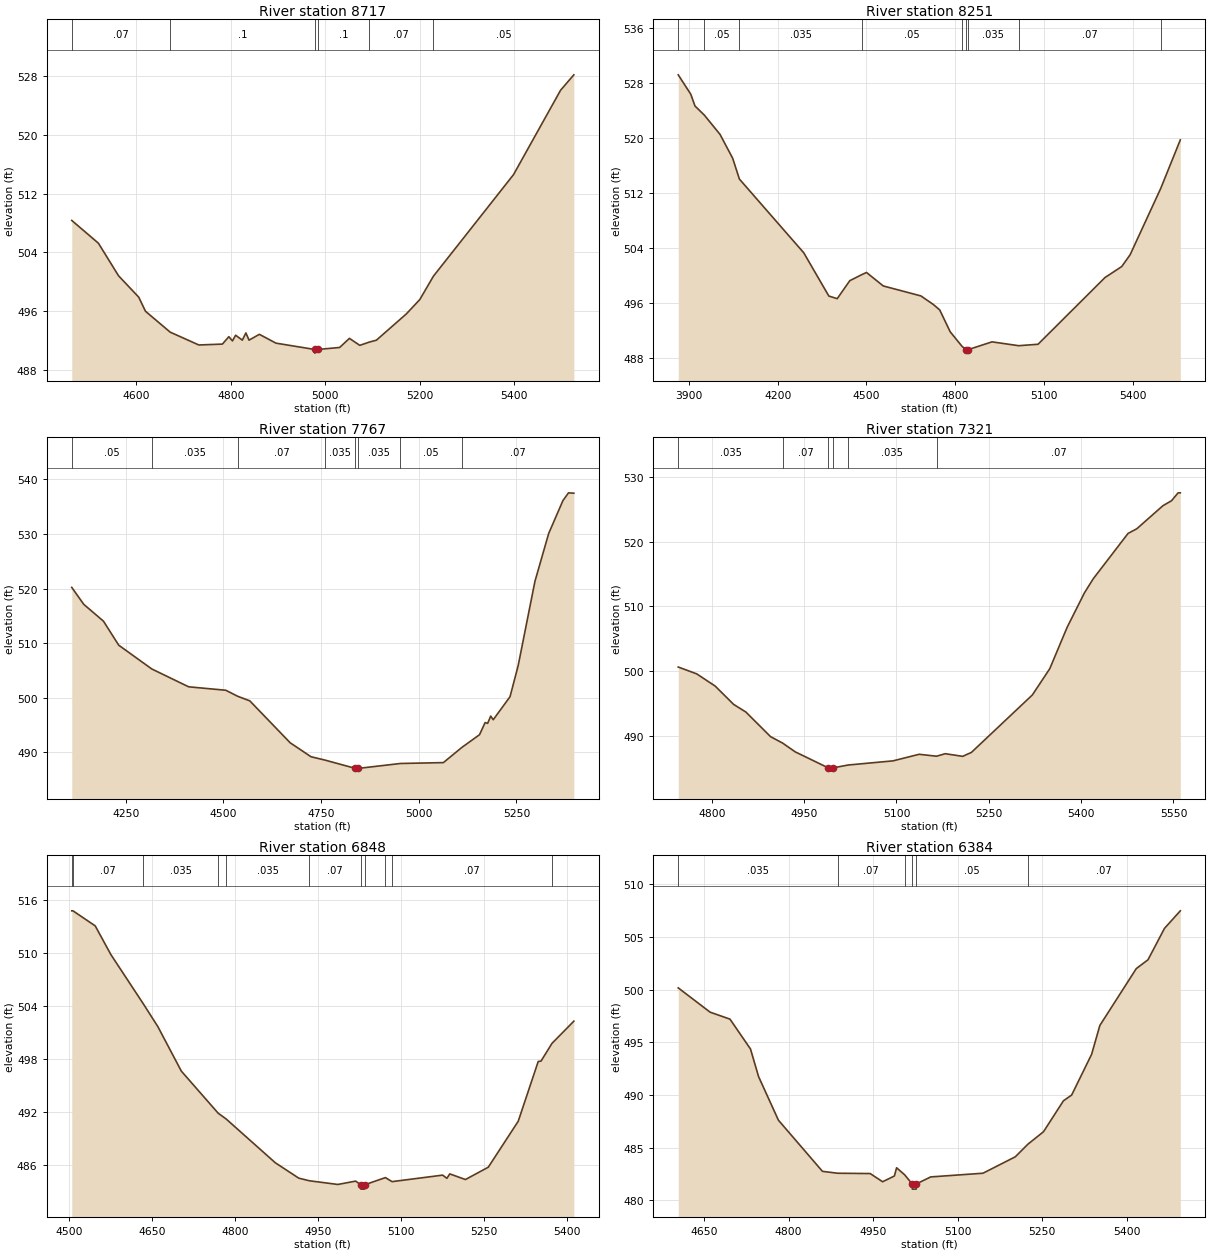
Type RM Length L Ch R = 1 ,8717    ,466,466,466
BEGIN DESCRIPTION:
Stream0386 17.0
END DESCRIPTION:
XS GIS Cut Line= 3
      2464074.97     13841524.97        2463725.       13841125.
      2463324.98     13840774.98
#Sta/Elev= 30
  4463.3  508.36  4519.7  505.26  4562.4  500.82  4605.1  497.91  4619.4  495.99
  4671.6  493.15  4732.3   491.4  4782.2  491.52  4795.9  492.53  4803.5  491.95
  4810.2  492.73  4824.4  492.06    4832  493.04  4838.6  492.06  4860.5  492.85
  4895.6  491.65  4977.4  490.79  4977.9  490.29  4984.6  490.79  5030.4  491.06
  5051.2   492.3  5073.1  491.35  5093.1  491.79  5108.2  492.05  5171.8  495.64
  5200.2  497.59  5228.9  500.76  5398.6   514.6  5498.3   526.1  5526.3  528.19
#Mann= 6 ,-1 , 0
  4463.3     .07       0  4671.6      .1       0  4977.4     .05       0
  4984.6      .1       0  5093.1     .07       0  5228.9     .05       0
Bank Sta=4977.4,4984.6
XS Rating Curve= 0 ,0
Exp/Cntr=0.3,0.1

Type RM Length L Ch R = 1 ,8251    ,484,484,484
BEGIN DESCRIPTION:
Stream0386 16.0
END DESCRIPTION:
XS GIS Cut Line= 3
      2464825.01     13841625.01        2464025.       13840825.
      2463624.98     13840424.98
#Sta/Elev= 30
  3863.9  529.14  3906.3  526.32  3920.5  524.61  3952.6  523.26  4005.3  520.47
  4047.8  517.02  4070.7  513.98  4288.2  503.26    4373  496.97  4401.3  496.59
  4443.7   499.2  4484.2  500.08  4500.3   500.4  4556.9  498.44  4684.2  496.99
  4726.6  495.73  4747.8  494.95  4783.2  491.77    4823  489.67  4836.1  489.17
  4836.6  488.67  4843.4  489.17  4924.6  490.31  5014.6  489.75  5080.1  489.96
  5306.4  499.66    5363  501.26  5391.3  502.97    5495  512.64    5561  519.68
#Mann= 9 ,-1 , 0
  3863.9     .07       0  3952.6     .05       0  4070.7    .035       0
  4484.2     .05       0    4823    .035       0  4836.1    .035       0
  4843.4    .035       0  5014.6     .07       0    5495     .05       0
Bank Sta=4836.1,4843.4
XS Rating Curve= 0 ,0
Exp/Cntr=0.3,0.1

Type RM Length L Ch R = 1 ,7767    ,446,446,446
BEGIN DESCRIPTION:
Stream0386 15.0
END DESCRIPTION:
XS GIS Cut Line= 3
        2464825.     13841474.99        2464425.       13840675.
      2464175.02     13840375.03
#Sta/Elev= 30
    4112  520.21  4142.7  517.11  4193.1  514.03  4232.2  509.63  4316.7  505.28
  4411.1  502.01  4506.1  501.38  4536.8  500.27  4567.6  499.44    4671  491.76
  4724.1  489.21    4760  488.59  4837.9  487.07  4838.4  486.57  4845.2  487.07
  4953.2  487.97    5063  488.13  5110.3  490.91  5155.5  493.24  5169.8  495.46
  5176.3  495.32  5184.1  496.64  5190.6  495.98  5233.6   500.2  5254.4  505.88
  5297.4  521.34  5332.5  530.08  5368.9   536.1  5383.3  537.53  5396.9  537.46
#Mann= 8 ,-1 , 0
    4112     .05       0  4316.7    .035       0  4536.8     .07       0
    4760    .035       0  4837.9     .05       0  4845.2    .035       0
  4953.2     .05       0  5110.3     .07       0
Bank Sta=4837.9,4845.2
XS Rating Curve= 0 ,0
Exp/Cntr=0.3,0.1

Type RM Length L Ch R = 1 ,7321    ,473,473,473
BEGIN DESCRIPTION:
Stream0386 14.0
END DESCRIPTION:
XS GIS Cut Line= 3
        2464825.       13840975.        2464825.       13840725.
      2464424.99     13840324.99
#Sta/Elev= 30
  4745.4  500.62  4775.4  499.56  4805.4  497.67  4835.4  494.83  4855.4  493.64
  4895.4  489.83  4915.1  488.83  4935.4  487.48  4989.2  484.99  4989.7  484.49
  4996.1  484.49  4996.6  484.99  5021.7  485.44  5094.4  486.08  5136.8   487.1
    5165   486.8  5179.2  487.19  5207.5  486.78  5221.7  487.39  5320.7  496.29
    5349  500.36  5377.2  506.77  5405.5  512.14  5419.7   514.3  5476.2  521.32
  5490.4  522.04  5532.8  525.61  5546.9  526.39  5557.5  527.61  5561.1  527.61
#Mann= 6 ,-1 , 0
  4745.4    .035       0  4915.1     .07       0  4989.2     .05       0
  4996.6     .07       0  5021.7    .035       0    5165     .07       0
Bank Sta=4989.2,4996.6
XS Rating Curve= 0 ,0
Exp/Cntr=0.3,0.1

Type RM Length L Ch R = 1 ,6848    ,464,464,464
BEGIN DESCRIPTION:
Stream0386 13.0
END DESCRIPTION:
XS GIS Cut Line= 3
        2465525.       13840825.        2465175.       13840475.
        2465075.     13840074.98
#Sta/Elev= 30
  4505.5  514.81  4507.7  514.81  4547.9   513.1  4576.2  509.84  4634.7  504.26
  4661.1  501.66  4703.5  496.61  4770.1  491.83  4784.2  491.19  4873.2  486.21
  4915.6  484.46  4934.8  484.16  4986.3  483.74  5018.5  484.12  5027.6  483.71
  5028.1  483.21  5034.6  483.21  5035.1  483.71  5072.3  484.52  5084.3  484.06
  5175.7   484.8  5183.4  484.44  5188.6  484.94  5216.9   484.3  5258.2   485.7
  5312.3  490.92  5348.4   497.7  5353.5  497.75  5373.3  499.76  5412.8  502.28
#Mann= 11 ,-1 , 0
  4505.5    .035       0  4507.7     .07       0  4634.7    .035       0
  4770.1     .05       0  4784.2    .035       0  4934.8     .07       0
  5027.6     .05       0  5035.1     .07       0  5072.3     .05       0
  5084.3     .07       0  5373.3     .05       0
Bank Sta=5027.6,5035.1
XS Rating Curve= 0 ,0
Exp/Cntr=0.3,0.1

Type RM Length L Ch R = 1 ,6384    ,439,439,439
BEGIN DESCRIPTION:
Stream0386 12.0
END DESCRIPTION:
XS GIS Cut Line= 3
        2465775.       13840525.        2465525.       13840225.
      2465125.01     13839925.01
#Sta/Elev= 30
  4604.2  500.17  4660.8  497.86    4696   497.2  4732.4  494.36  4746.7  491.74
  4781.9   487.6    4860  482.74  4886.8  482.56  4944.6  482.53  4966.7  481.75
  4987.6   482.3  4991.5  483.08  5005.8  482.41    5019  481.55  5019.5  481.05
  5026.2  481.05  5026.7  481.55    5052  482.21  5144.7  482.56    5202  484.12
  5224.4  485.32    5252   486.5  5287.4  489.44    5302  489.99  5337.4  493.86
    5352   496.6  5416.6     502  5437.4  502.84  5466.6  505.82  5494.7  507.49
#Mann= 6 ,-1 , 0
  4604.2    .035       0  4886.8     .07       0  5005.8     .05       0
    5019     .05       0  5026.7     .05       0  5224.4     .07       0
Bank Sta=5019,5026.7
XS Rating Curve= 0 ,0
Exp/Cntr=0.3,0.1

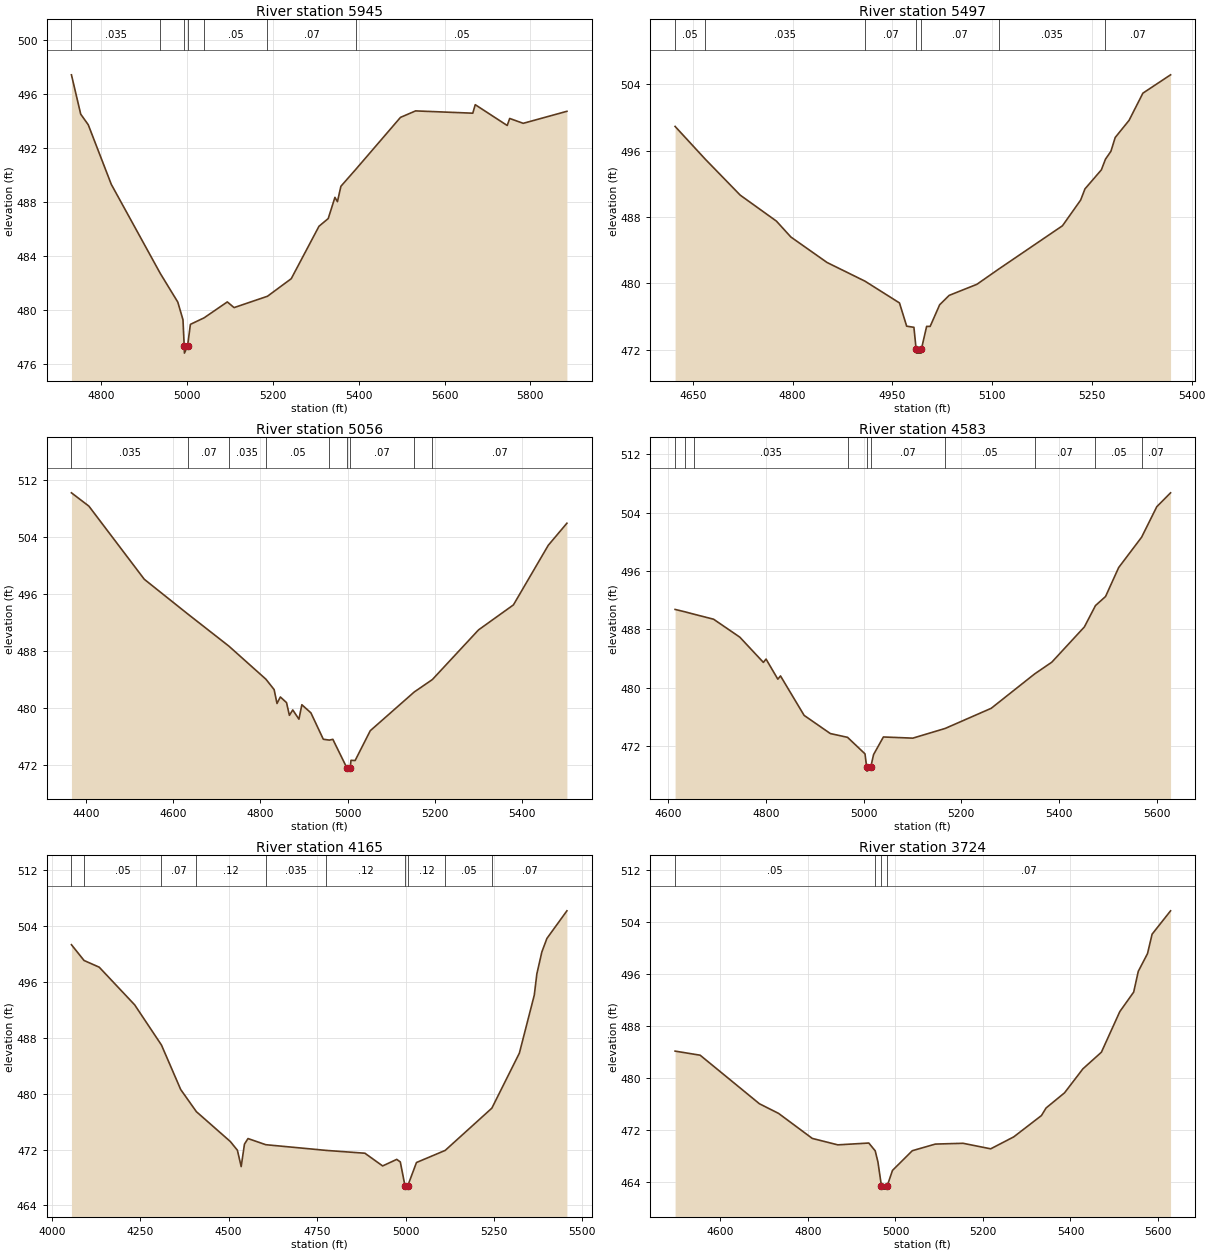
Type RM Length L Ch R = 1 ,5945    ,448,448,448
BEGIN DESCRIPTION:
Stream0386 11.0
END DESCRIPTION:
XS GIS Cut Line= 3
      2465774.98     13840425.04        2465875.       13840175.
      2466319.85      13839409.7
#Sta/Elev= 30
  4730.6   497.4  4752.2  494.49  4769.7  493.71  4823.5  489.29  4937.6   482.7
  4978.4  480.58  4990.5  479.27  4993.4   477.3  4993.9   476.8  5001.1   477.3
  5007.8  478.93  5039.6  479.41  5093.8  480.59  5109.6  480.17  5187.4  481.01
  5242.8  482.31  5307.4  486.19  5328.9  486.76  5344.6  488.33  5350.4  488.01
  5358.5  489.15  5393.9  490.43  5497.3  494.25  5532.5  494.73  5665.8  494.56
  5671.5  495.19    5746  493.65  5751.8  494.17  5783.3  493.81  5885.1   494.7
#Mann= 7 ,-1 , 0
  4730.6    .035       0  4937.6     .07       0  4993.4     .05       0
  5001.1     .07       0  5039.6     .05       0  5187.4     .07       0
  5393.9     .05       0
Bank Sta=4993.4,5001.1
XS Rating Curve= 0 ,0
Exp/Cntr=0.3,0.1

Type RM Length L Ch R = 1 ,5497    ,441,441,441
BEGIN DESCRIPTION:
Stream0386 10.0
END DESCRIPTION:
XS GIS Cut Line= 3
      2465875.01     13840574.99        2466225.       13840425.
      2466575.02     13840324.99
#Sta/Elev= 30
  4623.5  498.92  4668.9  494.97  4721.4  490.64  4775.8  487.51  4797.6  485.59
    4852  482.52    4909  480.27  4960.8  477.65  4971.6  474.85  4982.5  474.71
  4985.8   472.1  4986.3   471.6  4993.3   471.6  4993.8   472.1  5001.6  474.82
  5006.9  474.82  5021.2  477.43  5035.5  478.56  5077.1  479.89  5109.8  481.72
  5205.8  486.95  5233.1  490.04  5239.6  491.39  5264.3  493.69  5270.4  494.97
  5278.6  495.92  5285.1  497.59  5305.9  499.65  5326.7  502.93  5368.3  505.14
#Mann= 7 ,-1 , 0
  4623.5     .05       0  4668.9    .035       0    4909     .07       0
  4985.8     .05       0  4993.8     .07       0  5109.8    .035       0
  5270.4     .07       0
Bank Sta=4985.8,4993.8
XS Rating Curve= 0 ,0
Exp/Cntr=0.3,0.1

Type RM Length L Ch R = 1 ,5056    ,473,473,473
BEGIN DESCRIPTION:
Stream0386 9.0
END DESCRIPTION:
XS GIS Cut Line= 3
      2465899.37     13841236.03        2466375.       13840825.
      2466632.92     13840385.28
#Sta/Elev= 30
  4365.7  510.18  4405.8  508.31  4533.1  498.03  4633.7  493.12  4727.2  488.65
  4812.5  483.99  4831.4  482.53    4838  480.58  4845.7  481.49  4859.9   480.7
  4866.5  478.91  4874.2  479.67  4888.4  478.37  4895.1   480.4  4915.9  479.26
  4944.4  475.55  4958.2  475.43  4966.3  475.54  4998.2  471.57  4998.7  471.07
  5006.2  471.57    5008  472.59  5017.5  472.56  5052.3  476.75  5153.3  482.19
    5195  483.94  5301.1  490.92  5381.2  494.43  5461.3  502.81  5504.1  505.91
#Mann= 9 ,-1 , 0
  4365.7    .035       0  4633.7     .07       0  4727.2    .035       0
  4812.5     .05       0  4958.2     .07       0  4998.2     .05       0
  5006.2     .07       0  5153.3     .05       0    5195     .07       0
Bank Sta=4998.2,5006.2
XS Rating Curve= 0 ,0
Exp/Cntr=0.3,0.1

Type RM Length L Ch R = 1 ,4583    ,418,418,418
BEGIN DESCRIPTION:
Stream0386 8.0
END DESCRIPTION:
XS GIS Cut Line= 3
      2466580.79     13841383.63        2466725.       13841025.
      2466667.69     13840399.16
#Sta/Elev= 30
  4613.6  490.72  4633.4   490.4  4651.5  490.08  4692.4  489.38  4746.2  486.92
  4794.5  483.46  4799.9  483.92  4824.1  481.16  4829.5  481.61  4877.9   476.2
  4931.6  473.71  4966.9  473.19  5002.6  470.93  5006.2  469.06  5006.7  468.56
  5014.2  469.06  5020.2  470.83  5040.3  473.24  5100.6  473.08  5166.9  474.41
  5261.2  477.17  5349.9  481.87  5385.3  483.49    5452  488.32  5474.8  491.25
  5495.4  492.49  5522.3  496.46  5569.3  500.62  5600.4   504.8  5628.6   506.7
#Mann= 10 ,-1 , 0
  4613.6    .035       0  4633.4     .07       0  4651.5    .035       0
  4966.9     .07       0  5006.2     .05       0  5014.2     .07       0
  5166.9     .05       0  5349.9     .07       0  5474.8     .05       0
  5569.3     .07       0
Bank Sta=5006.2,5014.2
XS Rating Curve= 0 ,0
Exp/Cntr=0.3,0.1

Type RM Length L Ch R = 1 ,4165    ,441,441,441
BEGIN DESCRIPTION:
Stream0386 7.0
END DESCRIPTION:
XS GIS Cut Line= 3
       2467075.6     13841713.49        2467025.       13840775.
      2466725.02     13840425.03
#Sta/Elev= 30
  4055.5  501.32  4091.2  499.06  4134.1   498.1  4234.3  492.71  4310.1  486.95
  4364.4  480.59  4408.7  477.42  4504.6  473.15  4524.7   471.9  4535.4  469.56
  4544.7  472.77  4554.7  473.57  4604.9  472.69  4776.6  471.87  4885.2  471.47
  4935.3  469.65  4975.3  470.59  4985.3  470.22  4998.4  466.83  4998.9  466.33
  5006.5  466.83    5031  470.14  5112.1  471.87  5244.1  477.92  5321.9   485.8
  5364.1  494.11  5371.3  497.14  5385.5  500.29  5399.8  502.22  5456.3  506.17
#Mann= 10 ,-1 , 0
  4055.5    .035       0  4091.2     .05       0  4310.1     .07       0
  4408.7     .12       0  4604.9    .035       0  4776.6     .12       0
  4998.4     .05       0  5006.5     .12       0  5112.1     .05       0
  5244.1     .07       0
Bank Sta=4998.4,5006.5
XS Rating Curve= 0 ,0
Exp/Cntr=0.3,0.1

Type RM Length L Ch R = 1 ,3724    ,459,459,459
BEGIN DESCRIPTION:
Stream0386 6.0
END DESCRIPTION:
XS GIS Cut Line= 3
      2467675.03     13841025.04        2467375.       13840625.
        2466775.       13840425.
#Sta/Elev= 30
  4496.3  484.18  4553.6  483.55  4689.1  476.08  4732.8   474.6  4809.9  470.75
  4868.2  469.76  4939.1  470.04  4953.7  468.84  4959.9  467.14  4967.9  463.45
  4968.4  462.95  4980.6  462.95  4981.1  463.45  4993.2  465.83  5038.5  468.86
  5091.2  469.88  5154.5     470  5217.7  469.15  5270.4  470.99  5333.7  474.27
  5344.2  475.43  5386.4  477.76  5428.5  481.46  5470.7  484.01  5512.8  490.26
  5544.5  493.26    5555  496.45  5576.1  499.18  5586.6  502.17  5628.8  505.76
#Mann= 4 ,-1 , 0
  4496.3     .05       0  4953.7     .07       0  4967.9     .05       0
  4981.1     .07       0
Bank Sta=4967.9,4981.1
XS Rating Curve= 0 ,0
Exp/Cntr=0.3,0.1