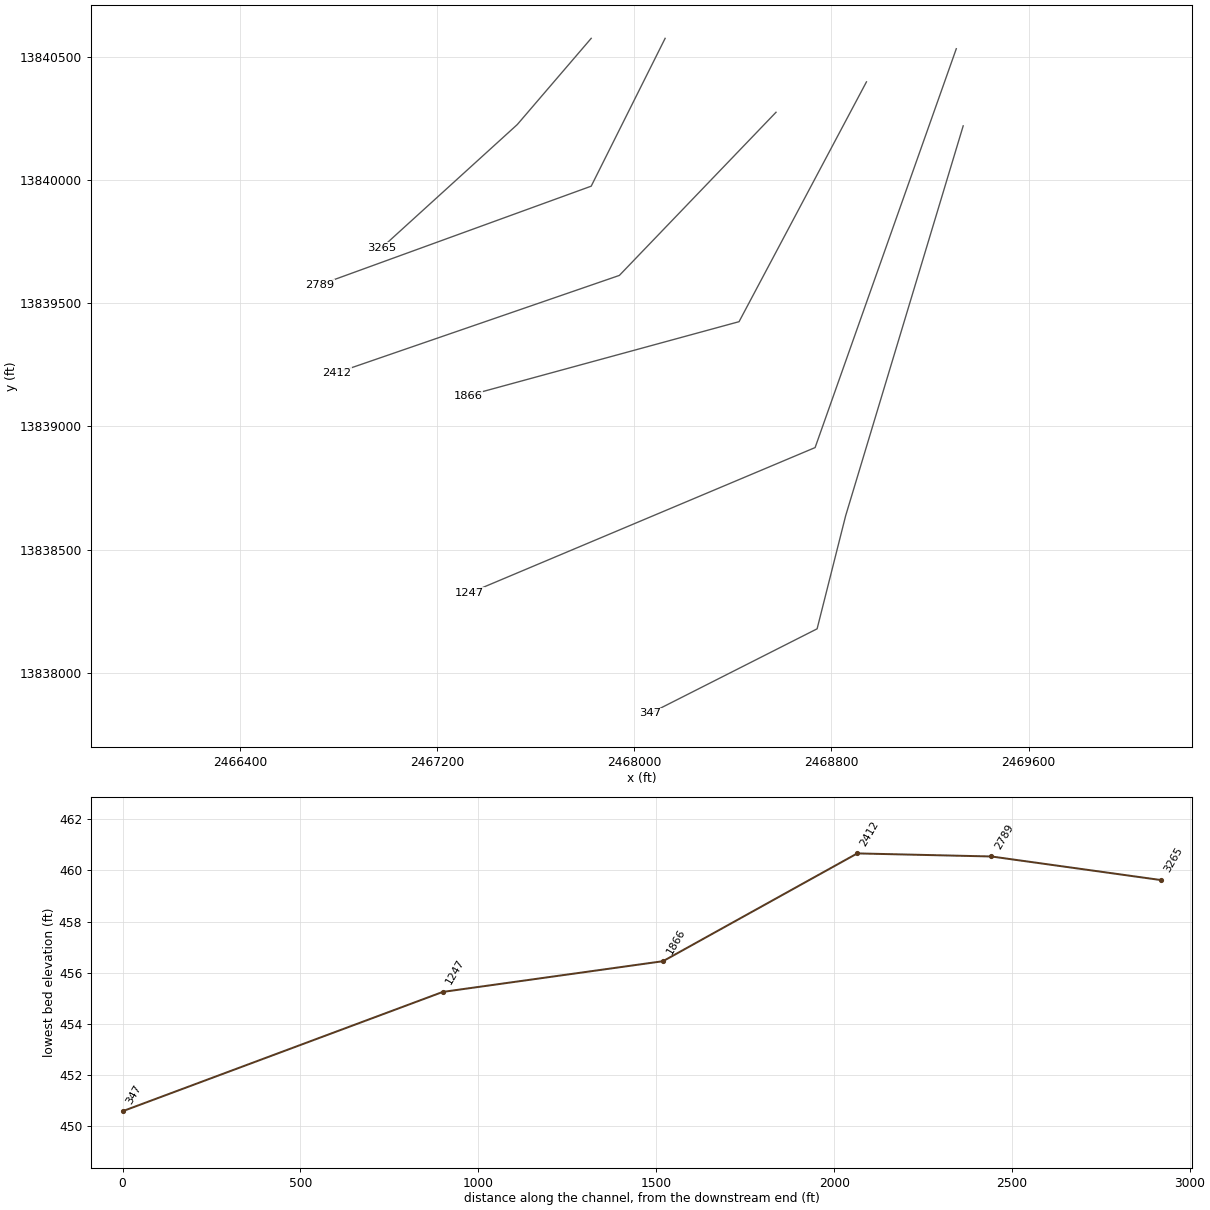
HEC-RAS study Stream0386.prj: Stream0386 Base Level Engineering

--- Stream0386.g01 (geometry) --- (continued)

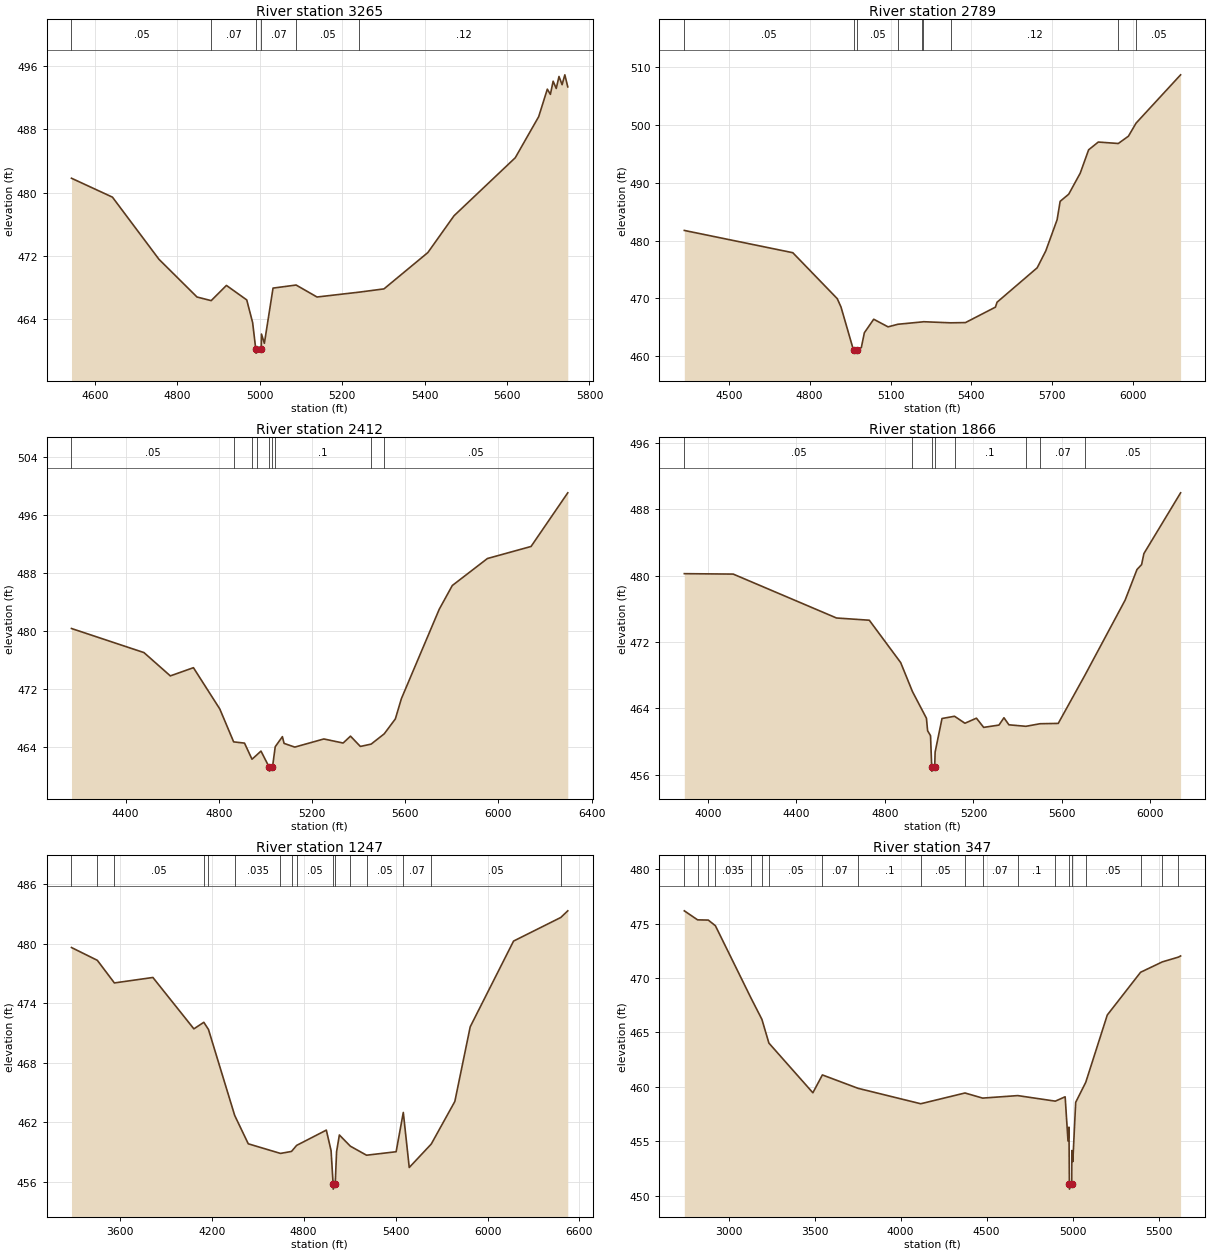
Type RM Length L Ch R = 1 ,3265    ,476,476,476
BEGIN DESCRIPTION:
Stream0386 5.0
END DESCRIPTION:
XS GIS Cut Line= 3
      2467825.03     13840575.03        2467525.       13840225.
      2466975.02     13839725.01
#Sta/Elev= 30
  4543.1  481.81  4642.5  479.41  4755.5  471.52  4847.7  466.74  4882.1  466.28
  4919.1  468.21  4968.4  466.37  4982.7  463.49  4990.3  460.12  4990.8  459.62
  5003.6  460.12  5004.1  462.04  5011.2  460.87  5032.2  467.87  5088.2  468.26
  5138.9  466.74  5241.7  467.36  5301.4  467.77  5407.9  472.38  5471.4  477.05
    5620  484.41  5676.8  489.62  5697.8  493.11  5705.2  492.45  5711.9  494.12
  5719.4   493.2  5726.1  494.72  5733.6  493.68  5740.3  494.93  5747.4   493.4
#Mann= 6 ,-1 , 0
  4543.1     .05       0  4882.1     .07       0  4990.3     .05       0
  5003.6     .07       0  5088.2     .05       0  5241.7     .12       0
Bank Sta=4990.3,5003.6
XS Rating Curve= 0 ,0
Exp/Cntr=0.3,0.1

Type RM Length L Ch R = 1 ,2789    ,377,377,377
BEGIN DESCRIPTION:
Stream0386 4.0
END DESCRIPTION:
XS GIS Cut Line= 3
      2468124.99     13840574.99        2467825.       13839975.
      2466724.98     13839574.99
#Sta/Elev= 30
    4335  481.75  4737.5   477.9  4902.4  469.96  4916.4  468.51  4962.8  461.04
  4963.3  460.54  4976.1  461.04  4991.8  461.51    5003  464.06  5037.7   466.4
  5090.9  465.08  5127.4  465.53  5218.4  465.94  5222.4  465.97  5322.6  465.78
  5378.2  465.82  5489.3  468.49  5495.3  469.34  5644.2  475.29  5676.2  478.22
  5718.1  483.59  5729.4  486.78  5761.3  488.02  5803.9  491.65  5835.1  495.69
    5871  497.03  5945.2  496.78  5982.7  498.04  6011.1   500.3  6176.3  508.65
#Mann= 9 ,-1 , 0
    4335     .05       0  4962.8     .05       0  4976.1     .05       0
  5127.4     .07       0  5218.4     .05       0  5222.4      .1       0
  5322.6     .12       0  5945.2     .07       0  6011.1     .05       0
Bank Sta=4962.8,4976.1
XS Rating Curve= 0 ,0
Exp/Cntr=0.3,0.1

Type RM Length L Ch R = 1 ,2412    ,546,546,546
BEGIN DESCRIPTION:
Stream0386 3.0
END DESCRIPTION:
XS GIS Cut Line= 3
      2468574.97     13840274.97      2467939.32     13839612.75
       2466793.5     13839217.79
#Sta/Elev= 30
    4168  480.31  4479.1  476.99  4592.3  473.78  4691.4  474.91  4804.6  469.22
    4864  464.69  4910.6  464.52  4942.7   462.3  4962.9  462.88  4981.3  463.42
  5017.2  461.16  5017.7  460.66  5030.5  461.16  5042.4  464.02  5073.2  465.41
  5080.4  464.48  5126.3  463.97  5251.1  465.09  5333.8  464.53  5365.4  465.48
  5407.8  464.06  5453.9  464.38    5510  465.79  5557.9  467.85  5583.8  470.64
  5746.3  482.96  5802.3  486.23  5953.1  489.95  6140.3  491.61  6297.9     499
#Mann= 9 ,-1 , 0
    4168     .05       0    4864     .07       0  4942.7     .05       0
  4962.9     .07       0  5017.2     .05       0  5030.5     .07       0
  5042.4      .1       0  5453.9     .07       0    5510     .05       0
Bank Sta=5017.2,5030.5
XS Rating Curve= 0 ,0
Exp/Cntr=0.3,0.1

Type RM Length L Ch R = 1 ,1866    ,619,619,619
BEGIN DESCRIPTION:
Stream0386 2.0
END DESCRIPTION:
XS GIS Cut Line= 3
      2468941.91     13840398.32        2468425.       13839425.
      2467325.04     13839125.01
#Sta/Elev= 30
  3893.8  480.24  4114.7  480.19  4581.4   474.9  4729.6  474.63  4871.3  469.53
  4924.5  466.04  4987.7  462.82    4993  461.32  5006.2  460.72  5011.6  456.95
  5012.1  456.45    5025  456.95    5027  458.75  5058.1  462.79  5114.6  463.06
  5161.7  462.22  5213.5  462.83  5246.4  461.72  5315.5     462  5337.9  462.88
  5360.4  462.03  5437.2  461.85    5501  462.16  5583.2   462.2  5703.6     468
  5885.5  477.06  5939.1  480.75  5959.8  481.33  5970.2  482.66    6136  489.98
#Mann= 8 ,-1 , 0
  3893.8     .05       0  4924.5     .07       0  5011.6     .05       0
    5025     .07       0  5114.6      .1       0  5437.2     .05       0
    5501     .07       0  5703.6     .05       0
Bank Sta=5011.6,5025
XS Rating Curve= 0 ,0
Exp/Cntr=0.3,0.1

Type RM Length L Ch R = 1 ,1247    ,900,900,900
BEGIN DESCRIPTION:
Stream0386 1.0
END DESCRIPTION:
XS GIS Cut Line= 3
       2469306.5     13840532.88      2468733.59     13838913.97
      2467331.68     13838323.69
#Sta/Elev= 30
  3285.2  479.61  3453.9  478.32  3565.2  476.04  3816.4  476.59  4083.9  471.41
  4148.7  472.07  4179.1  471.35  4350.2  462.68  4438.8  459.82    4649  458.85
  4720.9  459.05  4754.4  459.66  4948.2   461.2  4979.1  459.13  4992.6  455.75
  4993.1  455.25    5006  455.75    5015  459.02  5033.3  460.71  5104.9  459.58
  5210.5  458.67  5403.6  459.02  5450.4  462.98  5489.2  457.43    5633   459.8
  5786.7  464.09  5887.1  471.62  6169.9  480.26    6478  482.64  6523.6  483.31
#Mann= 16 ,-1 , 0
  3285.2     .05       0  3453.9    .035       0  3565.2     .05       0
  4148.7    .035       0  4179.1     .05       0  4350.2    .035       0
    4649     .05       0  4720.9    .035       0  4754.4     .05       0
  4992.6     .05       0    5006     .05       0  5104.9    .035       0
  5210.5     .05       0  5450.4     .07       0    5633     .05       0
    6478    .035       0
Bank Sta=4992.6,5006
XS Rating Curve= 0 ,0
Exp/Cntr=0.3,0.1

Type RM Length L Ch R = 1 ,347     ,0,0,0
BEGIN DESCRIPTION:
E20949
END DESCRIPTION:
XS GIS Cut Line= 4
      2469334.49     13840219.76      2468857.56     13838637.43
      2468741.68     13838178.34      2468064.18     13837835.14
#Sta/Elev= 30
  2742.1  476.18  2819.3  475.35  2881.4  475.33  2922.9  474.81  3130.2  468.15
  3193.3   466.2  3233.9  464.02  3489.6  459.45  3544.9  461.09  3752.2  459.86
  4116.7  458.44  4374.1  459.43  4476.6  458.96    4681  459.19  4899.3  458.68
  4956.4  459.08  4973.1  455.01  4978.7  456.29    4981  451.09  4981.5  450.59
  4994.6  451.09  4995.4  454.14    5001  453.12  5017.7  458.57  5076.2  460.41
  5201.4   466.6    5395  470.53  5522.1  471.49  5614.2  471.92  5627.7  472.03
#Mann= 20 ,-1 , 0
  2742.1     .05       0  2819.3    .035       0  2881.4     .05       0
  2922.9    .035       0  3130.2     .05       0  3193.3    .035       0
  3233.9     .05       0  3544.9     .07       0  3752.2      .1       0
  4116.7     .05       0  4374.1     .07       0  4476.6     .07       0
    4681      .1       0  4899.3     .07       0    4981     .05       0
  4994.6     .07       0  5076.2     .05       0    5395    .035       0
  5522.1     .07       0  5614.2     .12       0
Bank Sta=4981,4994.6
XS Rating Curve= 0 ,0
Exp/Cntr=0.3,0.1

Chan Stop Cuts=-1
Use User Specified Reach Order=0
Composite Channel Slope=5