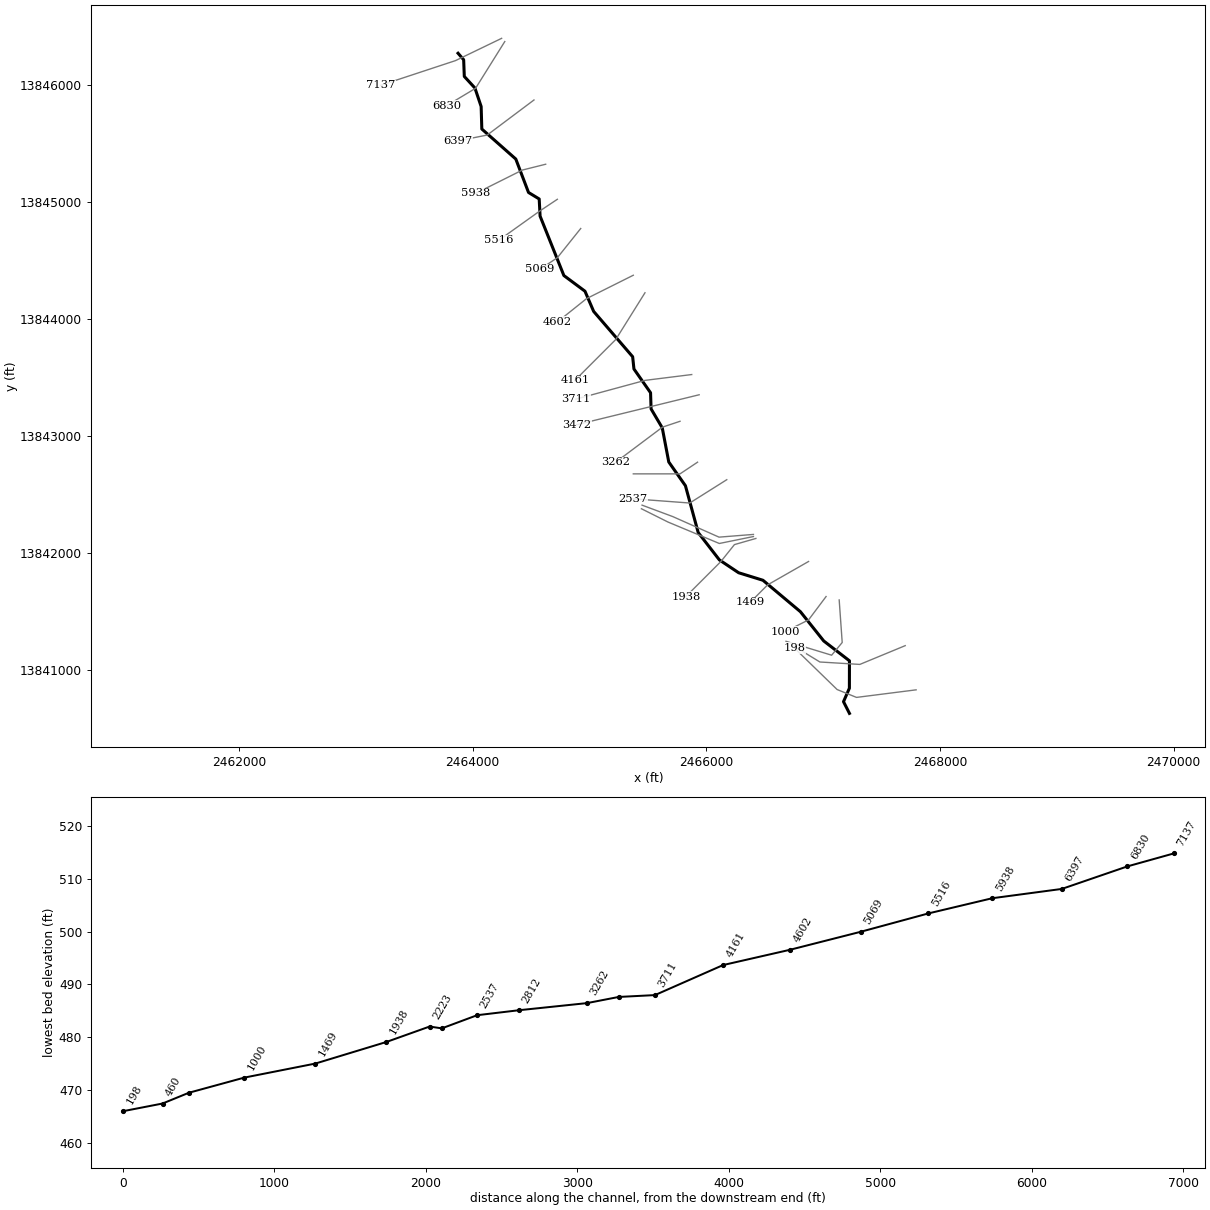
--- Stream0387.prj (project) ---

Proj Title=Stream0387 Base Level Engineering
Current Plan=p01
Default Exp/Contr=0.3,0.1
English Units
Geom File=g01
Flow File=f01
Plan File=p01
BEGIN DESCRIPTION:
Stream0387
END DESCRIPTION:

--- Stream0387.p01 (plan) ---

Plan Title=Multiple Run
Short Identifier=Multiple
Geom File=g01
Flow File=f01
Subcritical Flow
K Sum by GR= 0
Std Step Tol= 0.01
Critical Tol= 0.01
Num of Std Step Trials= 20
Max Error Tol= 0.3
Flow Tol Ratio= 0.001
Split Flow NTrial= 30
Split Flow Tol= 0.02
Split Flow Ratio= 0.02
Log Output Level= 0
Friction Slope Method= 1
Unsteady Friction Slope Method= 2
Unsteady Bridges Friction Slope Method= 1
Parabolic Critical Depth
Global Vel Dist=  1 , 1 , 1
Global Log Level= 0
CheckData=True
Encroach Param= -1, 0, 0, 0
BEGIN DESCRIPTION:
Multiple Run
END DESCRIPTION:

--- Stream0387.f01 (steady flow) ---

Flow Title=Multiple
Number of Profiles=7
Profile Names=10-year,25-year,50-year,1pct_min,100-year,1pct_plu,500-year
River Rch & RM= Stream0387,Reach-1,7137
     912    1497    2033    1337    2668    5323    4547
River Rch & RM= Stream0387,Reach-1,460
    1381    2318    3200    2134    4259    8497    7476
Boundary for River Rch & Prof#=Stream0387,Reach-1,1
Up Type=0
Dn Type=3
Dn Slope=0.005
Boundary for River Rch & Prof#=Stream0387,Reach-1,2
Up Type=0
Dn Type=3
Dn Slope=0.005
Boundary for River Rch & Prof#=Stream0387,Reach-1,3
Up Type=0
Dn Type=3
Dn Slope=0.005
Boundary for River Rch & Prof#=Stream0387,Reach-1,4
Up Type=0
Dn Type=3
Dn Slope=0.005
Boundary for River Rch & Prof#=Stream0387,Reach-1,5
Up Type=0
Dn Type=3
Dn Slope=0.005
Boundary for River Rch & Prof#=Stream0387,Reach-1,6
Up Type=0
Dn Type=3
Dn Slope=0.005
Boundary for River Rch & Prof#=Stream0387,Reach-1,7
Up Type=0
Dn Type=3
Dn Slope=0.005

--- Stream0387.g01 (geometry) ---

Geom Title=Existing Conditions

River Reach=Stream0387,Reach-1
Reach XY= 30
      2463875.00     13846275.00      2463923.09     13846219.21
      2463928.55     13846076.47      2464019.46     13845977.42
      2464072.74     13845819.06      2464078.53     13845626.45
      2464369.38     13845369.38      2464478.19     13845083.35
      2464569.60     13845027.68      2464577.27     13844880.94
      2464780.73     13844372.45      2464961.39     13844238.24
      2465035.76     13844065.32      2465369.48     13843677.43
      2465380.54     13843572.58      2465522.75     13843369.07
      2465527.25     13843230.93      2465622.75     13843069.07
      2465678.62     13842776.50      2465821.17     13842573.42
      2465930.54     13842172.58      2466111.76     13841938.62
      2466276.50     13841828.62      2466484.68     13841764.24
      2466805.16     13841495.39      2467004.87     13841244.77
      2467225.00     13841075.00      2467224.48     13840840.21
      2467174.18     13840725.04      2467225.00     13840625.00

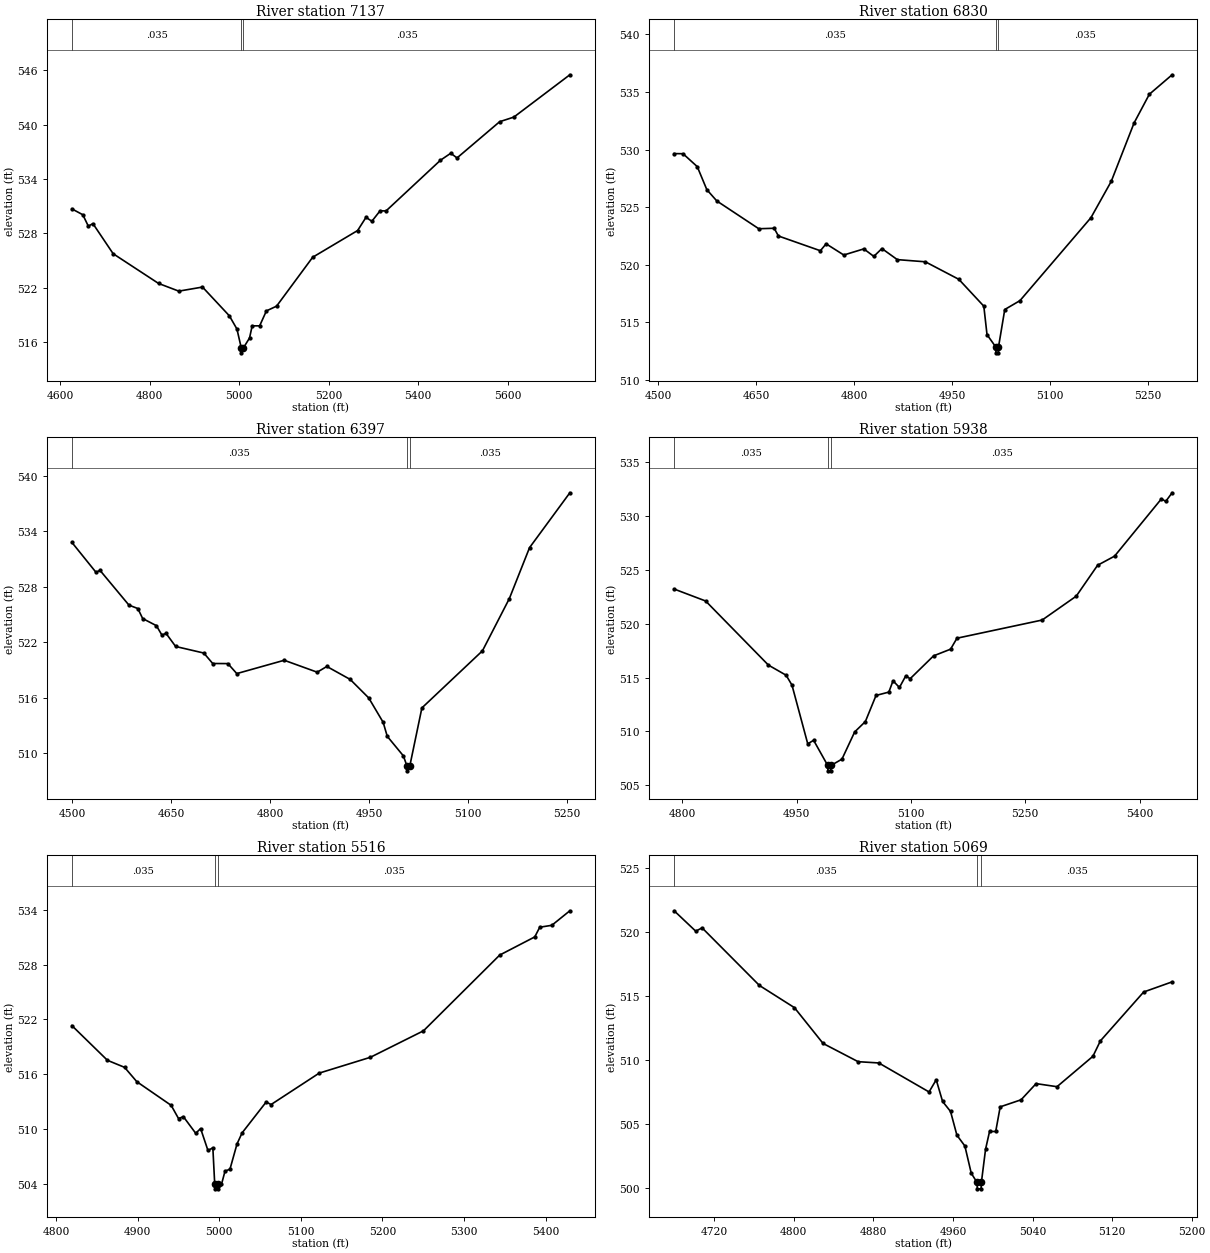
Type RM Length L Ch R = 1,7137,307,307,307
BEGIN DESCRIPTION:
XS6637
END DESCRIPTION:
XS GIS Cut Line= 3
      2464248.09     13846402.57      2463852.78     13846211.73
      2463212.09     13846000.44
#Sta/Elev= 30
  4625.6  530.71  4650.1  530.06  4662.3  528.81  4672.7  529.08  4717.9  525.76
  4819.4  522.48  4864.7  521.63  4917.7  522.08  4977.7  518.91  4994.7  517.45
  5004.6  515.32  5004.8  514.82  5008.6  515.32  5022.9  516.46  5028.8  517.80
  5045.5  517.80  5060.6  519.45  5083.3  519.97  5164.1  525.37  5264.6  528.32
  5283.4  529.78  5296.4  529.34  5314.9  530.50  5328.1  530.48  5449.9  536.08
  5472.9  536.85  5486.9  536.33  5582.2  540.33  5614.0  540.84  5739.2  545.51
#Mann=3,-1,0
  4625.6   0.035       0  5004.6   0.035       0  5008.6   0.035       0
Bank Sta=5004.6,5008.6
Exp/Cntr=0.3,0.1

Type RM Length L Ch R = 1,6830,433,433,433
BEGIN DESCRIPTION:
Stream0387 14.0
END DESCRIPTION:
XS GIS Cut Line= 3
      2464275.00     13846374.99      2464025.00     13845975.00
      2463775.03     13845825.02
#Sta/Elev= 30
  4524.3  529.65  4537.9  529.64  4559.7  528.52  4574.4  526.52  4589.7  525.54
  4654.0  523.13  4677.6  523.17  4684.1  522.50  4748.4  521.22  4757.2  521.82
  4784.3  520.85  4815.0  521.38  4830.3  520.73  4842.7  521.41  4866.3  520.45
  4909.3  520.26  4960.6  518.74  4998.9  516.41  5003.8  513.94  5017.3  512.86
  5017.5  512.36  5021.1  512.36  5021.4  512.86  5031.0  516.12  5054.3  516.89
  5163.1  524.09  5194.2  527.24  5229.2  532.31  5252.6  534.80  5287.5  536.49
#Mann=3,-1,0
  4524.3   0.035       0  5017.3   0.035       0  5021.4   0.035       0
Bank Sta=5017.3,5021.4
Exp/Cntr=0.3,0.1

Type RM Length L Ch R = 1,6397,459,459,459
BEGIN DESCRIPTION:
Stream0387 13.0
END DESCRIPTION:
XS GIS Cut Line= 3
      2464524.99     13845875.00      2464125.00     13845575.00
      2463875.04     13845525.01
#Sta/Elev= 30
  4499.4  532.78  4535.9  529.55  4542.1  529.75  4585.9  526.00  4599.4  525.63
  4606.7  524.55  4627.5  523.78  4635.9  522.76  4642.1  522.95  4656.7  521.53
  4699.4  520.82  4712.9  519.69  4735.9  519.68  4749.4  518.60  4821.3  520.04
  4871.3  518.75  4885.9  519.37  4921.3  517.97  4949.4  515.97  4971.3  513.33
  4977.5  511.82  5001.9  509.71  5007.5  508.59  5007.8  508.09  5011.6  508.59
  5030.0  514.89  5121.8  521.06  5162.6  526.71  5193.2  532.21  5254.3  538.14
#Mann=3,-1,0
  4499.4   0.035       0  5007.5   0.035       0  5011.6   0.035       0
Bank Sta=5007.5,5011.6
Exp/Cntr=0.3,0.1

Type RM Length L Ch R = 1,5938,422,422,422
BEGIN DESCRIPTION:
Stream0387 12.0
END DESCRIPTION:
XS GIS Cut Line= 3
      2464625.03     13845325.01      2464425.00     13845275.00
      2464025.00     13845075.00
#Sta/Elev= 30
  4789.3  523.23  4830.6  522.12  4913.0  516.16  4936.2  515.22  4943.9  514.30
  4964.6  508.84  4972.3  509.17  4990.8  506.83  4991.1  506.33  4994.8  506.33
  4995.1  506.83  5009.5  507.42  5026.2  509.95  5040.2  510.91  5054.2  513.34
  5071.0  513.65  5076.5  514.70  5084.9  514.08  5093.3  515.17  5098.9  514.89
  5129.7  517.02  5152.0  517.64  5160.4  518.66  5272.2  520.35  5316.9  522.57
  5344.9  525.44  5367.2  526.29  5428.7  531.62  5434.3  531.38  5442.7  532.18
#Mann=3,-1,0
  4789.3   0.035       0  4990.8   0.035       0  4995.1   0.035       0
Bank Sta=4990.8,4995.1
Exp/Cntr=0.3,0.1

Type RM Length L Ch R = 1,5516,447,447,447
BEGIN DESCRIPTION:
Stream0387 11.0
END DESCRIPTION:
XS GIS Cut Line= 3
      2464725.01     13845025.01      2464575.00     13844925.00
      2464225.01     13844675.01
#Sta/Elev= 30
  4819.3  521.32  4862.9  517.52  4883.9  516.75  4898.9  515.18  4941.0  512.59
  4950.0  511.15  4956.0  511.35  4971.1  509.53  4977.1  510.05  4986.1  507.65
  4992.1  507.94  4994.4  503.95  4994.7  503.45  4998.5  503.45  4998.8  503.95
  5002.7  503.95  5007.0  505.38  5013.1  505.61  5021.7  508.36  5027.9  509.57
  5057.4  512.95  5063.5  512.68  5122.5  516.12  5185.2  517.85  5250.3  520.75
  5343.7  529.04  5386.7  531.03  5392.8  532.09  5407.6  532.30  5429.7  533.89
#Mann=3,-1,0
  4819.3   0.035       0  4994.4   0.035       0  4998.8   0.035       0
Bank Sta=4994.4,4998.8
Exp/Cntr=0.3,0.1

Type RM Length L Ch R = 1,5069,467,467,467
BEGIN DESCRIPTION:
Stream0387 10.0
END DESCRIPTION:
XS GIS Cut Line= 3
      2464925.03     13844775.03      2464725.00     13844525.00
      2464574.98     13844424.99
#Sta/Elev= 30
  4679.8  521.64  4701.5  520.05  4707.9  520.31  4765.5  515.82  4800.7  514.09
  4829.5  511.30  4864.7  509.88  4885.5  509.78  4936.0  507.52  4943.2  508.47
  4949.6  506.78  4957.6  506.00  4964.0  504.15  4972.0  503.31  4978.4  501.19
  4984.2  500.47  4984.5  499.97  4988.3  499.97  4988.6  500.47  4992.8  503.06
  4996.8  504.44  5003.0  504.44  5007.5  506.36  5028.5  506.91  5043.6  508.17
  5064.6  507.93  5100.7  510.30  5108.2  511.50  5151.7  515.31  5180.3  516.10
#Mann=3,-1,0
  4679.8   0.035       0  4984.2   0.035       0  4988.6   0.035       0
Bank Sta=4984.2,4988.6
Exp/Cntr=0.3,0.1

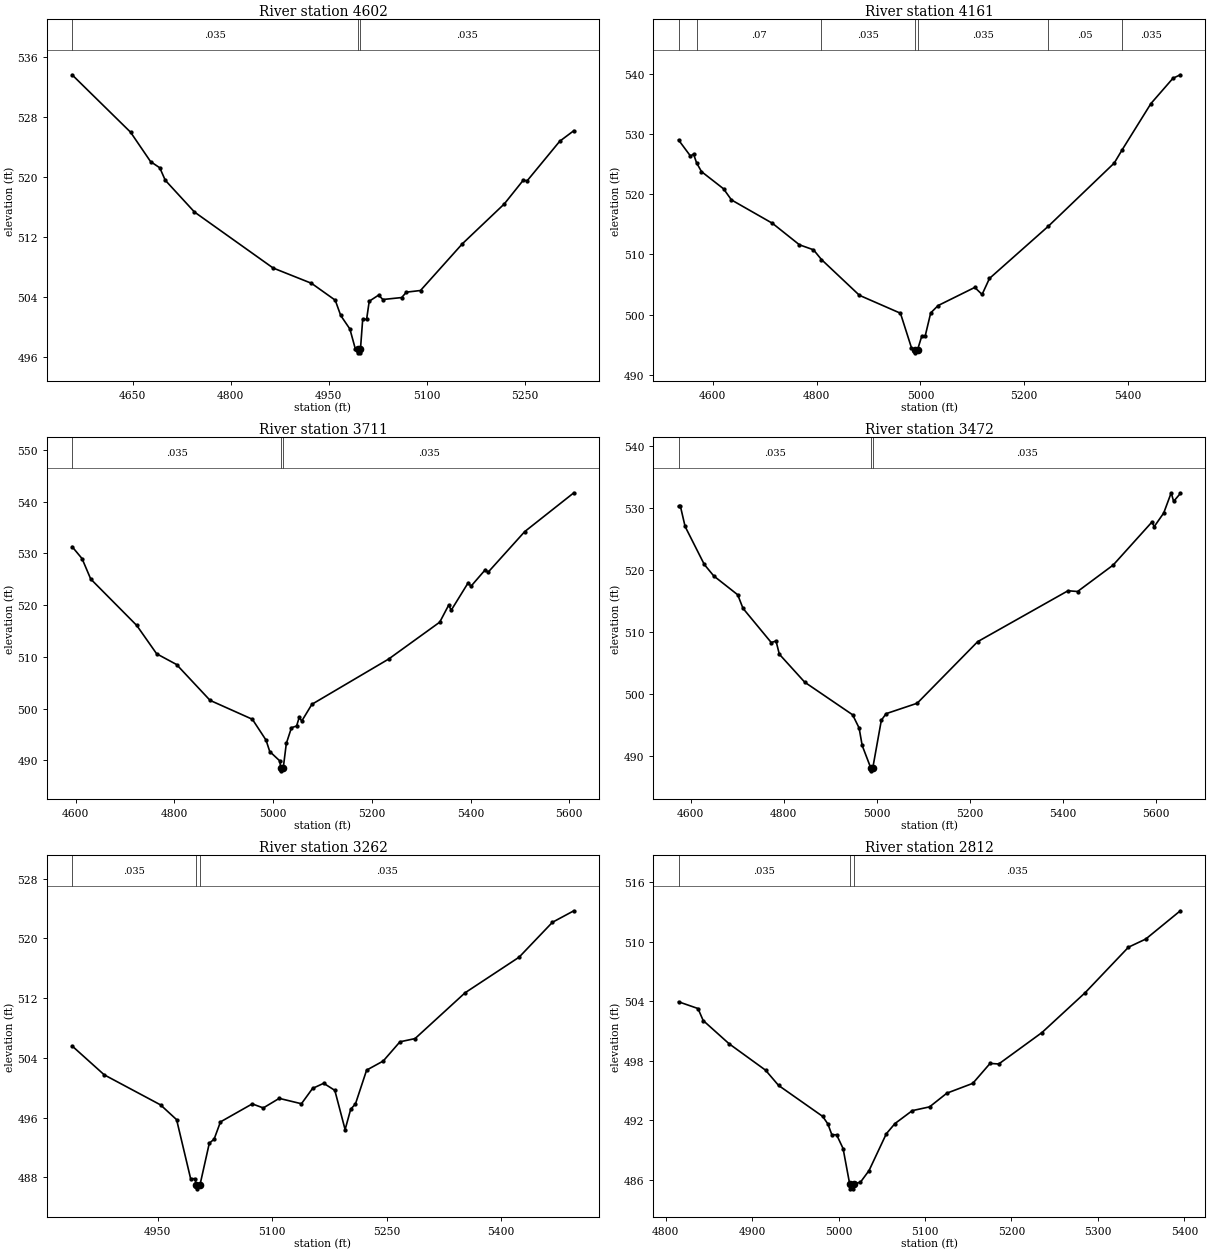
Type RM Length L Ch R = 1,4602,441,441,441
BEGIN DESCRIPTION:
Stream0387 9.0
END DESCRIPTION:
XS GIS Cut Line= 3
      2465374.96     13844374.98      2464975.00     13844175.00
      2464725.02     13843975.02
#Sta/Elev= 30
  4557.4  533.63  4646.8  525.98  4677.5  522.05  4691.5  521.23  4699.9  519.57
  4744.6  515.33  4864.8  507.87  4923.5  505.83  4959.8  503.58  4968.2  501.54
  4982.2  499.74  4990.6  497.07  4993.9  497.06  4994.2  496.56  4998.1  496.56
  4998.4  497.06  5001.8  501.03  5007.8  501.03  5011.8  503.44  5026.2  504.26
  5032.6  503.67  5061.4  503.93  5068.6  504.65  5090.2  504.87  5154.2  511.10
  5218.3  516.41  5247.1  519.55  5253.5  519.52  5303.1  524.77  5324.7  526.18
#Mann=3,-1,0
  4557.4   0.035       0  4993.9   0.035       0  4998.4   0.035       0
Bank Sta=4993.9,4998.4
Exp/Cntr=0.3,0.1

Type RM Length L Ch R = 1,4161,450,450,450
BEGIN DESCRIPTION:
Stream0387 8.0
END DESCRIPTION:
XS GIS Cut Line= 3
      2465475.00     13844224.99      2465225.00     13843825.00
      2464874.98     13843474.98
#Sta/Elev= 30
  4533.9  528.98  4556.9  526.31  4562.8  526.64  4568.6  525.20  4578.1  523.73
  4620.6  520.88  4635.9  519.03  4714.9  515.15  4766.8  511.59  4793.9  510.76
  4809.2  509.15  4882.4  503.21  4961.4  500.24  4982.6  494.52  4989.8  494.17
  4990.1  493.67  4994.3  494.17  5002.6  496.47  5009.1  496.47  5019.7  500.29
  5033.9  501.51  5104.6  504.52  5118.7  503.35  5132.9  506.01  5246.2  514.66
  5373.3  525.15  5388.2  527.30  5444.0  535.02  5486.4  539.21  5500.6  539.79
#Mann=7,-1,0
  4533.9   0.035       0  4568.6    0.07       0  4809.2   0.035       0
  4989.8   0.035       0  4994.3   0.035       0  5246.2    0.05       0
  5388.2   0.035       0
Bank Sta=4989.8,4994.3
Exp/Cntr=0.3,0.1

Type RM Length L Ch R = 1,3711,239,239,239
BEGIN DESCRIPTION:
Stream0387 7.0
END DESCRIPTION:
XS GIS Cut Line= 3
      2465875.04     13843525.00      2465475.00     13843475.00
      2464882.68     13843314.23
#Sta/Elev= 30
  4592.5  531.29  4612.7  528.98  4630.3  525.03  4723.6  516.06  4763.9  510.59
  4804.2  508.52  4872.2  501.59  4957.9  497.94  4985.6  493.91  4993.1  491.71
  5013.0  489.94  5015.8  488.48  5016.1  487.98  5020.4  488.48  5026.7  493.27
  5037.1  496.31  5047.5  496.64  5052.8  498.30  5058.0  497.60  5078.5  500.83
  5234.0  509.57  5337.6  516.70  5355.7  519.99  5360.9  519.01  5395.5  524.35
  5400.7  523.61  5430.2  526.86  5435.3  526.31  5509.8  534.19  5609.4  541.69
#Mann=3,-1,0
  4592.5   0.035       0  5015.8   0.035       0  5020.4   0.035       0
Bank Sta=5015.8,5020.4
Exp/Cntr=0.3,0.1

Type RM Length L Ch R = 1,3472,210,210,210
BEGIN DESCRIPTION:
E20952
END DESCRIPTION:
XS GIS Cut Line= 2
      2465938.70     13843351.96      2464890.30     13843095.51
#Sta/Elev= 30
  4573.9  530.27  4578.0  530.27  4588.0  527.04  4629.3  520.91  4649.8  519.05
  4701.2  516.02  4712.5  513.84  4773.3  508.32  4783.6  508.57  4790.7  506.44
  4845.4  501.92  4948.3  496.67  4962.3  494.54  4968.9  491.72  4987.2  488.13
  4987.5  487.63  4991.8  488.13  5010.1  495.79  5020.4  496.85  5087.2  498.53
  5217.3  508.46  5411.6  516.67  5432.2  516.55  5508.7  520.81  5592.0  527.74
  5597.1  527.02  5617.5  529.21  5633.6  532.47  5638.8  531.08  5653.2  532.36
#Mann=3,-1,0
  4573.9   0.035       0  4987.2   0.035       0  4991.8   0.035       0
Bank Sta=4987.2,4991.8
Exp/Cntr=0.3,0.1

Type RM Length L Ch R = 1,3262,450,450,450
BEGIN DESCRIPTION:
Stream0387 6.0
END DESCRIPTION:
XS GIS Cut Line= 3
      2465775.02     13843125.01      2465625.00     13843075.00
      2465225.03     13842775.02
#Sta/Elev= 30
  4837.6  505.59  4879.8  501.72  4953.6  497.70  4974.7  495.72  4993.1  487.82
  4998.9  487.82  5000.7  486.96  5001.0  486.46  5005.3  486.96  5017.6  492.57
  5023.9  493.11  5032.2  495.42  5073.9  497.83  5088.4  497.29  5109.3  498.57
  5138.4  497.85  5153.0  499.90  5167.6  500.59  5182.2  499.64  5195.7  494.39
  5203.0  497.11  5209.3  497.84  5223.9  502.35  5245.7  503.57  5267.6  506.14
  5287.4  506.57  5353.0  512.70  5423.9  517.47  5467.6  522.14  5495.7  523.68
#Mann=3,-1,0
  4837.6   0.035       0  5000.7   0.035       0  5005.3   0.035       0
Bank Sta=5000.7,5005.3
Exp/Cntr=0.3,0.1

Type RM Length L Ch R = 1,2812,275,275,275
BEGIN DESCRIPTION:
Stream0387 5.0
END DESCRIPTION:
XS GIS Cut Line= 3
      2465924.98     13842774.99      2465775.00     13842675.00
      2465374.96     13842675.00
#Sta/Elev= 30
  4815.0  503.96  4837.5  503.28  4843.5  502.07  4873.6  499.72  4915.6  497.07
  4930.7  495.53  4981.7  492.41  4987.7  491.65  4992.3  490.56  4997.8  490.56
  5005.3  489.17  5012.9  485.61  5013.3  485.11  5017.3  485.11  5017.6  485.61
  5025.3  485.77  5035.3  486.95  5055.3  490.66  5065.3  491.69  5085.3  492.99
  5105.3  493.37  5125.3  494.75  5155.3  495.74  5175.3  497.75  5185.3  497.69
  5235.3  500.86  5285.3  504.88  5335.3  509.46  5355.3  510.28  5395.3  513.13
#Mann=3,-1,0
  4815.0   0.035       0  5012.9   0.035       0  5017.6   0.035       0
Bank Sta=5012.9,5017.6
Exp/Cntr=0.3,0.1

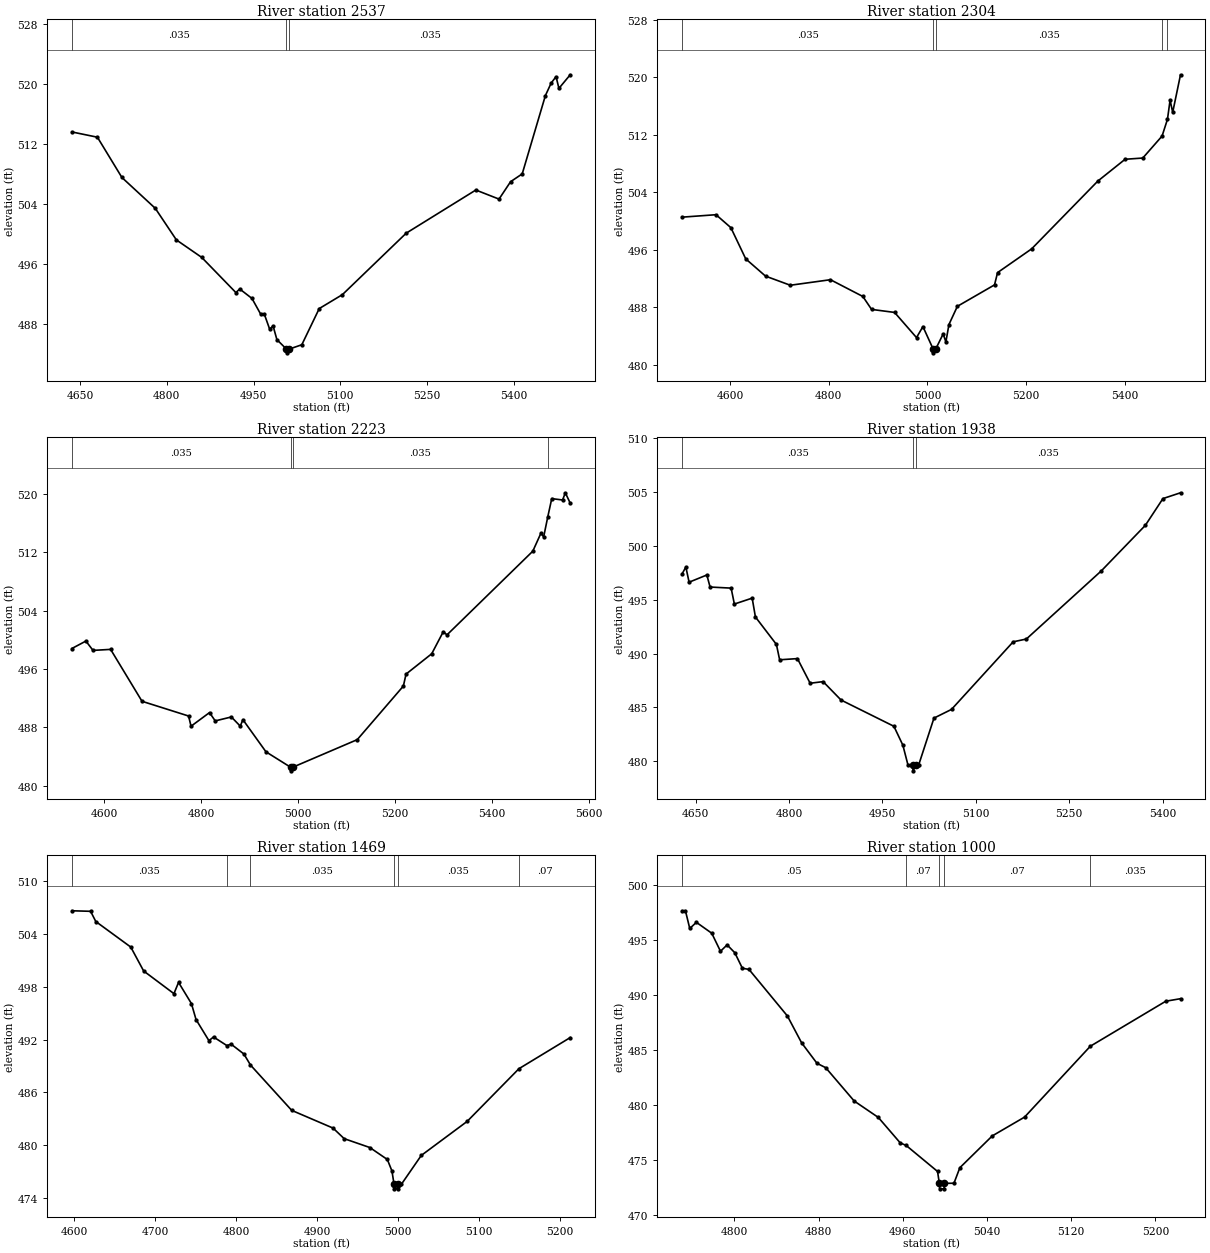
Type RM Length L Ch R = 1,2537,233,233,233
BEGIN DESCRIPTION:
Stream0387 4.0
END DESCRIPTION:
XS GIS Cut Line= 3
      2466174.96     13842624.98      2465858.00     13842425.40
      2465372.21     13842461.57
#Sta/Elev= 30
  4635.9  513.61  4680.0  512.91  4722.4  507.54  4780.1  503.43  4816.6  499.22
  4860.4  496.89  4919.5  492.20  4926.1  492.68  4947.3  491.42  4962.6  489.29
  4968.5  489.36  4977.9  487.32  4983.8  487.76  4990.4  485.93  5006.9  484.67
  5007.2  484.17  5011.7  484.67  5033.5  485.25  5063.6  490.07  5103.7  491.93
  5214.0  500.12  5334.4  505.87  5374.5  504.66  5394.5  506.98  5414.6  508.02
  5454.7  518.46  5464.7  520.13  5473.1  520.98  5478.1  519.42  5497.6  521.23
#Mann=3,-1,0
  4635.9   0.035       0  5006.9   0.035       0  5011.7   0.035       0
Bank Sta=5006.9,5011.7
Exp/Cntr=0.3,0.1

Type RM Length L Ch R = 1,2304,81,81,81
BEGIN DESCRIPTION:
XS6639
END DESCRIPTION:
XS GIS Cut Line= 4
      2466403.27     13842156.64      2466108.67     13842133.38
      2465713.28     13842309.11      2465449.87     13842407.24
#Sta/Elev= 30
  4503.3  500.55  4571.8  500.89  4601.9  499.09  4632.0  494.75  4672.1  492.35
  4722.3  491.08  4803.6  491.85  4869.2  489.52  4886.9  487.72  4933.5  487.30
  4977.9  483.80  4990.9  485.33  5011.8  482.18  5012.1  481.68  5016.6  482.18
  5031.9  484.31  5037.4  483.20  5043.6  485.62  5060.7  488.15  5135.9  491.13
  5142.1  492.84  5211.1  496.14  5345.2  505.57  5400.4  508.60  5436.2  508.77
  5475.3  511.83  5486.2  514.16  5491.5  516.82  5496.8  515.13  5512.6  520.35
#Mann=5,-1,0
  4503.3   0.035       0  5011.8   0.035       0  5016.6   0.035       0
  5475.3    0.07       0  5486.2   0.035       0
Bank Sta=5011.8,5016.6
Exp/Cntr=0.3,0.1

Type RM Length L Ch R = 1,2223,285,285,285
BEGIN DESCRIPTION:
XS6640
END DESCRIPTION:
XS GIS Cut Line= 4
      2466403.31     13842138.56      2466111.25     13842079.11
      2465671.94     13842262.59      2465444.52     13842376.30
#Sta/Elev= 30
  4532.8  498.80  4561.7  499.82  4576.4  498.54  4612.7  498.68  4677.5  491.56
  4773.6  489.54  4778.7  488.14  4816.8  490.01  4828.6  488.87  4861.9  489.41
  4880.3  488.15  4885.7  489.04  4933.3  484.63  4984.0  482.52  4984.3  482.02
  4988.8  482.52  5121.7  486.30  5216.9  493.65  5222.4  495.29  5275.4  498.08
  5299.2  501.10  5306.9  500.67  5484.0  512.15  5500.8  514.62  5506.4  514.11
  5514.9  516.86  5523.1  519.36  5545.5  519.17  5551.1  520.16  5561.2  518.74
#Mann=4,-1,0
  4532.8   0.035       0  4984.0   0.035       0  4988.8   0.035       0
  5514.9    0.07       0
Bank Sta=4984,4988.8
Exp/Cntr=0.3,0.1

Type RM Length L Ch R = 1,1938,469,469,469
BEGIN DESCRIPTION:
Stream0387 3.0
END DESCRIPTION:
XS GIS Cut Line= 4
      2466424.16     13842122.04      2466240.57     13842069.46
      2466125.00     13841925.00      2465825.03     13841625.03
#Sta/Elev= 30
  4628.6  497.42  4634.5  498.04  4639.7  496.63  4668.2  497.30  4673.4  496.18
  4707.2  496.08  4712.4  494.60  4741.0  495.15  4746.2  493.40  4779.9  490.85
  4785.1  489.42  4813.7  489.53  4834.1  487.24  4854.9  487.39  4883.7  485.68
  4968.6  483.24  4983.0  481.48  4991.0  479.68  4999.0  479.60  4999.3  479.10
  5003.8  479.60  5008.1  479.60  5032.9  484.00  5061.1  484.81  5160.1  491.09
  5181.3  491.35  5301.6  497.68  5372.3  501.91  5400.6  504.40  5428.8  504.94
#Mann=3,-1,0
  4628.6   0.035       0  4999.0   0.035       0  5003.8   0.035       0
Bank Sta=4999,5003.8
Exp/Cntr=0.3,0.1

Type RM Length L Ch R = 1,1469,469,469,469
BEGIN DESCRIPTION:
Stream0387 2.0
END DESCRIPTION:
XS GIS Cut Line= 3
      2466875.02     13841925.01      2466525.00     13841725.00
      2466374.97     13841574.97
#Sta/Elev= 30
  4597.1  506.65  4620.2  506.59  4626.6  505.43  4669.8  502.52  4685.7  499.80
  4723.1  497.22  4728.8  498.50  4744.7  496.09  4750.4  494.27  4766.3  491.87
  4772.0  492.29  4788.5  491.31  4793.6  491.48  4809.5  490.35  4817.6  489.10
  4868.5  483.94  4919.6  481.92  4933.3  480.72  4965.0  479.71  4986.6  478.35
  4992.3  477.04  4994.9  475.51  4995.3  475.01  4999.5  475.01  4999.8  475.51
  5003.8  475.51  5028.5  478.81  5085.1  482.68  5149.1  488.68  5212.4  492.22
#Mann=6,-1,0
  4597.1   0.035       0  4788.5    0.05       0  4817.6   0.035       0
  4994.9   0.035       0  4999.8   0.035       0  5149.1    0.07       0
Bank Sta=4994.9,4999.8
Exp/Cntr=0.3,0.1

Type RM Length L Ch R = 1,1000,366,366,366
BEGIN DESCRIPTION:
Stream0387 1.0
END DESCRIPTION:
XS GIS Cut Line= 3
      2467024.97     13841624.96      2466875.00     13841425.00
      2466674.96     13841324.98
#Sta/Elev= 30
  4750.3  497.62  4753.4  497.62  4757.5  496.01  4763.8  496.57  4778.4  495.58
  4786.7  493.94  4793.0  494.52  4800.3  493.81  4807.5  492.40  4813.8  492.29
  4850.3  488.06  4863.8  485.62  4878.4  483.76  4886.7  483.36  4913.8  480.33
  4936.7  478.84  4957.5  476.53  4963.2  476.29  4993.0  473.93  4994.7  472.85
  4995.0  472.35  4999.2  472.35  4999.6  472.85  5008.6  472.86  5014.2  474.27
  5045.0  477.16  5075.7  478.87  5138.2  485.31  5209.9  489.40  5223.9  489.63
#Mann=5,-1,0
  4750.3    0.05       0  4963.2    0.07       0  4994.7    0.05       0
  4999.6    0.07       0  5138.2   0.035       0
Bank Sta=4994.7,4999.6
Exp/Cntr=0.3,0.1

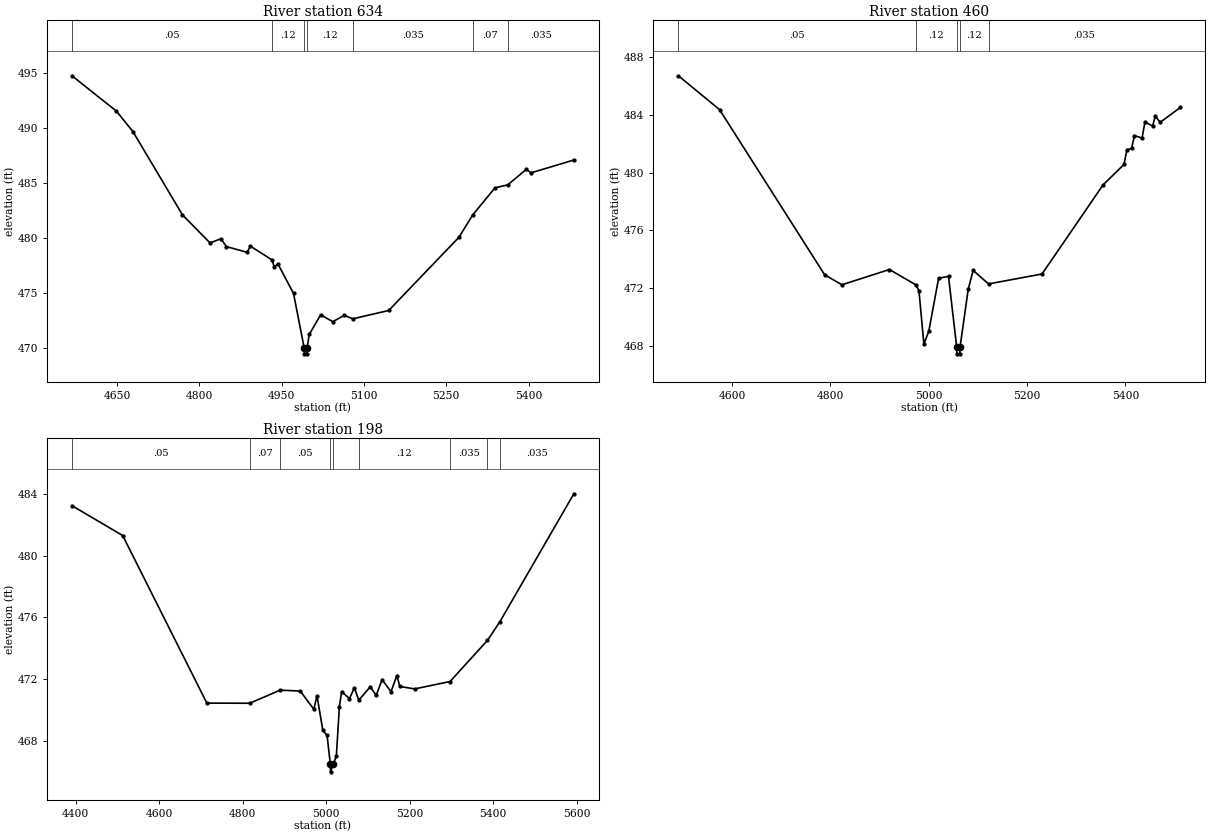
Type RM Length L Ch R = 1,634,174,174,174
BEGIN DESCRIPTION:
XS6638
END DESCRIPTION:
XS GIS Cut Line= 4
      2467137.18     13841595.83      2467163.02     13841231.49
      2467072.58     13841122.95      2466682.32     13841241.84
#Sta/Elev= 30
  4567.9  494.74  4648.9  491.53  4679.0  489.67  4769.2  482.11  4819.4  479.56
  4839.4  479.93  4849.4  479.22  4887.5  478.70  4892.5  479.28  4932.8  478.00
  4936.5  477.34  4943.0  477.67  4971.6  474.97  4991.2  469.98  4991.6  469.48
  4995.8  469.48  4996.1  469.98  5000.3  471.24  5021.1  473.03  5043.2  472.40
  5064.1  472.98  5079.6  472.66  5145.1  473.42  5273.0  480.07  5298.0  482.09
  5338.6  484.56  5362.0  484.83  5396.0  486.25  5404.3  485.92  5482.4  487.09
#Mann=7,-1,0
  4567.9    0.05       0  4932.8    0.12       0  4991.2    0.05       0
  4996.1    0.12       0  5079.6   0.035       0  5298.0    0.07       0
  5362.0   0.035       0
Bank Sta=4991.2,4996.1
Exp/Cntr=0.3,0.1

Type RM Length L Ch R = 1,460,262,262,262
BEGIN DESCRIPTION:
E20951
END DESCRIPTION:
XS GIS Cut Line= 4
      2467702.36     13841204.65      2467313.82     13841044.05
      2466971.88     13841064.77      2466751.71     13841199.47
#Sta/Elev= 30
  4490.6  486.73  4574.3  484.38  4788.0  472.93  4823.2  472.23  4919.9  473.29
  4974.4  472.21  4980.0  471.80  4990.0  468.12  5000.0  469.01  5020.0  472.69
  5040.1  472.81  5056.6  467.94  5057.1  467.44  5063.2  467.44  5063.7  467.94
  5080.2  471.92  5090.2  473.23  5121.5  472.29  5230.4  472.98  5354.5  479.16
  5397.1  480.58  5403.0  481.59  5412.6  481.70  5418.4  482.58  5433.9  482.41
  5439.7  483.52  5455.2  483.25  5461.0  483.93  5470.6  483.50  5511.7  484.53
#Mann=5,-1,0
  4490.6    0.05       0  4974.4    0.12       0  5056.6    0.05       0
  5063.7    0.12       0  5121.5   0.035       0
Bank Sta=5056.6,5063.7
Exp/Cntr=0.3,0.1

Type RM Length L Ch R = 1,198,0,0,0
BEGIN DESCRIPTION:
E20950
END DESCRIPTION:
XS GIS Cut Line= 4
      2467795.61     13840826.45      2467285.32     13840761.69
      2467119.53     13840829.04      2466754.28     13841183.94
#Sta/Elev= 30
  4390.8  483.25  4512.4  481.31  4714.0  470.44  4816.7  470.43  4889.7  471.28
  4937.9  471.22  4970.3  470.04  4978.0  470.91  4991.9  468.68  5002.1  468.34
  5009.9  466.48  5010.4  465.98  5017.0  466.48  5024.3  466.99  5031.6  470.21
  5037.0  471.19  5055.7  470.73  5067.4  471.43  5078.1  470.63  5105.6  471.50
  5119.8  470.94  5133.9  471.96  5155.2  471.18  5169.4  472.23  5176.3  471.52
  5211.8  471.36  5296.8  471.84  5386.4  474.51  5416.4  475.73  5593.4  484.02
#Mann=9,-1,0
  4390.8    0.05       0  4816.7    0.07       0  4889.7    0.05       0
  5009.9    0.05       0  5017.0    0.05       0  5078.1    0.12       0
  5296.8   0.035       0  5386.4    0.07       0  5416.4   0.035       0
Bank Sta=5009.9,5017
Exp/Cntr=0.3,0.1

Chan Stop Cuts=-1