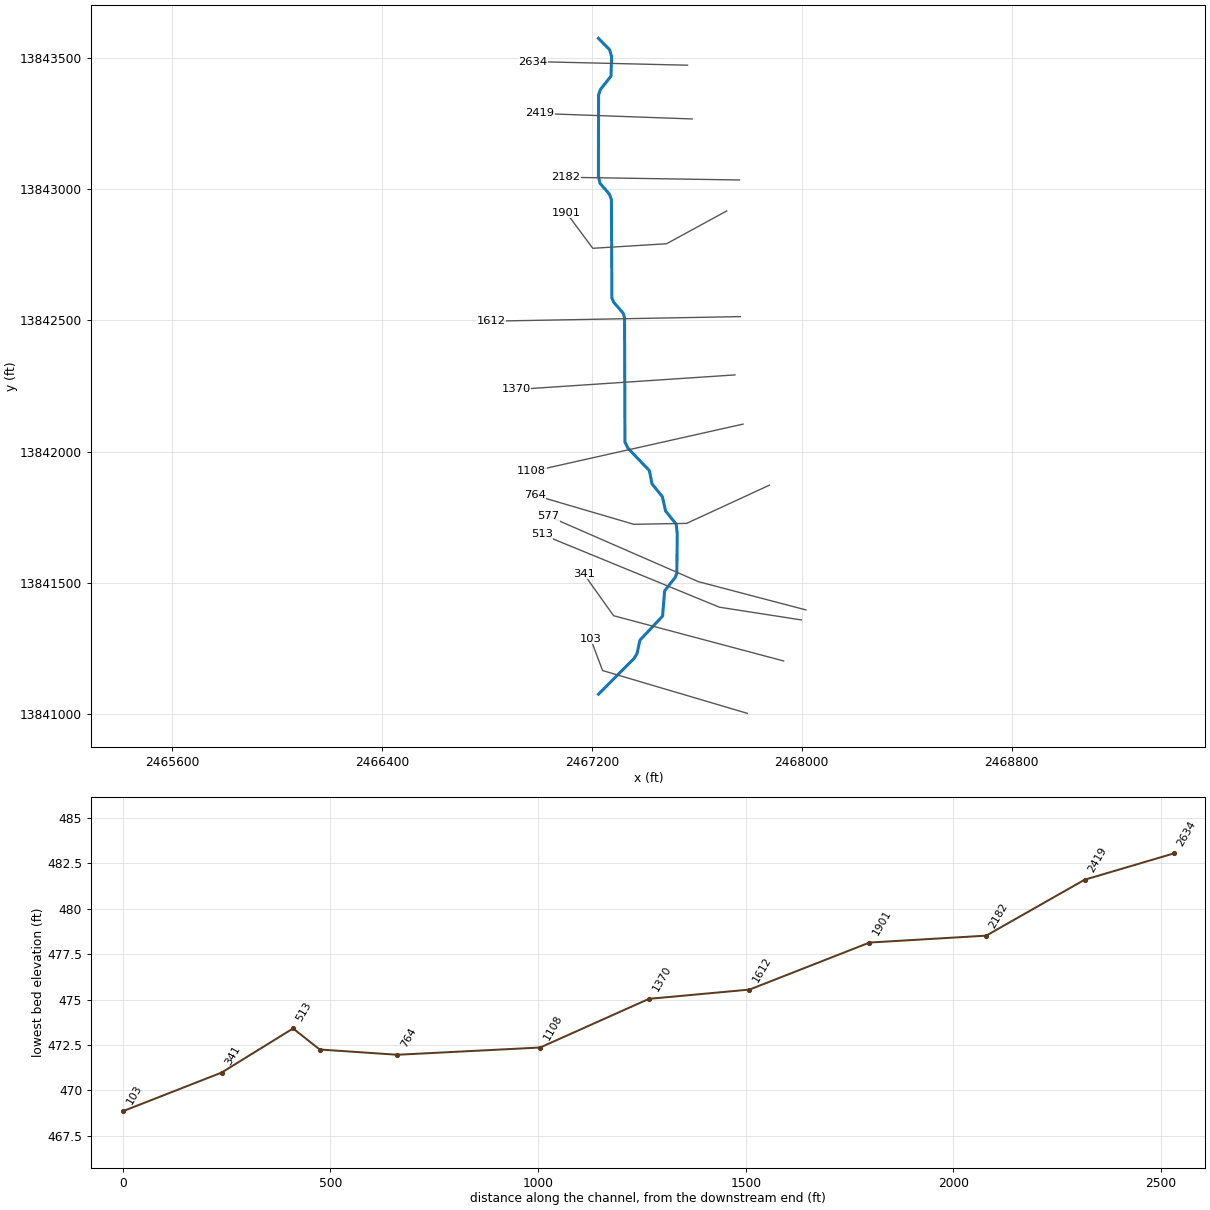
--- Stream0388.prj (project) ---

Proj Title=Stream0388 Base Level Engineering
Current Plan=p01
Default Exp/Contr=0.3,0.1
English Units
Geom File=g01
Flow File=f01
Plan File=p01
BEGIN DESCRIPTION:
Stream0388
END DESCRIPTION:

--- Stream0388.p01 (plan) ---

Plan Title=Multiple Run
Short Identifier=Multiple
Geom File=g01
Flow File=f01
Subcritical Flow
K Sum by GR= 0
Std Step Tol= 0.01
Critical Tol= 0.01
Num of Std Step Trials= 20
Max Error Tol= 0.3
Flow Tol Ratio= 0.001
Split Flow NTrial= 30
Split Flow Tol= 0.02
Split Flow Ratio= 0.02
Log Output Level= 0
Friction Slope Method= 1
Unsteady Friction Slope Method= 2
Unsteady Bridges Friction Slope Method= 1
Parabolic Critical Depth
Global Vel Dist=  1 , 1 , 1
Global Log Level= 0
CheckData=True
Encroach Param= -1, 0, 0, 0
BEGIN DESCRIPTION:
Multiple Run
END DESCRIPTION:

--- Stream0388.f01 (steady flow) ---

Flow Title=Multiple
Number of Profiles=7
Profile Names=10-year,25-year,50-year,1pct_min,100-year,1pct_plu,500-year
River Rch & RM= Stream0388,Reach-1,2634
     733    1191    1608    1052    2099    4189    3543
Boundary for River Rch & Prof#=Stream0388,Reach-1,1
Up Type=0
Dn Type=3
Dn Slope=0.005
Boundary for River Rch & Prof#=Stream0388,Reach-1,2
Up Type=0
Dn Type=3
Dn Slope=0.005
Boundary for River Rch & Prof#=Stream0388,Reach-1,3
Up Type=0
Dn Type=3
Dn Slope=0.005
Boundary for River Rch & Prof#=Stream0388,Reach-1,4
Up Type=0
Dn Type=3
Dn Slope=0.005
Boundary for River Rch & Prof#=Stream0388,Reach-1,5
Up Type=0
Dn Type=3
Dn Slope=0.005
Boundary for River Rch & Prof#=Stream0388,Reach-1,6
Up Type=0
Dn Type=3
Dn Slope=0.005
Boundary for River Rch & Prof#=Stream0388,Reach-1,7
Up Type=0
Dn Type=3
Dn Slope=0.005

--- Stream0388.g01 (geometry) ---

Geom Title=Existing Conditions

River Reach=Stream0388,Reach-1
Reach XY= 30
      2467225.00     13843575.00      2467267.64     13843531.32
      2467275.22     13843504.92      2467272.84     13843430.96
      2467233.14     13843381.06      2467225.52     13843359.78
      2467224.80     13843049.92      2467230.75     13843022.67
      2467266.86     13842981.06      2467274.48     13842959.78
      2467276.22     13842585.50      2467283.14     13842568.94
      2467319.25     13842527.33      2467324.48     13842509.78
      2467326.05     13842035.44      2467338.40     13842011.69
      2467419.15     13841927.29      2467429.19     13841876.74
      2467468.92     13841827.20      2467481.12     13841772.82
      2467521.25     13841723.45      2467525.46     13841685.19
      2467523.78     13841535.50      2467516.86     13841518.94
      2467477.36     13841469.02      2467469.46     13841372.58
      2467383.18     13841281.04      2467372.47     13841231.05
      2467361.38     13841211.79      2467225.00     13841075.00

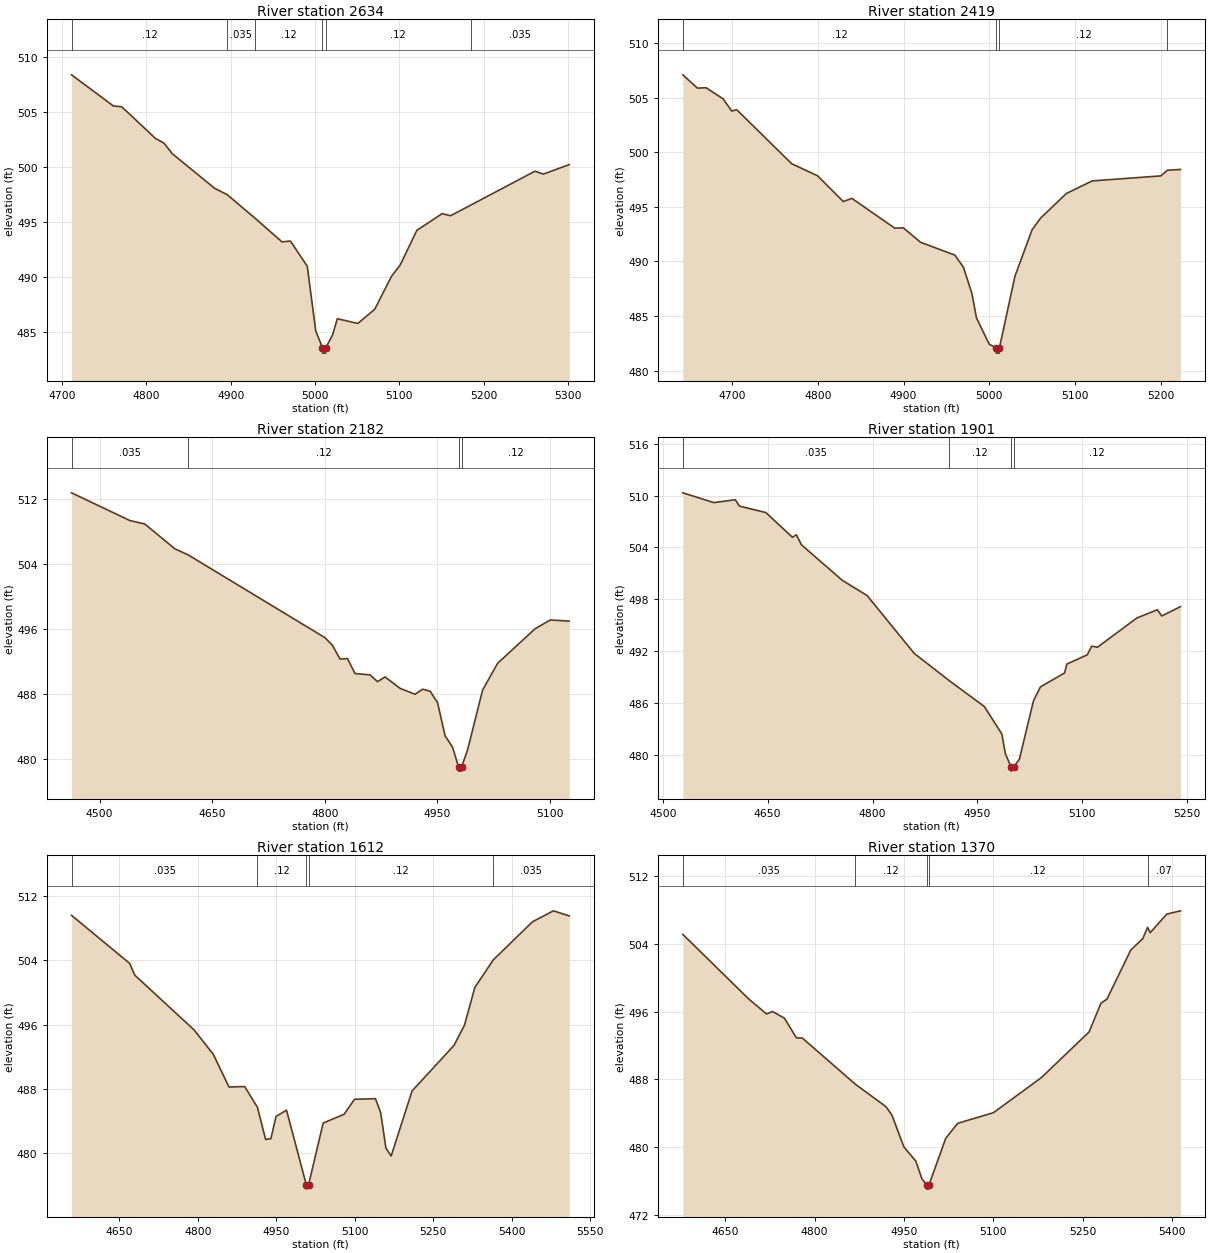
Type RM Length L Ch R = 1,2634,215,215,215
BEGIN DESCRIPTION:
XS6651
END DESCRIPTION:
XS GIS Cut Line= 2
      2467564.61     13843472.57      2466974.28     13843486.46
#Sta/Elev= 30
  4711.1  508.37  4760.7  505.54  4770.7  505.46  4810.7  502.58  4820.7  502.16
  4830.7  501.19  4880.8  498.05  4895.9  497.46  4929.2  495.30  4960.8  493.17
  4970.8  493.25  4990.8  490.95  5000.8  485.07  5008.8  483.55  5009.0  483.05
  5012.5  483.05  5012.8  483.55  5020.8  484.70  5026.4  486.18  5050.8  485.75
  5070.8  487.04  5090.8  490.05  5100.8  491.04  5120.8  494.22  5150.8  495.74
  5160.8  495.55  5184.8  496.52  5260.9  499.60  5270.9  499.34  5301.6  500.20
#Mann=6,-1,0
  4711.1    0.12       0  4895.9   0.035       0  4929.2    0.12       0
  5008.8    0.05       0  5012.8    0.12       0  5184.8   0.035       0
Bank Sta=5008.8,5012.8
Exp/Cntr=0.3,0.1

Type RM Length L Ch R = 1,2419,237,237,237
BEGIN DESCRIPTION:
XS6650
END DESCRIPTION:
XS GIS Cut Line= 2
      2467581.97     13843267.71      2467002.04     13843288.54
#Sta/Elev= 30
  4642.7  507.10  4659.7  505.88  4669.7  505.92  4689.7  504.90  4699.7  503.78
  4705.6  503.90  4769.7  498.95  4799.8  497.85  4829.8  495.49  4839.8  495.78
  4889.8  493.05  4899.8  493.08  4919.8  491.76  4959.9  490.58  4969.9  489.47
  4979.9  487.03  4985.0  484.85  4999.9  482.42  5007.9  482.10  5008.2  481.60
  5011.7  481.60  5011.9  482.10  5029.9  488.64  5049.9  492.90  5059.9  493.98
  5090.0  496.23  5120.0  497.38  5200.0  497.84  5207.8  498.36  5223.0  498.43
#Mann=4,-1,0
  4642.7    0.12       0  5007.9    0.05       0  5011.9    0.12       0
  5207.8   0.035       0
Bank Sta=5007.9,5011.9
Exp/Cntr=0.3,0.1

Type RM Length L Ch R = 1,2182,281,281,281
BEGIN DESCRIPTION:
XS6649
END DESCRIPTION:
XS GIS Cut Line= 2
      2467762.55     13843035.07      2467099.63     13843045.48
#Sta/Elev= 30
  4462.6  512.70  4540.2  509.30  4560.2  508.87  4600.2  505.83  4618.1  505.07
  4800.2  494.91  4810.2  493.97  4820.2  492.29  4830.2  492.34  4840.2  490.51
  4860.2  490.34  4870.2  489.51  4880.2  490.09  4900.2  488.69  4920.2  487.96
  4930.2  488.58  4940.2  488.34  4950.2  486.93  4960.2  482.86  4970.2  481.45
  4978.2  479.02  4978.5  478.52  4982.0  478.52  4982.2  479.02  4990.2  481.14
  5010.2  488.48  5030.2  491.77  5080.2  496.01  5100.2  497.08  5125.6  496.95
#Mann=4,-1,0
  4462.6   0.035       0  4618.1    0.12       0  4978.2    0.05       0
  4982.2    0.12       0
Bank Sta=4978.2,4982.2
Exp/Cntr=0.3,0.1

Type RM Length L Ch R = 1,1901,289,289,289
BEGIN DESCRIPTION:
XS6648
END DESCRIPTION:
XS GIS Cut Line= 4
      2467713.93     13842917.04      2467484.72     13842792.01
      2467203.47     13842774.65      2467102.79     13842910.05
#Sta/Elev= 30
  4528.8  510.32  4573.1  509.19  4603.9  509.52  4609.6  508.79  4647.5  508.04
  4685.5  505.18  4691.2  505.47  4698.4  504.31  4756.7  500.21  4792.3  498.44
  4859.7  491.75  4909.6  488.61  4959.9  485.61  4984.9  482.44  4990.0  480.15
  4998.0  478.64  4998.3  478.14  5002.0  478.64  5010.0  479.52  5030.1  486.26
  5040.1  487.88  5074.6  489.49  5077.9  490.52  5107.1  491.59  5113.4  492.59
  5121.7  492.47  5178.0  495.85  5207.3  496.80  5213.5  496.08  5240.4  497.16
#Mann=4,-1,0
  4528.8   0.035       0  4909.6    0.12       0  4998.0    0.05       0
  5002.0    0.12       0
Bank Sta=4998,5002
Exp/Cntr=0.3,0.1

Type RM Length L Ch R = 1,1612,242,242,242
BEGIN DESCRIPTION:
XS6647
END DESCRIPTION:
XS GIS Cut Line= 2
      2467765.94     13842514.24      2466814.60     13842496.88
#Sta/Elev= 30
  4558.8  509.58  4669.8  503.61  4679.8  502.14  4792.9  495.35  4829.8  492.31
  4859.8  488.24  4889.8  488.30  4914.2  485.72  4929.8  481.73  4939.8  481.81
  4949.8  484.59  4969.8  485.36  5007.8  476.05  5008.1  475.55  5011.8  476.05
  5039.8  483.76  5079.8  484.85  5099.8  486.72  5139.8  486.79  5149.8  485.05
  5159.8  480.66  5169.8  479.66  5209.8  487.75  5289.9  493.41  5309.9  495.91
  5329.9  500.63  5365.2  504.05  5439.9  508.77  5479.9  510.14  5510.3  509.51
#Mann=5,-1,0
  4558.8   0.035       0  4914.2    0.12       0  5007.8    0.05       0
  5011.8    0.12       0  5365.2   0.035       0
Bank Sta=5007.8,5011.8
Exp/Cntr=0.3,0.1

Type RM Length L Ch R = 1,1370,262,262,262
BEGIN DESCRIPTION:
XS6646
END DESCRIPTION:
XS GIS Cut Line= 2
      2467745.16     13842292.02      2466911.81     13842236.46
#Sta/Elev= 30
  4578.9  505.13  4689.3  497.51  4719.4  495.73  4729.4  496.02  4749.4  495.23
  4769.5  492.91  4779.5  492.88  4868.5  487.43  4919.8  484.78  4929.8  483.78
  4949.9  480.02  4969.9  478.35  4979.9  476.30  4988.0  475.54  4988.2  475.04
  4991.7  475.04  4992.0  475.54  5020.0  481.03  5040.1  482.81  5100.2  484.07
  5180.4  488.20  5260.6  493.60  5280.6  497.00  5290.6  497.48  5330.7  503.29
  5350.8  504.63  5358.8  505.96  5363.3  505.33  5390.9  507.52  5414.1  507.91
#Mann=5,-1,0
  4578.9   0.035       0  4868.5    0.12       0  4988.0    0.05       0
  4992.0    0.12       0  5358.8    0.07       0
Bank Sta=4988,4992
Exp/Cntr=0.3,0.1

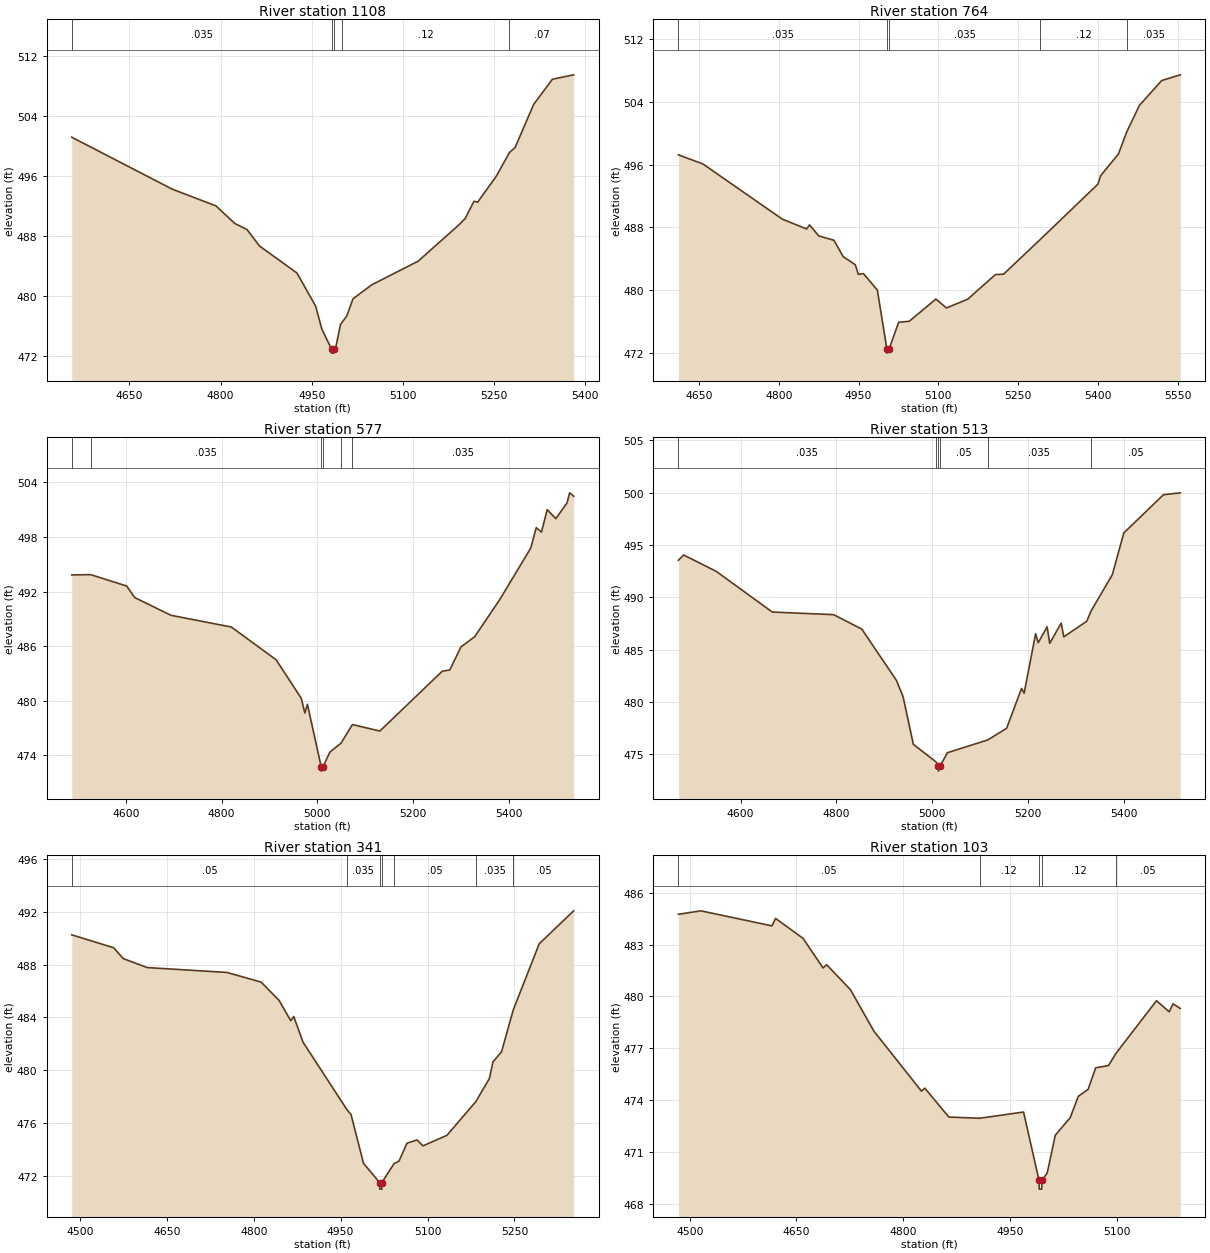
Type RM Length L Ch R = 1,1108,344,344,344
BEGIN DESCRIPTION:
XS6645
END DESCRIPTION:
XS GIS Cut Line= 2
      2467776.44     13842104.52      2466970.83     13841923.96
#Sta/Elev= 30
  4555.2  501.19  4720.6  494.25  4792.4  492.02  4823.1  489.69  4843.6  488.85
  4864.1  486.66  4925.6  483.06  4956.3  478.65  4966.6  475.56  4982.7  472.86
  4982.9  472.36  4986.4  472.36  4986.7  472.86  4989.8  473.24  4997.3  476.21
  4999.7  476.47  5007.6  477.31  5017.8  479.61  5048.6  481.48  5125.0  484.64
  5192.1  489.49  5202.3  490.33  5216.8  492.64  5222.8  492.51  5253.5  495.98
  5275.2  499.15  5284.3  499.79  5315.0  505.57  5345.8  508.93  5380.8  509.52
#Mann=5,-1,0
  4555.2   0.035       0  4982.7    0.05       0  4986.7   0.035       0
  4999.7    0.12       0  5275.2    0.07       0
Bank Sta=4982.7,4986.7
Exp/Cntr=0.3,0.1

Type RM Length L Ch R = 1,764,187,187,187
BEGIN DESCRIPTION:
XS6644
END DESCRIPTION:
XS GIS Cut Line= 4
      2467877.07     13841871.87      2467561.11     13841726.04
      2467359.72     13841722.57      2466981.30     13841833.67
#Sta/Elev= 30
  4611.2  497.24  4657.5  496.07  4806.4  489.05  4852.3  487.79  4857.8  488.31
  4875.2  486.90  4903.7  486.35  4921.1  484.26  4943.9  483.23  4949.6  482.00
  4959.2  482.10  4985.3  480.00  5003.3  472.46  5003.6  471.96  5007.3  472.46
  5025.3  475.89  5045.3  476.02  5095.3  478.85  5115.3  477.72  5155.3  478.84
  5207.2  481.97  5222.7  482.03  5291.3  486.43  5400.0  493.50  5405.2  494.59
  5438.6  497.34  5454.3  500.18  5478.2  503.55  5519.9  506.71  5555.0  507.44
#Mann=5,-1,0
  4611.2   0.035       0  5003.3   0.035       0  5007.3   0.035       0
  5291.3    0.12       0  5454.3   0.035       0
Bank Sta=5003.3,5007.3
Exp/Cntr=0.3,0.1

Type RM Length L Ch R = 1,577,64,64,64
BEGIN DESCRIPTION:
XS6643
END DESCRIPTION:
XS GIS Cut Line= 3
      2468015.92     13841396.19      2467606.25     13841503.82
      2467033.30     13841753.83
#Sta/Elev= 30
  4487.1  493.83  4526.7  493.86  4601.8  492.61  4618.7  491.34  4694.3  489.39
  4820.5  488.10  4914.1  484.50  4966.6  480.26  4974.1  478.64  4979.5  479.60
  5008.2  472.75  5008.5  472.25  5012.2  472.75  5026.4  474.34  5049.5  475.31
  5073.5  477.37  5130.9  476.66  5261.2  483.24  5276.9  483.37  5300.3  485.91
  5329.1  487.04  5381.4  491.12  5446.2  496.79  5457.6  499.03  5468.5  498.54
  5480.5  501.01  5498.5  500.02  5521.9  501.75  5527.4  502.86  5535.8  502.48
#Mann=6,-1,0
  4487.1    0.12       0  4526.7   0.035       0  5008.2   0.035       0
  5012.2   0.035       0  5049.5    0.05       0  5073.5   0.035       0
Bank Sta=5008.2,5012.2
Exp/Cntr=0.3,0.1

Type RM Length L Ch R = 1,513,172,172,172
BEGIN DESCRIPTION:
XS6642
END DESCRIPTION:
XS GIS Cut Line= 3
      2467998.61     13841357.99      2467686.11     13841406.60
      2467009.50     13841684.18
#Sta/Elev= 30
  4470.1  493.56  4481.0  494.06  4549.0  492.50  4666.0  488.61  4794.1  488.36
  4852.9  486.98  4924.9  482.10  4938.9  480.55  4960.5  475.97  5008.1  474.28
  5012.5  473.91  5012.8  473.41  5016.5  473.91  5031.6  475.17  5115.8  476.39
  5155.1  477.50  5186.3  481.31  5191.7  480.86  5215.7  486.53  5221.1  485.68
  5239.7  487.20  5245.1  485.62  5269.1  487.55  5274.5  486.24  5322.4  487.73
  5331.3  488.70  5375.8  492.18  5399.8  496.17  5482.5  499.82  5517.7  500.00
#Mann=6,-1,0
  4470.1   0.035       0  5008.1    0.05       0  5012.5   0.035       0
  5016.5    0.05       0  5115.8   0.035       0  5331.3    0.05       0
Bank Sta=5012.5,5016.5
Exp/Cntr=0.3,0.1

Type RM Length L Ch R = 1,341,238,238,238
BEGIN DESCRIPTION:
E20953
END DESCRIPTION:
XS GIS Cut Line= 3
      2467930.91     13841201.64      2467282.86     13841374.06
      2467169.19     13841533.49
#Sta/Elev= 30
  4485.9  490.25  4558.3  489.27  4574.8  488.45  4616.2  487.77  4753.8  487.40
  4812.8  486.67  4843.8  485.28  4863.9  483.74  4869.1  484.06  4885.2  482.11
  4960.8  477.01  4968.0  476.63  4989.5  472.94  5017.3  471.48  5017.6  470.98
  5021.1  470.98  5021.3  471.48  5042.1  472.91  5050.8  473.10  5064.6  474.46
  5081.8  474.71  5092.2  474.26  5133.6  475.06  5183.5  477.62  5206.8  479.36
  5213.0  480.62  5227.8  481.39  5248.0  484.56  5292.8  489.57  5352.3  492.07
#Mann=7,-1,0
  4485.9    0.05       0  4960.8   0.035       0  5017.3   0.035       0
  5021.3   0.035       0  5042.1    0.05       0  5183.5   0.035       0
  5248.0    0.05       0
Bank Sta=5017.3,5021.3
Exp/Cntr=0.3,0.1

Type RM Length L Ch R = 1,103,0,0,0
BEGIN DESCRIPTION:
XS6641
END DESCRIPTION:
XS GIS Cut Line= 3
      2467792.90     13841001.84      2467240.78     13841165.04
      2467195.17     13841286.32
#Sta/Elev= 30
  4484.1  484.75  4515.7  484.95  4615.5  484.08  4620.7  484.51  4659.2  483.36
  4687.3  481.65  4692.5  481.83  4725.8  480.39  4759.0  477.98  4825.6  474.52
  4830.4  474.69  4864.1  473.02  4907.3  472.95  4969.1  473.31  4990.9  469.35
  4991.1  468.85  4994.6  468.85  4994.9  469.35  5002.4  469.79  5013.7  471.97
  5034.6  472.98  5046.1  474.22  5059.8  474.62  5070.5  475.87  5088.5  476.00
  5099.1  476.71  5155.9  479.75  5173.8  479.11  5179.2  479.57  5189.4  479.30
#Mann=5,-1,0
  4484.1    0.05       0  4907.3    0.12       0  4990.9    0.05       0
  4994.9    0.12       0  5099.1    0.05       0
Bank Sta=4990.9,4994.9
Exp/Cntr=0.3,0.1

Chan Stop Cuts=-1