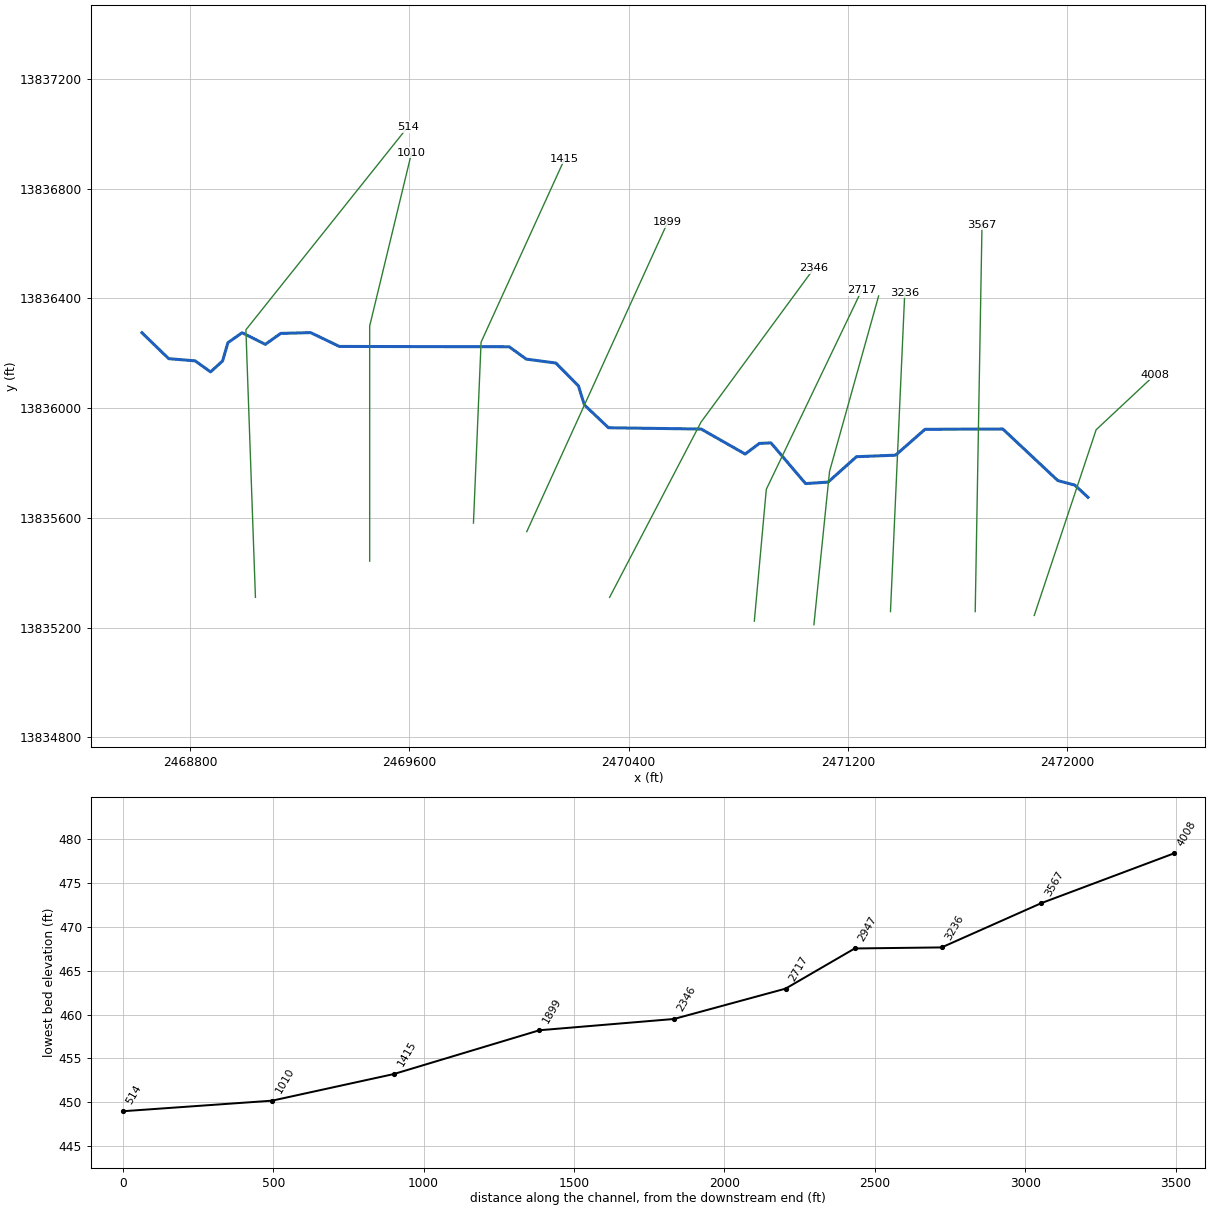
--- Stream0389.prj (project) ---

Proj Title=Stream0389 Base Level Engineering
Current Plan=p01
Default Exp/Contr=0.3,0.1
English Units
Geom File=g01
Flow File=f01
Plan File=p01
BEGIN DESCRIPTION:
Stream0389
END DESCRIPTION:

--- Stream0389.p01 (plan) ---

Plan Title=Multiple Run
Short Identifier=Multiple
Geom File=g01
Flow File=f01
Subcritical Flow
K Sum by GR= 0
Std Step Tol= 0.01
Critical Tol= 0.01
Num of Std Step Trials= 20
Max Error Tol= 0.3
Flow Tol Ratio= 0.001
Split Flow NTrial= 30
Split Flow Tol= 0.02
Split Flow Ratio= 0.02
Log Output Level= 0
Friction Slope Method= 1
Unsteady Friction Slope Method= 2
Unsteady Bridges Friction Slope Method= 1
Parabolic Critical Depth
Global Vel Dist=  1 , 1 , 1
Global Log Level= 0
CheckData=True
Encroach Param= -1, 0, 0, 0
BEGIN DESCRIPTION:
Multiple Run
END DESCRIPTION:

--- Stream0389.f01 (steady flow) ---

Flow Title=Multiple
Number of Profiles=7
Profile Names=10-year,25-year,50-year,1pct_min,100-year,1pct_plu,500-year
River Rch & RM= Stream0389,Reach-1,4008
     489     771    1020     655    1306    2607    2120
Boundary for River Rch & Prof#=Stream0389,Reach-1,1
Up Type=0
Dn Type=3
Dn Slope=0.005
Boundary for River Rch & Prof#=Stream0389,Reach-1,2
Up Type=0
Dn Type=3
Dn Slope=0.005
Boundary for River Rch & Prof#=Stream0389,Reach-1,3
Up Type=0
Dn Type=3
Dn Slope=0.005
Boundary for River Rch & Prof#=Stream0389,Reach-1,4
Up Type=0
Dn Type=3
Dn Slope=0.005
Boundary for River Rch & Prof#=Stream0389,Reach-1,5
Up Type=0
Dn Type=3
Dn Slope=0.005
Boundary for River Rch & Prof#=Stream0389,Reach-1,6
Up Type=0
Dn Type=3
Dn Slope=0.005
Boundary for River Rch & Prof#=Stream0389,Reach-1,7
Up Type=0
Dn Type=3
Dn Slope=0.005

--- Stream0389.g01 (geometry) ---

Geom Title=Existing Conditions

River Reach=Stream0389,Reach-1
Reach XY= 30
      2472075.00     13835675.00      2472027.35     13835719.29
      2471965.29     13835735.70      2471764.57     13835923.95
      2471480.86     13835922.93      2471373.53     13835828.56
      2471230.86     13835822.92      2471127.36     13835730.39
      2471045.26     13835724.87      2470918.96     13835873.35
      2470876.65     13835871.43      2470825.00     13835832.56
      2470664.50     13835923.80      2470326.45     13835928.53
      2470238.62     13836011.76      2470216.85     13836081.07
      2470134.81     13836164.49      2470026.60     13836178.86
      2469964.50     13836223.78      2469345.03     13836225.07
      2469240.16     13836275.47      2469130.86     13836272.55
      2469074.99     13836232.59      2468990.24     13836275.04
      2468938.49     13836238.67      2468919.14     13836172.18
      2468875.31     13836132.23      2468819.12     13836172.43
      2468722.55     13836180.46      2468625.00     13836275.00

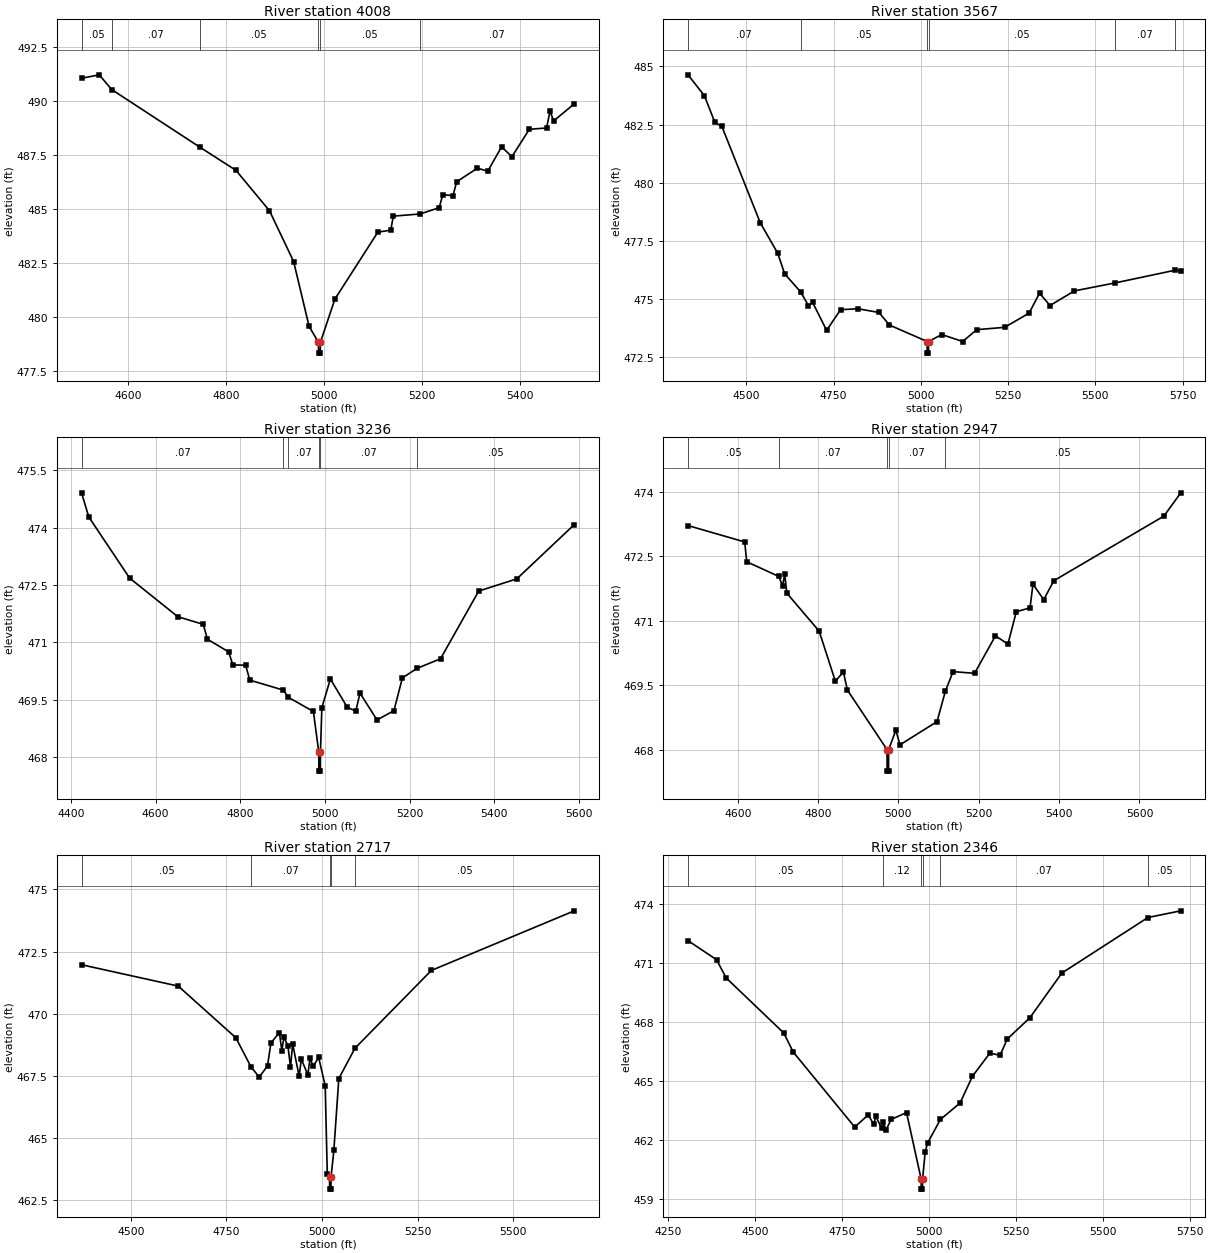
Type RM Length L Ch R = 1,4008,441,441,441
BEGIN DESCRIPTION:
XS6660
END DESCRIPTION:
XS GIS Cut Line= 3
      2471879.16     13835244.07      2472104.86     13835921.18
      2472318.73     13836121.25
#Sta/Elev= 30
  4504.9  491.04  4541.0  491.20  4566.4  490.52  4746.7  487.85  4820.3  486.78
  4888.8  484.91  4938.1  482.56  4969.7  479.56  4988.8  478.82  4989.0  478.32
  4992.5  478.32  4992.8  478.82  5022.4  480.82  5110.2  483.92  5136.5  484.01
  5141.8  484.66  5196.2  484.76  5235.5  485.05  5242.8  485.65  5263.8  485.61
  5271.1  486.25  5313.6  486.88  5334.6  486.74  5363.0  487.87  5384.0  487.41
  5419.6  488.68  5454.8  488.74  5462.1  489.54  5469.0  489.06  5511.5  489.86
#Mann=6,-1,0
  4504.9    0.05       0  4566.4    0.07       0  4746.7    0.05       0
  4988.8    0.05       0  4992.8    0.05       0  5196.2    0.07       0
Bank Sta=4988.8,4992.8
Exp/Cntr=0.3,0.1

Type RM Length L Ch R = 1,3567,331,331,331
BEGIN DESCRIPTION:
XS6659
END DESCRIPTION:
XS GIS Cut Line= 2
      2471663.89     13835257.99      2471688.69     13836669.68
#Sta/Elev= 30
  4332.8  484.64  4379.8  483.74  4409.8  482.59  4429.8  482.42  4539.8  478.27
  4589.8  476.96  4609.8  476.07  4655.2  475.30  4677.7  474.71  4689.9  474.84
  4729.9  473.64  4769.9  474.53  4819.9  474.57  4879.9  474.41  4909.9  473.87
  5017.9  473.16  5018.2  472.66  5021.7  472.66  5021.9  473.16  5059.9  473.46
  5119.9  473.16  5159.9  473.67  5239.9  473.77  5310.0  474.38  5340.0  475.24
  5370.0  474.71  5440.0  475.34  5555.7  475.68  5728.8  476.23  5744.7  476.20
#Mann=6,-1,0
  4332.8    0.07       0  4655.2    0.05       0  5017.9    0.05       0
  5021.9    0.05       0  5555.7    0.07       0  5728.8    0.05       0
Bank Sta=5017.9,5021.9
Exp/Cntr=0.3,0.1

Type RM Length L Ch R = 1,3236,289,289,289
BEGIN DESCRIPTION:
XS6658
END DESCRIPTION:
XS GIS Cut Line= 2
      2471354.86     13835258.03      2471406.92     13836420.57
#Sta/Elev= 30
  4425.0  474.91  4442.0  474.28  4538.5  472.68  4652.2  471.67  4712.3  471.47
  4722.3  471.08  4772.3  470.75  4782.3  470.41  4812.4  470.40  4822.4  470.01
  4901.4  469.75  4913.5  469.56  4972.5  469.19  4985.2  468.13  4985.5  467.63
  4989.0  467.63  4989.2  468.13  4992.5  469.29  5012.6  470.04  5052.6  469.30
  5072.6  469.20  5082.6  469.67  5122.7  468.97  5162.7  469.21  5182.7  470.07
  5217.7  470.32  5272.8  470.57  5362.9  472.34  5453.0  472.66  5588.7  474.08
#Mann=6,-1,0
  4425.0    0.07       0  4901.4    0.05       0  4913.5    0.07       0
  4985.2    0.05       0  4989.2    0.07       0  5217.7    0.05       0
Bank Sta=4985.2,4989.2
Exp/Cntr=0.3,0.1

Type RM Length L Ch R = 1,2947,230,230,230
BEGIN DESCRIPTION:
E20954
END DESCRIPTION:
XS GIS Cut Line= 3
      2471075.63     13835210.26      2471132.60     13835769.07
      2471311.65     13836409.30
#Sta/Elev= 30
  4476.3  473.21  4617.4  472.83  4622.4  472.37  4702.2  472.03  4711.9  471.81
  4716.9  472.09  4722.3  471.64  4802.7  470.76  4842.9  469.60  4863.0  469.81
  4873.1  469.39  4971.6  468.01  4971.9  467.51  4975.4  467.51  4975.6  468.01
  4993.7  468.46  5003.8  468.12  5096.1  468.66  5117.0  469.37  5136.1  469.82
  5189.5  469.78  5241.5  470.65  5272.6  470.46  5293.4  471.21  5327.6  471.30
  5334.9  471.85  5361.7  471.49  5386.8  471.93  5660.8  473.43  5702.8  473.97
#Mann=5,-1,0
  4476.3    0.05       0  4702.2    0.07       0  4971.6    0.05       0
  4975.6    0.07       0  5117.0    0.05       0
Bank Sta=4971.6,4975.6
Exp/Cntr=0.3,0.1

Type RM Length L Ch R = 1,2717,371,371,371
BEGIN DESCRIPTION:
XS6657
END DESCRIPTION:
XS GIS Cut Line= 3
      2470858.33     13835223.25      2470902.02     13835703.97
      2471249.98     13836430.10
#Sta/Elev= 30
  4371.3  471.97  4624.1  471.11  4774.7  469.03  4814.5  467.85  4835.8  467.45
  4857.3  467.90  4866.2  468.82  4888.4  469.24  4894.8  468.50  4900.3  469.06
  4910.6  468.71  4917.4  467.86  4923.0  468.78  4940.1  467.48  4945.6  468.17
  4962.8  467.54  4968.3  468.20  4977.1  467.89  4991.0  468.24  5008.1  467.10
  5013.6  463.54  5019.5  463.44  5019.7  462.94  5023.2  462.94  5023.5  463.44
  5030.7  464.50  5043.7  467.39  5085.9  468.61  5285.5  471.74  5659.2  474.14
#Mann=5,-1,0
  4371.3    0.05       0  4814.5    0.07       0  5019.5    0.05       0
  5023.5    0.07       0  5085.9    0.05       0
Bank Sta=5019.5,5023.5
Exp/Cntr=0.3,0.1

Type RM Length L Ch R = 1,2346,447,447,447
BEGIN DESCRIPTION:
XS6656
END DESCRIPTION:
XS GIS Cut Line= 3
      2470330.58     13835310.11      2470663.89     13835948.96
      2471076.54     13836510.71
#Sta/Elev= 30
  4306.3  472.15  4388.3  471.18  4416.1  470.25  4581.5  467.45  4609.2  466.47
  4785.9  462.65  4824.5  463.27  4840.9  462.79  4846.5  463.21  4863.0  462.60
  4868.3  462.91  4875.8  462.50  4890.7  463.04  4934.9  463.39  4977.1  459.99
  4977.3  459.49  4980.8  459.49  4981.1  459.99  4988.6  461.39  4995.5  461.84
  5032.5  463.04  5089.0  463.88  5124.5  465.24  5174.7  466.42  5204.0  466.31
  5224.8  467.14  5289.7  468.22  5381.8  470.50  5629.5  473.33  5723.9  473.67
#Mann=6,-1,0
  4306.3    0.05       0  4868.3    0.12       0  4977.1    0.05       0
  4981.1    0.12       0  5032.5    0.07       0  5629.5    0.05       0
Bank Sta=4977.1,4981.1
Exp/Cntr=0.3,0.1

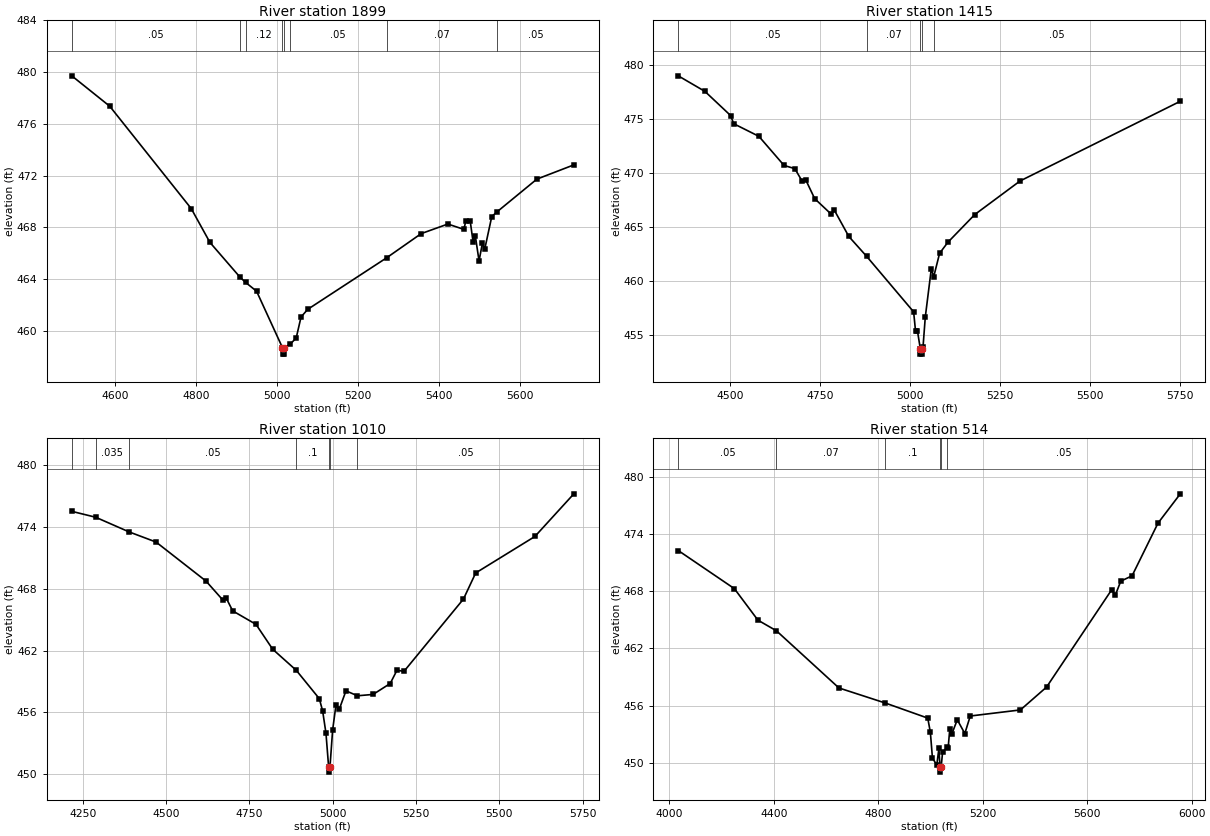
Type RM Length L Ch R = 1,1899,484,484,484
BEGIN DESCRIPTION:
XS6655
END DESCRIPTION:
XS GIS Cut Line= 2
      2470028.48     13835549.68      2470542.34     13836678.08
#Sta/Elev= 30
  4492.5  479.71  4586.3  477.36  4787.6  469.45  4833.7  466.84  4908.4  464.14
  4921.8  463.75  4948.9  463.07  5012.8  458.71  5013.0  458.21  5016.5  458.21
  5016.8  458.71  5031.4  458.97  5046.7  459.45  5058.7  461.08  5075.2  461.67
  5270.0  465.65  5355.4  467.52  5421.3  468.26  5460.6  467.85  5466.1  468.53
  5476.3  468.53  5483.6  466.87  5489.1  467.34  5498.3  465.41  5506.7  466.80
  5512.2  466.30  5529.7  468.84  5543.4  469.22  5641.1  471.73  5732.4  472.83
#Mann=8,-1,0
  4492.5    0.05       0  4908.4    0.07       0  4921.8    0.12       0
  5012.8    0.05       0  5016.8    0.12       0  5031.4    0.05       0
  5270.0    0.07       0  5543.4    0.05       0
Bank Sta=5012.8,5016.8
Exp/Cntr=0.3,0.1

Type RM Length L Ch R = 1,1415,405,405,405
BEGIN DESCRIPTION:
XS6654
END DESCRIPTION:
XS GIS Cut Line= 3
      2469834.03     13835580.92      2469861.81     13836240.63
      2470167.19     13836910.40
#Sta/Elev= 30
  4355.3  479.04  4429.4  477.60  4500.9  475.36  4509.5  474.60  4579.6  473.43
  4649.6  470.73  4679.7  470.43  4699.7  469.28  4709.7  469.41  4734.8  467.65
  4779.8  466.24  4789.8  466.56  4829.8  464.14  4879.0  462.31  5010.0  457.15
  5015.3  455.37  5020.7  455.37  5028.6  453.73  5028.9  453.23  5032.4  453.23
  5032.6  453.73  5036.1  453.88  5042.4  456.66  5059.2  461.15  5065.8  460.40
  5082.2  462.58  5105.2  463.60  5179.9  466.17  5306.1  469.29  5751.7  476.68
#Mann=5,-1,0
  4355.3    0.05       0  4879.0    0.07       0  5028.6    0.05       0
  5032.6    0.07       0  5065.8    0.05       0
Bank Sta=5028.6,5032.6
Exp/Cntr=0.3,0.1

Type RM Length L Ch R = 1,1010,496,496,496
BEGIN DESCRIPTION:
XS6653
END DESCRIPTION:
XS GIS Cut Line= 3
      2469455.56     13835441.98      2469455.56     13836299.65
      2469608.14     13836930.80
#Sta/Elev= 30
  4217.0  475.51  4288.5  474.94  4389.4  473.51  4470.0  472.53  4620.0  468.74
  4670.0  466.92  4680.0  467.13  4700.0  465.85  4770.0  464.54  4820.0  462.13
  4890.9  460.08  4960.0  457.33  4970.0  456.14  4980.0  453.97  4988.0  450.70
  4988.3  450.20  4992.0  450.70  5000.0  454.29  5010.0  456.72  5020.0  456.31
  5040.0  458.09  5074.5  457.61  5121.3  457.74  5172.8  458.80  5193.3  460.10
  5213.9  459.97  5392.7  467.00  5429.4  469.53  5607.1  473.07  5724.0  477.21
#Mann=7,-1,0
  4217.0    0.05       0  4288.5   0.035       0  4389.4    0.05       0
  4890.9     0.1       0  4988.0    0.05       0  4992.0     0.1       0
  5074.5    0.05       0
Bank Sta=4988,4992
Exp/Cntr=0.3,0.1

Type RM Length L Ch R = 1,514,0,0,0
BEGIN DESCRIPTION:
XS6652
END DESCRIPTION:
XS GIS Cut Line= 3
      2469038.89     13835310.09      2469004.17     13836285.76
      2469594.41     13837025.31
#Sta/Elev= 30
  4034.2  472.30  4249.2  468.29  4339.3  464.98  4410.2  463.86  4649.5  457.85
  4826.6  456.27  4989.7  454.68  4999.7  453.17  5007.6  450.48  5024.3  449.75
  5032.3  451.49  5036.7  449.50  5036.9  449.00  5040.7  449.50  5046.7  451.14
  5064.2  451.59  5067.5  451.49  5073.9  453.49  5081.9  453.02  5102.7  454.50
  5131.6  453.06  5152.4  454.90  5344.5  455.54  5444.5  457.94  5693.6  468.16
  5708.0  467.62  5728.8  469.08  5772.0  469.64  5871.3  475.18  5956.7  478.26
#Mann=6,-1,0
  4034.2    0.05       0  4410.2    0.07       0  4826.6     0.1       0
  5036.7    0.05       0  5040.7     0.1       0  5064.2    0.05       0
Bank Sta=5036.7,5040.7
Exp/Cntr=0.3,0.1

Chan Stop Cuts=-1