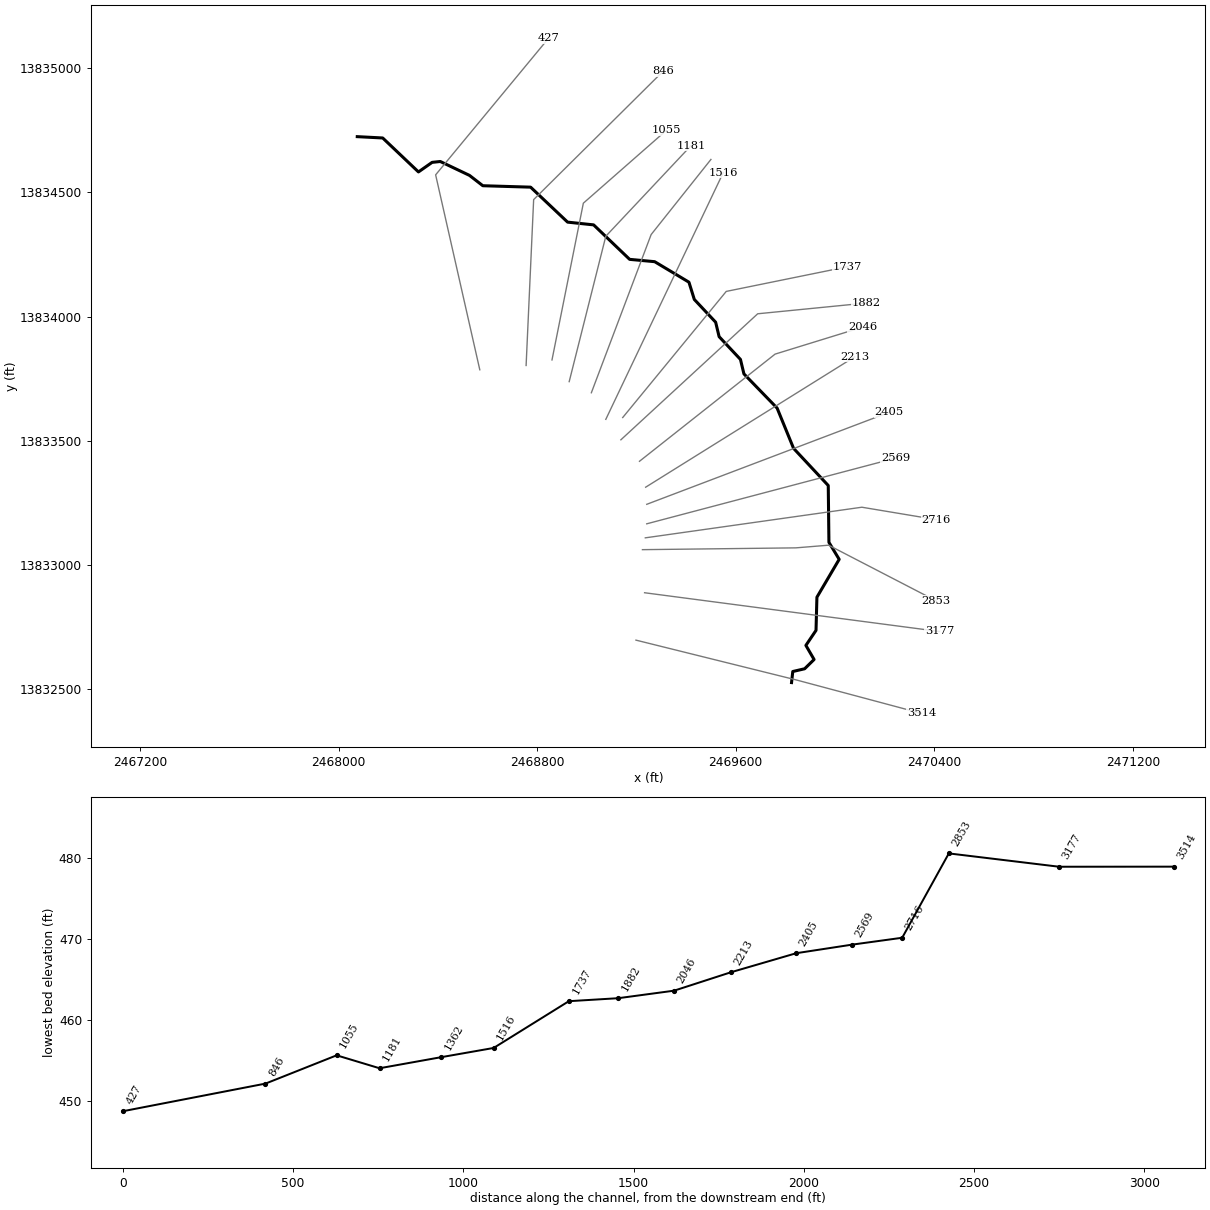
--- Stream0390.prj (project) ---

Proj Title=Stream0390 Base Level Engineering
Current Plan=p01
Default Exp/Contr=0.3,0.1
English Units
Geom File=g01
Flow File=f01
Plan File=p01
BEGIN DESCRIPTION:
Stream0390
END DESCRIPTION:

--- Stream0390.p01 (plan) ---

Plan Title=Multiple Run
Short Identifier=Multiple
Geom File=g01
Flow File=f01
Subcritical Flow
K Sum by GR= 0
Std Step Tol= 0.01
Critical Tol= 0.01
Num of Std Step Trials= 20
Max Error Tol= 0.3
Flow Tol Ratio= 0.001
Split Flow NTrial= 30
Split Flow Tol= 0.02
Split Flow Ratio= 0.02
Log Output Level= 0
Friction Slope Method= 1
Unsteady Friction Slope Method= 2
Unsteady Bridges Friction Slope Method= 1
Parabolic Critical Depth
Global Vel Dist=  1 , 1 , 1
Global Log Level= 0
CheckData=True
Encroach Param= -1, 0, 0, 0
BEGIN DESCRIPTION:
Multiple Run
END DESCRIPTION:

--- Stream0390.f01 (steady flow) ---

Flow Title=Multiple
Number of Profiles=7
Profile Names=10-year,25-year,50-year,1pct_min,100-year,1pct_plu,500-year
River Rch & RM= Stream0390,Reach-1,3514
     255     385     497     311     621    1239     958
Boundary for River Rch & Prof#=Stream0390,Reach-1,1
Up Type=0
Dn Type=3
Dn Slope=0.005
Boundary for River Rch & Prof#=Stream0390,Reach-1,2
Up Type=0
Dn Type=3
Dn Slope=0.005
Boundary for River Rch & Prof#=Stream0390,Reach-1,3
Up Type=0
Dn Type=3
Dn Slope=0.005
Boundary for River Rch & Prof#=Stream0390,Reach-1,4
Up Type=0
Dn Type=3
Dn Slope=0.005
Boundary for River Rch & Prof#=Stream0390,Reach-1,5
Up Type=0
Dn Type=3
Dn Slope=0.005
Boundary for River Rch & Prof#=Stream0390,Reach-1,6
Up Type=0
Dn Type=3
Dn Slope=0.005
Boundary for River Rch & Prof#=Stream0390,Reach-1,7
Up Type=0
Dn Type=3
Dn Slope=0.005

--- Stream0390.g01 (geometry) ---

Geom Title=Existing Conditions

River Reach=Stream0390,Reach-1
Reach XY= 30
      2469825.00     13832525.00      2469830.01     13832569.67
      2469877.76     13832580.71      2469915.84     13832618.06
      2469882.81     13832674.89      2469923.61     13832735.44
      2469927.25     13832869.07      2470016.96     13833021.68
      2469975.66     13833090.16      2469972.94     13833319.15
      2469833.14     13833468.94      2469766.86     13833631.06
      2469633.16     13833768.95      2469619.13     13833827.28
      2469533.18     13833918.96      2469519.13     13833977.28
      2469433.18     13834068.98      2469411.52     13834138.56
      2469273.42     13834221.17      2469172.57     13834230.52
      2469027.43     13834369.48      2468922.57     13834380.52
      2468773.54     13834521.46      2468580.93     13834527.24
      2468527.18     13834568.89      2468409.59     13834624.86
      2468376.63     13834621.38      2468321.59     13834582.82
      2468177.50     13834719.65      2468075.00     13834725.00

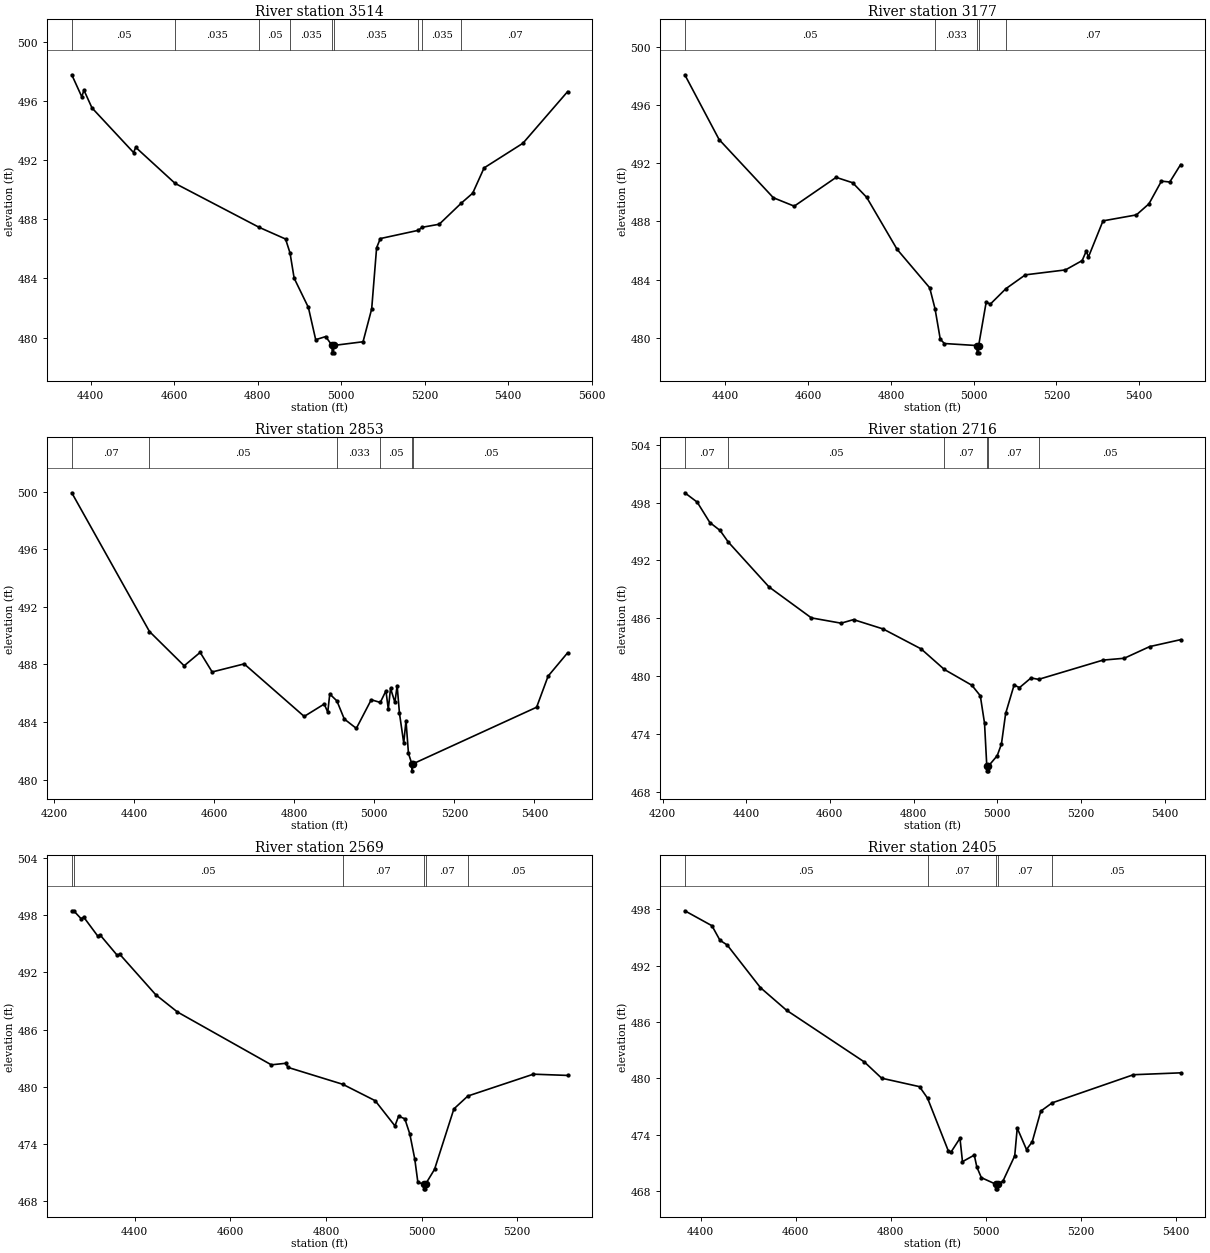
Type RM Length L Ch R = 1,3514,337,337,337
BEGIN DESCRIPTION:
XS6669
END DESCRIPTION:
XS GIS Cut Line= 3
      2469198.06     13832696.10      2469844.79     13832535.50
      2470348.25     13832400.96
#Sta/Elev= 30
  4354.6  497.78  4378.6  496.29  4383.7  496.74  4403.0  495.54  4502.6  492.52
  4507.8  492.87  4602.2  490.43  4803.4  487.46  4866.6  486.67  4877.3  485.73
  4887.2  484.02  4921.3  482.04  4938.8  479.86  4962.7  480.07  4978.0  479.47
  4978.2  478.97  4981.7  478.97  4982.0  479.47  5052.2  479.72  5072.9  481.94
  5084.7  486.08  5093.6  486.70  5184.9  487.26  5193.2  487.46  5234.7  487.67
  5287.6  489.10  5314.8  489.77  5342.1  491.48  5435.2  493.15  5542.1  496.64
#Mann=9,-1,0
  4354.6    0.05       0  4602.2   0.035       0  4803.4    0.05       0
  4877.3   0.035       0  4978.0   0.035       0  4982.0   0.035       0
  5184.9    0.07       0  5193.2   0.035       0  5287.6    0.07       0
Bank Sta=4978,4982
Exp/Cntr=0.3,0.1

Type RM Length L Ch R = 1,3177,324,324,324
BEGIN DESCRIPTION:
XS6668
END DESCRIPTION:
XS GIS Cut Line= 2
      2469232.79     13832887.07      2470420.98     13832730.96
#Sta/Elev= 30
  4301.8  498.07  4384.7  493.62  4515.8  489.62  4566.3  489.04  4667.6  491.02
  4707.5  490.65  4741.3  489.65  4815.0  486.07  4893.7  483.43  4906.6  481.99
  4919.3  479.89  4929.4  479.60  5008.0  479.46  5008.3  478.96  5011.8  478.96
  5012.0  479.46  5030.2  482.44  5040.3  482.31  5077.9  483.37  5124.9  484.32
  5221.9  484.66  5262.2  485.30  5272.2  485.96  5277.3  485.54  5312.6  488.03
  5393.3  488.44  5423.6  489.20  5453.8  490.76  5474.0  490.70  5500.2  491.90
#Mann=5,-1,0
  4301.8    0.05       0  4906.6   0.033       0  5008.0   0.033       0
  5012.0   0.033       0  5077.9    0.07       0
Bank Sta=5008,5012
Exp/Cntr=0.3,0.1

Type RM Length L Ch R = 1,2853,137,137,137
BEGIN DESCRIPTION:
XS6670
END DESCRIPTION:
XS GIS Cut Line= 4
      2469224.15     13833060.68      2469842.59     13833067.95
      2469974.32     13833078.69      2470408.21     13832854.14
#Sta/Elev= 30
  4243.9  499.93  4438.1  490.29  4524.8  487.91  4564.8  488.84  4594.8  487.48
  4674.8  488.04  4824.8  484.39  4874.8  485.25  4883.7  484.69  4888.7  485.95
  4906.5  485.47  4925.0  484.21  4955.1  483.56  4992.4  485.55  5015.0  485.36
  5029.1  486.17  5035.0  484.90  5040.6  486.34  5051.5  485.37  5057.1  486.53
  5062.9  484.61  5073.6  482.54  5079.2  484.10  5085.4  481.82  5093.7  481.11
  5094.0  480.61  5097.7  481.11  5405.7  485.03  5434.4  487.19  5483.1  488.81
#Mann=6,-1,0
  4243.9    0.07       0  4438.1    0.05       0  4906.5   0.033       0
  5015.0    0.05       0  5093.7   0.033       0  5097.7    0.05       0
Bank Sta=5093.7,5097.7
Exp/Cntr=0.3,0.1

Type RM Length L Ch R = 1,2716,147,147,147
BEGIN DESCRIPTION:
E20960
END DESCRIPTION:
XS GIS Cut Line= 3
      2469235.70     13833108.31      2470108.30     13833231.71
      2470407.99     13833181.76
#Sta/Elev= 30
  4253.3  499.02  4282.9  498.05  4313.2  495.93  4337.6  495.11  4357.0  493.92
  4454.6  489.25  4555.8  486.04  4626.9  485.49  4656.6  485.86  4727.3  484.89
  4818.2  482.82  4873.6  480.69  4939.4  479.05  4959.6  477.96  4969.7  475.11
  4975.1  470.67  4975.4  470.17  4978.9  470.17  4979.1  470.67  5000.0  471.74
  5010.1  472.95  5020.2  476.13  5040.4  479.08  5053.2  478.80  5080.8  479.81
  5098.8  479.66  5252.9  481.66  5303.6  481.85  5364.4  483.06  5438.4  483.78
#Mann=6,-1,0
  4253.3    0.07       0  4357.0    0.05       0  4873.6    0.07       0
  4975.1    0.05       0  4979.1    0.07       0  5098.8    0.05       0
Bank Sta=4975.1,4979.1
Exp/Cntr=0.3,0.1

Type RM Length L Ch R = 1,2569,164,164,164
BEGIN DESCRIPTION:
XS6667
END DESCRIPTION:
XS GIS Cut Line= 2
      2469241.46     13833164.83      2470244.09     13833429.60
#Sta/Elev= 30
  4268.2  498.47  4272.2  498.47  4287.9  497.63  4293.1  497.81  4323.0  495.79
  4328.2  495.89  4363.3  493.80  4368.4  493.92  4443.8  489.67  4489.2  487.86
  4685.6  482.32  4715.4  482.48  4720.5  482.05  4835.0  480.28  4902.8  478.56
  4944.1  475.92  4951.8  476.94  4964.8  476.66  4975.2  475.07  4985.5  472.47
  4992.1  469.99  5004.2  469.82  5004.5  469.32  5008.0  469.32  5008.2  469.82
  5026.9  471.36  5067.4  477.70  5096.6  479.05  5233.7  481.34  5305.2  481.21
#Mann=6,-1,0
  4268.2    0.07       0  4272.2    0.05       0  4835.0    0.07       0
  5004.2    0.05       0  5008.2    0.07       0  5096.6    0.05       0
Bank Sta=5004.2,5008.2
Exp/Cntr=0.3,0.1

Type RM Length L Ch R = 1,2405,192,192,192
BEGIN DESCRIPTION:
E20955
END DESCRIPTION:
XS GIS Cut Line= 2
      2469241.61     13833243.46      2470217.02     13833613.65
#Sta/Elev= 30
  4366.7  497.84  4423.8  496.25  4440.7  494.70  4455.9  494.20  4525.7  489.67
  4580.7  487.26  4744.7  481.75  4780.9  480.03  4860.6  479.13  4877.4  477.91
  4920.9  472.33  4926.5  472.14  4945.7  473.64  4951.0  471.15  4975.8  471.85
  4981.2  470.58  4990.7  469.45  5020.8  468.76  5021.0  468.26  5024.5  468.26
  5024.8  468.76  5036.1  469.08  5060.9  471.77  5066.2  474.72  5085.7  472.44
  5097.7  473.26  5115.8  476.53  5139.8  477.41  5310.7  480.40  5410.0  480.60
#Mann=5,-1,0
  4366.7    0.05       0  4877.4    0.07       0  5020.8    0.05       0
  5024.8    0.07       0  5139.8    0.05       0
Bank Sta=5020.8,5024.8
Exp/Cntr=0.3,0.1

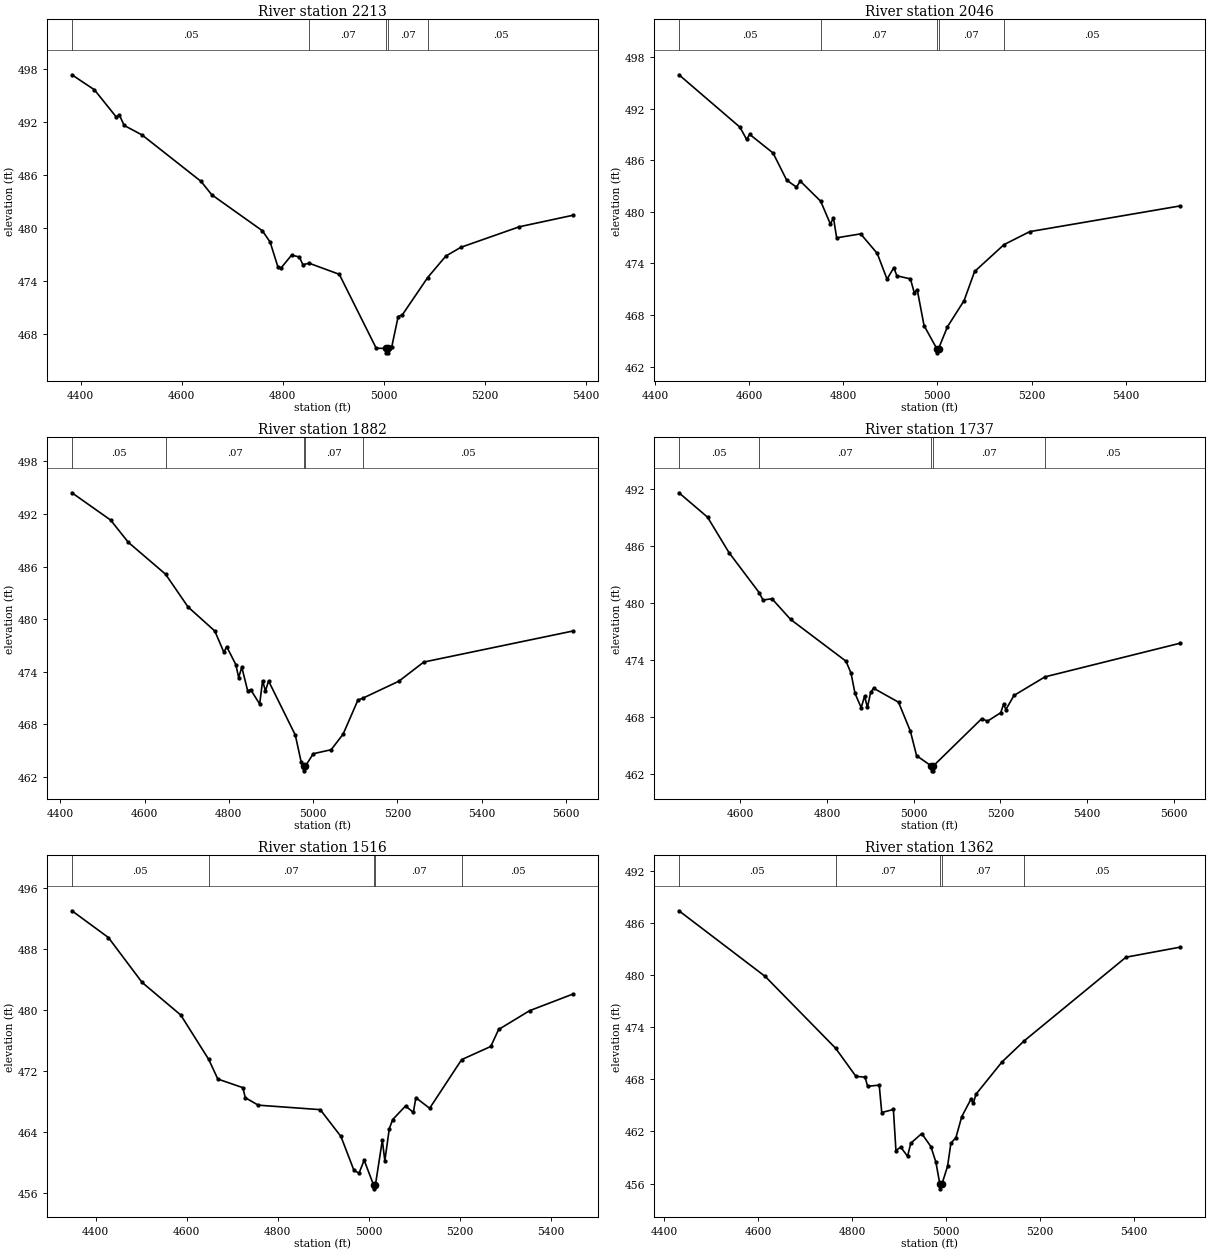
Type RM Length L Ch R = 1,2213,167,167,167
BEGIN DESCRIPTION:
XS6666
END DESCRIPTION:
XS GIS Cut Line= 2
      2469237.12     13833312.39      2470079.16     13833837.58
#Sta/Elev= 30
  4382.9  497.31  4427.5  495.61  4470.8  492.53  4476.7  492.79  4486.2  491.59
  4521.8  490.51  4638.4  485.27  4659.6  483.76  4759.9  479.69  4775.2  478.41
  4790.6  475.61  4796.4  475.46  4817.7  476.94  4833.0  476.73  4840.0  475.86
  4852.6  476.02  4912.1  474.77  4985.2  466.42  5004.4  466.40  5004.7  465.90
  5008.2  465.90  5008.4  466.40  5015.9  466.57  5028.6  469.99  5037.1  470.21
  5087.1  474.41  5122.9  476.83  5152.7  477.82  5268.4  480.14  5375.3  481.45
#Mann=5,-1,0
  4382.9    0.05       0  4852.6    0.07       0  5004.4    0.05       0
  5008.4    0.07       0  5087.1    0.05       0
Bank Sta=5004.4,5008.4
Exp/Cntr=0.3,0.1

Type RM Length L Ch R = 1,2046,164,164,164
BEGIN DESCRIPTION:
E20956
END DESCRIPTION:
XS GIS Cut Line= 3
      2469212.24     13833416.81      2469758.69     13833848.68
      2470110.63     13833957.20
#Sta/Elev= 30
  4451.2  495.92  4580.6  489.84  4594.9  488.41  4601.4  489.00  4651.1  486.83
  4680.0  483.68  4700.8  482.87  4708.8  483.57  4752.2  481.23  4772.9  478.57
  4779.3  479.32  4786.1  476.98  4837.1  477.44  4872.3  475.17  4893.1  472.18
  4907.6  473.52  4913.9  472.57  4942.8  472.21  4950.9  470.60  4957.2  470.96
  4971.7  466.79  4998.6  464.12  4998.8  463.62  5002.6  464.12  5021.4  466.65
  5056.6  469.67  5079.1  473.07  5141.5  476.19  5196.2  477.70  5516.0  480.69
#Mann=5,-1,0
  4451.2    0.05       0  4752.2    0.07       0  4998.6    0.05       0
  5002.6    0.07       0  5141.5    0.05       0
Bank Sta=4998.6,5002.6
Exp/Cntr=0.3,0.1

Type RM Length L Ch R = 1,1882,145,145,145
BEGIN DESCRIPTION:
XS6665
END DESCRIPTION:
XS GIS Cut Line= 3
      2469137.29     13833503.35      2469688.54     13834011.20
      2470126.88     13834054.60
#Sta/Elev= 30
  4427.5  494.41  4519.3  491.30  4561.3  488.76  4649.8  485.12  4703.0  481.39
  4766.6  478.64  4788.1  476.22  4794.9  476.85  4816.5  474.81  4823.3  473.32
  4830.6  474.53  4844.8  471.78  4851.6  471.96  4873.1  470.31  4880.0  472.97
  4886.8  471.80  4894.2  472.94  4957.7  466.77  4971.8  463.65  4977.2  463.19
  4977.5  462.69  4981.2  463.19  5000.2  464.64  5042.7  465.10  5071.1  466.87
  5106.2  470.75  5119.3  471.01  5203.6  472.92  5262.6  475.10  5617.5  478.65
#Mann=5,-1,0
  4427.5    0.05       0  4649.8    0.07       0  4977.2    0.05       0
  4981.2    0.07       0  5119.3    0.05       0
Bank Sta=4977.2,4981.2
Exp/Cntr=0.3,0.1

Type RM Length L Ch R = 1,1737,221,221,221
BEGIN DESCRIPTION:
E20957
END DESCRIPTION:
XS GIS Cut Line= 3
      2469144.69     13833593.12      2469561.85     13834101.35
      2470051.20     13834200.97
#Sta/Elev= 30
  4458.2  491.61  4524.2  489.04  4573.8  485.30  4643.5  481.08  4652.0  480.31
  4672.8  480.45  4715.8  478.27  4843.6  473.87  4855.2  472.62  4864.4  470.48
  4878.7  468.97  4886.6  470.19  4893.1  469.00  4900.5  470.59  4907.4  471.02
  4964.8  469.55  4992.1  466.51  5006.5  463.92  5040.8  462.82  5041.1  462.32
  5044.6  462.32  5044.8  462.82  5156.9  467.82  5170.0  467.55  5200.6  468.44
  5207.4  469.36  5212.5  468.77  5231.2  470.26  5302.8  472.22  5615.1  475.77
#Mann=5,-1,0
  4458.2    0.05       0  4643.5    0.07       0  5040.8    0.05       0
  5044.8    0.07       0  5302.8    0.05       0
Bank Sta=5040.8,5044.8
Exp/Cntr=0.3,0.1

Type RM Length L Ch R = 1,1516,154,154,154
BEGIN DESCRIPTION:
XS6664
END DESCRIPTION:
XS GIS Cut Line= 2
      2469076.55     13833585.83      2469549.66     13834579.78
#Sta/Elev= 30
  4348.0  493.05  4428.0  489.54  4502.1  483.64  4586.9  479.36  4648.4  473.52
  4668.3  470.95  4723.2  469.82  4728.7  468.50  4757.0  467.52  4893.2  466.93
  4938.6  463.41  4967.3  458.94  4978.4  458.60  4989.6  460.29  5010.3  457.03
  5010.6  456.53  5014.3  457.03  5029.5  462.91  5035.0  460.21  5044.8  464.43
  5052.2  465.63  5080.4  467.41  5097.6  466.57  5103.1  468.50  5133.4  467.11
  5203.6  473.50  5267.6  475.23  5284.8  477.46  5352.9  479.93  5448.8  482.13
#Mann=5,-1,0
  4348.0    0.05       0  4648.4    0.07       0  5010.3    0.05       0
  5014.3    0.07       0  5203.6    0.05       0
Bank Sta=5010.3,5014.3
Exp/Cntr=0.3,0.1

Type RM Length L Ch R = 1,1362,181,181,181
BEGIN DESCRIPTION:
E20958
END DESCRIPTION:
XS GIS Cut Line= 3
      2469018.33     13833692.99      2469259.24     13834330.51
      2469500.14     13834633.11
#Sta/Elev= 30
  4431.4  487.38  4615.3  479.82  4765.1  471.57  4808.5  468.33  4828.0  468.24
  4833.3  467.19  4858.1  467.32  4863.5  464.17  4888.3  464.52  4893.7  459.80
  4903.9  460.19  4918.5  459.13  4925.3  460.64  4948.7  461.75  4968.1  460.26
  4978.9  458.45  4987.4  455.89  4987.7  455.39  4991.4  455.89  5003.7  457.98
  5010.8  460.64  5021.5  461.28  5033.9  463.69  5053.4  465.69  5058.7  465.26
  5064.3  466.28  5119.6  469.98  5167.1  472.42  5383.9  482.04  5499.7  483.20
#Mann=5,-1,0
  4431.4    0.05       0  4765.1    0.07       0  4987.4    0.05       0
  4991.4    0.07       0  5167.1    0.05       0
Bank Sta=4987.4,4991.4
Exp/Cntr=0.3,0.1

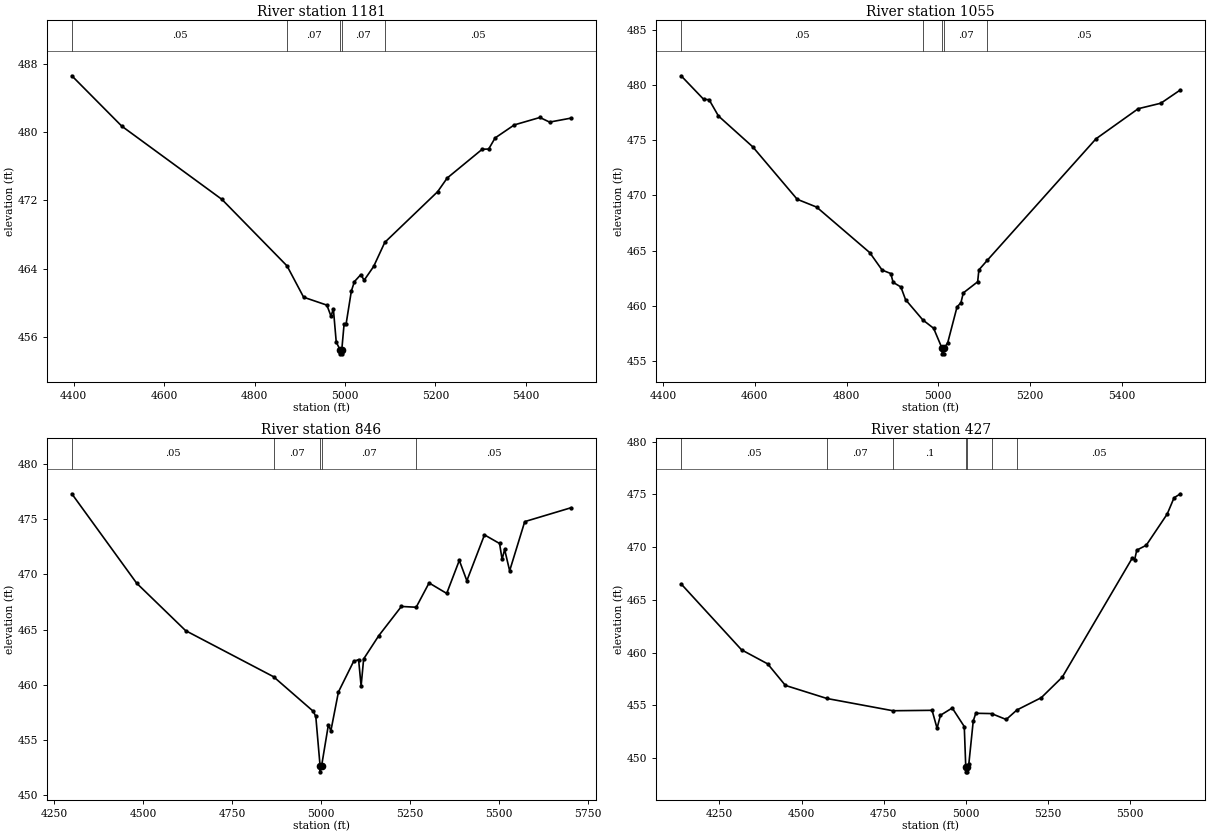
Type RM Length L Ch R = 1,1181,126,126,126
BEGIN DESCRIPTION:
XS6663
END DESCRIPTION:
XS GIS Cut Line= 3
      2468928.99     13833737.76      2469076.56     13834323.70
      2469419.43     13834688.26
#Sta/Elev= 30
  4395.7  486.62  4506.3  480.71  4727.7  472.13  4871.8  464.33  4908.5  460.66
  4960.0  459.73  4969.1  458.43  4974.3  459.30  4980.7  455.39  4989.0  454.52
  4989.2  454.02  4992.7  454.02  4993.0  454.52  4998.0  457.49  5002.4  457.49
  5014.1  461.38  5020.9  462.49  5035.1  463.31  5042.4  462.65  5063.4  464.26
  5088.1  467.09  5205.0  473.03  5226.1  474.63  5303.7  478.01  5317.9  478.03
  5332.1  479.33  5374.6  480.86  5431.2  481.73  5452.7  481.19  5500.4  481.66
#Mann=5,-1,0
  4395.7    0.05       0  4871.8    0.07       0  4989.0    0.05       0
  4993.0    0.07       0  5088.1    0.05       0
Bank Sta=4989,4993
Exp/Cntr=0.3,0.1

Type RM Length L Ch R = 1,1055,209,209,209
BEGIN DESCRIPTION:
E20959
END DESCRIPTION:
XS GIS Cut Line= 3
      2468859.68     13833825.20      2468986.01     13834456.84
      2469320.12     13834749.92
#Sta/Elev= 30
  4439.4  480.86  4488.6  478.72  4500.4  478.69  4520.8  477.21  4595.6  474.41
  4692.5  469.65  4734.9  468.94  4850.6  464.81  4877.7  463.22  4896.5  462.91
  4901.6  462.11  4918.5  461.69  4928.7  460.54  4966.3  458.70  4989.9  457.94
  5008.3  456.12  5008.5  455.62  5012.0  455.62  5012.3  456.12  5020.5  456.61
  5040.9  459.87  5049.5  460.27  5054.6  461.15  5085.9  462.16  5088.6  463.24
  5107.3  464.13  5343.9  475.14  5435.9  477.87  5485.3  478.37  5528.0  479.58
#Mann=5,-1,0
  4439.4    0.05       0  4966.3    0.07       0  5008.3    0.05       0
  5012.3    0.07       0  5107.3    0.05       0
Bank Sta=5008.3,5012.3
Exp/Cntr=0.3,0.1

Type RM Length L Ch R = 1,846,419,419,419
BEGIN DESCRIPTION:
XS6662
END DESCRIPTION:
XS GIS Cut Line= 3
      2468755.38     13833802.90      2468785.76     13834471.27
      2469306.63     13834987.79
#Sta/Elev= 30
  4300.1  477.29  4482.4  469.19  4619.8  464.90  4866.7  460.73  4978.3  457.60
  4985.4  457.13  4997.5  452.62  4997.8  452.12  5001.5  452.62  5020.8  456.38
  5027.8  455.84  5049.0  459.35  5091.5  462.11  5105.6  462.28  5112.7  459.89
  5119.8  462.34  5162.2  464.44  5225.8  467.09  5267.4  467.02  5303.6  469.22
  5353.1  468.27  5388.5  471.26  5409.7  469.42  5459.2  473.57  5501.6  472.79
  5508.7  471.36  5515.8  472.25  5529.9  470.32  5572.3  474.77  5702.7  476.03
#Mann=5,-1,0
  4300.1    0.05       0  4866.7    0.07       0  4997.5    0.05       0
  5001.5    0.07       0  5267.4    0.05       0
Bank Sta=4997.5,5001.5
Exp/Cntr=0.3,0.1

Type RM Length L Ch R = 1,427,0,0,0
BEGIN DESCRIPTION:
XS6661
END DESCRIPTION:
XS GIS Cut Line= 3
      2468568.74     13833785.53      2468390.80     13834571.09
      2468845.59     13835121.17
#Sta/Elev= 30
  4133.6  466.51  4317.6  460.26  4397.0  458.93  4450.9  456.89  4577.4  455.65
  4777.9  454.49  4897.2  454.53  4912.3  452.83  4922.6  454.06  4958.5  454.75
  4995.1  452.99  4999.6  449.20  4999.8  448.70  5003.3  448.70  5003.6  449.20
  5009.0  449.45  5022.4  453.52  5030.2  454.25  5078.0  454.22  5122.7  453.66
  5155.2  454.56  5229.5  455.73  5293.4  457.68  5505.7  468.93  5513.5  468.82
  5520.0  469.71  5548.7  470.17  5612.5  473.13  5633.3  474.67  5652.8  475.05
#Mann=7,-1,0
  4133.6    0.05       0  4577.4    0.07       0  4777.9     0.1       0
  4999.6    0.05       0  5003.6     0.1       0  5078.0    0.07       0
  5155.2    0.05       0
Bank Sta=4999.6,5003.6
Exp/Cntr=0.3,0.1

Chan Stop Cuts=-1