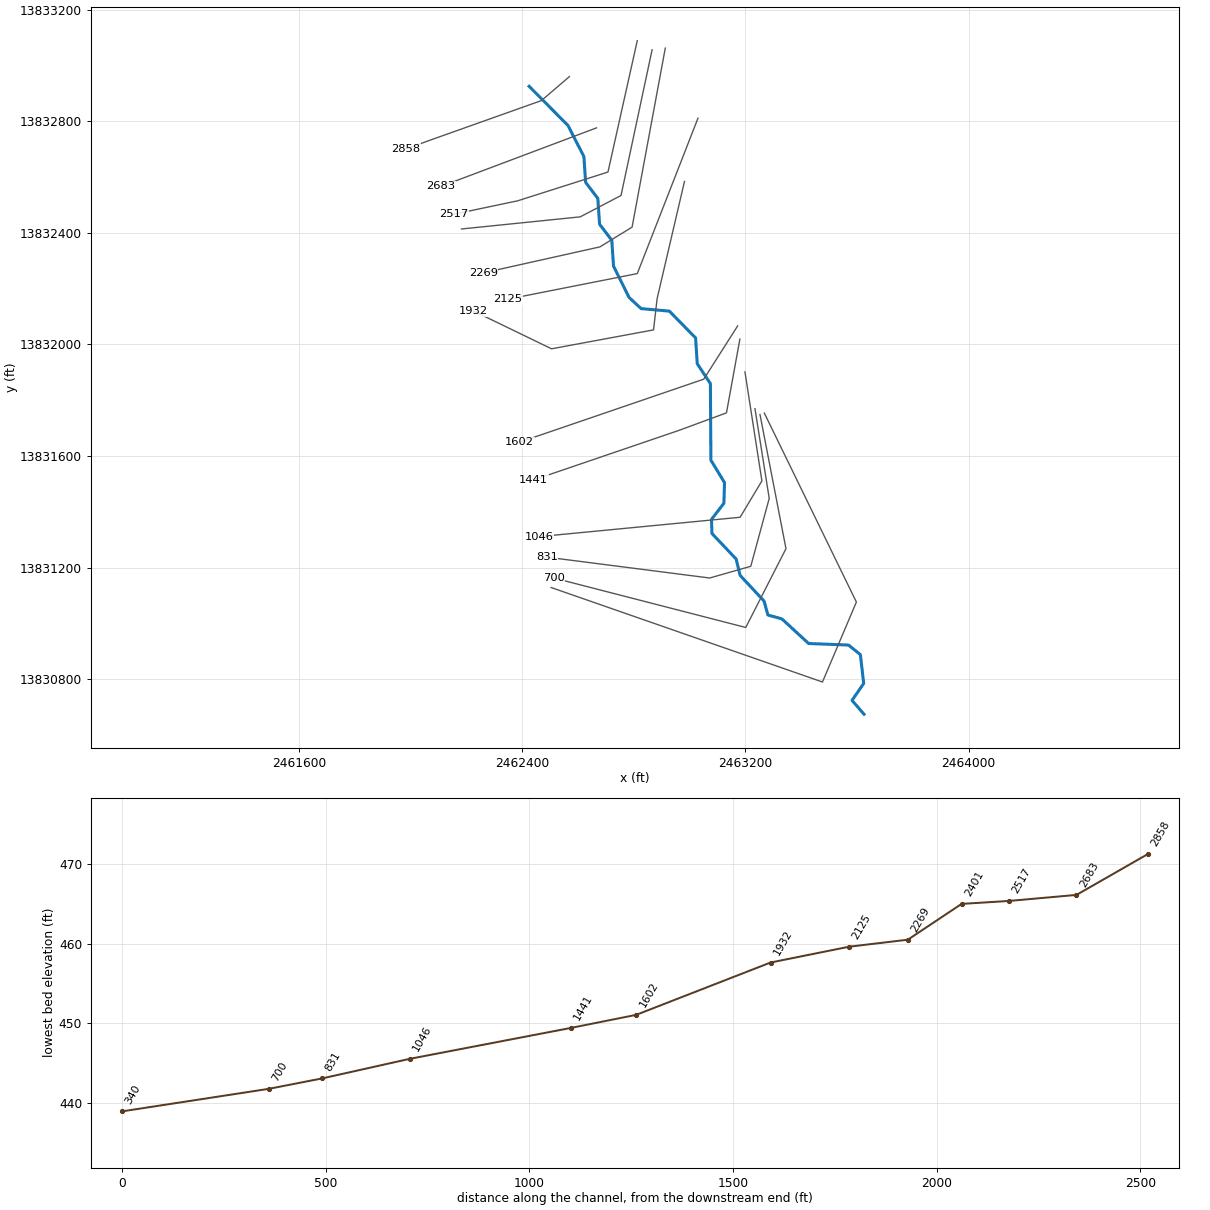
--- Stream0394.prj (project) ---

Proj Title=Stream0394 Base Level Engineering
Current Plan=p01
Default Exp/Contr=0.3,0.1
English Units
Geom File=g01
Flow File=f01
Plan File=p01
Y Axis Title=Elevation
X Axis Title(PF)=Main Channel Distance
X Axis Title(XS)=Station
BEGIN DESCRIPTION:
Stream0394
END DESCRIPTION:
DSS Export Rating Curves= 0
DSS Export Rating Curve Sorted= 0
DSS Export Volume Flow Curves= 0
DXF OffsetX= 0
DXF OffsetY= 0
DXF ScaleX= 1
DXF ScaleY= 10

--- Stream0394.p01 (plan) ---

Plan Title=Multiple Run
Short Identifier=Multiple
Geom File=g01
Flow File=f01
Subcritical Flow
K Sum by GR= 0
Std Step Tol= 0.01
Critical Tol= 0.01
Num of Std Step Trials= 20
Max Error Tol= 0.3
Flow Tol Ratio= 0.001
Split Flow NTrial= 30
Split Flow Tol= 0.02
Split Flow Ratio= 0.02
Log Output Level= 0
Friction Slope Method= 1
Unsteady Friction Slope Method= 2
Unsteady Bridges Friction Slope Method= 1
Parabolic Critical Depth
Global Vel Dist=  1 , 1 , 1
Global Log Level= 0
CheckData=True
Encroach Param= -1, 0, 0, 0
BEGIN DESCRIPTION:
Multiple Run
END DESCRIPTION:

--- Stream0394.f01 (steady flow) ---

Flow Title=Multiple
Number of Profiles=7
Profile Names=10-year,25-year,50-year,1pct_min,100-year,1pct_plu,500-year
River Rch & RM= Stream0394,Reach-1,2858
     210     314     402     251     501     999     765
Boundary for River Rch & Prof#=Stream0394,Reach-1,1
Up Type=0
Dn Type=3
Dn Slope=0.005
Boundary for River Rch & Prof#=Stream0394,Reach-1,2
Up Type=0
Dn Type=3
Dn Slope=0.005
Boundary for River Rch & Prof#=Stream0394,Reach-1,3
Up Type=0
Dn Type=3
Dn Slope=0.005
Boundary for River Rch & Prof#=Stream0394,Reach-1,4
Up Type=0
Dn Type=3
Dn Slope=0.005
Boundary for River Rch & Prof#=Stream0394,Reach-1,5
Up Type=0
Dn Type=3
Dn Slope=0.005
Boundary for River Rch & Prof#=Stream0394,Reach-1,6
Up Type=0
Dn Type=3
Dn Slope=0.005
Boundary for River Rch & Prof#=Stream0394,Reach-1,7
Up Type=0
Dn Type=3
Dn Slope=0.005

--- Stream0394.g01 (geometry) ---

Geom Title=Existing Conditions

River Reach=Stream0394,Reach-1
Reach XY= 30
      2462425.00     13832925.00      2462564.24     13832784.69
      2462621.18     13832673.42      2462627.35     13832580.97
      2462671.15     13832523.40      2462677.35     13832430.97
      2462721.15     13832373.40      2462727.33     13832280.96
      2462783.00     13832168.62      2462826.28     13832128.53
      2462927.44     13832119.48      2463021.39     13832023.52
      2463027.36     13831930.98      2463074.48     13831859.78
      2463076.22     13831585.50      2463125.09     13831504.90
      2463122.81     13831430.97      2463078.34     13831373.25
      2463080.10     13831322.71      2463166.82     13831231.04
      2463180.87     13831172.72      2463266.70     13831080.74
      2463280.62     13831030.62      2463330.74     13831016.70
      2463426.47     13830928.55      2463569.35     13830923.02
      2463611.84     13830888.73      2463623.81     13830785.48
      2463581.91     13830724.86      2463625.00     13830675.00

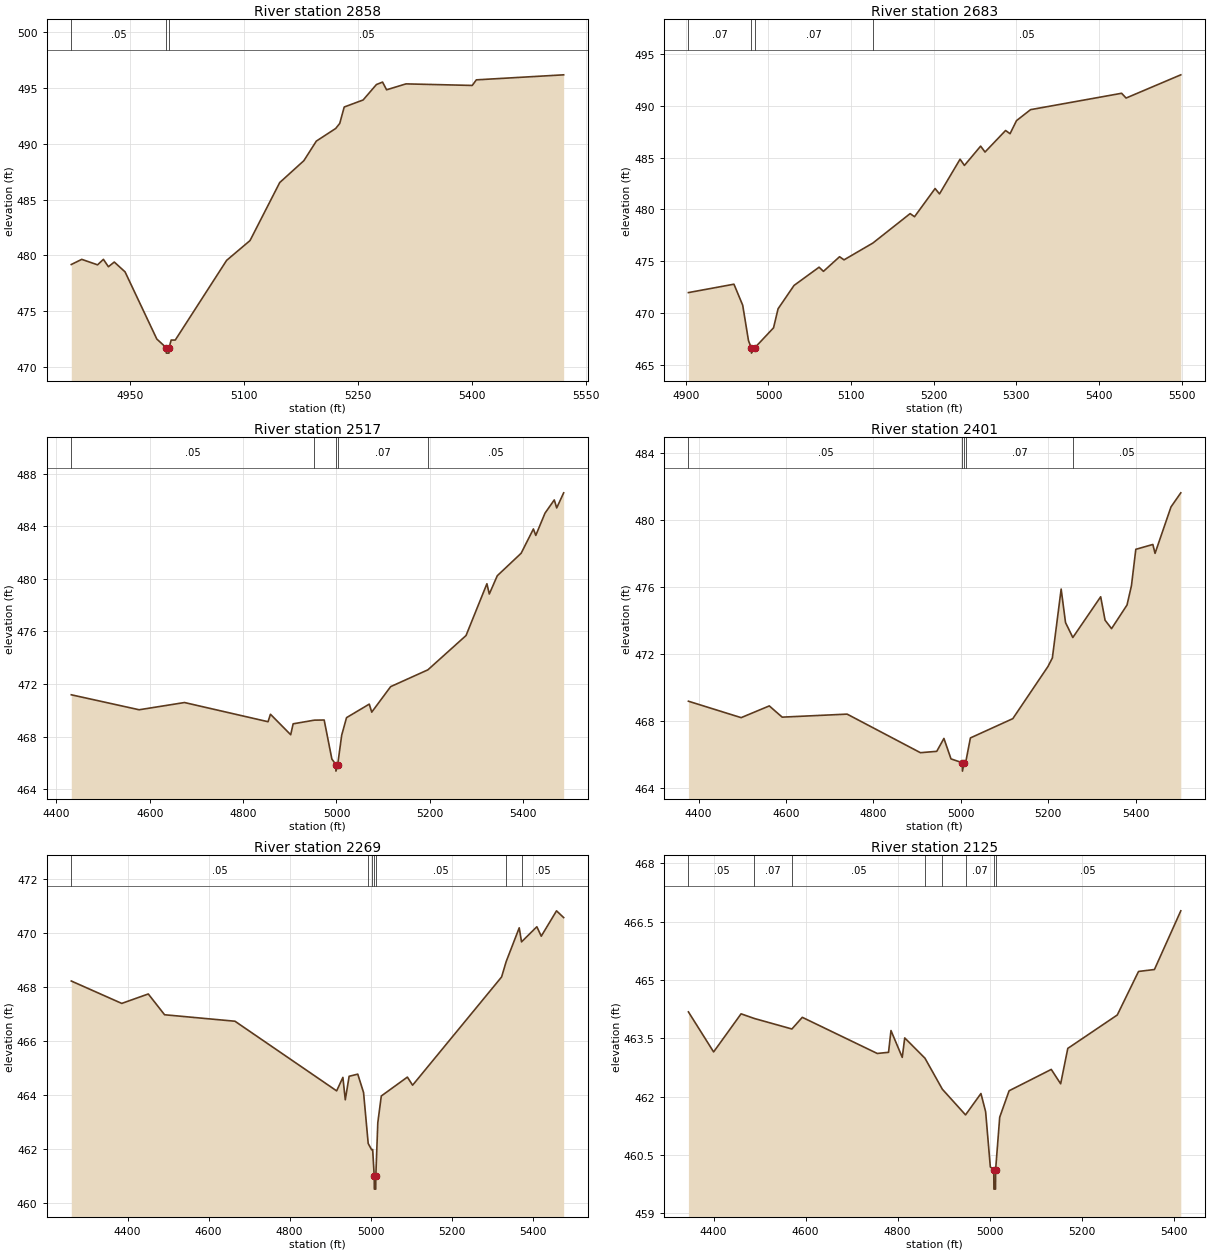
Type RM Length L Ch R = 1,2858,175,175,175
BEGIN DESCRIPTION:
XS6683
END DESCRIPTION:
XS GIS Cut Line= 4
      2462569.37     13832959.90      2462469.10     13832873.96
      2462078.47     13832735.07      2461983.03     13832700.36
#Sta/Elev= 30
  4872.9  479.19  4886.7  479.65  4907.5  479.16  4915.2  479.65  4921.8  478.99
  4929.5  479.41  4943.7  478.53  4985.5  472.52  4997.7  471.76  4998.0  471.26
  5001.5  471.26  5001.7  471.76  5004.4  472.43  5009.8  472.43  5077.4  479.56
  5108.2  481.33  5147.3  486.52  5179.1  488.48  5195.5  490.23  5221.0  491.36
  5226.3  491.81  5232.2  493.28  5257.1  493.91  5274.6  495.29  5282.7  495.51
  5288.0  494.82  5313.5  495.35  5400.8  495.21  5406.1  495.71  5521.1  496.16
#Mann=3,-1,0
  4872.9    0.05       0  4997.7    0.05       0  5001.7    0.05       0
Bank Sta=4997.7,5001.7
Exp/Cntr=0.3,0.1

Type RM Length L Ch R = 1,2683,166,166,166
BEGIN DESCRIPTION:
E20973
END DESCRIPTION:
XS GIS Cut Line= 2
      2462666.53     13832776.20      2462108.91     13832566.34
#Sta/Elev= 30
  4903.1  471.97  4958.2  472.78  4968.8  470.75  4975.8  467.33  4979.2  466.63
  4979.4  466.13  4983.2  466.63  5006.1  468.57  5011.6  470.41  5030.9  472.66
  5061.2  474.42  5066.5  474.02  5086.0  475.43  5091.4  475.13  5126.3  476.75
  5171.4  479.59  5176.7  479.29  5201.6  482.01  5206.9  481.49  5231.8  484.84
  5237.1  484.24  5256.7  486.10  5262.0  485.53  5286.9  487.61  5292.3  487.30
  5300.1  488.56  5317.1  489.62  5427.3  491.20  5432.7  490.74  5498.9  492.98
#Mann=4,-1,0
  4903.1    0.07       0  4979.2    0.05       0  4983.2    0.07       0
  5126.3    0.05       0
Bank Sta=4979.2,4983.2
Exp/Cntr=0.3,0.1

Type RM Length L Ch R = 1,2517,116,116,116
BEGIN DESCRIPTION:
E20972
END DESCRIPTION:
XS GIS Cut Line= 4
      2462812.42     13833088.43      2462707.43     13832617.86
      2462384.15     13832514.87      2462155.89     13832466.81
#Sta/Elev= 30
  4431.9  471.18  4577.3  470.04  4674.4  470.59  4853.4  469.13  4858.5  469.70
  4901.9  468.14  4907.1  468.97  4952.7  469.25  4973.6  469.26  4990.1  466.29
  4998.6  465.87  4998.8  465.37  5002.6  465.87  5011.1  468.10  5021.5  469.44
  5070.2  470.47  5075.5  469.86  5116.0  471.80  5195.8  473.08  5277.5  475.69
  5322.2  479.63  5327.3  478.85  5344.4  480.24  5395.5  481.95  5421.8  483.80
  5426.9  483.31  5446.6  485.00  5466.5  486.01  5471.7  485.40  5486.6  486.55
#Mann=5,-1,0
  4431.9    0.05       0  4952.7    0.07       0  4998.6    0.05       0
  5002.6    0.07       0  5195.8    0.05       0
Bank Sta=4998.6,5002.6
Exp/Cntr=0.3,0.1

Type RM Length L Ch R = 1,2401,132,132,132
BEGIN DESCRIPTION:
XS6682
END DESCRIPTION:
XS GIS Cut Line= 4
      2462865.58     13833055.93      2462754.25     13832533.91
      2462607.99     13832457.29      2462182.67     13832413.89
#Sta/Elev= 30
  4376.9  469.17  4497.5  468.19  4561.9  468.89  4591.4  468.22  4740.0  468.40
  4907.6  466.10  4945.0  466.18  4961.4  466.95  4977.6  465.73  5003.5  465.50
  5003.8  465.00  5007.5  465.50  5012.0  465.63  5022.0  466.98  5119.0  468.13
  5199.4  471.24  5209.5  471.75  5229.6  475.86  5239.6  473.86  5256.3  472.97
  5320.0  475.40  5330.1  474.00  5344.9  473.50  5380.3  474.91  5390.4  476.06
  5400.4  478.23  5439.4  478.52  5444.4  477.99  5480.9  480.76  5503.3  481.60
#Mann=5,-1,0
  4376.9    0.05       0  5003.5    0.05       0  5007.5    0.05       0
  5012.0    0.07       0  5256.3    0.05       0
Bank Sta=5003.5,5007.5
Exp/Cntr=0.3,0.1

Type RM Length L Ch R = 1,2269,144,144,144
BEGIN DESCRIPTION:
E20971
END DESCRIPTION:
XS GIS Cut Line= 4
      2462912.84     13833061.90      2462793.89     13832420.47
      2462678.50     13832349.67      2462261.00     13832256.55
#Sta/Elev= 30
  4261.2  468.21  4385.8  467.38  4451.3  467.73  4491.5  466.96  4665.3  466.72
  4916.3  464.14  4931.7  464.64  4937.6  463.81  4947.1  464.68  4968.4  464.76
  4982.7  464.08  4994.2  462.19  5002.6  461.96  5005.2  461.97  5009.0  461.00
  5009.3  460.50  5012.8  460.50  5013.0  461.00  5017.9  462.96  5026.5  463.95
  5090.9  464.65  5103.8  464.35  5323.5  468.36  5334.8  468.93  5367.0  470.18
  5372.7  469.66  5410.5  470.22  5421.4  469.87  5459.1  470.81  5476.7  470.56
#Mann=7,-1,0
  4261.2    0.05       0  4994.2    0.07       0  5002.6    0.05       0
  5009.0    0.05       0  5013.0    0.05       0  5334.8    0.07       0
  5372.7    0.05       0
Bank Sta=5009,5013
Exp/Cntr=0.3,0.1

Type RM Length L Ch R = 1,2125,193,193,193
BEGIN DESCRIPTION:
XS6681
END DESCRIPTION:
XS GIS Cut Line= 3
      2463029.97     13832810.89      2462812.52     13832254.06
      2462348.77     13832162.39
#Sta/Elev= 30
  4345.1  464.18  4399.9  463.15  4459.6  464.13  4488.5  464.01  4570.1  463.74
  4592.7  464.04  4755.7  463.11  4780.2  463.14  4785.5  463.70  4810.0  463.01
  4815.4  463.51  4859.3  462.99  4897.2  462.19  4947.6  461.53  4981.1  462.08
  4991.3  461.61  5001.5  460.19  5009.0  460.12  5009.3  459.62  5012.8  459.62
  5013.0  460.12  5021.9  461.47  5042.3  462.15  5134.0  462.70  5154.4  462.33
  5169.9  463.24  5277.5  464.10  5323.7  465.22  5358.3  465.27  5415.6  466.78
#Mann=8,-1,0
  4345.1    0.05       0  4488.5    0.07       0  4570.1    0.05       0
  4859.3    0.07       0  4897.2    0.05       0  4947.6    0.07       0
  5009.0    0.05       0  5013.0    0.05       0
Bank Sta=5009,5013
Exp/Cntr=0.3,0.1

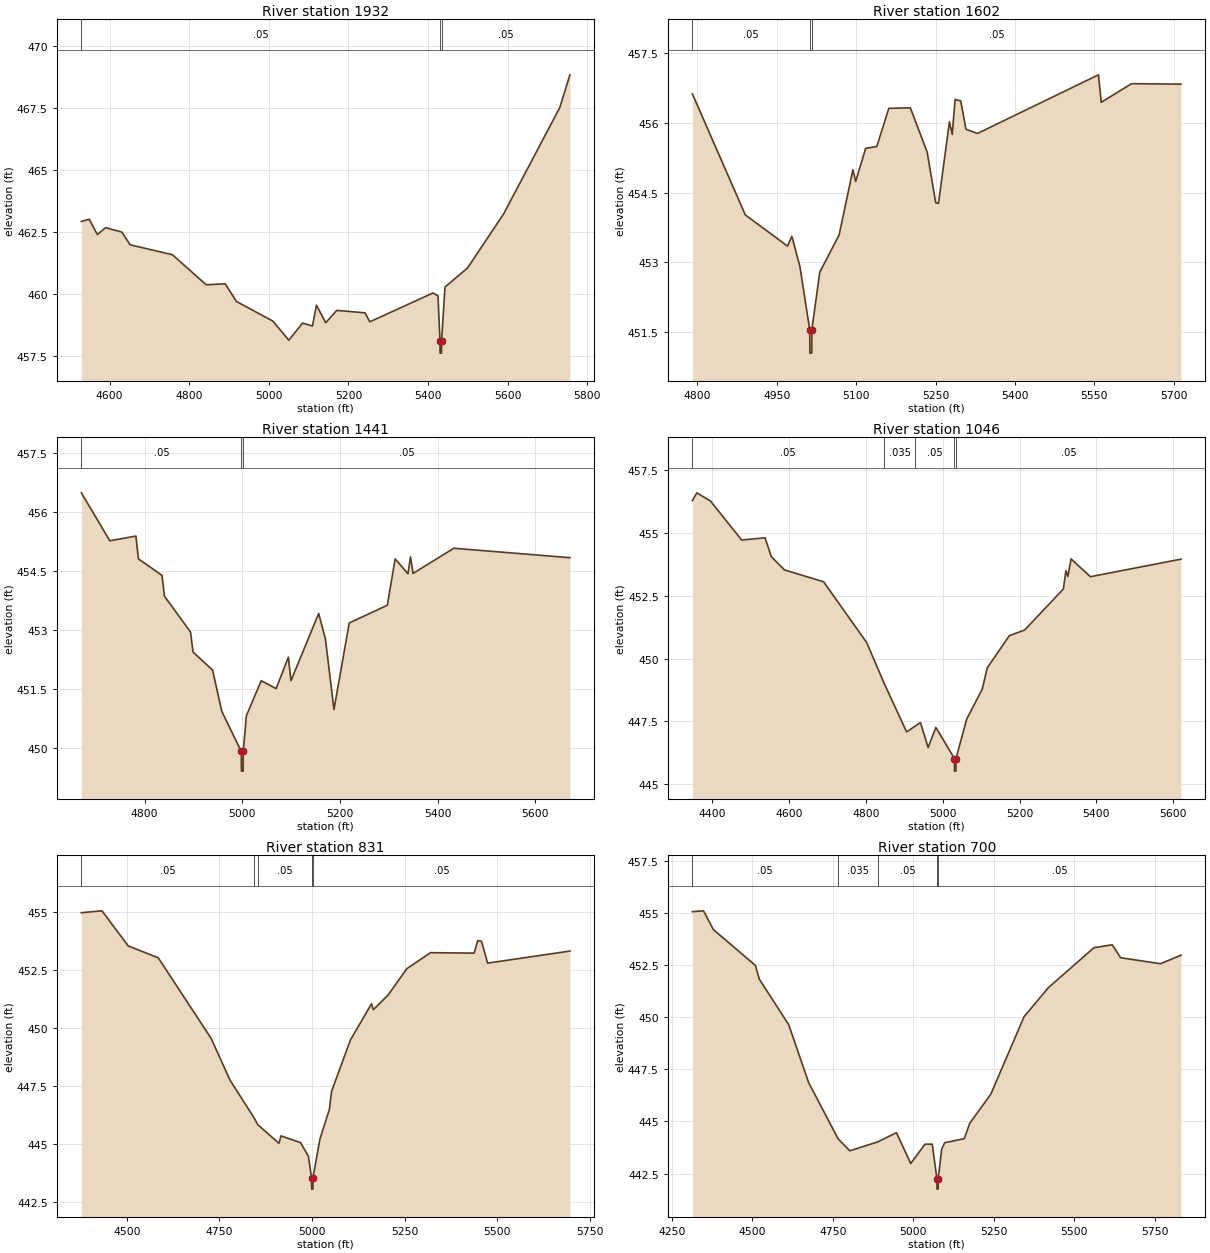
Type RM Length L Ch R = 1,1932,330,330,330
BEGIN DESCRIPTION:
E20970
END DESCRIPTION:
XS GIS Cut Line= 5
      2462981.60     13832584.21      2462883.54     13832164.30
      2462870.74     13832052.31      2462505.29     13831984.53
      2462225.11     13832120.20
#Sta/Elev= 30
  4529.3  462.93  4549.0  463.02  4569.6  462.40  4590.1  462.68  4631.2  462.50
  4651.7  461.99  4757.9  461.59  4842.9  460.38  4890.6  460.42  4918.7  459.71
  5010.1  458.92  5050.4  458.15  5085.0  458.84  5109.6  458.72  5119.7  459.56
  5142.9  458.85  5170.6  459.35  5241.8  459.25  5253.7  458.89  5412.3  460.05
  5424.9  459.94  5429.9  458.13  5430.1  457.63  5433.6  457.63  5433.9  458.13
  5442.5  460.29  5499.3  461.06  5589.6  463.23  5730.7  467.51  5756.2  468.83
#Mann=3,-1,0
  4529.3    0.05       0  5429.9    0.05       0  5433.9    0.05       0
Bank Sta=5429.9,5433.9
Exp/Cntr=0.3,0.1

Type RM Length L Ch R = 1,1602,161,161,161
BEGIN DESCRIPTION:
XS6680
END DESCRIPTION:
XS GIS Cut Line= 3
      2463172.22     13832066.66      2463050.69     13831875.69
      2462390.99     13831650.01
#Sta/Elev= 30
  4790.4  456.62  4890.4  454.02  4970.2  453.35  4978.4  453.56  4993.7  452.91
  5012.2  451.55  5012.5  451.05  5016.0  451.05  5016.2  451.55  5031.2  452.79
  5067.8  453.59  5093.8  454.99  5099.1  454.74  5117.9  455.45  5139.0  455.49
  5161.7  456.31  5202.4  456.32  5234.2  455.37  5250.3  454.28  5255.6  454.27
  5276.3  456.02  5281.6  455.75  5287.0  456.50  5297.6  456.47  5307.6  455.86
  5329.3  455.77  5558.0  457.03  5563.3  456.44  5620.6  456.84  5714.0  456.83
#Mann=3,-1,0
  4790.4    0.05       0  5012.2    0.05       0  5016.2    0.05       0
Bank Sta=5012.2,5016.2
Exp/Cntr=0.3,0.1

Type RM Length L Ch R = 1,1441,395,395,395
BEGIN DESCRIPTION:
E20969
END DESCRIPTION:
XS GIS Cut Line= 4
      2463180.10     13832019.23      2463132.05     13831754.95
      2462960.84     13831691.87      2462441.21     13831514.65
#Sta/Elev= 30
  4670.6  456.48  4728.9  455.26  4782.3  455.38  4787.4  454.80  4835.7  454.38
  4840.7  453.85  4894.1  452.94  4899.2  452.43  4939.2  451.97  4958.1  450.92
  4998.0  449.90  4998.3  449.40  5001.8  449.40  5002.0  449.90  5008.4  450.81
  5038.8  451.70  5069.3  451.50  5094.4  452.30  5099.7  451.70  5156.4  453.41
  5170.1  452.77  5187.7  450.97  5219.0  453.17  5296.9  453.62  5313.0  454.80
  5339.1  454.42  5344.4  454.85  5349.7  454.43  5433.1  455.07  5670.7  454.83
#Mann=3,-1,0
  4670.6    0.05       0  4998.0    0.05       0  5002.0    0.05       0
Bank Sta=4998,5002
Exp/Cntr=0.3,0.1

Type RM Length L Ch R = 1,1046,215,215,215
BEGIN DESCRIPTION:
XS6679
END DESCRIPTION:
XS GIS Cut Line= 4
      2463198.27     13831901.71      2463259.03     13831511.11
      2463180.90     13831380.90      2462460.38     13831311.46
#Sta/Elev= 30
  4349.0  456.29  4360.6  456.60  4396.3  456.27  4477.2  454.72  4538.0  454.81
  4554.3  454.06  4588.6  453.53  4690.2  453.06  4802.3  450.64  4848.0  449.01
  4906.3  447.08  4927.3  447.30  4942.3  447.45  4962.3  446.46  4982.4  447.26
  5030.7  446.02  5030.9  445.52  5034.4  445.52  5034.7  446.02  5062.8  447.60
  5103.0  448.78  5116.0  449.63  5173.3  450.91  5213.4  451.14  5314.0  452.77
  5320.7  453.50  5325.8  453.27  5334.1  453.97  5384.3  453.26  5620.0  453.96
#Mann=5,-1,0
  4349.0    0.05       0  4848.0   0.035       0  4927.3    0.05       0
  5030.7    0.05       0  5034.7    0.05       0
Bank Sta=5030.7,5034.7
Exp/Cntr=0.3,0.1

Type RM Length L Ch R = 1,831,131,131,131
BEGIN DESCRIPTION:
E20968
END DESCRIPTION:
XS GIS Cut Line= 5
      2463234.17     13831769.98      2463285.24     13831448.57
      2463219.16     13831205.28      2463071.98     13831163.23
      2462488.18     13831238.07
#Sta/Elev= 30
  4377.2  454.95  4432.9  455.03  4503.8  453.52  4584.8  453.01  4727.4  449.55
  4778.9  447.74  4842.7  446.15  4853.7  445.83  4910.9  445.03  4916.1  445.35
  4969.1  445.06  4990.3  444.47  4998.7  443.56  4998.9  443.06  5002.4  443.06
  5002.7  443.56  5021.5  445.22  5047.1  446.50  5052.7  447.26  5103.6  449.47
  5160.6  451.03  5165.7  450.78  5205.6  451.41  5256.0  452.54  5319.9  453.23
  5437.5  453.21  5447.6  453.75  5457.6  453.72  5474.2  452.78  5696.4  453.30
#Mann=5,-1,0
  4377.2    0.05       0  4842.7   0.035       0  4853.7    0.05       0
  4998.7    0.05       0  5002.7    0.05       0
Bank Sta=4998.7,5002.7
Exp/Cntr=0.3,0.1

Type RM Length L Ch R = 1,700,360,360,360
BEGIN DESCRIPTION:
E20967
END DESCRIPTION:
XS GIS Cut Line= 4
      2463252.20     13831748.94      2463345.31     13831268.36
      2463201.14     13830986.01      2462513.34     13831163.22
#Sta/Elev= 30
  4314.4  455.07  4349.0  455.11  4379.5  454.21  4510.0  452.49  4522.1  451.83
  4613.5  449.64  4675.4  446.86  4766.9  444.16  4803.1  443.59  4890.3  444.02
  4947.8  444.46  4992.2  442.98  5036.7  443.91  5058.9  443.91  5073.5  442.25
  5073.8  441.75  5077.3  441.75  5077.5  442.25  5088.4  443.68  5097.7  443.98
  5158.3  444.17  5175.4  444.91  5240.9  446.31  5344.1  450.03  5419.5  451.42
  5561.0  453.34  5617.8  453.48  5643.6  452.86  5767.5  452.57  5831.2  452.98
#Mann=5,-1,0
  4314.4    0.05       0  4766.9   0.035       0  4890.3    0.05       0
  5073.5    0.05       0  5077.5    0.05       0
Bank Sta=5073.5,5077.5
Exp/Cntr=0.3,0.1

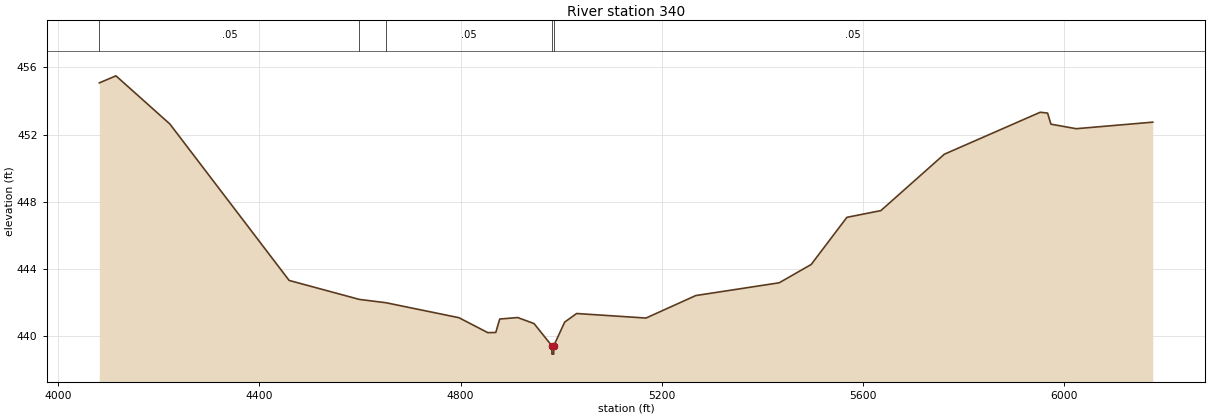
Type RM Length L Ch R = 1,340,0,0,0
BEGIN DESCRIPTION:
XS6678
END DESCRIPTION:
XS GIS Cut Line= 4
      2463267.71     13831754.17      2463597.57     13831077.08
      2463476.04     13830790.63      2462503.83     13831129.16
#Sta/Elev= 30
  4082.1  455.08  4115.1  455.50  4222.3  452.63  4459.4  443.31  4598.9  442.18
  4652.1  441.98  4796.9  441.09  4854.2  440.20  4870.1  440.21  4877.9  441.01
  4913.6  441.10  4946.2  440.74  4981.4  439.42  4981.7  438.92  4985.2  438.92
  4985.4  439.42  5007.1  440.83  5030.8  441.34  5168.7  441.07  5267.7  442.41
  5433.4  443.17  5497.0  444.26  5568.0  447.07  5635.5  447.47  5761.7  450.83
  5952.3  453.33  5966.9  453.28  5973.5  452.62  6023.8  452.35  6175.9  452.74
#Mann=5,-1,0
  4082.1    0.05       0  4598.9   0.035       0  4652.1    0.05       0
  4981.4    0.05       0  4985.4    0.05       0
Bank Sta=4981.4,4985.4
Exp/Cntr=0.3,0.1

Chan Stop Cuts=-1