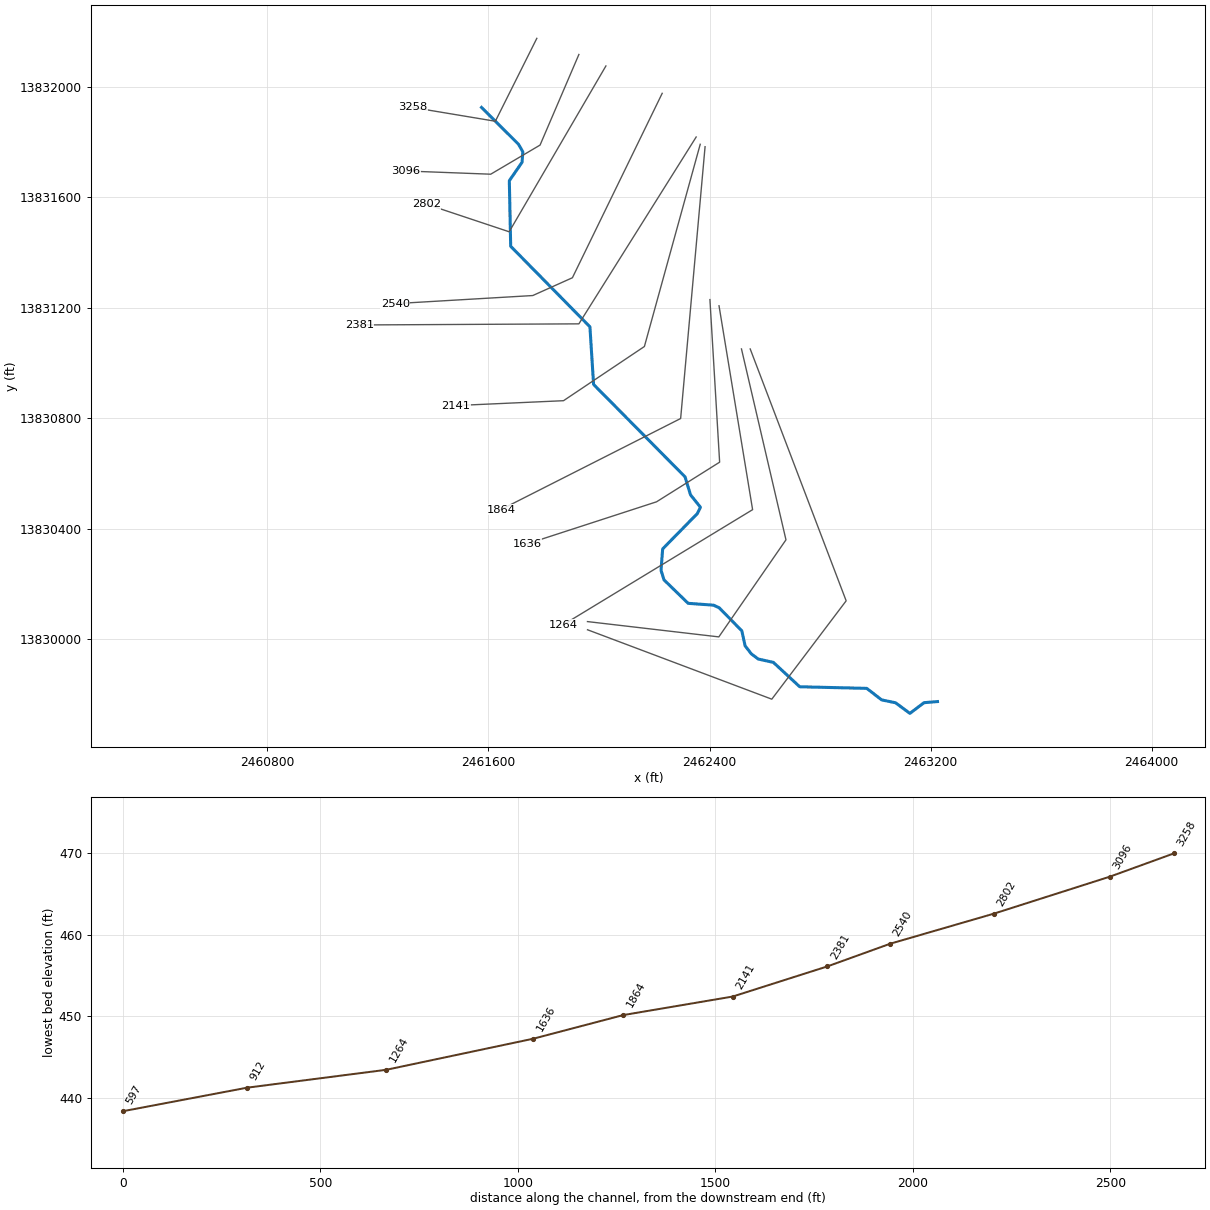
--- Stream0395.prj (project) ---

Proj Title=Stream0395 Base Level Engineering
Current Plan=p01
Default Exp/Contr=0.3,0.1
English Units
Geom File=g01
Flow File=f01
Plan File=p01
BEGIN DESCRIPTION:
Stream0395
END DESCRIPTION:

--- Stream0395.p01 (plan) ---

Plan Title=Multiple Run
Short Identifier=Multiple
Geom File=g01
Flow File=f01
Subcritical Flow
K Sum by GR= 0
Std Step Tol= 0.01
Critical Tol= 0.01
Num of Std Step Trials= 20
Max Error Tol= 0.3
Flow Tol Ratio= 0.001
Split Flow NTrial= 30
Split Flow Tol= 0.02
Split Flow Ratio= 0.02
Log Output Level= 0
Friction Slope Method= 1
Unsteady Friction Slope Method= 2
Unsteady Bridges Friction Slope Method= 1
Parabolic Critical Depth
Global Vel Dist=  1 , 1 , 1
Global Log Level= 0
CheckData=True
Encroach Param= -1, 0, 0, 0
BEGIN DESCRIPTION:
Multiple Run
END DESCRIPTION:

--- Stream0395.f01 (steady flow) ---

Flow Title=Multiple
Number of Profiles=7
Profile Names=10-year,25-year,50-year,1pct_min,100-year,1pct_plu,500-year
River Rch & RM= Stream0395,Reach-1,3258
     286     439     571     362     722    1441    1138
Boundary for River Rch & Prof#=Stream0395,Reach-1,1
Up Type=0
Dn Type=3
Dn Slope=0.005
Boundary for River Rch & Prof#=Stream0395,Reach-1,2
Up Type=0
Dn Type=3
Dn Slope=0.005
Boundary for River Rch & Prof#=Stream0395,Reach-1,3
Up Type=0
Dn Type=3
Dn Slope=0.005
Boundary for River Rch & Prof#=Stream0395,Reach-1,4
Up Type=0
Dn Type=3
Dn Slope=0.005
Boundary for River Rch & Prof#=Stream0395,Reach-1,5
Up Type=0
Dn Type=3
Dn Slope=0.005
Boundary for River Rch & Prof#=Stream0395,Reach-1,6
Up Type=0
Dn Type=3
Dn Slope=0.005
Boundary for River Rch & Prof#=Stream0395,Reach-1,7
Up Type=0
Dn Type=3
Dn Slope=0.005

--- Stream0395.g01 (geometry) ---

Geom Title=Existing Conditions

River Reach=Stream0395,Reach-1
Reach XY= 30
      2461575.00     13831925.00      2461708.79     13831791.68
      2461724.41     13831764.38      2461721.66     13831726.75
      2461675.54     13831659.79      2461680.46     13831422.55
      2461967.19     13831131.19      2461980.46     13830922.55
      2462311.40     13830588.21      2462331.43     13830522.71
      2462367.17     13830478.23      2462355.72     13830454.97
      2462230.40     13830327.43      2462224.49     13830249.96
      2462235.42     13830215.19      2462322.56     13830130.52
      2462414.52     13830123.84      2462434.81     13830114.49
      2462516.84     13830031.05      2462528.89     13829976.43
      2462551.16     13829947.86      2462576.43     13829928.89
      2462631.02     13829916.81      2462726.47     13829828.55
      2462969.07     13829822.76      2463022.83     13829781.09
      2463073.37     13829770.59      2463125.03     13829732.28
      2463176.36     13829771.00      2463225.00     13829775.00

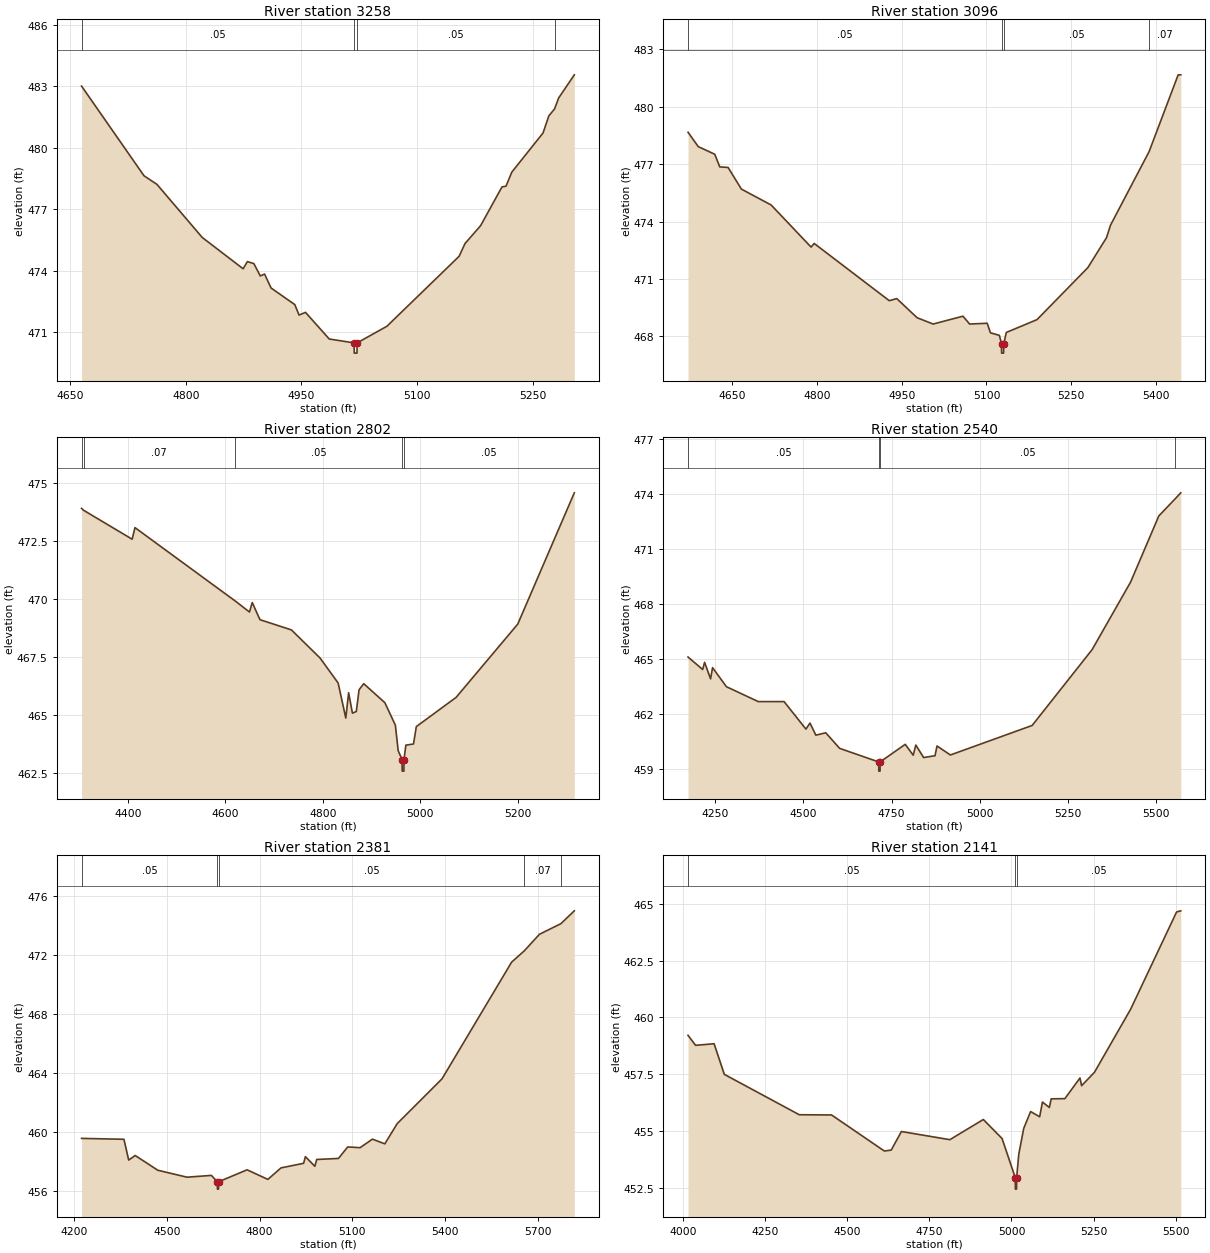
Type RM Length L Ch R = 1,3258,162,162,162
BEGIN DESCRIPTION:
Stream0395 7.0
END DESCRIPTION:
XS GIS Cut Line= 3
      2461775.02     13832175.04      2461625.00     13831875.00
      2461324.99     13831925.00
#Sta/Elev= 30
  4664.6  483.02  4745.7  478.64  4762.5  478.22  4821.2  475.63  4874.3  474.10
  4879.9  474.45  4888.3  474.35  4896.6  473.75  4902.2  473.84  4910.6  473.16
  4941.4  472.35  4946.9  471.84  4955.3  471.97  4986.1  470.67  5018.3  470.48
  5018.6  469.98  5022.1  469.98  5022.3  470.48  5060.9  471.29  5154.7  474.71
  5162.3  475.33  5182.5  476.20  5210.4  478.10  5215.5  478.13  5223.1  478.82
  5263.6  480.73  5271.2  481.57  5278.5  481.90  5283.9  482.44  5304.2  483.57
#Mann=4,-1,0
  4664.6    0.05       0  5018.3    0.05       0  5022.3    0.05       0
  5278.5    0.12       0
Bank Sta=5018.3,5022.3
Exp/Cntr=0.3,0.1

Type RM Length L Ch R = 1,3096,294,294,294
BEGIN DESCRIPTION:
E20978
END DESCRIPTION:
XS GIS Cut Line= 4
      2461927.27     13832116.62      2461786.76     13831788.75
      2461608.20     13831683.38      2461300.87     13831695.08
#Sta/Elev= 30
  4572.1  478.67  4590.2  477.92  4619.4  477.52  4628.3  476.86  4643.0  476.83
  4666.5  475.70  4719.1  474.87  4789.8  472.67  4795.3  472.86  4928.1  469.87
  4941.3  469.98  4977.3  468.98  5005.7  468.65  5058.4  469.06  5070.2  468.65
  5101.3  468.69  5107.1  468.19  5122.8  468.06  5126.6  467.63  5126.8  467.13
  5130.3  467.13  5130.6  467.63  5135.1  468.21  5189.4  468.88  5279.4  471.60
  5312.3  473.16  5319.5  473.82  5387.7  477.66  5439.1  481.67  5443.7  481.67
#Mann=4,-1,0
  4572.1    0.05       0  5126.6    0.05       0  5130.6    0.05       0
  5387.7    0.07       0
Bank Sta=5126.6,5130.6
Exp/Cntr=0.3,0.1

Type RM Length L Ch R = 1,2802,262,262,262
BEGIN DESCRIPTION:
Stream0395 6.0
END DESCRIPTION:
XS GIS Cut Line= 3
      2462025.02     13832075.03      2461675.00     13831475.00
      2461374.99     13831575.00
#Sta/Elev= 30
  4304.9  473.92  4308.9  473.84  4408.7  472.59  4414.5  473.09  4619.9  469.93
  4649.4  469.45  4655.1  469.86  4670.9  469.12  4735.4  468.68  4794.1  467.47
  4831.3  466.39  4847.0  464.88  4852.8  465.97  4860.6  465.09  4868.5  465.16
  4874.3  466.10  4883.8  466.36  4927.2  465.54  4948.7  464.57  4954.5  463.47
  4962.4  463.09  4962.7  462.59  4966.2  462.59  4966.4  463.09  4970.2  463.71
  4985.9  463.76  4991.7  464.51  5073.3  465.77  5199.8  468.93  5315.8  474.59
#Mann=5,-1,0
  4304.9    0.05       0  4308.9    0.07       0  4619.9    0.05       0
  4962.4    0.05       0  4966.4    0.05       0
Bank Sta=4962.4,4966.4
Exp/Cntr=0.3,0.1

Type RM Length L Ch R = 1,2540,159,159,159
BEGIN DESCRIPTION:
E20977
END DESCRIPTION:
XS GIS Cut Line= 4
      2462228.75     13831976.08      2461903.84     13831308.70
      2461760.41     13831244.30      2461262.77     13831215.03
#Sta/Elev= 30
  4172.6  465.13  4214.1  464.45  4219.6  464.84  4236.6  463.94  4242.2  464.55
  4281.7  463.51  4371.9  462.70  4445.1  462.70  4507.2  461.20  4518.6  461.53
  4535.3  460.87  4563.4  461.00  4602.9  460.15  4713.6  459.41  4713.9  458.91
  4717.4  458.91  4717.6  459.41  4788.8  460.37  4811.4  459.78  4818.9  460.33
  4841.1  459.65  4873.4  459.75  4879.0  460.28  4917.0  459.79  5149.0  461.40
  5319.3  465.54  5428.1  469.21  5508.3  472.82  5554.5  473.75  5570.6  474.08
#Mann=4,-1,0
  4172.6    0.05       0  4713.6    0.05       0  4717.6    0.05       0
  5554.5    0.07       0
Bank Sta=4713.6,4717.6
Exp/Cntr=0.3,0.1

Type RM Length L Ch R = 1,2381,240,240,240
BEGIN DESCRIPTION:
XS6687
END DESCRIPTION:
XS GIS Cut Line= 3
      2462351.69     13831818.01      2461927.26     13831141.85
      2461132.30     13831137.85
#Sta/Elev= 30
  4224.5  459.57  4361.6  459.51  4376.9  458.10  4398.1  458.41  4471.1  457.41
  4565.4  456.94  4644.3  457.06  4663.6  456.63  4663.8  456.13  4667.3  456.13
  4667.6  456.63  4759.8  457.44  4826.9  456.79  4869.4  457.57  4942.4  457.88
  4948.3  458.33  4978.9  457.68  4984.8  458.14  5055.1  458.21  5085.1  458.99
  5125.1  458.94  5165.1  459.52  5205.1  459.20  5245.1  460.57  5390.1  463.61
  5615.1  471.52  5656.2  472.29  5705.1  473.41  5774.5  474.13  5817.8  475.00
#Mann=5,-1,0
  4224.5    0.05       0  4663.6    0.05       0  4667.6    0.05       0
  5656.2    0.07       0  5774.5     0.1       0
Bank Sta=4663.6,4667.6
Exp/Cntr=0.3,0.1

Type RM Length L Ch R = 1,2141,277,277,277
BEGIN DESCRIPTION:
E20976
END DESCRIPTION:
XS GIS Cut Line= 4
      2462366.33     13831791.65      2462164.36     13831059.89
      2461871.65     13830863.77      2461482.31     13830846.20
#Sta/Elev= 30
  4014.6  459.21  4037.7  458.77  4094.1  458.84  4125.2  457.49  4353.5  455.71
  4451.9  455.70  4612.8  454.11  4633.6  454.15  4664.7  454.97  4812.3  454.61
  4914.3  455.50  4971.4  454.66  5011.7  452.93  5011.9  452.43  5015.4  452.43
  5015.7  452.93  5022.4  453.98  5037.4  455.11  5058.4  455.85  5085.9  455.62
  5094.4  456.27  5115.4  456.03  5121.0  456.41  5162.7  456.42  5208.7  457.33
  5213.7  456.99  5252.8  457.58  5363.0  460.36  5503.1  464.65  5515.8  464.70
#Mann=3,-1,0
  4014.6    0.05       0  5011.7    0.05       0  5015.7    0.05       0
Bank Sta=5011.7,5015.7
Exp/Cntr=0.3,0.1

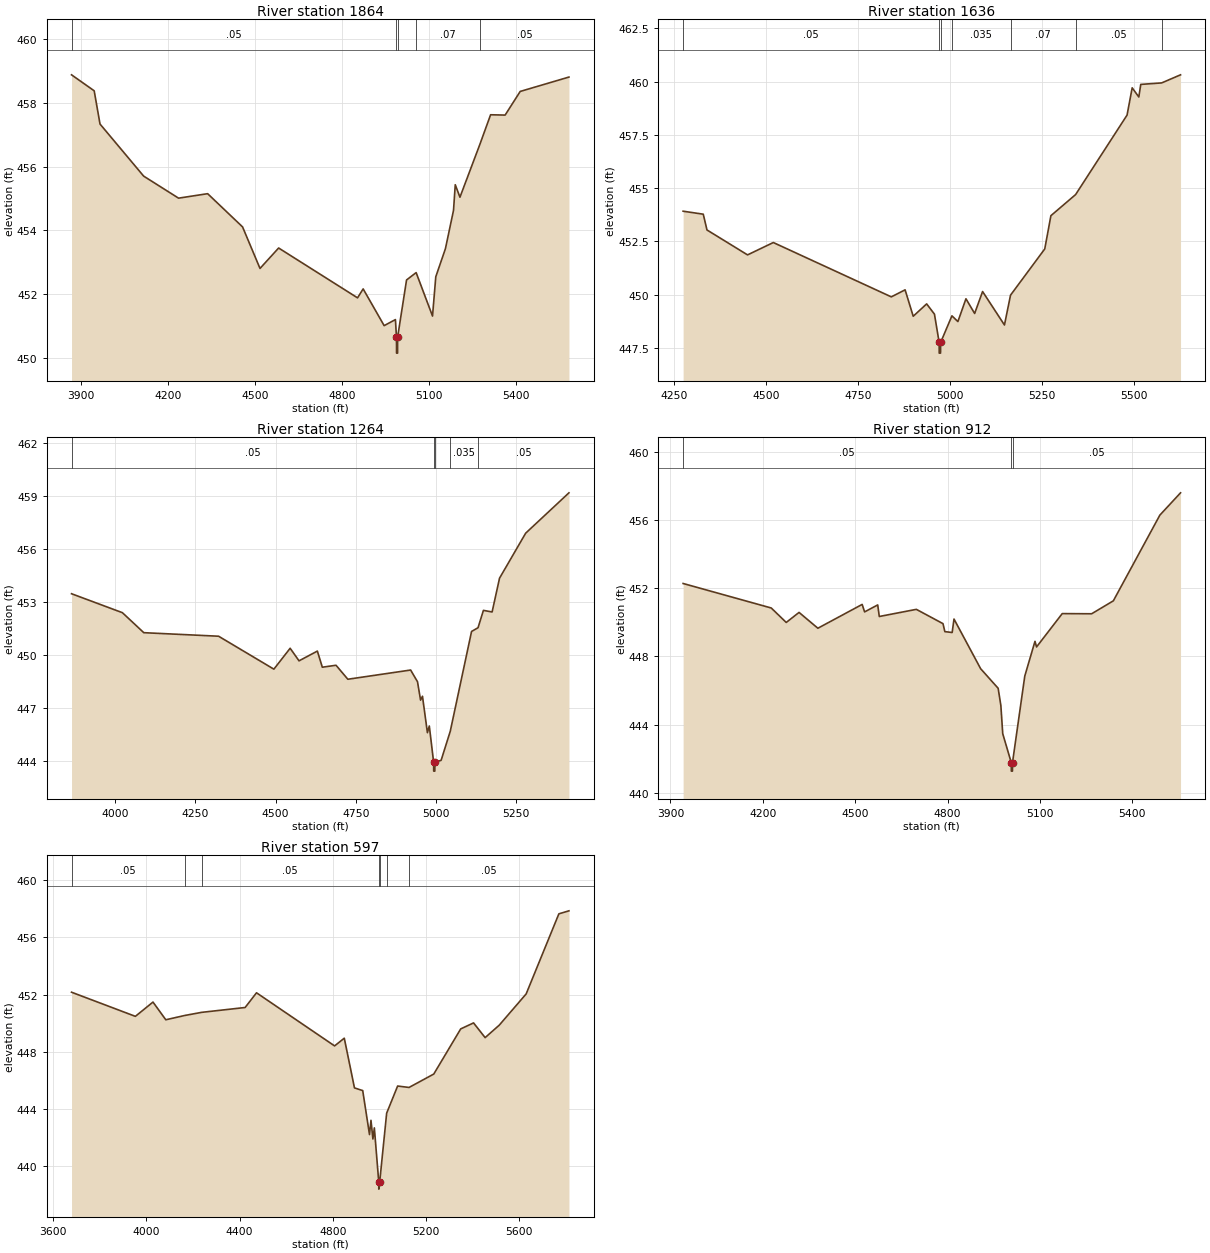
Type RM Length L Ch R = 1,1864,228,228,228
BEGIN DESCRIPTION:
XS6686
END DESCRIPTION:
XS GIS Cut Line= 3
      2462383.90     13831782.90      2462295.49     13830799.31
      2461644.98     13830469.72
#Sta/Elev= 30
  3867.5  458.87  3945.7  458.37  3965.8  457.33  4116.4  455.70  4236.9  455.01
  4337.3  455.15  4457.8  454.11  4518.0  452.81  4582.3  453.45  4854.7  451.89
  4874.0  452.17  4946.5  451.02  4985.4  451.21  4989.0  450.66  4989.3  450.16
  4992.8  450.16  4993.0  450.66  5023.8  452.45  5056.9  452.68  5113.4  451.32
  5124.7  452.55  5158.0  453.43  5185.9  454.63  5191.9  455.43  5208.1  455.04
  5276.7  456.69  5313.9  457.62  5364.0  457.61  5416.1  458.35  5584.3  458.80
#Mann=5,-1,0
  3867.5    0.05       0  4989.0    0.05       0  4993.0    0.05       0
  5056.9    0.07       0  5276.7    0.05       0
Bank Sta=4989,4993
Exp/Cntr=0.3,0.1

Type RM Length L Ch R = 1,1636,372,372,372
BEGIN DESCRIPTION:
E20975
END DESCRIPTION:
XS GIS Cut Line= 4
      2462401.46     13831229.64      2462436.59     13830641.30
      2462208.27     13830497.87      2461740.00     13830345.68
#Sta/Elev= 30
  4275.7  453.92  4330.4  453.78  4340.5  453.04  4450.7  451.87  4520.8  452.45
  4841.3  449.90  4878.8  450.23  4900.8  448.99  4937.3  449.57  4958.5  449.09
  4971.3  447.76  4971.5  447.26  4975.0  447.26  4975.3  447.76  5006.0  449.01
  5022.2  448.74  5044.1  449.81  5067.7  449.12  5089.3  450.15  5148.7  448.58
  5165.2  449.98  5258.2  452.15  5274.9  453.71  5342.0  454.70  5481.8  458.43
  5495.7  459.71  5513.8  459.28  5519.0  459.87  5575.8  459.94  5627.1  460.32
#Mann=7,-1,0
  4275.7    0.05       0  4971.3    0.05       0  4975.3    0.05       0
  5006.0   0.035       0  5165.2    0.07       0  5342.0    0.05       0
  5575.8   0.035       0
Bank Sta=4971.3,4975.3
Exp/Cntr=0.3,0.1

Type RM Length L Ch R = 1,1264,352,352,352
BEGIN DESCRIPTION:
XS6685
END DESCRIPTION:
XS GIS Cut Line= 3
      2462434.38     13831207.25      2462555.90     13830469.44
      2461870.11     13830052.76
#Sta/Elev= 30
  3864.1  453.47  4022.6  452.40  4089.3  451.27  4322.4  451.07  4494.7  449.21
  4545.4  450.39  4573.1  449.68  4630.2  450.23  4645.7  449.32  4688.4  449.43
  4725.2  448.64  4920.9  449.16  4942.3  448.50  4951.9  447.46  4957.8  447.68
  4973.2  445.62  4979.1  446.00  4992.6  443.95  4992.8  443.45  4996.3  443.45
  4996.6  443.95  5015.9  444.06  5044.4  445.70  5110.8  451.34  5131.0  451.55
  5147.7  452.53  5174.8  452.44  5198.0  454.35  5279.4  456.89  5414.3  459.17
#Mann=5,-1,0
  3864.1    0.05       0  4992.6    0.05       0  4996.6    0.05       0
  5044.4   0.035       0  5131.0    0.05       0
Bank Sta=4992.6,4996.6
Exp/Cntr=0.3,0.1

Type RM Length L Ch R = 1,912,315,315,315
BEGIN DESCRIPTION:
E20974
END DESCRIPTION:
XS GIS Cut Line= 4
      2462515.62     13831051.11      2462676.62     13830360.29
      2462433.66     13830009.03      2461958.31     13830064.44
#Sta/Elev= 30
  3941.2  452.29  4227.3  450.85  4276.0  450.00  4317.6  450.59  4378.7  449.66
  4522.5  451.06  4530.4  450.62  4573.0  451.03  4578.1  450.35  4698.4  450.77
  4784.9  449.93  4791.0  449.46  4814.7  449.41  4820.7  450.20  4907.2  447.28
  4964.0  446.13  4972.8  445.12  4978.9  443.46  5006.6  441.76  5006.9  441.26
  5010.4  441.26  5010.6  441.76  5050.5  446.85  5083.6  448.89  5088.7  448.56
  5172.1  450.52  5267.6  450.51  5338.0  451.27  5489.1  456.31  5556.2  457.62
#Mann=3,-1,0
  3941.2    0.05       0  5006.6    0.05       0  5010.6    0.05       0
Bank Sta=5006.6,5010.6
Exp/Cntr=0.3,0.1

Type RM Length L Ch R = 1,597,0,0,0
BEGIN DESCRIPTION:
XS6684
END DESCRIPTION:
XS GIS Cut Line= 4
      2462547.24     13831051.00      2462894.44     13830139.58
      2462625.35     13829783.68      2461958.47     13830034.84
#Sta/Elev= 30
  3678.9  452.16  3952.8  450.47  4028.4  451.47  4083.3  450.23  4164.2  450.53
  4237.3  450.75  4423.7  451.09  4472.5  452.12  4807.5  448.40  4849.1  448.94
  4892.8  445.46  4928.2  445.27  4957.3  442.19  4963.6  443.19  4971.9  441.88
  4978.1  442.66  4997.0  438.87  4997.2  438.37  5001.0  438.87  5030.9  443.69
  5078.0  445.59  5126.9  445.49  5233.1  446.43  5348.6  449.59  5403.7  450.01
  5453.4  448.98  5513.8  449.85  5629.4  452.04  5769.8  457.65  5813.0  457.86
#Mann=7,-1,0
  3678.9    0.05       0  4164.2   0.035       0  4237.3    0.05       0
  4997.0    0.05       0  5001.0    0.05       0  5030.9    0.07       0
  5126.9    0.05       0
Bank Sta=4997,5001
Exp/Cntr=0.3,0.1

Chan Stop Cuts=-1