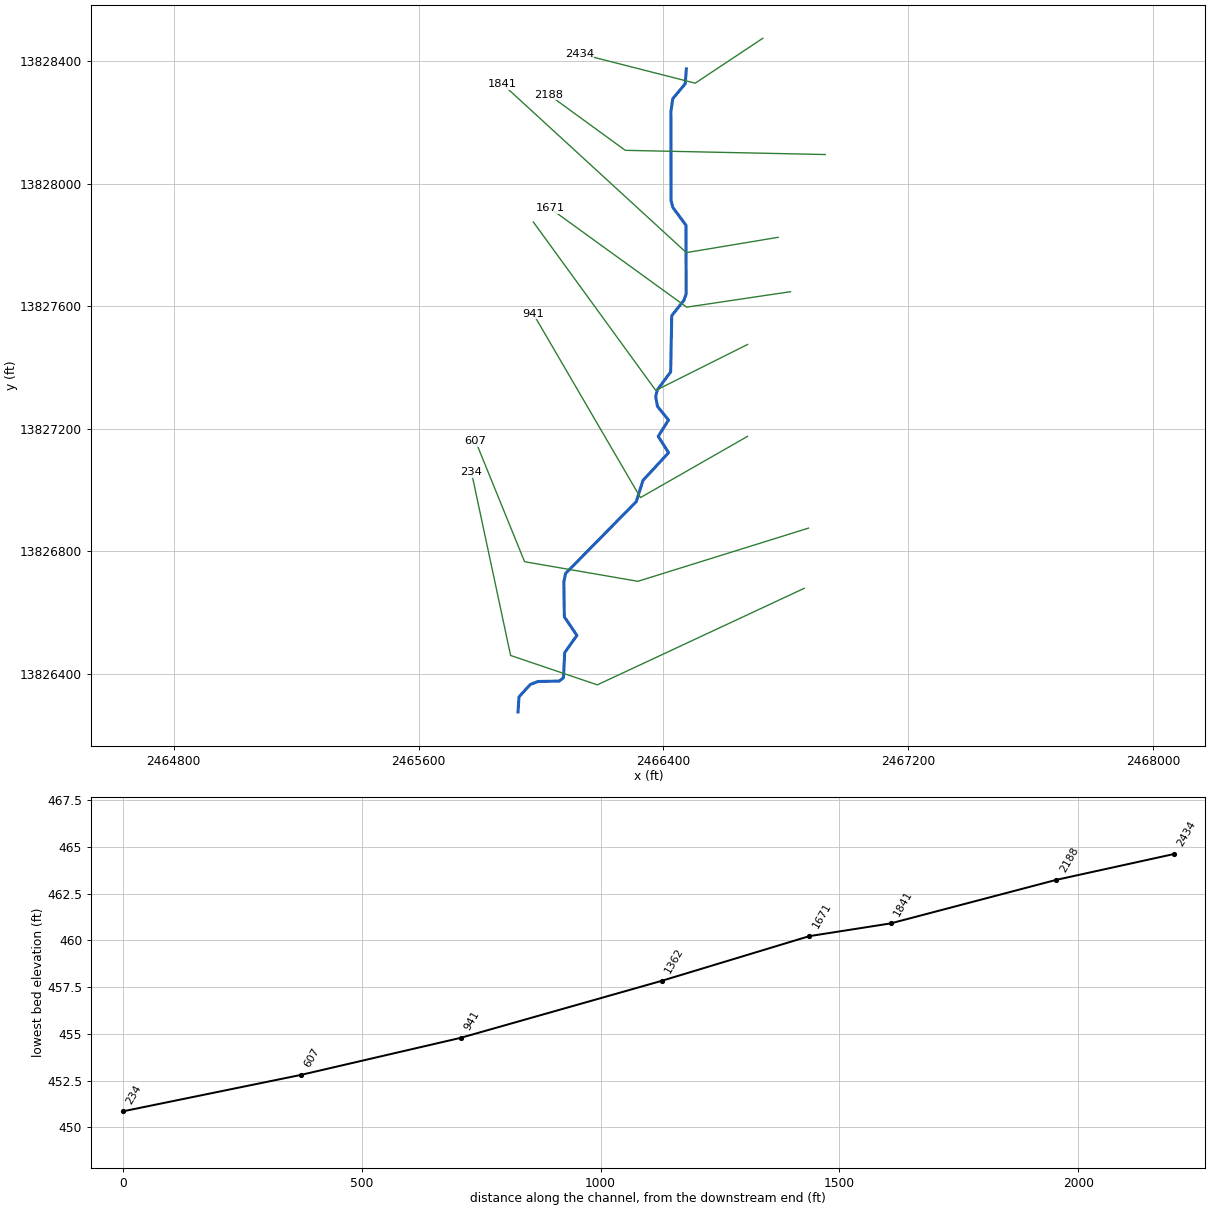
--- Stream0402.prj (project) ---

Proj Title=Stream0402 Base Level Engineering
Current Plan=p01
Default Exp/Contr=0.3,0.1
English Units
Geom File=g01
Flow File=f01
Plan File=p01
Y Axis Title=Elevation
X Axis Title(PF)=Main Channel Distance
X Axis Title(XS)=Station
BEGIN DESCRIPTION:
Stream0402
END DESCRIPTION:
DSS Export Rating Curves= 0
DSS Export Rating Curve Sorted= 0
DSS Export Volume Flow Curves= 0
DXF OffsetX= 0
DXF OffsetY= 0
DXF ScaleX= 1
DXF ScaleY= 10

--- Stream0402.p01 (plan) ---

Plan Title=Multiple Run
Short Identifier=Multiple
Geom File=g01
Flow File=f01
Subcritical Flow
K Sum by GR= 0
Std Step Tol= 0.01
Critical Tol= 0.01
Num of Std Step Trials= 20
Max Error Tol= 0.3
Flow Tol Ratio= 0.001
Split Flow NTrial= 30
Split Flow Tol= 0.02
Split Flow Ratio= 0.02
Log Output Level= 0
Friction Slope Method= 1
Unsteady Friction Slope Method= 2
Unsteady Bridges Friction Slope Method= 1
Parabolic Critical Depth
Global Vel Dist=  1 , 1 , 1
Global Log Level= 0
CheckData=True
Encroach Param= -1, 0, 0, 0
BEGIN DESCRIPTION:
Multiple Run
END DESCRIPTION:

--- Stream0402.f01 (steady flow) ---

Flow Title=Multiple
Number of Profiles=7
Profile Names=10-year,25-year,50-year,1pct_min,100-year,1pct_plu,500-year
River Rch & RM= Stream0402,Reach-1,2434
     216     323     413     257     512    1022     777
Boundary for River Rch & Prof#=Stream0402,Reach-1,1
Up Type=0
Dn Type=3
Dn Slope=0.005
Boundary for River Rch & Prof#=Stream0402,Reach-1,2
Up Type=0
Dn Type=3
Dn Slope=0.005
Boundary for River Rch & Prof#=Stream0402,Reach-1,3
Up Type=0
Dn Type=3
Dn Slope=0.005
Boundary for River Rch & Prof#=Stream0402,Reach-1,4
Up Type=0
Dn Type=3
Dn Slope=0.005
Boundary for River Rch & Prof#=Stream0402,Reach-1,5
Up Type=0
Dn Type=3
Dn Slope=0.005
Boundary for River Rch & Prof#=Stream0402,Reach-1,6
Up Type=0
Dn Type=3
Dn Slope=0.005
Boundary for River Rch & Prof#=Stream0402,Reach-1,7
Up Type=0
Dn Type=3
Dn Slope=0.005

--- Stream0402.g01 (geometry) ---

Geom Title=Existing Conditions
Program Version=4.10

River Reach=Stream0402      ,Reach-1
Reach XY= 30
        2466475.       13828375.      2466471.35     13828326.51
      2466430.53     13828277.42      2466424.54     13828235.19
      2466425.07     13827945.03      2466430.75     13827922.67
      2466473.78      13827864.5      2466474.48     13827640.22
      2466466.86     13827618.94      2466427.26     13827569.06
      2466423.76      13827385.5       2466380.4     13827327.17
      2466374.79     13827304.79      2466380.63      13827272.7
      2466416.69     13827228.23      2466383.04       13827175.
        2466417.     13827121.67       2466333.2     13827031.05
      2466311.37     13826961.79      2466080.45     13826727.45
      2466074.68     13826700.11      2466076.37     13826585.44
      2466117.44       13826525.       2466077.6     13826469.01
      2466073.39     13826386.58      2466059.37     13826375.69
      2465990.27     13826374.47      2465964.95     13826364.72
      2465928.12     13826324.01        2465925.       13826275.

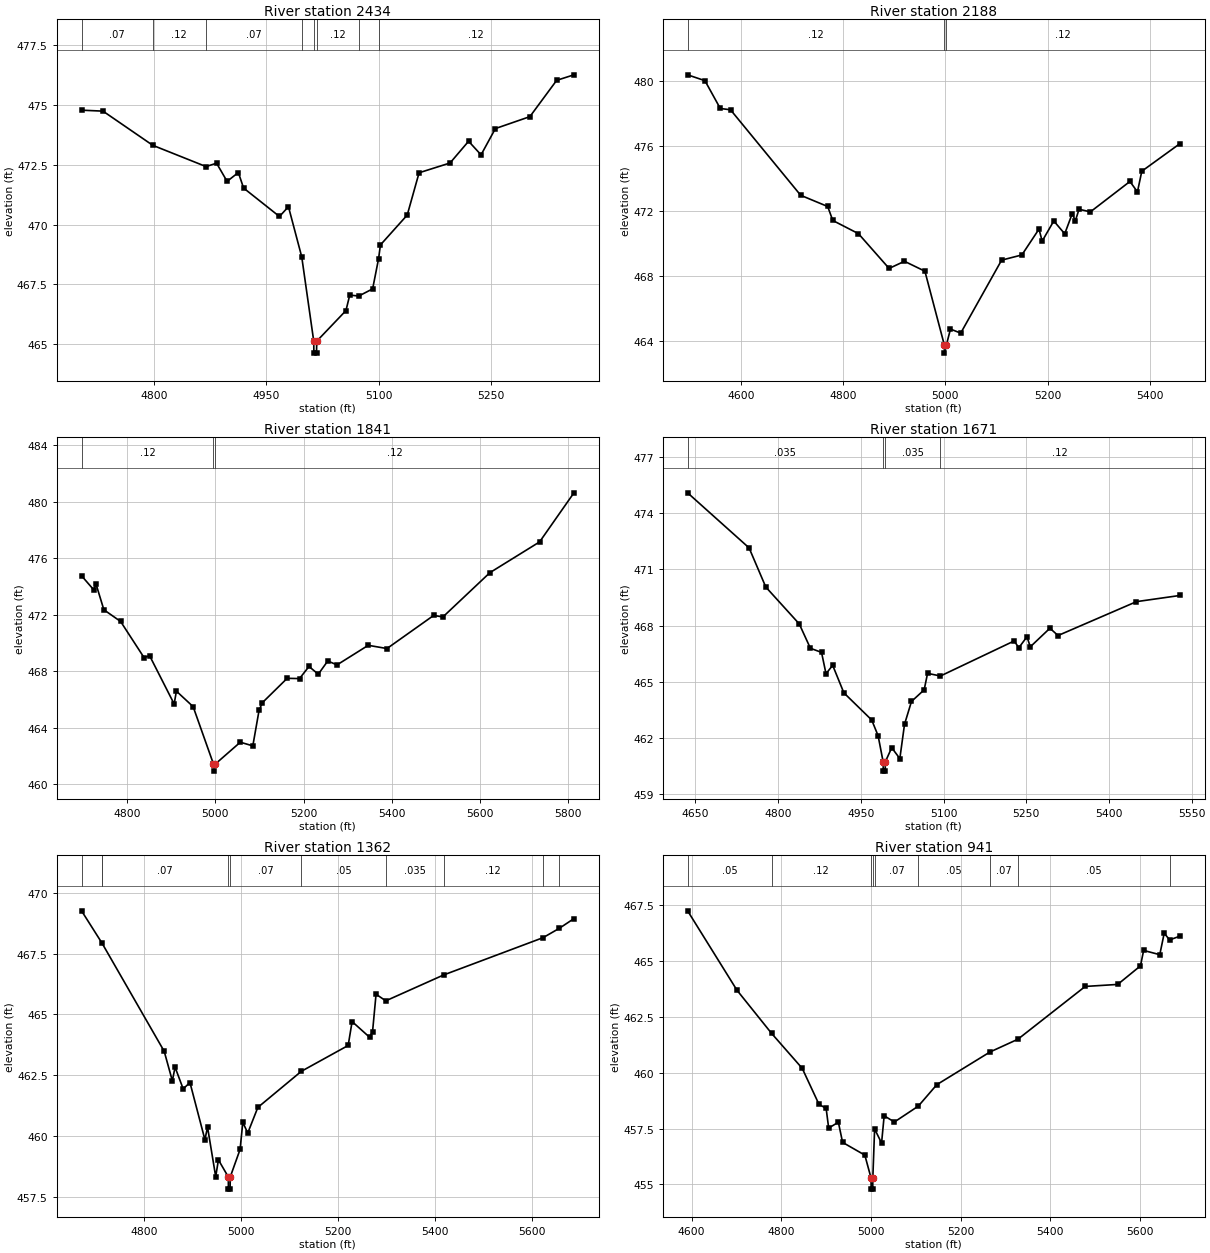
Type RM Length L Ch R = 1 ,2434    ,246,246,246
BEGIN DESCRIPTION:
Stream0402 4.0
END DESCRIPTION:
XS GIS Cut Line= 3
      2466724.99       13828475.      2466503.93     13828328.36
      2466125.03     13828424.99
#Sta/Elev= 30
  4703.8  474.79  4732.4  474.75  4798.7  473.32  4869.7  472.43  4883.8  472.57
  4897.8  471.81  4912.8  472.18  4919.8  471.53  4967.6  470.34  4979.6  470.75
  4997.3  468.65  5013.3  465.12  5013.5  464.62    5017  464.62  5017.3  465.12
  5056.2   466.4  5061.3  467.05  5073.3  467.01  5091.8  467.31  5099.7  468.57
  5102.2  469.15  5137.9   470.4  5153.7  472.17    5195  472.58  5219.7  473.49
  5236.3  472.92  5255.4  474.02  5301.4  474.52  5337.1  476.04  5360.1  476.27
#Mann= 8 ,-1 , 0
  4703.8     .07       0  4798.7     .12       0  4869.7     .07       0
  4997.3     .12       0  5013.3     .05       0  5017.3     .12       0
  5073.3     .07       0  5099.7     .12       0
Bank Sta=5013.3,5017.3
XS Rating Curve= 0 ,0
Exp/Cntr=0.3,0.1

Type RM Length L Ch R = 1 ,2188    ,347,347,347
BEGIN DESCRIPTION:
XS6709
END DESCRIPTION:
XS GIS Cut Line= 3
      2466928.88     13828095.32      2466275.45     13828109.03
      2466025.37     13828290.91
#Sta/Elev= 30
    4496  480.36  4529.9     480  4559.9  478.29  4579.9  478.21  4717.1  472.95
  4769.9  472.26  4779.9   471.4    4830  470.59    4890  468.45    4920  468.89
    4960  468.28    4998  463.74  4998.2  463.24    5002  463.74    5010  464.72
    5030  464.47    5110  468.96  5149.6  469.28  5183.1  470.87  5189.3  470.13
    5212  471.37  5233.4  470.58  5248.1  471.82  5254.2  471.38  5261.4  472.09
  5283.6  471.93  5360.9   473.8  5375.6  473.16  5384.1  474.43  5458.8  476.13
#Mann= 3 ,-1 , 0
    4496     .12       0    4998     .05       0    5002     .12       0
Bank Sta=4998,5002
XS Rating Curve= 0 ,0
Exp/Cntr=0.3,0.1

Type RM Length L Ch R = 1 ,1841    ,170,170,170
BEGIN DESCRIPTION:
Stream0402 3.0
END DESCRIPTION:
XS GIS Cut Line= 3
      2466774.96     13827824.99        2466475.       13827775.
      2465875.03     13828324.97
#Sta/Elev= 30
    4696  474.76  4723.8  473.76  4728.9  474.17  4746.7  472.35  4784.7  471.52
  4837.9  468.96  4850.6  469.09  4906.3  465.67  4911.4  466.58  4949.4  465.48
  4995.6  461.41  4995.8  460.91  4999.6  461.41  5056.5  462.96  5084.9   462.7
  5099.1  465.22  5106.5  465.76  5162.9  467.49  5190.9  467.47  5212.5  468.33
  5233.5  467.78  5255.1  468.72    5276  468.44    5347  469.83  5389.5   469.6
  5495.6  471.95  5516.5  471.84  5623.2  474.98    5736  477.16    5814  480.64
#Mann= 3 ,-1 , 0
    4696     .12       0  4995.6     .05       0  4999.6     .12       0
Bank Sta=4995.6,4999.6
XS Rating Curve= 0 ,0
Exp/Cntr=0.3,0.1

Type RM Length L Ch R = 1 ,1671    ,309,309,309
BEGIN DESCRIPTION:
E20990
END DESCRIPTION:
XS GIS Cut Line= 3
      2466815.28     13827647.39      2466476.09     13827596.93
      2466030.38      13827919.3
#Sta/Elev= 30
  4635.9  475.09  4747.4  472.15  4777.7  470.06  4838.4  468.09  4858.6  466.79
  4878.8  466.57  4886.9  465.43    4899  465.88  4919.3  464.41  4969.8  462.96
  4981.4  462.12  4990.5  460.73  4990.8  460.23  4994.3  460.23  4994.5  460.73
  5006.1  461.48  5020.8   460.9  5029.3  462.73  5041.9  463.95  5064.9  464.57
  5071.1  465.45  5094.5  465.31  5228.1  467.18  5236.6  466.82  5251.3   467.4
  5257.5  466.87    5293  467.86  5307.7  467.47    5450  469.28  5528.9  469.61
#Mann= 4 ,-1 , 0
  4635.9    .035       0  4990.5    .035       0  4994.5    .035       0
  5094.5     .12       0
Bank Sta=4990.5,4994.5
XS Rating Curve= 0 ,0
Exp/Cntr=0.3,0.1

Type RM Length L Ch R = 1 ,1362    ,421,421,421
BEGIN DESCRIPTION:
Stream0402 2.0
END DESCRIPTION:
XS GIS Cut Line= 3
        2466675.       13827475.        2466375.       13827325.
      2465974.99     13827875.01
#Sta/Elev= 30
  4671.2  469.25  4713.3  467.93  4841.7  463.49  4858.5  462.28  4864.1  462.84
  4880.8  461.95  4894.8  462.21  4925.6  459.87  4931.1  460.38  4947.9  458.35
  4953.5  459.04  4973.9  458.34  4974.1  457.84  4977.6  457.84  4977.9  458.34
  4998.2  459.47  5003.8  460.58    5014  460.14  5034.8  461.19  5124.5  462.67
  5221.1  463.73  5229.2  464.71  5265.1  464.07  5271.3  464.28  5278.6  465.83
  5298.7  465.56  5417.9  466.62  5623.1  468.15  5656.3  468.53  5686.7  468.93
#Mann= 10 ,-1 , 0
  4671.2     .07       0  4713.3     .05       0  4713.3     .07       0
  4973.9     .05       0  4977.9     .07       0  5124.5     .05       0
  5298.7    .035       0  5417.9     .12       0  5623.1     .07       0
  5656.3     .12       0
Bank Sta=4973.9,4977.9
XS Rating Curve= 0 ,0
Exp/Cntr=0.3,0.1

Type RM Length L Ch R = 1 ,941     ,334,334,334
BEGIN DESCRIPTION:
Stream0402 1.0
END DESCRIPTION:
XS GIS Cut Line= 3
      2466674.96     13827174.98        2466325.       13826975.
      2465974.99     13827575.01
#Sta/Elev= 30
  4591.2  467.23  4701.3  463.68  4778.5  461.75  4846.7  460.19  4884.1  458.58
    4900   458.4  4905.7  457.52  4927.3  457.78  4936.7  456.88  4986.3  456.31
  5000.1  455.29  5000.4  454.79  5003.9  454.79  5004.1  455.29  5008.1  457.48
  5023.6  456.85  5029.4  458.07  5052.1  457.79  5105.5   458.5  5146.8  459.46
  5265.3  460.92  5327.5  461.49  5477.6  463.85    5550  463.94  5600.8  464.77
  5607.8  465.46  5643.8  465.27  5653.7  466.23  5665.8  465.93  5688.9   466.1
#Mann= 9 ,-1 , 0
  4591.2     .05       0  4778.5     .12       0  5000.1     .05       0
  5004.1     .12       0  5008.1     .07       0  5105.5     .05       0
  5265.3     .07       0  5327.5     .05       0  5665.8    .035       0
Bank Sta=5000.1,5004.1
XS Rating Curve= 0 ,0
Exp/Cntr=0.3,0.1

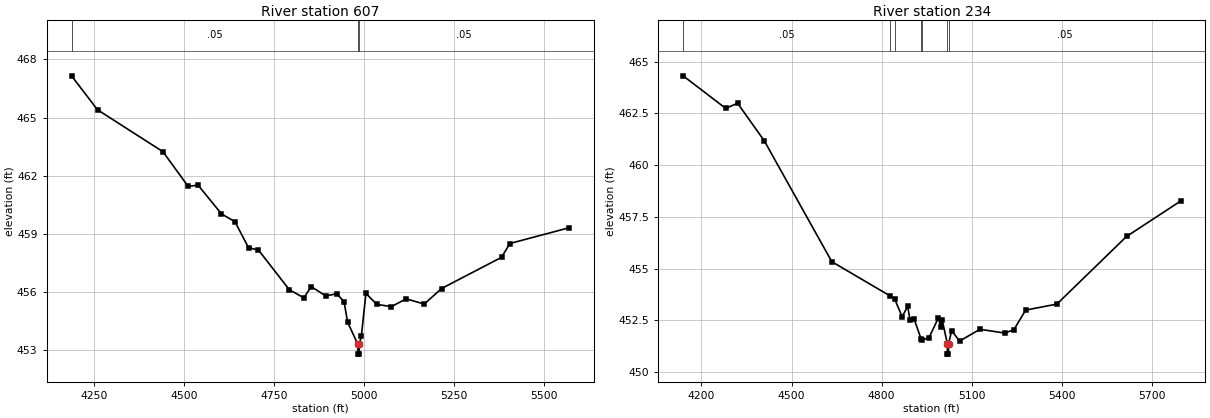
Type RM Length L Ch R = 1 ,607     ,373,373,373
BEGIN DESCRIPTION:
XS6708
END DESCRIPTION:
XS GIS Cut Line= 4
      2466874.02     13826875.25      2466316.58     13826701.62
      2465946.45      13826765.6      2465786.53     13827158.53
#Sta/Elev= 30
  4186.7  467.15    4259   465.4    4441  463.24  4511.3  461.45  4538.6  461.52
  4603.6  460.04  4641.4  459.63  4679.2  458.29  4706.4  458.18  4792.5  456.13
    4833  455.71  4853.3  456.29  4893.9  455.81  4924.4  455.92  4944.7  455.52
  4954.8  454.45  4983.3  453.31  4983.5  452.81    4987  452.81  4987.3  453.31
  4993.1  453.76  5005.6  455.94    5036  455.37  5076.6  455.26  5117.8  455.66
  5167.9  455.39    5216  456.19    5383   457.8    5406  458.51  5570.4  459.32
#Mann= 3 ,-1 , 0
  4186.7     .05       0  4983.3     .05       0  4987.3     .05       0
Bank Sta=4983.3,4987.3
XS Rating Curve= 0 ,0
Exp/Cntr=0.3,0.1

Type RM Length L Ch R = 1 ,234     ,0,0,0
BEGIN DESCRIPTION:
XS6707
END DESCRIPTION:
XS GIS Cut Line= 4
      2466860.37     13826678.79      2466184.06     13826363.48
      2465900.76     13826459.44      2465772.82       13827058.
#Sta/Elev= 30
  4138.9  464.32  4280.4  462.75  4320.6  462.99  4409.6  461.17  4634.4  455.33
  4828.1  453.68  4843.7  453.53  4868.6  452.67  4887.2  453.17  4894.7  452.52
    4908  452.58  4932.4  451.57  4933.3  451.54    4958  451.65  4989.7  452.62
    4997  452.16  5002.2  452.51  5019.4  451.36  5019.6  450.86  5023.1  450.86
  5023.4  451.36  5033.7     452  5059.8  451.49  5127.9  452.06  5210.4  451.88
    5241  452.04  5280.2  452.99  5384.3  453.28  5616.3  456.55  5796.3  458.26
#Mann= 7 ,-1 , 0
  4138.9     .05       0  4828.1     .12       0  4843.7     .07       0
  4932.4     .12       0  4933.3     .05       0  5019.4     .05       0
  5023.4     .05       0
Bank Sta=5019.4,5023.4
XS Rating Curve= 0 ,0
Exp/Cntr=0.3,0.1

Chan Stop Cuts=-1
Use User Specified Reach Order=0
Composite Channel Slope=5