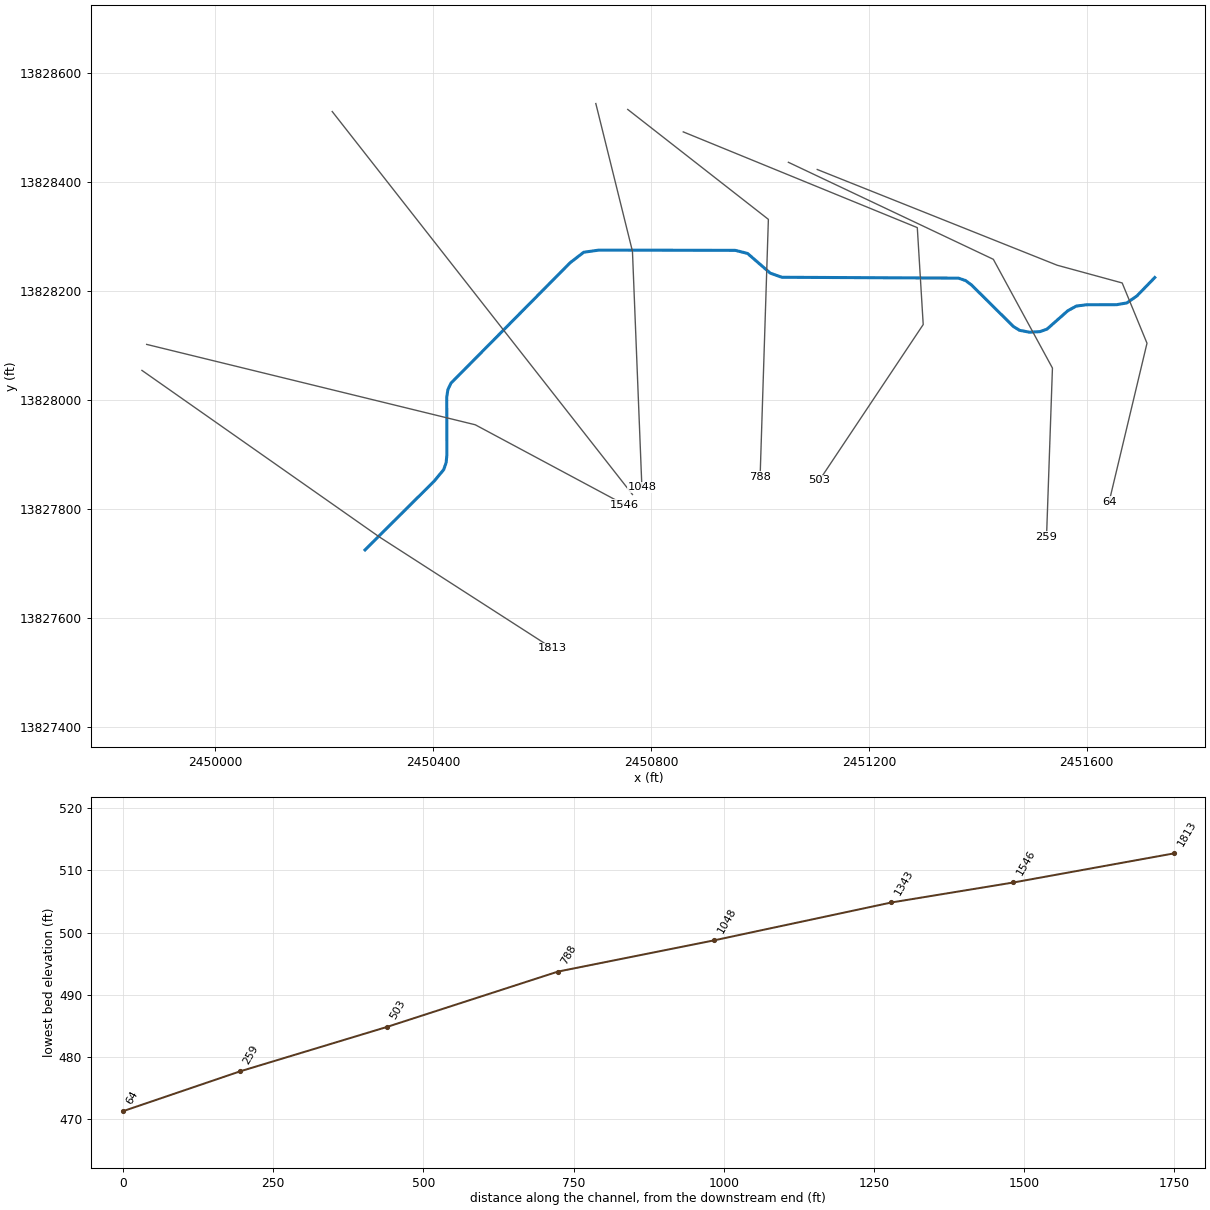
--- Stream0407.prj (project) ---

Proj Title=Stream0407 Base Level Engineering
Current Plan=p01
Default Exp/Contr=0.3,0.1
English Units
Geom File=g01
Flow File=f01
Plan File=p01
BEGIN DESCRIPTION:
Stream0407
END DESCRIPTION:

--- Stream0407.p01 (plan) ---

Plan Title=Multiple Run
Short Identifier=Multiple
Geom File=g01
Flow File=f01
Subcritical Flow
K Sum by GR= 0
Std Step Tol= 0.01
Critical Tol= 0.01
Num of Std Step Trials= 20
Max Error Tol= 0.3
Flow Tol Ratio= 0.001
Split Flow NTrial= 30
Split Flow Tol= 0.02
Split Flow Ratio= 0.02
Log Output Level= 0
Friction Slope Method= 1
Unsteady Friction Slope Method= 2
Unsteady Bridges Friction Slope Method= 1
Parabolic Critical Depth
Global Vel Dist=  1 , 1 , 1
Global Log Level= 0
CheckData=True
Encroach Param= -1, 0, 0, 0
BEGIN DESCRIPTION:
Multiple Run
END DESCRIPTION:

--- Stream0407.f01 (steady flow) ---

Flow Title=Multiple
Number of Profiles=7
Profile Names=10-year,25-year,50-year,1pct_min,100-year,1pct_plu,500-year
River Rch & RM= Stream0407,Reach-1,1813
     346     543     716     460     918    1832    1490
River Rch & RM= Stream0407,Reach-1,64
    1426    2401    3320    2219    4427    8833    7799
Boundary for River Rch & Prof#=Stream0407,Reach-1,1
Up Type=0
Dn Type=3
Dn Slope=0.005
Boundary for River Rch & Prof#=Stream0407,Reach-1,2
Up Type=0
Dn Type=3
Dn Slope=0.005
Boundary for River Rch & Prof#=Stream0407,Reach-1,3
Up Type=0
Dn Type=3
Dn Slope=0.005
Boundary for River Rch & Prof#=Stream0407,Reach-1,4
Up Type=0
Dn Type=3
Dn Slope=0.005
Boundary for River Rch & Prof#=Stream0407,Reach-1,5
Up Type=0
Dn Type=3
Dn Slope=0.005
Boundary for River Rch & Prof#=Stream0407,Reach-1,6
Up Type=0
Dn Type=3
Dn Slope=0.005
Boundary for River Rch & Prof#=Stream0407,Reach-1,7
Up Type=0
Dn Type=3
Dn Slope=0.005

--- Stream0407.g01 (geometry) ---

Geom Title=Existing Conditions

River Reach=Stream0407,Reach-1
Reach XY= 30
      2450275.00     13827725.00      2450402.15     13827851.47
      2450419.54     13827872.55      2450423.94     13827885.44
      2450425.27     13827899.89      2450424.98     13828005.01
      2450427.07     13828019.14      2450432.82     13828031.19
      2450651.47     13828252.14      2450676.46     13828271.46
      2450704.82     13828275.43      2450954.97     13828274.93
      2450977.33     13828269.25      2451018.94     13828233.14
      2451040.22     13828225.52      2451364.56     13828223.94
      2451377.45     13828219.52      2451388.31     13828211.60
      2451465.33     13828135.21      2451476.64     13828128.14
      2451495.13     13828124.61      2451514.29     13828125.72
      2451527.17     13828130.35      2451565.34     13828164.05
      2451580.95     13828172.65      2451599.97     13828175.05
      2451654.92     13828175.18      2451673.60     13828178.39
      2451692.05     13828191.12      2451725.00     13828225.00

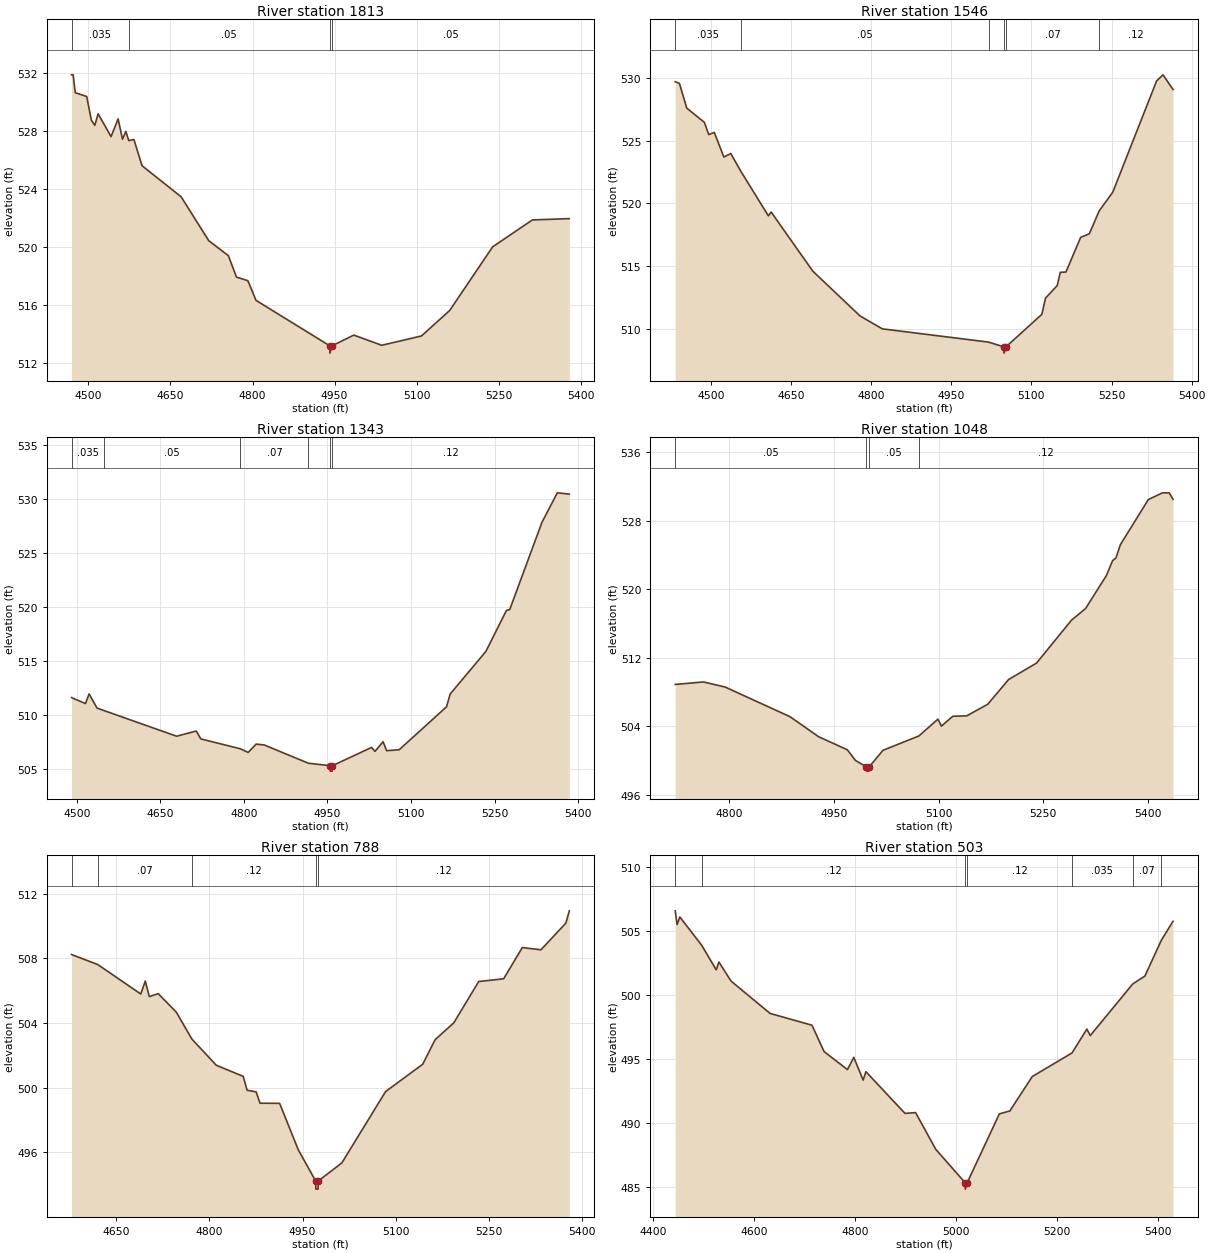
Type RM Length L Ch R = 1,1813,267,267,267
BEGIN DESCRIPTION:
XS6725
END DESCRIPTION:
XS GIS Cut Line= 3
      2449865.33     13828054.54      2450301.56     13827748.52
      2450618.41     13827544.53
#Sta/Elev= 30
  4469.3  531.85  4472.2  531.85  4476.1  530.62  4497.0  530.36  4505.5  528.73
  4511.8  528.38  4517.9  529.17  4541.5  527.60  4554.4  528.82  4562.4  527.42
  4568.5  527.96  4573.8  527.33  4583.3  527.40  4598.1  525.60  4669.6  523.46
  4720.1  520.44  4755.9  519.41  4770.7  517.94  4791.6  517.69  4806.4  516.34
  4941.3  513.21  4941.5  512.71  4945.3  513.21  4985.1  513.95  5036.2  513.25
  5108.8  513.89  5160.3  515.64  5238.9  520.02  5311.5  521.87  5379.0  521.96
#Mann=4,-1,0
  4469.3   0.035       0  4573.8    0.05       0  4941.3    0.05       0
  4945.3    0.05       0
Bank Sta=4941.3,4945.3
Exp/Cntr=0.3,0.1

Type RM Length L Ch R = 1,1546,203,203,203
BEGIN DESCRIPTION:
XS6724
END DESCRIPTION:
XS GIS Cut Line= 3
      2449874.02     13828102.26      2450477.34     13827954.69
      2450751.51     13827807.89
#Sta/Elev= 30
  4433.0  529.73  4440.8  529.60  4454.6  527.62  4487.6  526.48  4495.8  525.50
  4506.1  525.68  4524.1  523.71  4537.0  523.99  4556.0  522.56  4607.4  519.01
  4612.5  519.32  4690.6  514.59  4779.1  511.01  4820.7  509.98  5019.8  508.92
  5048.3  508.54  5048.6  508.04  5052.3  508.54  5119.5  511.14  5126.4  512.44
  5148.3  513.44  5154.0  514.50  5164.6  514.52  5192.2  517.29  5208.5  517.58
  5226.8  519.40  5252.3  520.90  5334.4  529.79  5346.4  530.28  5365.1  529.11
#Mann=6,-1,0
  4433.0   0.035       0  4556.0    0.05       0  5019.8    0.07       0
  5048.3    0.05       0  5052.3    0.07       0  5226.8    0.12       0
Bank Sta=5048.3,5052.3
Exp/Cntr=0.3,0.1

Type RM Length L Ch R = 1,1343,295,295,295
BEGIN DESCRIPTION:
XS6723
END DESCRIPTION:
XS GIS Cut Line= 2
      2450214.73     13828529.81      2450765.99     13827826.63
#Sta/Elev= 30
  4490.7  511.63  4515.7  511.08  4522.2  511.97  4536.5  510.66  4549.0  510.43
  4679.3  508.06  4714.6  508.54  4722.7  507.81  4793.6  506.90  4807.7  506.56
  4822.1  507.33  4836.6  507.25  4915.8  505.56  4954.8  505.33  4955.1  504.83
  4958.6  504.83  4958.8  505.33  5029.1  507.02  5035.5  506.66  5049.9  507.55
  5056.3  506.72  5078.9  506.81  5163.8  510.78  5170.3  511.96  5234.4  515.90
  5271.4  519.70  5277.2  519.77  5335.4  527.88  5362.7  530.57  5384.2  530.45
#Mann=6,-1,0
  4490.7   0.035       0  4549.0    0.05       0  4793.6    0.07       0
  4915.8    0.12       0  4954.8    0.05       0  4958.8    0.12       0
Bank Sta=4954.8,4958.8
Exp/Cntr=0.3,0.1

Type RM Length L Ch R = 1,1048,260,260,260
BEGIN DESCRIPTION:
XS6722
END DESCRIPTION:
XS GIS Cut Line= 3
      2450698.71     13828544.49      2450765.97     13828273.26
      2450783.32     13827839.65
#Sta/Elev= 30
  4722.5  508.88  4763.2  509.17  4794.1  508.57  4886.8  505.12  4928.0  502.77
  4969.2  501.24  4980.9  499.99  4996.5  499.25  4996.7  498.75  5000.2  498.75
  5000.5  499.25  5020.2  501.18  5071.7  502.86  5099.0  504.82  5104.0  504.01
  5120.3  505.16  5140.3  505.21  5170.3  506.56  5200.4  509.46  5240.4  511.38
  5290.4  516.39  5310.5  517.74  5340.5  521.61  5349.2  523.33  5354.2  523.67
  5360.5  525.21  5400.5  530.48  5420.5  531.26  5430.5  531.27  5435.9  530.52
#Mann=4,-1,0
  4722.5    0.05       0  4996.5    0.05       0  5000.5    0.05       0
  5071.7    0.12       0
Bank Sta=4996.5,5000.5
Exp/Cntr=0.3,0.1

Type RM Length L Ch R = 1,788,285,285,285
BEGIN DESCRIPTION:
XS6721
END DESCRIPTION:
XS GIS Cut Line= 3
      2450757.32     13828533.66      2451015.54     13828331.86
      2451000.37     13827859.42
#Sta/Elev= 30
  4578.6  508.23  4620.7  507.61  4689.9  505.79  4697.2  506.59  4703.6  505.63
  4718.0  505.81  4747.0  504.67  4772.0  503.01  4811.2  501.39  4854.6  500.70
  4860.9  499.84  4875.4  499.74  4881.7  499.04  4913.2  499.03  4943.2  496.16
  4971.2  494.23  4971.5  493.73  4975.0  493.73  4975.2  494.23  5013.2  495.35
  5083.6  499.76  5143.3  501.45  5163.3  502.97  5193.3  504.01  5233.3  506.56
  5273.4  506.73  5303.4  508.66  5333.4  508.52  5373.4  510.17  5379.0  510.93
#Mann=5,-1,0
  4578.6    0.05       0  4620.7    0.07       0  4772.0    0.12       0
  4971.2    0.05       0  4975.2    0.12       0
Bank Sta=4971.2,4975.2
Exp/Cntr=0.3,0.1

Type RM Length L Ch R = 1,503,244,244,244
BEGIN DESCRIPTION:
XS6720
END DESCRIPTION:
XS GIS Cut Line= 4
      2450859.26     13828492.46      2451288.98     13828316.67
      2451299.83     13828138.72      2451109.43     13827853.13
#Sta/Elev= 30
  4444.1  506.58  4447.7  505.51  4453.2  506.10  4496.8  503.87  4525.2  501.97
  4530.6  502.58  4554.6  501.09  4632.0  498.56  4714.9  497.64  4738.9  495.58
  4785.2  494.17  4797.7  495.13  4816.3  493.35  4821.7  494.01  4899.1  490.75
  4920.1  490.81  4960.1  487.94  5018.3  485.33  5018.5  484.83  5022.3  485.33
  5086.0  490.71  5106.8  490.94  5151.2  493.63  5229.8  495.47  5259.4  497.34
  5266.0  496.83  5350.3  500.87  5374.2  501.48  5406.9  504.29  5429.9  505.76
#Mann=7,-1,0
  4444.1    0.07       0  4496.8    0.12       0  5018.3    0.05       0
  5022.3    0.12       0  5229.8   0.035       0  5350.3    0.07       0
  5406.9   0.035       0
Bank Sta=5018.3,5022.3
Exp/Cntr=0.3,0.1

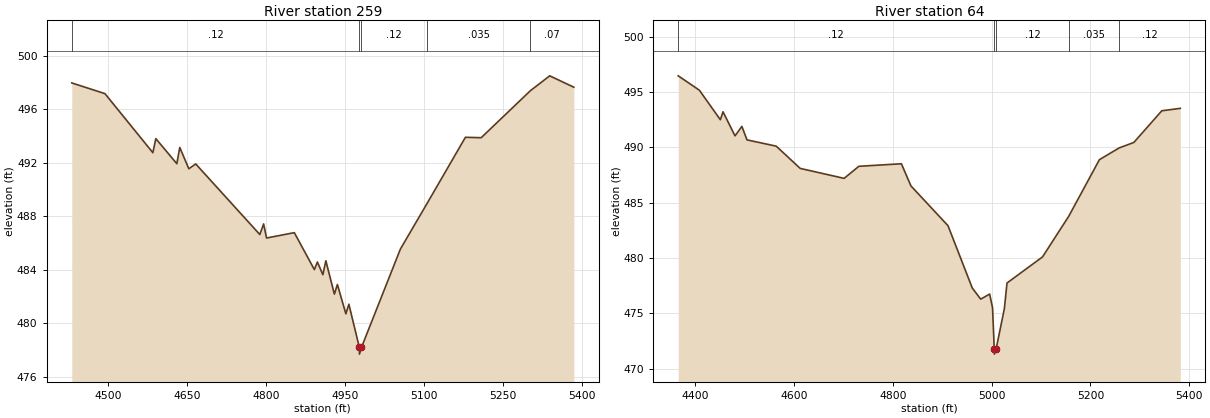
Type RM Length L Ch R = 1,259,195,195,195
BEGIN DESCRIPTION:
XS6719
END DESCRIPTION:
XS GIS Cut Line= 4
      2451052.28     13828436.63      2451428.60     13828258.49
      2451537.11     13828058.83      2451526.28     13827749.21
#Sta/Elev= 30
  4431.2  497.96  4494.2  497.16  4585.2  492.75  4590.8  493.80  4630.7  491.93
  4636.3  493.14  4653.5  491.55  4666.6  491.91  4788.3  486.64  4795.5  487.43
  4801.1  486.38  4853.8  486.78  4891.9  484.02  4897.6  484.59  4908.0  483.64
  4913.7  484.68  4929.9  482.19  4935.6  482.91  4951.7  480.72  4957.4  481.44
  4977.3  478.21  4977.5  477.71  4981.3  478.21  5055.3  485.56  5105.0  488.90
  5178.7  493.90  5208.7  493.87  5302.1  497.38  5338.8  498.49  5384.6  497.64
#Mann=5,-1,0
  4431.2    0.12       0  4977.3    0.05       0  4981.3    0.12       0
  5105.0   0.035       0  5302.1    0.07       0
Bank Sta=4977.3,4981.3
Exp/Cntr=0.3,0.1

Type RM Length L Ch R = 1,64,0,0,0
BEGIN DESCRIPTION:
E20997
END DESCRIPTION:
XS GIS Cut Line= 5
      2451105.26     13828423.41      2451545.79     13828247.64
      2451665.15     13828215.08      2451710.72     13828104.41
      2451641.27     13827813.60
#Sta/Elev= 30
  4365.3  496.47  4408.1  495.17  4450.6  492.50  4456.0  493.22  4480.3  491.04
  4494.2  491.90  4504.5  490.68  4563.8  490.11  4612.3  488.10  4701.2  487.20
  4731.1  488.29  4817.2  488.52  4836.5  486.52  4911.6  482.92  4960.7  477.29
  4977.8  476.28  4995.9  476.74  5001.8  475.50  5005.2  471.81  5005.5  471.31
  5009.2  471.81  5025.7  475.42  5031.1  477.74  5103.0  480.10  5156.3  483.79
  5218.2  488.89  5258.1  489.95  5288.0  490.45  5344.5  493.31  5382.0  493.53
#Mann=5,-1,0
  4365.3    0.12       0  5005.2    0.05       0  5009.2    0.12       0
  5156.3   0.035       0  5258.1    0.12       0
Bank Sta=5005.2,5009.2
Exp/Cntr=0.3,0.1

Chan Stop Cuts=-1