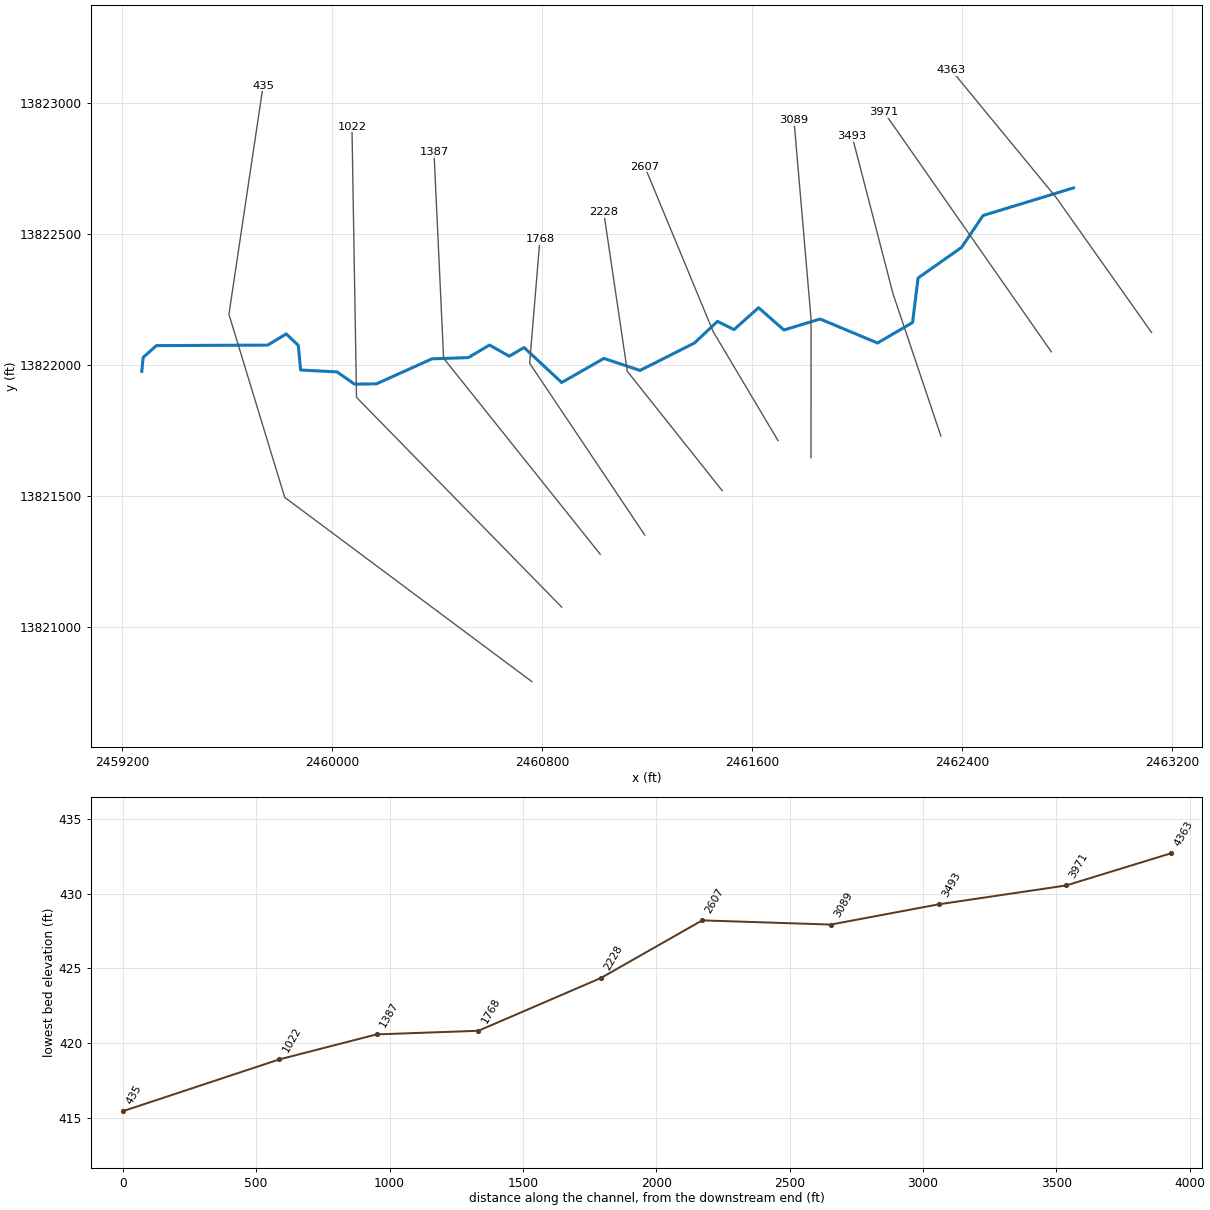
--- Stream0411.prj (project) ---

Proj Title=Stream0411 Base Level Engineering
Current Plan=p01
Default Exp/Contr=0.3,0.1
English Units
Geom File=g01
Flow File=f01
Plan File=p01
BEGIN DESCRIPTION:
Stream0411
END DESCRIPTION:

--- Stream0411.p01 (plan) ---

Plan Title=Multiple Run
Short Identifier=Multiple
Geom File=g01
Flow File=f01
Subcritical Flow
K Sum by GR= 0
Std Step Tol= 0.01
Critical Tol= 0.01
Num of Std Step Trials= 20
Max Error Tol= 0.3
Flow Tol Ratio= 0.001
Split Flow NTrial= 30
Split Flow Tol= 0.02
Split Flow Ratio= 0.02
Log Output Level= 0
Friction Slope Method= 1
Unsteady Friction Slope Method= 2
Unsteady Bridges Friction Slope Method= 1
Parabolic Critical Depth
Global Vel Dist=  1 , 1 , 1
Global Log Level= 0
CheckData=True
Encroach Param= -1, 0, 0, 0
BEGIN DESCRIPTION:
Multiple Run
END DESCRIPTION:

--- Stream0411.f01 (steady flow) ---

Flow Title=Multiple
Number of Profiles=7
Profile Names=10-year,25-year,50-year,1pct_min,100-year,1pct_plu,500-year
River Rch & RM= Stream0411,Reach-1,4363
     456     713     939     600    1196    2387    1920
Boundary for River Rch & Prof#=Stream0411,Reach-1,1
Up Type=0
Dn Type=3
Dn Slope=0.005
Boundary for River Rch & Prof#=Stream0411,Reach-1,2
Up Type=0
Dn Type=3
Dn Slope=0.005
Boundary for River Rch & Prof#=Stream0411,Reach-1,3
Up Type=0
Dn Type=3
Dn Slope=0.005
Boundary for River Rch & Prof#=Stream0411,Reach-1,4
Up Type=0
Dn Type=3
Dn Slope=0.005
Boundary for River Rch & Prof#=Stream0411,Reach-1,5
Up Type=0
Dn Type=3
Dn Slope=0.005
Boundary for River Rch & Prof#=Stream0411,Reach-1,6
Up Type=0
Dn Type=3
Dn Slope=0.005
Boundary for River Rch & Prof#=Stream0411,Reach-1,7
Up Type=0
Dn Type=3
Dn Slope=0.005

--- Stream0411.g01 (geometry) ---

Geom Title=Existing Conditions

River Reach=Stream0411,Reach-1
Reach XY= 30
      2462825.00     13822675.00      2462480.47     13822569.74
      2462398.51     13822448.00      2462232.81     13822331.21
      2462211.77     13822161.33      2462078.32     13822083.04
      2461859.72     13822174.61      2461721.58     13822132.83
      2461625.00     13822217.88      2461531.67     13822134.34
      2461468.34     13822165.68      2461381.06     13822083.18
      2461173.28     13821978.34      2461035.69     13822024.25
      2460874.91     13821932.29      2460731.67     13822065.70
      2460675.09     13822032.84      2460600.04     13822075.32
      2460519.07     13822027.30      2460380.94     13822022.73
      2460169.03     13821927.17      2460085.55     13821926.10
      2460019.05     13821972.72      2459880.08     13821980.05
      2459871.36     13822073.90      2459825.34     13822117.78
      2459755.02     13822075.19      2459330.69     13822073.07
      2459280.13     13822027.95      2459275.00     13821975.00

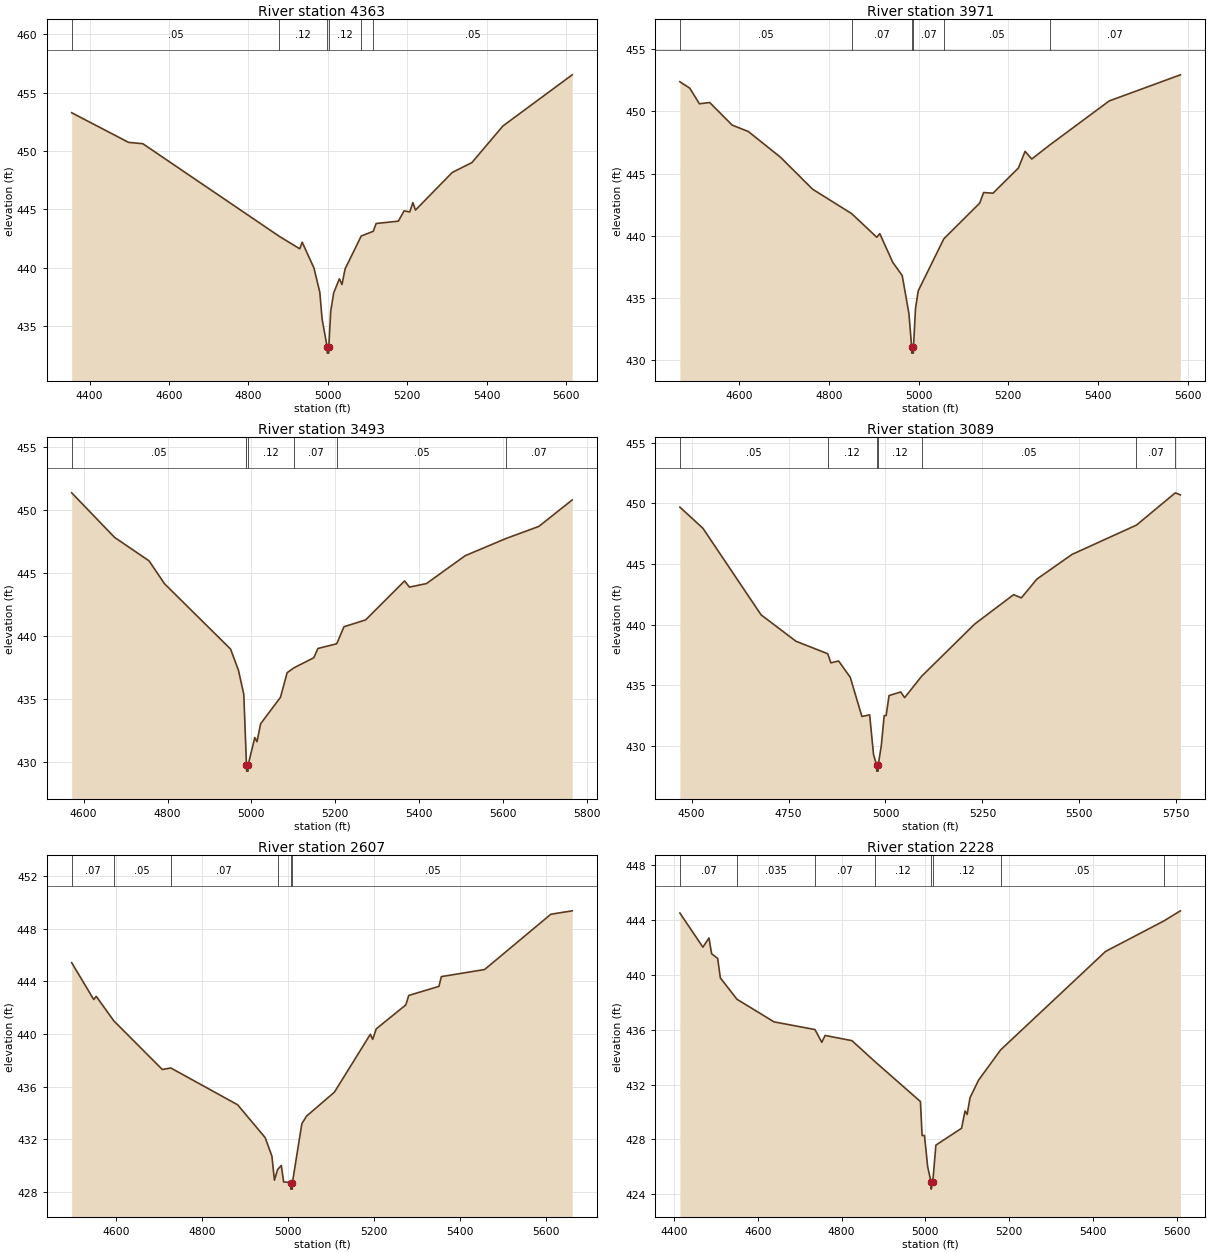
Type RM Length L Ch R = 1,4363,392,392,392
BEGIN DESCRIPTION:
XS6747
END DESCRIPTION:
XS GIS Cut Line= 3
      2463122.68     13822122.96      2462758.07     13822639.50
      2462359.36     13823124.88
#Sta/Elev= 30
  4354.9  453.28  4498.2  450.74  4533.9  450.63  4878.1  442.68  4929.2  441.62
  4935.3  442.19  4964.9  439.98  4979.7  437.90  4985.5  435.60  4998.3  433.18
  4998.6  432.68  5002.1  432.68  5002.3  433.18  5007.2  436.28  5014.7  437.85
  5029.0  439.05  5035.5  438.56  5043.4  439.90  5084.1  442.72  5114.2  443.12
  5121.6  443.79  5177.5  443.99  5191.9  444.87  5206.2  444.78  5214.1  445.58
  5220.6  444.94  5313.1  448.16  5362.7  449.01  5440.9  452.15  5615.3  456.53
#Mann=6,-1,0
  4354.9    0.05       0  4878.1    0.12       0  4998.3    0.05       0
  5002.3    0.12       0  5084.1    0.07       0  5114.2    0.05       0
Bank Sta=4998.3,5002.3
Exp/Cntr=0.3,0.1

Type RM Length L Ch R = 1,3971,478,478,478
BEGIN DESCRIPTION:
XS6746
END DESCRIPTION:
XS GIS Cut Line= 2
      2462740.69     13822049.24      2462102.69     13822965.01
#Sta/Elev= 30
  4467.8  452.39  4489.8  451.88  4511.4  450.62  4534.3  450.72  4584.5  448.90
  4620.7  448.38  4692.3  446.31  4763.8  443.74  4851.0  441.77  4906.9  439.87
  4913.6  440.16  4942.7  437.84  4963.6  436.79  4978.5  433.74  4984.7  431.04
  4984.9  430.54  4988.4  430.54  4988.7  431.04  4993.3  434.16  4999.4  435.56
  5056.3  439.74  5136.4  442.62  5145.1  443.47  5166.1  443.42  5222.8  445.45
  5237.6  446.79  5252.5  446.17  5292.6  447.30  5425.3  450.85  5583.9  452.95
#Mann=6,-1,0
  4467.8    0.05       0  4851.0    0.07       0  4984.7    0.05       0
  4988.7    0.07       0  5056.3    0.05       0  5292.6    0.07       0
Bank Sta=4984.7,4988.7
Exp/Cntr=0.3,0.1

Type RM Length L Ch R = 1,3493,404,404,404
BEGIN DESCRIPTION:
XS6745
END DESCRIPTION:
XS GIS Cut Line= 3
      2462319.72     13821728.00      2462137.41     13822270.57
      2461981.66     13822871.95
#Sta/Elev= 30
  4571.4  451.33  4673.7  447.80  4755.9  445.94  4792.7  444.13  4950.3  438.95
  4969.1  437.27  4981.8  435.37  4986.3  431.44  4988.2  429.78  4988.5  429.28
  4992.0  429.28  4992.2  429.78  5008.1  431.94  5013.3  431.61  5021.9  433.03
  5069.3  435.13  5085.2  437.08  5101.7  437.47  5148.6  438.26  5158.7  439.00
  5203.4  439.37  5220.7  440.72  5272.3  441.26  5365.3  444.35  5376.8  443.86
  5417.4  444.14  5509.9  446.35  5607.0  447.71  5685.5  448.67  5765.0  450.77
#Mann=7,-1,0
  4571.4    0.05       0  4986.3    0.12       0  4988.2    0.05       0
  4992.2    0.12       0  5101.7    0.07       0  5203.4    0.05       0
  5607.0    0.07       0
Bank Sta=4988.2,4992.2
Exp/Cntr=0.3,0.1

Type RM Length L Ch R = 1,3089,482,482,482
BEGIN DESCRIPTION:
Stream0411 7.0
END DESCRIPTION:
XS GIS Cut Line= 3
      2461824.91     13821645.59      2461825.00     13822175.00
      2461759.91     13822933.50
#Sta/Elev= 30
  4469.8  449.70  4529.2  447.96  4679.2  440.82  4769.2  438.64  4851.1  437.61
  4859.2  436.86  4879.2  437.01  4909.2  435.67  4939.2  432.44  4959.2  432.57
  4969.2  429.30  4977.2  428.43  4977.5  427.93  4981.0  427.93  4981.2  428.43
  4989.2  430.02  4996.7  432.51  5001.7  432.51  5009.2  434.16  5039.4  434.46
  5049.4  433.99  5093.1  435.75  5230.1  440.06  5330.4  442.48  5350.5  442.22
  5390.6  443.77  5481.0  445.80  5647.3  448.22  5747.5  450.88  5760.5  450.71
#Mann=7,-1,0
  4469.8    0.05       0  4851.1    0.12       0  4977.2    0.05       0
  4981.2    0.12       0  5093.1    0.05       0  5647.3    0.07       0
  5747.5    0.05       0
Bank Sta=4977.2,4981.2
Exp/Cntr=0.3,0.1

Type RM Length L Ch R = 1,2607,379,379,379
BEGIN DESCRIPTION:
Stream0411 6.0
END DESCRIPTION:
XS GIS Cut Line= 3
      2461699.06     13821710.65      2461451.65     13822127.34
      2461191.23     13822756.69
#Sta/Elev= 30
  4496.2  445.42  4547.5  442.62  4553.4  442.86  4594.3  441.00  4707.3  437.30
  4726.9  437.42  4882.7  434.62  4946.9  432.12  4962.5  430.72  4968.4  428.89
  4975.8  429.70  4984.4  430.01  4989.8  428.76  5006.3  428.71  5006.5  428.21
  5010.0  428.21  5010.3  428.71  5032.2  433.18  5043.2  433.76  5108.1  435.58
  5191.8  439.98  5197.2  439.59  5205.5  440.39  5274.3  442.21  5281.3  442.93
  5351.5  443.62  5357.1  444.36  5457.9  444.90  5612.1  449.10  5661.9  449.36
#Mann=6,-1,0
  4496.2    0.07       0  4594.3    0.05       0  4726.9    0.07       0
  4975.8    0.05       0  5006.3    0.05       0  5010.3    0.05       0
Bank Sta=5006.3,5010.3
Exp/Cntr=0.3,0.1

Type RM Length L Ch R = 1,2228,460,460,460
BEGIN DESCRIPTION:
Stream0411 5.0
END DESCRIPTION:
XS GIS Cut Line= 3
      2461486.39     13821519.68      2461125.00     13821975.00
      2461035.20     13822581.58
#Sta/Elev= 30
  4414.0  444.51  4469.0  442.02  4483.4  442.69  4489.8  441.54  4504.2  441.20
  4510.6  439.78  4550.2  438.22  4638.8  436.57  4736.4  436.01  4752.7  435.08
  4760.6  435.58  4824.7  435.20  4880.0  433.66  4988.1  430.76  4992.1  428.28
  4997.8  428.28  5005.4  426.00  5013.5  424.87  5013.8  424.37  5017.5  424.87
  5025.0  427.58  5086.3  428.81  5094.5  430.07  5099.6  429.82  5106.5  431.04
  5126.7  432.31  5179.3  434.52  5430.0  441.71  5568.4  443.92  5608.5  444.67
#Mann=8,-1,0
  4414.0    0.07       0  4550.2   0.035       0  4736.4    0.07       0
  4880.0    0.12       0  5013.5    0.05       0  5017.5    0.12       0
  5179.3    0.05       0  5568.4    0.07       0
Bank Sta=5013.5,5017.5
Exp/Cntr=0.3,0.1

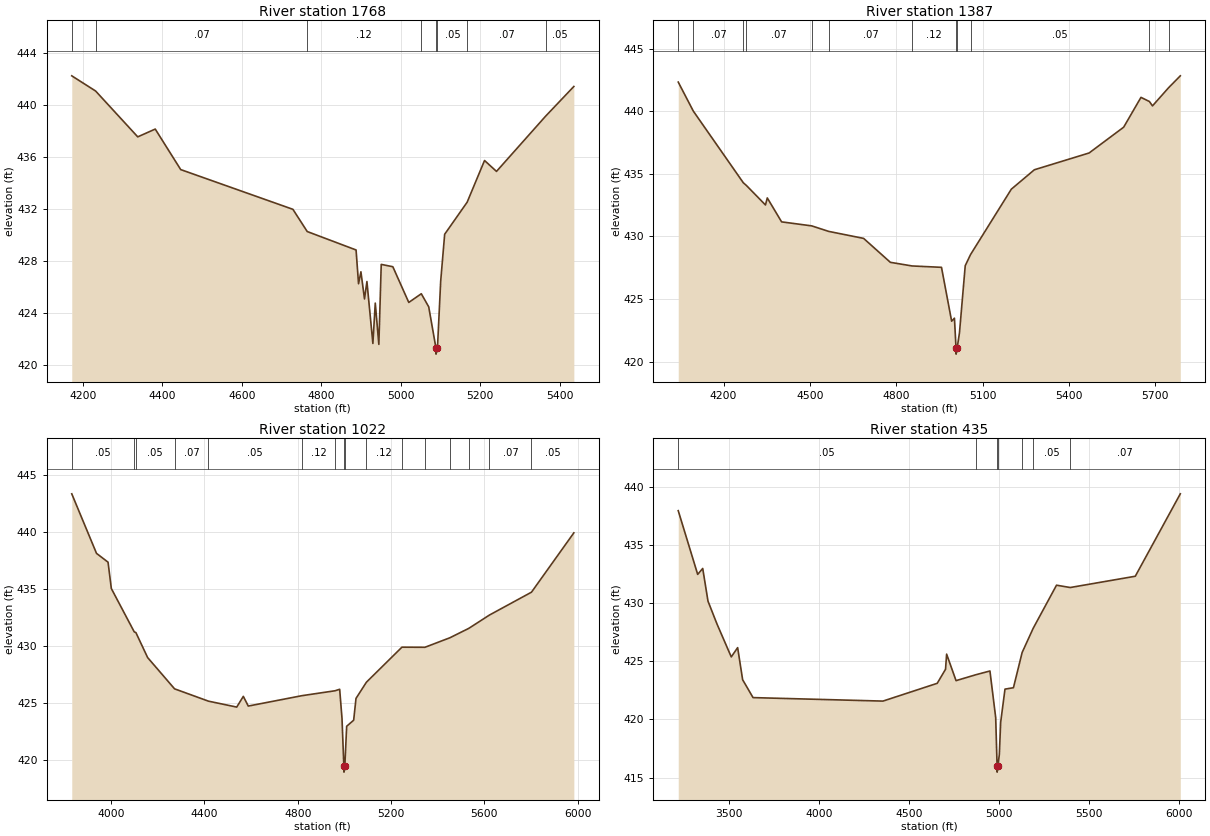
Type RM Length L Ch R = 1,1768,381,381,381
BEGIN DESCRIPTION:
Stream0411 4.0
END DESCRIPTION:
XS GIS Cut Line= 3
      2461191.25     13821350.41      2460752.86     13822005.82
      2460791.93     13822478.90
#Sta/Elev= 30
  4172.4  442.27  4232.4  441.10  4338.4  437.57  4382.4  438.17  4446.5  435.05
  4728.8  431.99  4764.8  430.28  4887.7  428.86  4893.9  426.26  4899.9  427.18
  4908.9  425.09  4915.0  426.43  4930.0  421.66  4936.0  424.77  4945.0  421.59
  4951.0  427.75  4980.2  427.57  5020.3  424.82  5051.8  425.49  5070.5  424.48
  5088.5  421.34  5088.8  420.84  5092.5  421.34  5100.6  426.46  5110.6  430.07
  5167.2  432.54  5210.9  435.75  5241.0  434.91  5364.5  439.16  5435.6  441.45
#Mann=8,-1,0
  4172.4   0.035       0  4232.4    0.07       0  4764.8    0.12       0
  5051.8    0.05       0  5088.5    0.05       0  5092.5    0.05       0
  5167.2    0.07       0  5364.5    0.05       0
Bank Sta=5088.5,5092.5
Exp/Cntr=0.3,0.1

Type RM Length L Ch R = 1,1387,365,365,365
BEGIN DESCRIPTION:
Stream0411 3.0
END DESCRIPTION:
XS GIS Cut Line= 3
      2461021.95     13821276.66      2460425.00     13822025.00
      2460388.35     13822811.58
#Sta/Elev= 30
  4042.4  442.32  4094.9  440.00  4268.6  434.28  4279.1  434.07  4345.5  432.51
  4351.9  433.07  4401.6  431.16  4506.2  430.84  4565.1  430.40  4686.6  429.84
  4779.5  427.93  4854.9  427.64  4957.2  427.53  4992.5  423.23  5002.2  423.47
  5007.7  421.10  5007.9  420.60  5011.7  421.10  5019.7  422.30  5039.7  427.66
  5058.2  428.55  5199.9  433.77  5280.0  435.32  5470.2  436.66  5590.3  438.72
  5650.4  441.10  5679.7  440.77  5690.4  440.42  5746.4  441.87  5787.1  442.82
#Mann=12,-1,0
  4042.4    0.05       0  4094.9    0.07       0  4268.6    0.05       0
  4279.1    0.07       0  4506.2    0.05       0  4565.1    0.07       0
  4854.9    0.12       0  5007.7    0.05       0  5011.7    0.12       0
  5058.2    0.05       0  5679.7    0.07       0  5746.4    0.05       0
Bank Sta=5007.7,5011.7
Exp/Cntr=0.3,0.1

Type RM Length L Ch R = 1,1022,587,587,587
BEGIN DESCRIPTION:
Stream0411 2.0
END DESCRIPTION:
XS GIS Cut Line= 3
      2460874.98     13821075.02      2460093.14     13821875.61
      2460075.78     13822908.64
#Sta/Elev= 30
  3831.4  443.32  3937.5  438.10  3986.9  437.33  4001.0  435.02  4099.3  431.22
  4106.3  431.16  4156.6  428.97  4272.0  426.23  4417.2  425.15  4538.5  424.63
  4566.8  425.57  4588.0  424.72  4818.2  425.63  4959.9  426.06  4979.8  426.19
  4989.8  423.63  4997.8  419.43  4998.1  418.93  5001.8  419.43  5009.8  422.95
  5039.8  423.48  5049.8  425.39  5094.4  426.81  5246.7  429.88  5345.1  429.87
  5451.7  430.70  5533.4  431.53  5621.3  432.69  5802.0  434.70  5983.6  439.90
#Mann=16,-1,0
  3831.4    0.05       0  4099.3    0.07       0  4106.3    0.05       0
  4272.0    0.07       0  4417.2    0.05       0  4818.2    0.12       0
  4959.9     0.1       0  4997.8    0.05       0  5001.8     0.1       0
  5094.4    0.12       0  5246.7    0.07       0  5345.1    0.05       0
  5451.7    0.07       0  5533.4    0.05       0  5621.3    0.07       0
  5802.0    0.05       0
Bank Sta=4997.8,5001.8
Exp/Cntr=0.3,0.1

Type RM Length L Ch R = 1,435,0,0,0
BEGIN DESCRIPTION:
Stream0411 1.0
END DESCRIPTION:
XS GIS Cut Line= 4
      2460761.56     13820790.53      2459819.70     13821493.66
      2459607.03     13822192.45      2459737.25     13823064.89
#Sta/Elev= 30
  3217.0  437.96  3325.0  432.48  3353.0  432.99  3382.2  430.18  3432.3  428.21
  3511.5  425.38  3546.9  426.18  3574.6  423.42  3632.4  421.88  4353.7  421.58
  4655.1  423.11  4701.3  424.32  4707.3  425.62  4759.6  423.34  4870.2  423.85
  4947.8  424.17  4979.8  420.16  4987.6  415.97  4987.8  415.47  4991.6  415.97
  5000.0  416.98  5007.4  419.76  5031.4  422.61  5078.3  422.73  5126.6  425.76
  5187.9  427.84  5317.5  431.55  5393.6  431.35  5754.9  432.32  6004.9  439.41
#Mann=7,-1,0
  3217.0    0.05       0  4870.2     0.1       0  4987.6    0.05       0
  4991.6     0.1       0  5126.6    0.12       0  5187.9    0.05       0
  5393.6    0.07       0
Bank Sta=4987.6,4991.6
Exp/Cntr=0.3,0.1

Chan Stop Cuts=-1