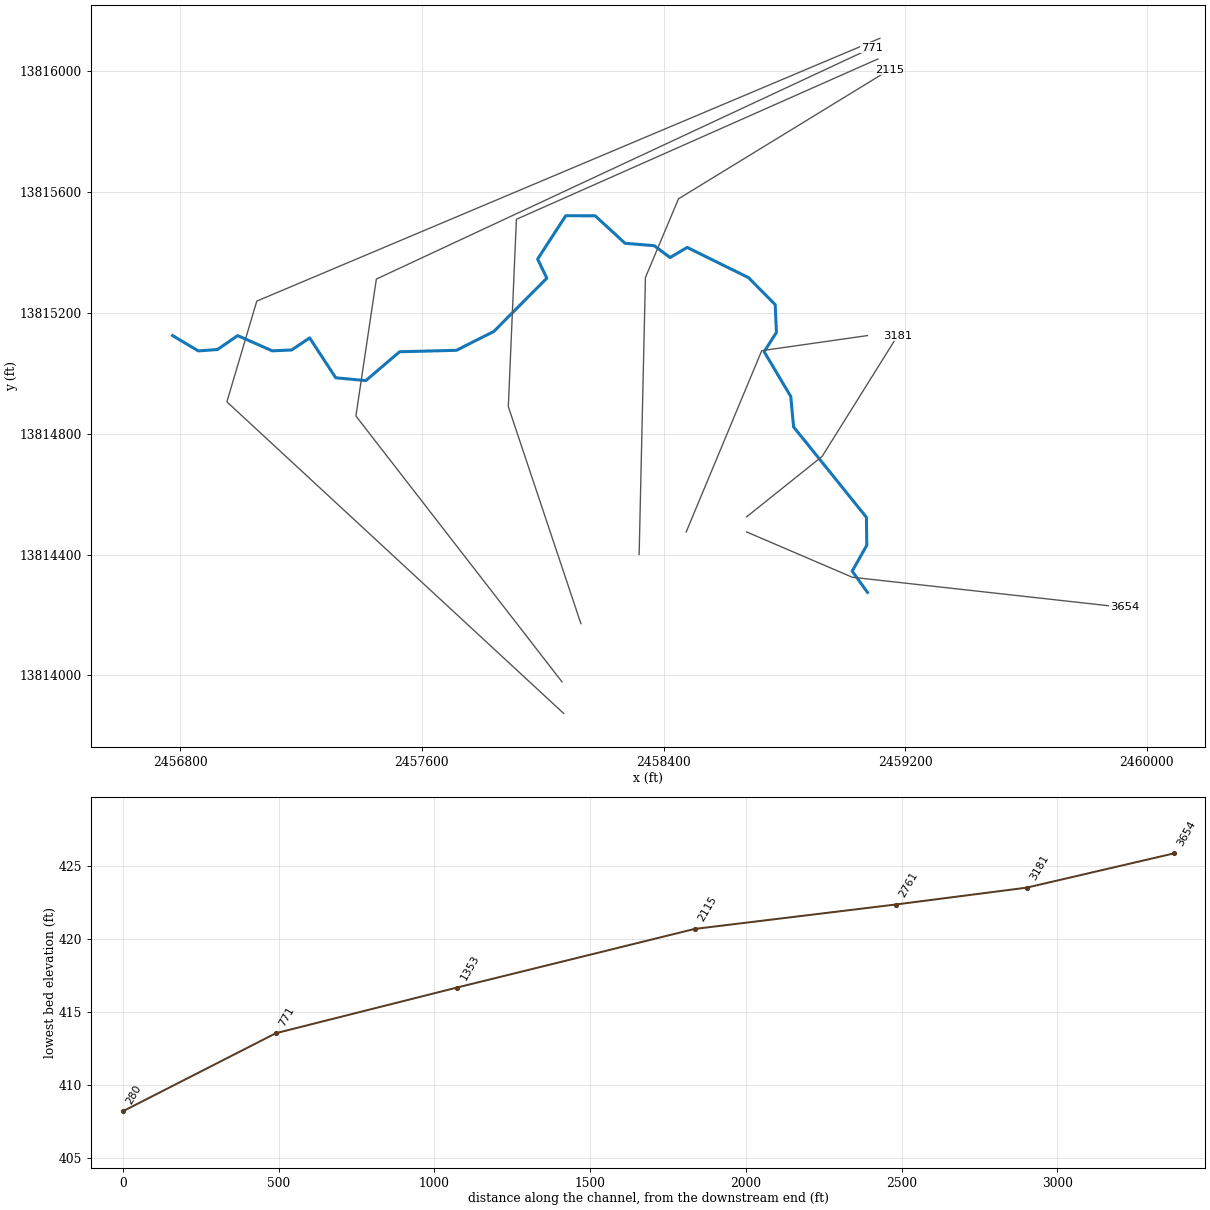
--- Stream0414.prj (project) ---

Proj Title=Stream0414 Base Level Engineering
Current Plan=p01
Default Exp/Contr=0.3,0.1
English Units
Geom File=g01
Flow File=f01
Plan File=p01
BEGIN DESCRIPTION:
Stream0414
END DESCRIPTION:

--- Stream0414.p01 (plan) ---

Plan Title=Multiple Run
Short Identifier=Multiple
Geom File=g01
Flow File=f01
Subcritical Flow
K Sum by GR= 0
Std Step Tol= 0.01
Critical Tol= 0.01
Num of Std Step Trials= 20
Max Error Tol= 0.3
Flow Tol Ratio= 0.001
Split Flow NTrial= 30
Split Flow Tol= 0.02
Split Flow Ratio= 0.02
Log Output Level= 0
Friction Slope Method= 1
Unsteady Friction Slope Method= 2
Unsteady Bridges Friction Slope Method= 1
Parabolic Critical Depth
Global Vel Dist=  1 , 1 , 1
Global Log Level= 0
CheckData=True
Encroach Param= -1, 0, 0, 0
BEGIN DESCRIPTION:
Multiple Run
END DESCRIPTION:

--- Stream0414.f01 (steady flow) ---

Flow Title=Multiple
Number of Profiles=7
Profile Names=10-year,25-year,50-year,1pct_min,100-year,1pct_plu,500-year
River Rch & RM= Stream0414,Reach-1,3654
     185     271     341     209     416     830     611
Boundary for River Rch & Prof#=Stream0414,Reach-1,1
Up Type=0
Dn Type=3
Dn Slope=0.005
Boundary for River Rch & Prof#=Stream0414,Reach-1,2
Up Type=0
Dn Type=3
Dn Slope=0.005
Boundary for River Rch & Prof#=Stream0414,Reach-1,3
Up Type=0
Dn Type=3
Dn Slope=0.005
Boundary for River Rch & Prof#=Stream0414,Reach-1,4
Up Type=0
Dn Type=3
Dn Slope=0.005
Boundary for River Rch & Prof#=Stream0414,Reach-1,5
Up Type=0
Dn Type=3
Dn Slope=0.005
Boundary for River Rch & Prof#=Stream0414,Reach-1,6
Up Type=0
Dn Type=3
Dn Slope=0.005
Boundary for River Rch & Prof#=Stream0414,Reach-1,7
Up Type=0
Dn Type=3
Dn Slope=0.005

--- Stream0414.g01 (geometry) ---

Geom Title=Existing Conditions

River Reach=Stream0414,Reach-1
Reach XY= 30
      2459075.00     13814275.00      2459024.45     13814345.21
      2459072.82     13814430.96      2459071.53     13814523.50
      2458830.52     13814822.57      2458821.17     13814923.41
      2458733.05     13815071.68      2458773.74     13815135.49
      2458769.61     13815227.44      2458681.08     13815316.87
      2458478.23     13815416.76      2458421.78     13815383.28
      2458369.11     13815422.45      2458272.58     13815430.54
      2458173.50     13815521.53      2458076.28     13815521.63
      2457983.25     13815378.23      2458013.76     13815315.00
      2457838.22     13815138.62      2457714.50     13815076.20
      2457526.47     13815071.45      2457414.51     13814975.93
      2457314.90     13814985.31      2457228.67     13815117.30
      2457169.12     13815077.38      2457104.95     13815074.43
      2456990.39     13815124.91      2456923.43     13815078.73
      2456859.96     13815074.27      2456775.00     13815125.00

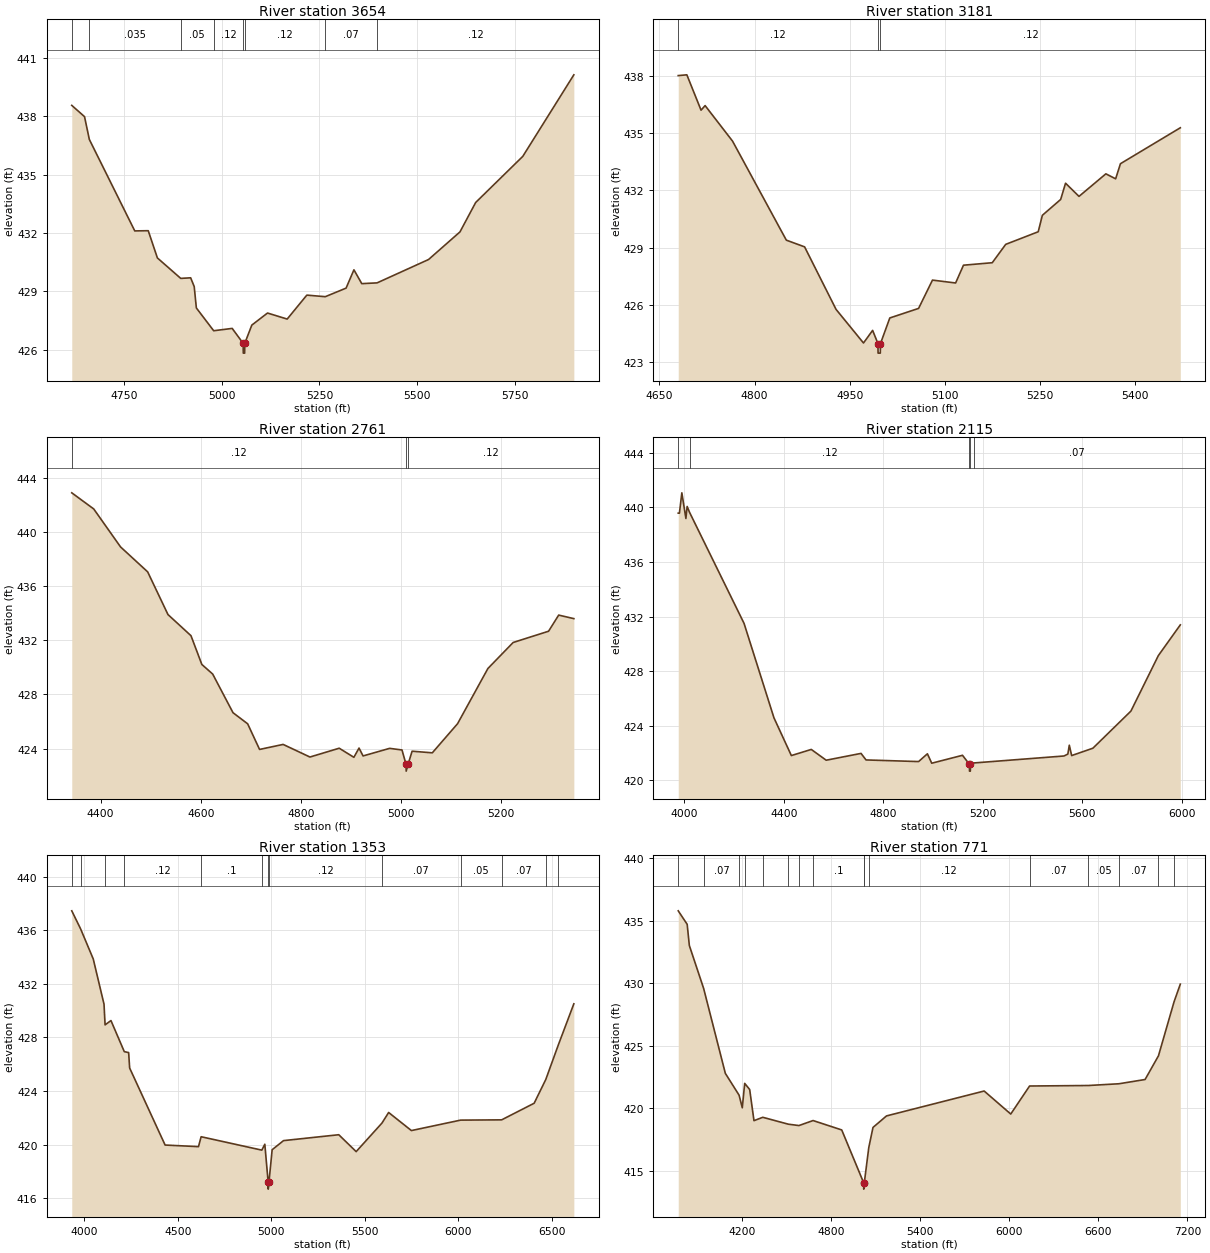
Type RM Length L Ch R = 1,3654,473,473,473
BEGIN DESCRIPTION:
Stream0414 5.0
END DESCRIPTION:
XS GIS Cut Line= 3
      2458674.98     13814475.01      2459025.00     13814325.00
      2459924.95     13814225.01
#Sta/Elev= 30
  4615.5  438.56  4648.2  437.98  4660.5  436.81  4776.9  432.11  4811.4  432.12
  4834.9  430.72  4894.7  429.67  4920.1  429.70  4929.2  429.25  4934.7  428.15
  4979.1  426.98  5026.5  427.10  5054.7  426.33  5054.9  425.83  5058.4  425.83
  5058.7  426.33  5076.8  427.27  5117.0  427.89  5167.4  427.58  5217.7  428.81
  5265.0  428.73  5318.3  429.17  5338.4  430.11  5358.5  429.40  5397.8  429.44
  5529.6  430.64  5610.1  432.06  5650.3  433.57  5771.0  435.94  5901.8  440.13
#Mann=8,-1,0
  4615.5    0.12       0  4660.5   0.035       0  4894.7    0.05       0
  4979.1    0.12       0  5054.7    0.05       0  5058.7    0.12       0
  5265.0    0.07       0  5397.8    0.12       0
Bank Sta=5054.7,5058.7
Exp/Cntr=0.3,0.1

Type RM Length L Ch R = 1,3181,420,420,420
BEGIN DESCRIPTION:
Stream0414 4.0
END DESCRIPTION:
XS GIS Cut Line= 3
      2458674.98     13814524.98      2458925.00     13814725.00
      2459175.01     13815125.02
#Sta/Elev= 30
  4679.6  438.01  4693.2  438.05  4715.6  436.20  4722.0  436.44  4765.3  434.58
  4850.1  429.40  4878.9  429.05  4928.5  425.78  4971.8  424.02  4986.2  424.68
  4994.6  423.99  4994.8  423.49  4998.3  423.49  4998.6  423.99  5013.3  425.33
  5058.7  425.83  5080.6  427.31  5117.1  427.16  5129.5  428.09  5174.9  428.22
  5196.1  429.18  5247.4  429.84  5253.9  430.70  5282.8  431.53  5290.5  432.38
  5311.7  431.69  5354.1  432.87  5369.5  432.61  5377.1  433.40  5471.5  435.28
#Mann=3,-1,0
  4679.6    0.12       0  4994.6    0.05       0  4998.6    0.12       0
Bank Sta=4994.6,4998.6
Exp/Cntr=0.3,0.1

Type RM Length L Ch R = 1,2761,646,646,646
BEGIN DESCRIPTION:
Stream0414 3.0
END DESCRIPTION:
XS GIS Cut Line= 3
      2458475.00     13814474.99      2458725.00     13815075.00
      2459075.04     13815125.01
#Sta/Elev= 30
  4342.2  442.87  4386.1  441.68  4439.7  438.88  4493.9  437.04  4534.5  433.89
  4580.5  432.33  4602.2  430.21  4623.9  429.50  4664.5  426.65  4693.8  425.83
  4717.6  423.94  4764.7  424.31  4818.3  423.38  4876.8  424.03  4906.1  423.36
  4916.4  424.04  4924.5  423.46  4977.6  424.02  5002.3  423.90  5010.4  422.84
  5010.7  422.34  5014.4  422.84  5022.5  423.81  5062.9  423.69  5113.4  425.84
  5174.0  429.91  5224.5  431.83  5295.3  432.66  5315.5  433.85  5345.8  433.59
#Mann=3,-1,0
  4342.2    0.12       0  5010.4    0.05       0  5014.4    0.12       0
Bank Sta=5010.4,5014.4
Exp/Cntr=0.3,0.1

Type RM Length L Ch R = 1,2115,762,762,762
BEGIN DESCRIPTION:
Stream0414 2.0
END DESCRIPTION:
XS GIS Cut Line= 4
      2458319.27     13814400.55      2458340.10     13815317.19
      2458449.48     13815577.60      2459147.44     13816004.71
#Sta/Elev= 30
  3975.8  439.58  3980.5  439.58  3990.3  441.07  4006.6  439.19  4011.6  440.07
  4021.3  439.64  4240.3  431.50  4360.4  424.58  4430.4  421.81  4510.4  422.26
  4570.4  421.47  4710.4  421.97  4730.4  421.49  4941.6  421.37  4977.1  421.94
  4994.5  421.25  5118.1  421.83  5145.9  421.17  5146.2  420.67  5149.7  420.67
  5149.9  421.17  5164.7  421.27  5526.0  421.78  5541.5  421.92  5547.3  422.57
  5556.8  421.81  5642.1  422.35  5794.9  425.07  5905.2  429.14  5993.4  431.39
#Mann=5,-1,0
  3975.8   0.035       0  4021.3    0.12       0  5145.9    0.05       0
  5149.9    0.12       0  5164.7    0.07       0
Bank Sta=5145.9,5149.9
Exp/Cntr=0.3,0.1

Type RM Length L Ch R = 1,1353,582,582,582
BEGIN DESCRIPTION:
Stream0414 1.0
END DESCRIPTION:
XS GIS Cut Line= 4
      2458126.57     13814171.33      2457886.23     13814889.86
      2457913.02     13815509.90      2459109.19     13816040.37
#Sta/Elev= 30
  3932.4  437.44  3979.5  436.10  4047.3  433.85  4105.0  430.47  4110.7  428.93
  4142.1  429.25  4213.5  426.93  4236.8  426.86  4242.1  425.71  4431.9  419.96
  4610.5  419.84  4624.7  420.58  4949.5  419.58  4965.5  420.02  4983.5  417.17
  4983.7  416.67  4987.5  417.17  5004.7  419.61  5065.6  420.29  5361.2  420.73
  5454.3  419.47  5592.4  421.60  5628.1  422.39  5749.9  421.04  6013.3  421.82
  6232.9  421.84  6406.8  423.08  6469.0  424.85  6535.6  427.41  6619.2  430.50
#Mann=13,-1,0
  3932.4    0.12       0  3979.5    0.07       0  4110.7   0.035       0
  4213.5    0.12       0  4624.7     0.1       0  4949.5    0.12       0
  4983.5    0.05       0  4987.5    0.12       0  5592.4    0.07       0
  6013.3    0.05       0  6232.9    0.07       0  6469.0    0.05       0
  6535.6    0.07       0
Bank Sta=4983.5,4987.5
Exp/Cntr=0.3,0.1

Type RM Length L Ch R = 1,771,491,491,491
BEGIN DESCRIPTION:
XS6757
END DESCRIPTION:
XS GIS Cut Line= 4
      2458064.08     13813978.62      2457381.77     13814858.85
      2457449.48     13815311.98      2459090.06     13816077.58
#Sta/Elev= 30
  3769.4  435.79  3829.7  434.71  3844.2  433.02  3940.5  429.59  4086.8  422.80
  4179.3  421.06  4200.9  420.05  4217.1  422.00  4250.7  421.51  4279.7  419.02
  4338.9  419.29  4510.9  418.74  4582.5  418.63  4677.8  419.03  4870.8  418.28
  5018.8  414.05  5019.0  413.55  5022.8  414.05  5053.2  416.88  5081.4  418.48
  5172.4  419.40  5830.3  421.39  6009.5  419.55  6136.3  421.79  6531.4  421.83
  6738.4  421.97  6914.4  422.31  7004.4  424.20  7109.6  428.52  7151.7  429.93
#Mann=16,-1,0
  3769.4    0.12       0  3940.5    0.07       0  4179.3    0.05       0
  4217.1   0.035       0  4338.9    0.12       0  4510.9   0.035       0
  4582.5    0.12       0  4677.8     0.1       0  5018.8    0.05       0
  5022.8     0.1       0  5053.2    0.12       0  6136.3    0.07       0
  6531.4    0.05       0  6738.4    0.07       0  7004.4    0.05       0
  7109.6    0.07       0
Bank Sta=5018.8,5022.8
Exp/Cntr=0.3,0.1

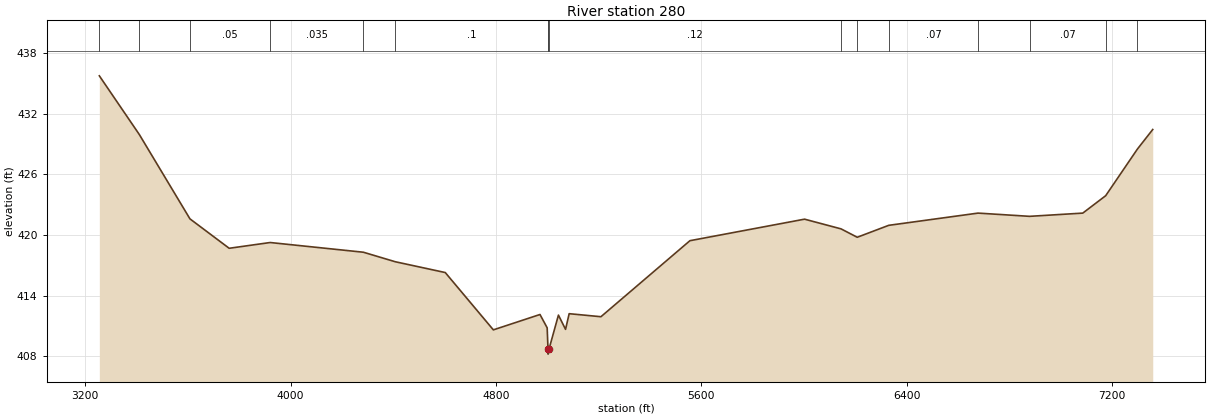
Type RM Length L Ch R = 1,280,0,0,0
BEGIN DESCRIPTION:
XS6758
END DESCRIPTION:
XS GIS Cut Line= 4
      2458069.28     13813874.47      2456954.69     13814905.73
      2457053.65     13815239.06      2459116.14     13816108.85
#Sta/Elev= 30
  3254.8  435.75  3410.7  429.94  3607.9  421.60  3760.7  418.69  3920.4  419.26
  4283.7  418.30  4407.7  417.36  4602.7  416.29  4790.1  410.62  4971.8  412.14
  4999.8  410.82  5001.7  409.57  5003.0  408.72  5003.3  408.22  5007.0  408.72
  5043.7  412.08  5071.4  410.67  5085.5  412.22  5209.3  411.92  5556.0  419.44
  6002.7  421.57  6144.9  420.61  6208.0  419.78  6330.6  420.96  6678.8  422.17
  6879.5  421.85  7086.8  422.17  7176.0  423.89  7299.8  428.51  7359.4  430.44
#Mann=16,-1,0
  3254.8    0.12       0  3410.7    0.07       0  3607.9    0.05       0
  3920.4   0.035       0  4283.7    0.12       0  4407.7     0.1       0
  5001.7    0.12       0  5003.0    0.05       0  5007.0    0.12       0
  6144.9   0.035       0  6208.0    0.12       0  6330.6    0.07       0
  6678.8    0.05       0  6879.5    0.07       0  7176.0    0.05       0
  7299.8    0.07       0
Bank Sta=5003,5007
Exp/Cntr=0.3,0.1

Chan Stop Cuts=-1