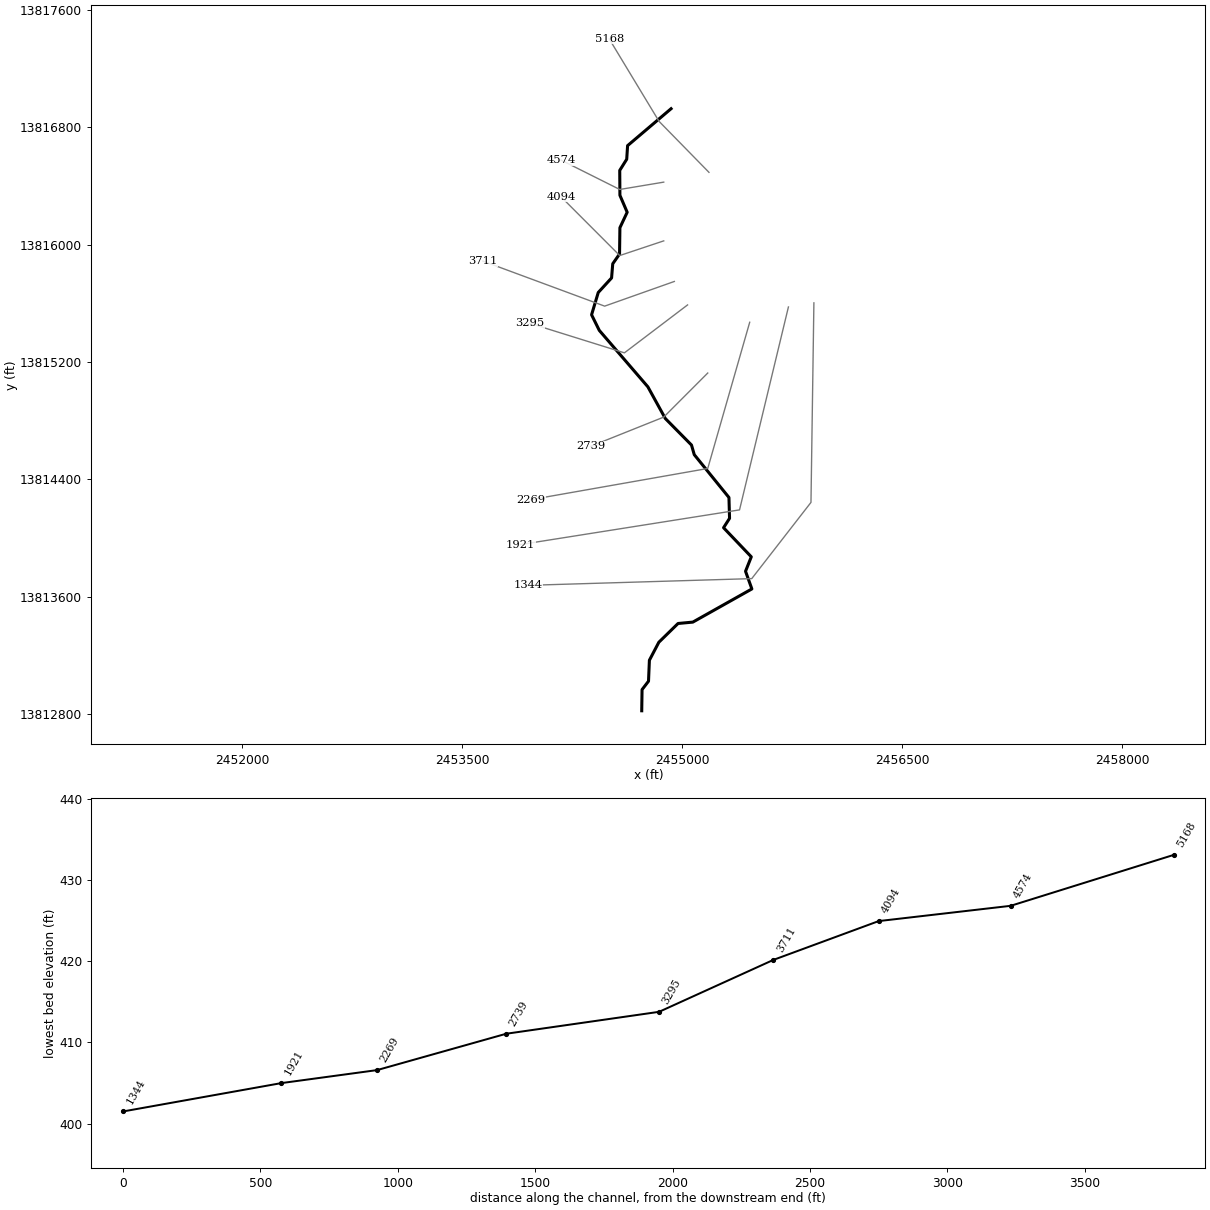
--- Stream0415.prj (project) ---

Proj Title=Stream0415 Base Level Engineering
Current Plan=p01
Default Exp/Contr=0.3,0.1
English Units
Geom File=g01
Flow File=f01
Plan File=p01
BEGIN DESCRIPTION:
Stream0415
END DESCRIPTION:

--- Stream0415.p01 (plan) ---

Plan Title=Multiple Run
Short Identifier=Multiple
Geom File=g01
Flow File=f01
Subcritical Flow
K Sum by GR= 0
Std Step Tol= 0.01
Critical Tol= 0.01
Num of Std Step Trials= 20
Max Error Tol= 0.3
Flow Tol Ratio= 0.001
Split Flow NTrial= 30
Split Flow Tol= 0.02
Split Flow Ratio= 0.02
Log Output Level= 0
Friction Slope Method= 1
Unsteady Friction Slope Method= 2
Unsteady Bridges Friction Slope Method= 1
Parabolic Critical Depth
Global Vel Dist=  1 , 1 , 1
Global Log Level= 0
CheckData=True
Encroach Param= -1, 0, 0, 0
BEGIN DESCRIPTION:
Multiple Run
END DESCRIPTION:

--- Stream0415.f01 (steady flow) ---

Flow Title=Multiple
Number of Profiles=7
Profile Names=10-year,25-year,50-year,1pct_min,100-year,1pct_plu,500-year
River Rch & RM= Stream0415,Reach-1,5168
     448     710     944     610    1217    2429    1999
River Rch & RM= Stream0415,Reach-1,2739
     770    1262    1715    1130    2255    4498    3855
Boundary for River Rch & Prof#=Stream0415,Reach-1,1
Up Type=0
Dn Type=3
Dn Slope=0.005
Boundary for River Rch & Prof#=Stream0415,Reach-1,2
Up Type=0
Dn Type=3
Dn Slope=0.005
Boundary for River Rch & Prof#=Stream0415,Reach-1,3
Up Type=0
Dn Type=3
Dn Slope=0.005
Boundary for River Rch & Prof#=Stream0415,Reach-1,4
Up Type=0
Dn Type=3
Dn Slope=0.005
Boundary for River Rch & Prof#=Stream0415,Reach-1,5
Up Type=0
Dn Type=3
Dn Slope=0.005
Boundary for River Rch & Prof#=Stream0415,Reach-1,6
Up Type=0
Dn Type=3
Dn Slope=0.005
Boundary for River Rch & Prof#=Stream0415,Reach-1,7
Up Type=0
Dn Type=3
Dn Slope=0.005

--- Stream0415.g01 (geometry) ---

Geom Title=Existing Conditions

River Reach=Stream0415,Reach-1
Reach XY= 30
      2454925.00     13816925.00      2454628.61     13816673.50
      2454622.64     13816580.98      2454575.07     13816504.97
      2454576.22     13816335.50      2454625.81     13816219.97
      2454576.22     13816114.50      2454573.78     13815935.50
      2454527.36     13815869.02      2454519.46     13815772.58
      2454428.62     13815673.50      2454383.04     13815521.68
      2454435.75     13815415.32      2454766.85     13815031.05
      2454885.78     13814815.32      2455064.22     13814634.68
      2455083.16     13814568.95      2455319.53     13814277.44
      2455323.62     13814135.44      2455282.79     13814071.58
      2455471.84     13813873.35      2455432.60     13813775.01
      2455475.77     13813654.66      2455073.41     13813428.83
      2454972.57     13813419.48      2454841.64     13813291.68
      2454777.25     13813169.07      2454771.22     13813026.57
      2454727.22     13812969.08      2454725.00     13812825.00

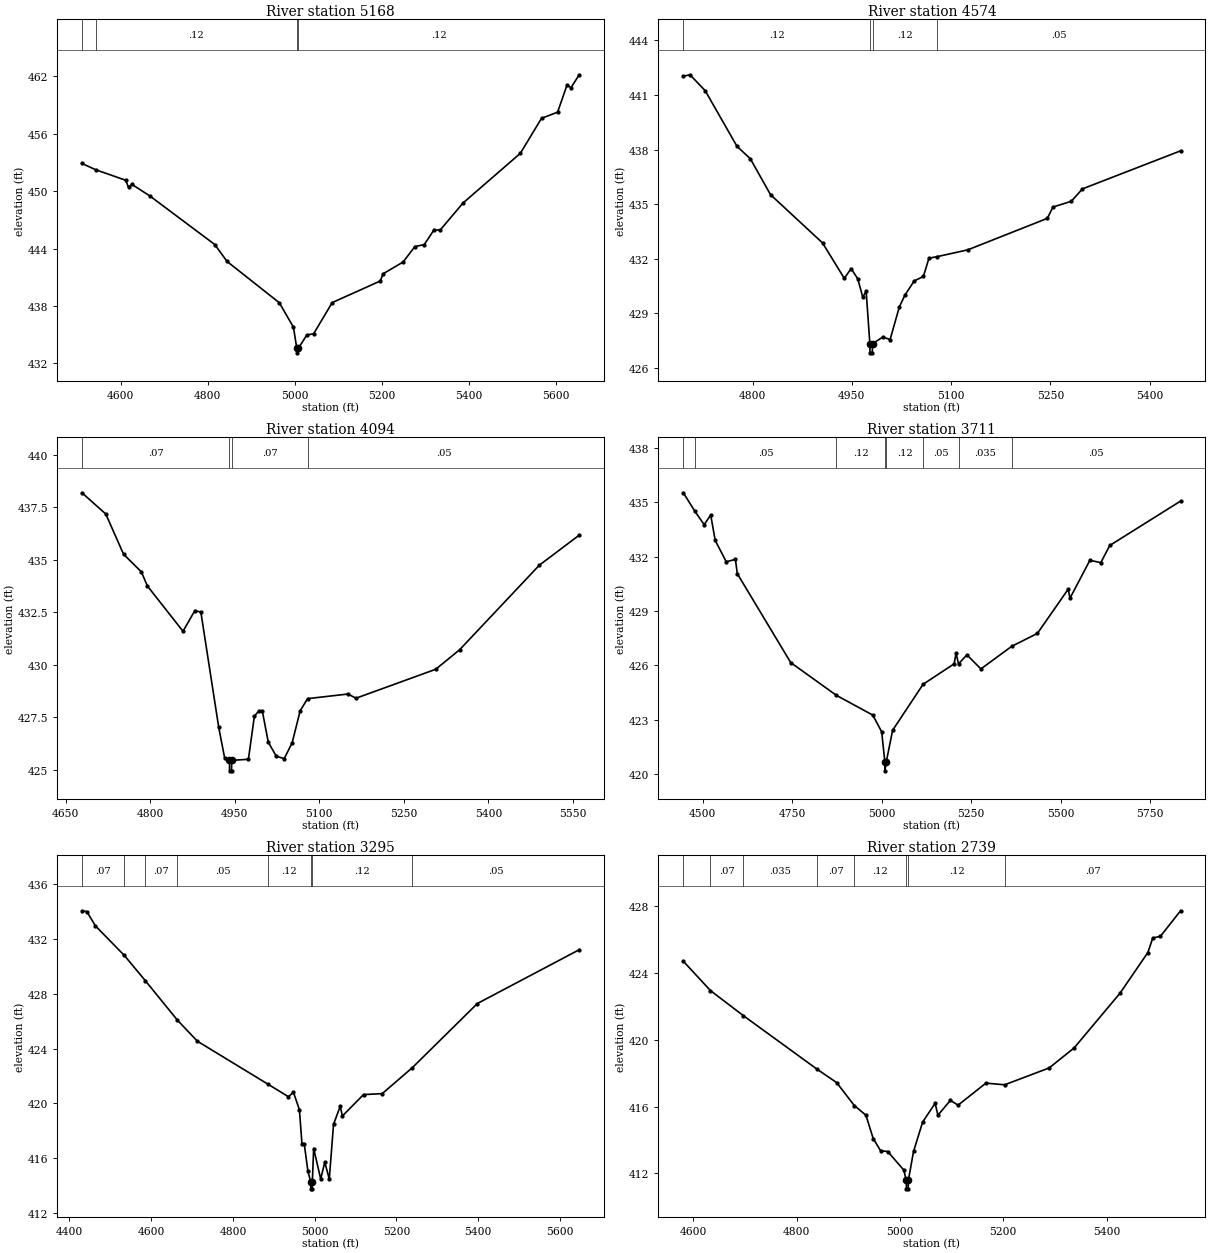
Type RM Length L Ch R = 1,5168,594,594,594
BEGIN DESCRIPTION:
Stream0415 9.0
END DESCRIPTION:
XS GIS Cut Line= 3
      2455183.32     13816491.68      2454843.06     13816838.89
      2454503.17     13817400.74
#Sta/Elev= 30
  4510.9  452.90  4542.3  452.25  4611.1  451.15  4618.1  450.39  4625.3  450.73
  4667.7  449.48  4816.1  444.43  4844.4  442.66  4964.6  438.34  4997.0  435.78
  5004.5  433.61  5004.7  433.11  5008.5  433.61  5027.8  434.98  5043.3  435.10
  5086.0  438.36  5196.6  440.62  5202.9  441.37  5248.9  442.60  5276.1  444.22
  5297.5  444.42  5319.7  445.94  5334.3  445.95  5386.7  448.77  5518.4  453.96
  5567.1  457.62  5604.0  458.26  5625.3  461.05  5635.0  460.84  5653.7  462.17
#Mann=4,-1,0
  4510.9    0.07       0  4542.3    0.12       0  5004.5    0.05       0
  5008.5    0.12       0
Bank Sta=5004.5,5008.5
Exp/Cntr=0.3,0.1

Type RM Length L Ch R = 1,4574,480,480,480
BEGIN DESCRIPTION:
Stream0415 8.0
END DESCRIPTION:
XS GIS Cut Line= 3
      2454875.01     13816425.00      2454575.00     13816375.00
      2454174.96     13816575.02
#Sta/Elev= 30
  4695.4  442.03  4705.5  442.11  4728.4  441.24  4776.5  438.18  4796.8  437.49
  4827.2  435.52  4905.8  432.87  4938.7  430.92  4948.9  431.46  4959.0  430.90
  4966.6  429.89  4971.7  430.22  4977.3  427.33  4977.5  426.83  4981.0  426.83
  4981.3  427.33  4997.0  427.70  5007.9  427.56  5021.9  429.36  5030.3  430.00
  5044.3  430.78  5058.2  431.03  5066.6  432.03  5079.5  432.12  5125.3  432.49
  5245.5  434.22  5253.9  434.84  5281.8  435.16  5298.6  435.84  5446.8  437.93
#Mann=4,-1,0
  4695.4    0.12       0  4977.3    0.05       0  4981.3    0.12       0
  5079.5    0.05       0
Bank Sta=4977.3,4981.3
Exp/Cntr=0.3,0.1

Type RM Length L Ch R = 1,4094,383,383,383
BEGIN DESCRIPTION:
Stream0415 7.0
END DESCRIPTION:
XS GIS Cut Line= 3
      2454875.03     13816025.01      2454575.00     13815925.00
      2454175.03     13816324.97
#Sta/Elev= 30
  4679.2  438.20  4721.4  437.19  4753.0  435.27  4784.6  434.43  4795.2  433.76
  4858.4  431.60  4879.5  432.59  4890.1  432.51  4921.7  427.03  4932.2  425.57
  4940.8  425.45  4941.0  424.95  4944.5  424.95  4944.8  425.45  4974.4  425.50
  4984.9  427.54  4992.8  427.81  4999.0  427.81  5009.6  426.32  5023.7  425.65
  5037.9  425.53  5052.0  426.29  5066.2  427.81  5079.3  428.39  5151.0  428.61
  5165.2  428.41  5306.6  429.79  5349.0  430.72  5490.4  434.75  5561.1  436.18
#Mann=4,-1,0
  4679.2    0.07       0  4940.8    0.05       0  4944.8    0.07       0
  5079.3    0.05       0
Bank Sta=4940.8,4944.8
Exp/Cntr=0.3,0.1

Type RM Length L Ch R = 1,3711,416,416,416
BEGIN DESCRIPTION:
Stream0415 6.0
END DESCRIPTION:
XS GIS Cut Line= 3
      2454947.21     13815748.61      2454472.22     13815580.56
      2453641.67     13815887.50
#Sta/Elev= 30
  4445.6  435.53  4477.9  434.51  4503.8  433.77  4522.2  434.30  4534.7  432.90
  4565.6  431.72  4591.2  431.85  4596.5  431.06  4745.7  426.15  4873.4  424.34
  4974.9  423.25  4999.8  422.33  5008.7  420.67  5008.9  420.17  5012.7  420.67
  5030.4  422.41  5115.5  424.95  5202.2  426.08  5207.6  426.66  5214.7  426.08
  5238.0  426.58  5277.0  425.80  5363.3  427.05  5434.9  427.76  5520.8  430.20
  5526.1  429.71  5581.6  431.80  5612.1  431.67  5637.1  432.62  5834.9  435.07
#Mann=8,-1,0
  4445.6    0.07       0  4477.9    0.05       0  4873.4    0.12       0
  5008.7    0.05       0  5012.7    0.12       0  5115.5    0.05       0
  5214.7   0.035       0  5363.3    0.05       0
Bank Sta=5008.7,5012.7
Exp/Cntr=0.3,0.1

Type RM Length L Ch R = 1,3295,556,556,556
BEGIN DESCRIPTION:
Stream0415 5.0
END DESCRIPTION:
XS GIS Cut Line= 3
      2455037.49     13815588.88      2454606.94     13815262.50
      2453961.08     13815463.90
#Sta/Elev= 30
  4430.6  434.04  4442.6  433.98  4463.5  432.94  4534.4  430.78  4585.5  428.95
  4664.1  426.07  4713.1  424.53  4885.7  421.40  4935.6  420.49  4948.2  420.80
  4962.7  419.54  4968.9  417.07  4974.5  417.07  4983.4  415.07  4990.3  414.27
  4990.6  413.77  4994.1  413.77  4994.3  414.27  4997.6  416.71  5014.8  414.49
  5024.8  415.71  5035.8  414.48  5046.2  418.47  5062.6  419.79  5067.8  419.08
  5119.6  420.64  5165.4  420.71  5239.3  422.61  5398.2  427.28  5647.4  431.20
#Mann=8,-1,0
  4430.6    0.07       0  4534.4    0.05       0  4585.5    0.07       0
  4664.1    0.05       0  4885.7    0.12       0  4990.3    0.05       0
  4994.3    0.12       0  5239.3    0.05       0
Bank Sta=4990.3,4994.3
Exp/Cntr=0.3,0.1

Type RM Length L Ch R = 1,2739,470,470,470
BEGIN DESCRIPTION:
Stream0415 4.0
END DESCRIPTION:
XS GIS Cut Line= 3
      2455175.03     13815125.03      2454875.00     13814825.00
      2454375.02     13814625.01
#Sta/Elev= 30
  4580.5  424.70  4633.1  422.94  4696.8  421.44  4840.1  418.22  4877.5  417.43
  4911.5  416.06  4934.1  415.48  4948.2  414.08  4962.4  413.36  4976.5  413.30
  5007.5  412.19  5012.2  411.57  5012.5  411.07  5016.0  411.07  5016.2  411.57
  5026.3  413.31  5043.9  415.07  5068.1  416.19  5073.5  415.48  5097.7  416.37
  5112.5  416.08  5166.4  417.40  5202.7  417.30  5288.9  418.31  5337.3  419.51
  5426.2  422.79  5480.0  425.22  5489.5  426.09  5504.3  426.19  5543.3  427.72
#Mann=8,-1,0
  4580.5    0.05       0  4633.1    0.07       0  4696.8   0.035       0
  4840.1    0.07       0  4911.5    0.12       0  5012.2    0.05       0
  5016.2    0.12       0  5202.7    0.07       0
Bank Sta=5012.2,5016.2
Exp/Cntr=0.3,0.1

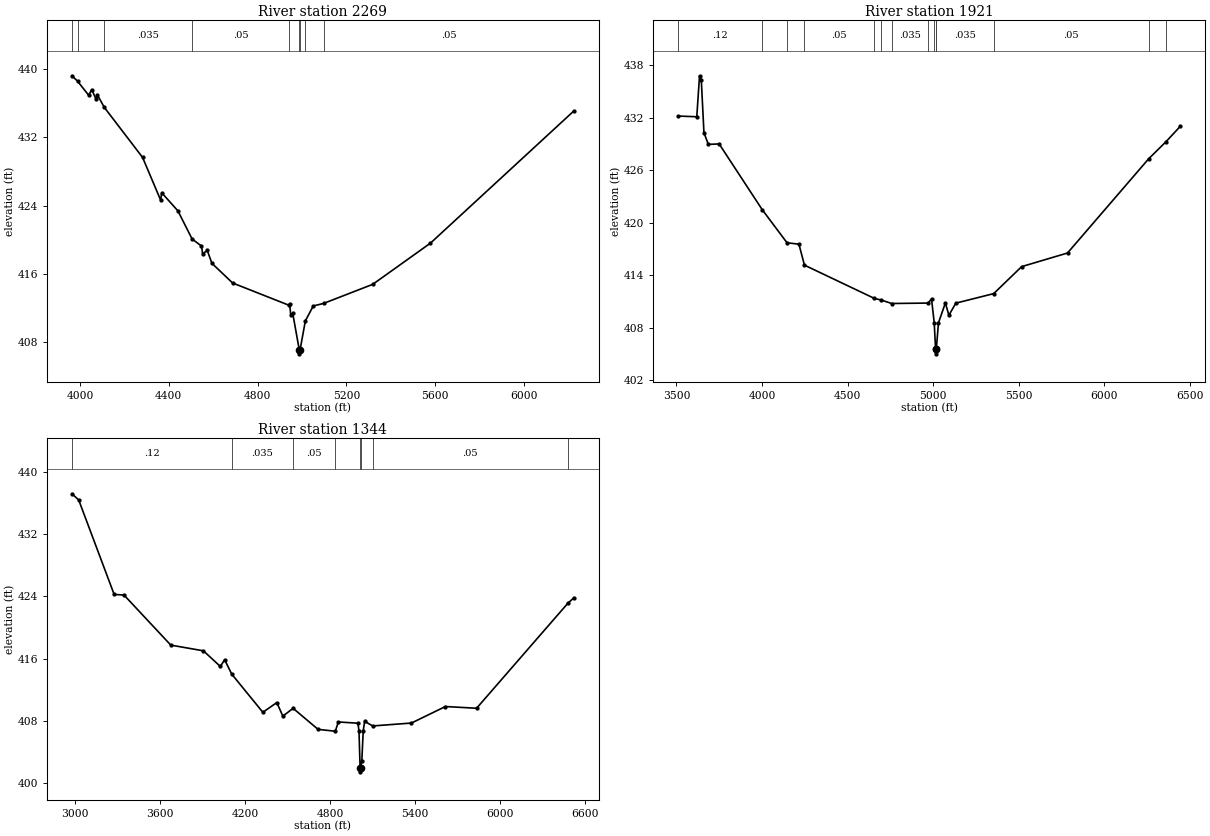
Type RM Length L Ch R = 1,2269,348,348,348
BEGIN DESCRIPTION:
Stream0415 3.0
END DESCRIPTION:
XS GIS Cut Line= 3
      2455461.12     13815470.85      2455175.00     13814475.00
      2453968.99     13814262.66
#Sta/Elev= 30
  3964.1  439.24  3989.2  438.61  4039.2  436.96  4053.4  437.62  4072.9  436.47
  4078.1  437.02  4109.8  435.53  4282.3  429.65  4363.4  424.65  4368.6  425.50
  4441.3  423.38  4505.4  420.07  4547.6  419.25  4552.8  418.33  4573.6  418.73
  4594.5  417.22  4687.7  414.91  4941.2  412.30  4944.5  412.44  4949.7  411.16
  4958.6  411.34  4987.8  407.09  4988.1  406.59  4991.8  407.09  5015.4  410.46
  5051.0  412.21  5097.5  412.51  5318.8  414.75  5579.0  419.59  6224.8  435.11
#Mann=9,-1,0
  3964.1   0.035       0  3989.2    0.05       0  4109.8   0.035       0
  4505.4    0.05       0  4941.2    0.12       0  4987.8    0.05       0
  4991.8    0.12       0  5015.4   0.035       0  5097.5    0.05       0
Bank Sta=4987.8,4991.8
Exp/Cntr=0.3,0.1

Type RM Length L Ch R = 1,1921,577,577,577
BEGIN DESCRIPTION:
Stream0415 2.0
END DESCRIPTION:
XS GIS Cut Line= 3
      2455724.99     13815574.98      2455391.67     13814193.06
      2453899.27     13813957.05
#Sta/Elev= 30
  3511.4  432.20  3618.7  432.12  3634.8  436.81  3645.1  436.32  3660.6  430.29
  3686.3  428.96  3749.5  429.01  4000.6  421.50  4145.9  417.70  4215.5  417.54
  4247.8  415.14  4655.6  411.34  4697.6  411.14  4757.5  410.75  4970.0  410.80
  4990.3  411.27  5006.0  408.54  5014.1  405.49  5014.3  404.99  5018.1  405.49
  5030.8  408.54  5071.3  410.82  5091.6  409.40  5132.1  410.79  5353.4  411.88
  5516.8  414.97  5784.9  416.53  6258.9  427.31  6359.9  429.26  6443.9  431.03
#Mann=14,-1,0
  3511.4    0.12       0  4000.6    0.05       0  4145.9   0.035       0
  4247.8    0.05       0  4655.6   0.035       0  4697.6    0.05       0
  4757.5   0.035       0  4970.0    0.12       0  5006.0   0.035       0
  5014.1    0.05       0  5018.1   0.035       0  5353.4    0.05       0
  6258.9   0.035       0  6359.9    0.05       0
Bank Sta=5014.1,5018.1
Exp/Cntr=0.3,0.1

Type RM Length L Ch R = 1,1344,0,0,0
BEGIN DESCRIPTION:
Stream0415 1.0
END DESCRIPTION:
XS GIS Cut Line= 4
      2455898.61     13815602.80      2455878.70     13814244.04
      2455475.00     13813725.00      2453948.64     13813679.21
#Sta/Elev= 30
  2978.9  437.17  3026.7  436.37  3276.7  424.26  3346.7  424.17  3676.8  417.75
  3906.8  417.02  4026.8  415.01  4056.8  415.88  4107.0  414.03  4326.8  409.13
  4425.3  410.38  4467.8  408.64  4540.4  409.64  4716.6  406.94  4838.3  406.70
  4859.6  407.89  4997.9  407.73  5005.4  406.74  5013.4  401.99  5013.6  401.49
  5017.4  401.99  5025.4  402.92  5035.4  406.74  5045.4  407.97  5102.1  407.38
  5375.5  407.75  5615.6  409.87  5835.7  409.65  6480.5  423.13  6522.4  423.82
#Mann=8,-1,0
  2978.9    0.12       0  4107.0   0.035       0  4540.4    0.05       0
  4838.3     0.1       0  5013.4    0.05       0  5017.4     0.1       0
  5102.1    0.05       0  6480.5   0.035       0
Bank Sta=5013.4,5017.4
Exp/Cntr=0.3,0.1

Chan Stop Cuts=-1