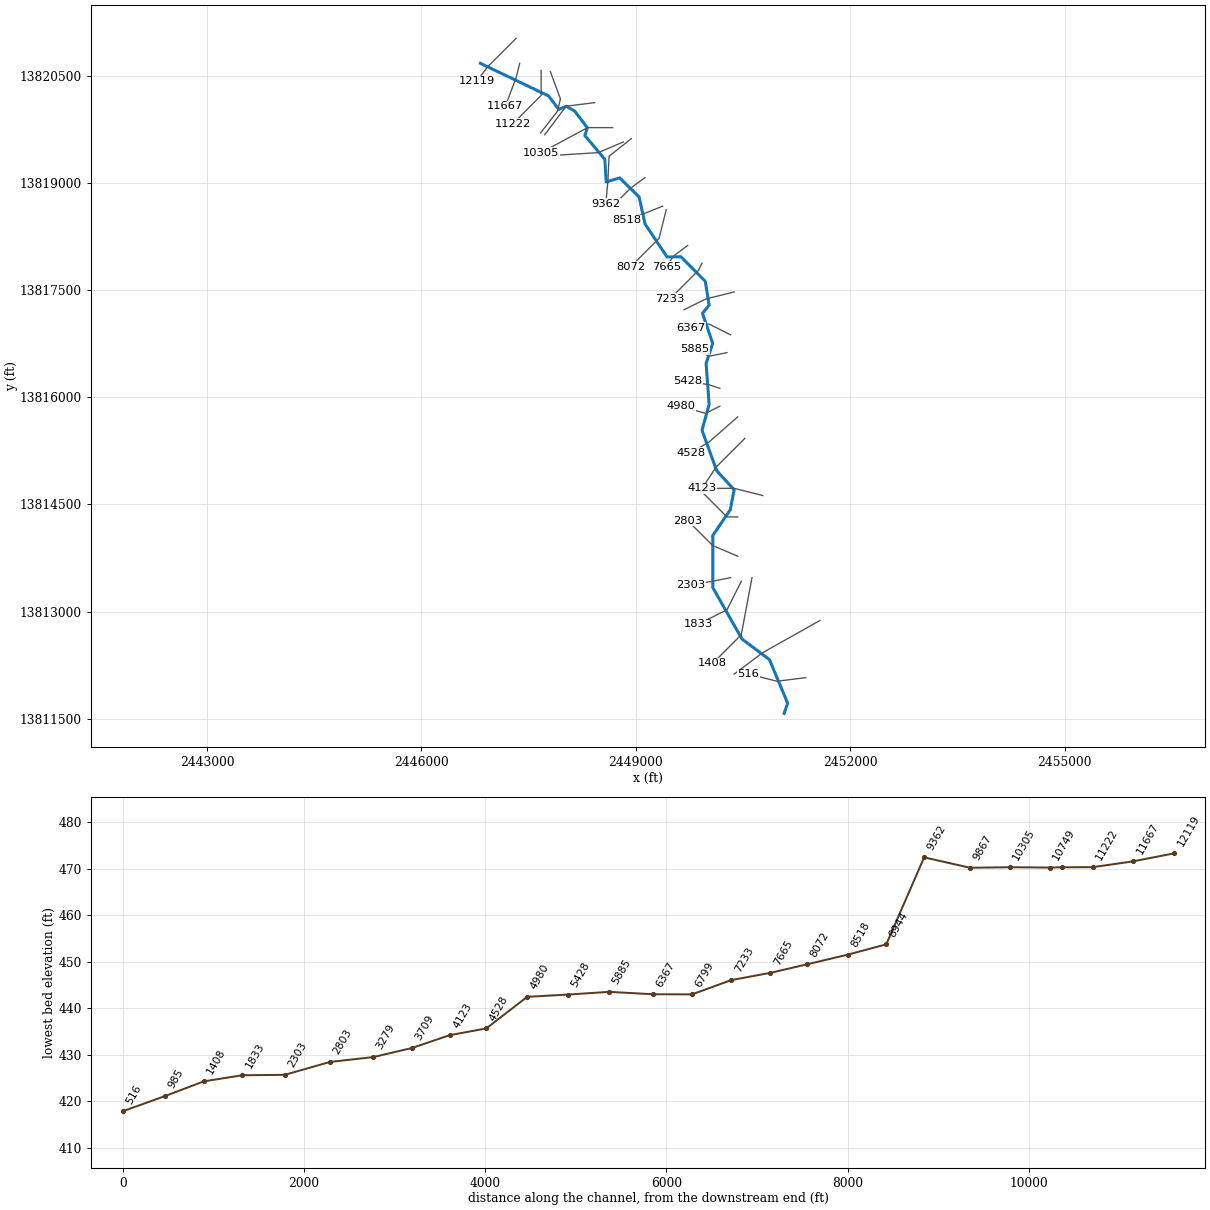
--- Stream0417.prj (project) ---

Proj Title=Stream0417 Base Level Engineering
Current Plan=p01
Default Exp/Contr=0.3,0.1
English Units
Geom File=g01
Flow File=f01
Plan File=p01
Y Axis Title=Elevation
X Axis Title(PF)=Main Channel Distance
X Axis Title(XS)=Station
BEGIN DESCRIPTION:
Stream0417
END DESCRIPTION:
DSS Export Rating Curves= 0
DSS Export Rating Curve Sorted= 0
DSS Export Volume Flow Curves= 0
DXF OffsetX= 0
DXF OffsetY= 0
DXF ScaleX= 1
DXF ScaleY= 10

--- Stream0417.p01 (plan) ---

Plan Title=Multiple Run
Short Identifier=Multiple
Geom File=g01
Flow File=f01
Subcritical Flow
K Sum by GR= 0
Std Step Tol= 0.01
Critical Tol= 0.01
Num of Std Step Trials= 20
Max Error Tol= 0.3
Flow Tol Ratio= 0.001
Split Flow NTrial= 30
Split Flow Tol= 0.02
Split Flow Ratio= 0.02
Log Output Level= 0
Friction Slope Method= 1
Unsteady Friction Slope Method= 2
Unsteady Bridges Friction Slope Method= 1
Parabolic Critical Depth
Global Vel Dist=  1 , 1 , 1
Global Log Level= 0
CheckData=True
Encroach Param= -1, 0, 0, 0
BEGIN DESCRIPTION:
Multiple Run
END DESCRIPTION:

--- Stream0417.f01 (steady flow) ---

Flow Title=Multiple
Number of Profiles=7
Profile Names=10-year,25-year,50-year,1pct_min,100-year,1pct_plu,500-year
River Rch & RM= Stream0417,Reach-1,12119
     885    1462    1998    1323    2640    5268    4563
River Rch & RM= Stream0417,Reach-1,10749
    1632    2763    3834    2569    5127   10229    9086
River Rch & RM= Stream0417,Reach-1,985
    1645    2781    3857    2583    5153   10282    9118
Boundary for River Rch & Prof#=Stream0417,Reach-1,1
Up Type=0
Dn Type=3
Dn Slope=0.005
Boundary for River Rch & Prof#=Stream0417,Reach-1,2
Up Type=0
Dn Type=3
Dn Slope=0.005
Boundary for River Rch & Prof#=Stream0417,Reach-1,3
Up Type=0
Dn Type=3
Dn Slope=0.005
Boundary for River Rch & Prof#=Stream0417,Reach-1,4
Up Type=0
Dn Type=3
Dn Slope=0.005
Boundary for River Rch & Prof#=Stream0417,Reach-1,5
Up Type=0
Dn Type=3
Dn Slope=0.005
Boundary for River Rch & Prof#=Stream0417,Reach-1,6
Up Type=0
Dn Type=3
Dn Slope=0.005
Boundary for River Rch & Prof#=Stream0417,Reach-1,7
Up Type=0
Dn Type=3
Dn Slope=0.005

--- Stream0417.g01 (geometry) ---

Geom Title=Existing Conditions
Program Version=4.10

River Reach=Stream0417      ,Reach-1
Reach XY= 30
        2446825.       13820675.      2447777.67     13820219.58
      2447922.64     13820030.05        2448025.       13820075.
       2448145.5      13820005.4      2448321.84     13819773.35
      2448286.11     13819664.95      2448565.69     13819331.66
      2448585.48     13819014.44      2448773.35      13819071.9
      2449045.39     13818805.16      2449128.74     13818426.52
      2449435.77     13817964.59      2449631.17     13817967.24
      2449971.25     13817623.45      2450025.04     13817290.34
       2449932.3     13817175.08      2450075.36     13816754.85
      2449982.59     13816474.99       2450025.4       13815900.
      2449925.49     13815540.22      2450130.83     13814972.69
       2450375.3     13814704.83      2450321.25     13814426.55
      2450076.05     13814064.57       2450076.2      13813335.5
      2450485.78     13812615.32      2450869.48     13812327.43
      2451123.23      13811718.9        2451075.       13811575.

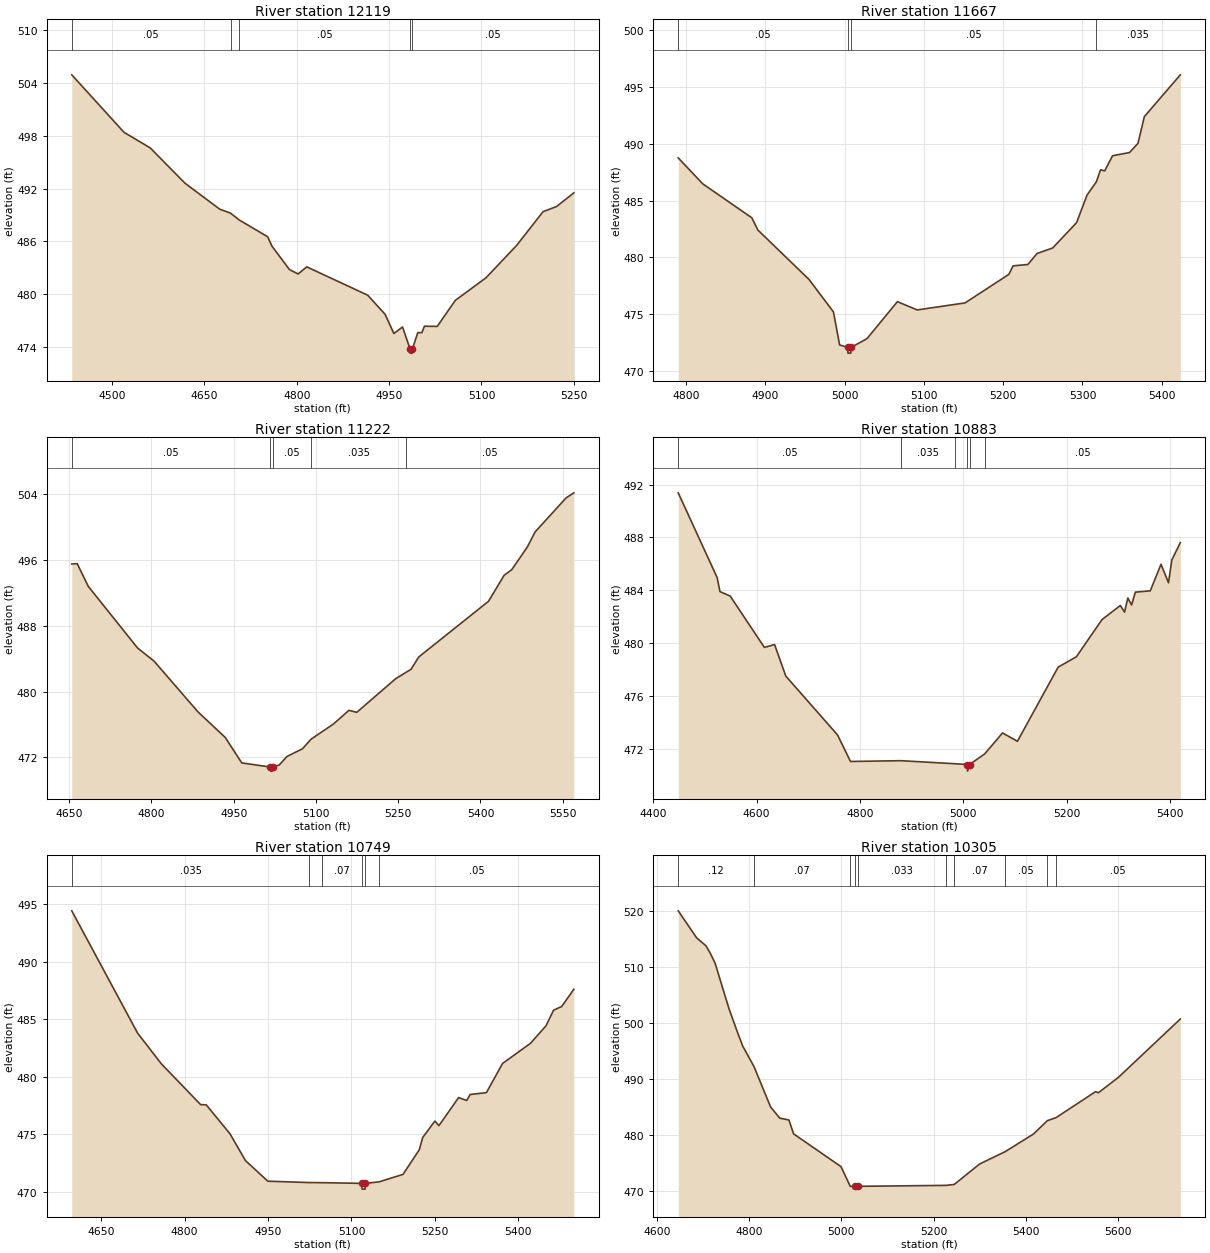
Type RM Length L Ch R = 1 ,12119   ,452,452,452
BEGIN DESCRIPTION:
Stream0417 27.0
END DESCRIPTION:
XS GIS Cut Line= 3
        2447325.       13821025.        2446925.       13820625.
      2446774.99     13820424.99
#Sta/Elev= 30
  4434.4  504.93  4519.3  498.39  4561.7  496.63  4618.3  492.61  4674.8  489.65
  4692.4   489.2  4706.5  488.42  4752.6  486.52  4759.7  485.44    4788  482.79
  4802.1  482.28  4816.2  483.09  4915.2  479.87  4943.5  477.69  4957.7  475.51
  4971.8  476.25  4983.9  473.78  4984.2  473.28  4987.7  473.28  4987.9  473.78
  4996.6  475.61  5003.2  475.61  5007.4  476.34  5028.2  476.32  5057.4  479.27
  5107.4  481.85  5157.4  485.55  5200.1  489.37    5222  489.95  5250.1  491.51
#Mann= 5 ,-1 , 0
  4434.4     .05       0  4692.4    .035       0  4706.5     .05       0
  4983.9     .05       0  4987.9     .05       0
Bank Sta=4983.9,4987.9
XS Rating Curve= 0 ,0
Exp/Cntr=0.3,0.1

Type RM Length L Ch R = 1 ,11667   ,445,445,445
BEGIN DESCRIPTION:
Stream0417 26.0
END DESCRIPTION:
XS GIS Cut Line= 3
        2447375.       13820675.        2447325.       13820475.
      2447174.98     13820074.96
#Sta/Elev= 30
    4790  488.75  4820.9  486.47  4882.8  483.48  4890.5   482.4  4954.9  478.06
  4985.8   475.2  4993.6  472.29  5003.9  472.07  5004.1  471.57  5007.7  471.57
    5008  472.07  5028.2  472.85  5066.5   476.1  5091.4  475.37  5151.9  475.99
  5207.1   478.5  5212.4  479.25  5231.1  479.37  5242.7  480.34  5262.3  480.82
  5292.5  483.05  5305.9   485.5  5317.4  486.63  5322.8   487.7  5328.1  487.61
  5337.9  488.94  5359.3  489.22    5370  490.03    5378  492.38  5423.4  496.06
#Mann= 4 ,-1 , 0
    4790     .05       0  5003.9     .05       0    5008     .05       0
  5317.4    .035       0
Bank Sta=5003.9,5008
XS Rating Curve= 0 ,0
Exp/Cntr=0.3,0.1

Type RM Length L Ch R = 1 ,11222   ,339,339,339
BEGIN DESCRIPTION:
Stream0417 25.0
END DESCRIPTION:
XS GIS Cut Line= 3
        2447675.     13820574.96        2447675.       13820225.
      2447275.03     13819825.03
#Sta/Elev= 30
  4654.7  495.52  4664.7  495.56  4684.7  492.81  4774.7   485.3  4804.7  483.71
  4884.7  477.54  4934.7  474.41  4964.7  471.32  5016.7  470.82    5017  470.32
  5020.6  470.32  5020.8  470.82  5032.9  471.06  5047.1   472.1  5075.4  473.04
  5091.3  474.22  5131.9  476.05  5160.2  477.72  5174.4  477.47  5245.1  481.55
  5264.8  482.36  5273.4  482.71  5287.5  484.21  5414.8  490.99  5443.1  494.14
  5457.2  494.84  5485.5  497.59  5499.6  499.42  5556.2  503.56  5570.3  504.18
#Mann= 5 ,-1 , 0
  4654.7     .05       0  5016.7     .05       0  5020.8     .05       0
  5091.3    .035       0  5264.8     .05       0
Bank Sta=5016.7,5020.8
XS Rating Curve= 0 ,0
Exp/Cntr=0.3,0.1

Type RM Length L Ch R = 1 ,10883   ,134,134,134
BEGIN DESCRIPTION:
E21012
END DESCRIPTION:
XS GIS Cut Line= 4
      2447803.69     13820560.13      2447944.75      13820178.2
      2447905.69     13820006.76      2447666.96     13819700.75
#Sta/Elev= 30
  4448.4  491.37  4523.7  484.95  4529.1  483.89  4548.8  483.56    4615  479.67
  4634.8  479.88  4656.4   477.5  4756.5  473.04  4781.6  471.03  4879.1  471.09
  4983.7  470.86  5007.7   470.8    5008   470.3  5011.9   470.8  5041.3  471.61
  5075.6  473.19  5104.5  472.56  5183.2  478.17  5218.5  478.96  5268.2  481.78
  5303.5  482.84  5311.7  482.34    5318  483.41  5325.3  482.88  5332.5  483.85
  5361.4  483.95  5382.2  485.96  5396.7  484.56    5403  486.28  5419.5   487.6
#Mann= 6 ,-1 , 0
  4448.4     .05       0  4879.1    .035       0  4983.7     .07       0
  5007.7     .05       0  5011.9     .07       0  5041.3     .05       0
Bank Sta=5007.7,5011.9
XS Rating Curve= 0 ,0
Exp/Cntr=0.3,0.1

Type RM Length L Ch R = 1 ,10749   ,444,444,444
BEGIN DESCRIPTION:
Stream0417 24.0
END DESCRIPTION:
XS GIS Cut Line= 3
      2448424.99       13820125.        2448025.       13820075.
        2447725.       13819675.
#Sta/Elev= 30
  4596.9  494.41  4715.3  483.79  4758.1  481.12  4828.7  477.58  4838.8  477.56
  4881.6  475.04  4909.3  472.72  4949.6  470.93  5023.8  470.81  5046.7   470.8
  5118.7  470.74  5119.2  470.24  5124.5  470.24    5125  470.74  5149.5  470.87
  5192.7  471.52  5221.9  473.65  5228.1  474.72    5250  476.15  5257.3  475.75
  5292.7  478.19  5307.3  477.94  5313.5  478.46  5342.7  478.62  5371.9  481.16
  5421.9   482.9    5450  484.43  5463.5  485.78  5478.1   486.1    5500   487.6
#Mann= 6 ,-1 , 0
  4596.9    .035       0  5023.8    .033       0  5046.7     .07       0
  5118.7    .035       0    5125     .07       0  5149.5     .05       0
Bank Sta=5118.7,5125
XS Rating Curve= 0 ,0
Exp/Cntr=0.3,0.1

Type RM Length L Ch R = 1 ,10305   ,438,438,438
BEGIN DESCRIPTION:
Stream0417 23.0
END DESCRIPTION:
XS GIS Cut Line= 3
      2448675.03       13819775.        2448325.       13819775.
      2447674.97     13819424.99
#Sta/Elev= 30
  4646.4  519.98  4686.4  515.15  4706.4  513.75  4716.4  512.34  4726.4  510.61
  4756.4  502.52  4776.4  497.94  4786.4  495.81  4810.9  492.14  4846.4  485.01
  4866.4  482.98  4886.4  482.65  4896.4  480.18  4999.3  474.32  5019.3  470.81
    5029  470.81  5029.5  470.31  5034.8  470.31  5035.3  470.81  5227.4  470.98
  5244.7  471.15  5299.8   474.8  5354.9  476.99  5416.7  480.16  5446.6  482.54
  5465.1  483.06  5551.3  487.72    5557   487.5  5600.8  490.28  5734.7  500.67
#Mann= 10 ,-1 , 0
  4646.4     .12       0  4810.9     .07       0  5019.3    .033       0
    5029     .05       0  5035.3    .033       0  5227.4     .12       0
  5244.7     .07       0  5354.9     .05       0  5446.6     .07       0
  5465.1     .05       0
Bank Sta=5029,5035.3
XS Rating Curve= 0 ,0
Exp/Cntr=0.3,0.1

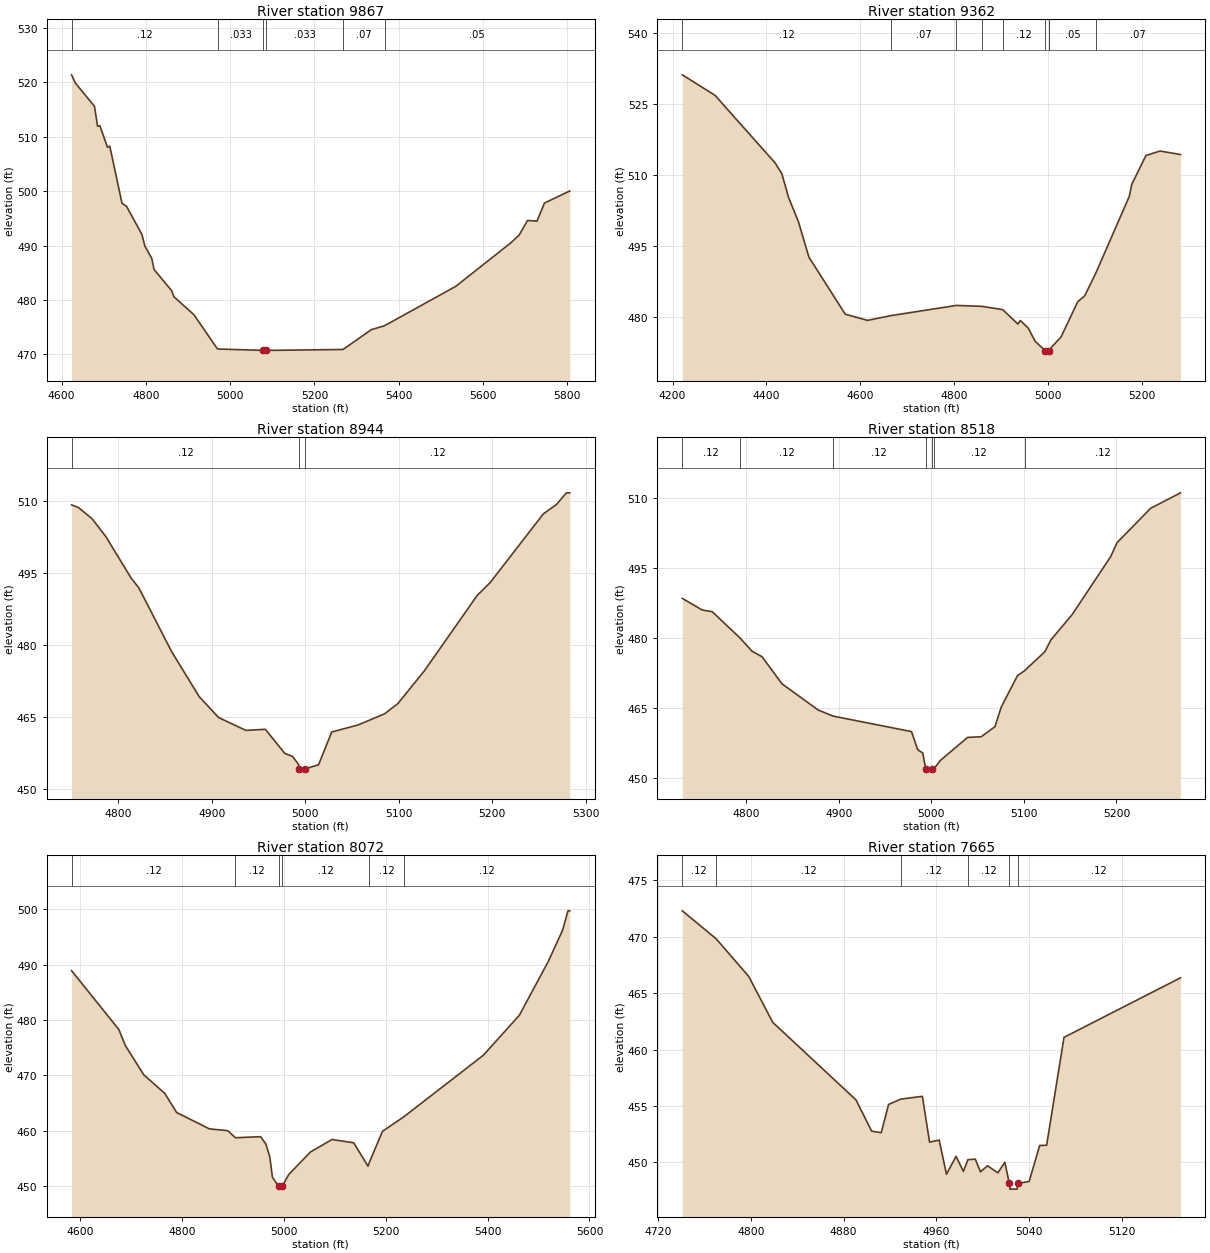
Type RM Length L Ch R = 1 ,9867    ,505,505,505
BEGIN DESCRIPTION:
Stream0417 22.0
END DESCRIPTION:
XS GIS Cut Line= 3
      2448825.04     13819575.02        2448475.       13819425.
      2447674.99       13819375.
#Sta/Elev= 30
  4623.5  521.41  4632.6  519.89  4677.9  515.61  4685.2  511.95  4690.6  512.06
  4708.8  508.07  4714.2  508.28  4743.2  497.77  4754.1   497.2  4790.4  492.04
  4797.6  489.89  4813.9  487.62  4819.4  485.58  4861.1  481.68  4866.5  480.56
  4913.7  477.29  4969.9  470.96  5078.8   470.7  5079.3   470.2  5085.2   470.7
  5267.8  470.87    5335  474.52  5366.3  475.24  5535.4  482.49  5665.6  490.47
  5685.7  491.91  5705.7  494.61  5728.2  494.49  5745.8  497.81  5805.9  500.04
#Mann= 6 ,-1 , 0
  4623.5     .12       0  4969.9    .033       0  5078.8    .033       0
  5085.2    .033       0  5267.8     .07       0  5366.3     .05       0
Bank Sta=5078.8,5085.2
XS Rating Curve= 0 ,0
Exp/Cntr=0.3,0.1

Type RM Length L Ch R = 1 ,9362    ,418,418,418
BEGIN DESCRIPTION:
Stream0417 21.0
END DESCRIPTION:
XS GIS Cut Line= 4
      2448936.63     13819621.49      2448625.83     13819374.16
      2448608.32     13819019.61      2448579.93      13818711.7
#Sta/Elev= 30
  4220.9  531.16  4290.4  526.85  4418.5  512.58    4433  510.27  4447.4  505.24
  4468.2  500.19  4490.6  492.69    4568  480.65  4615.4  479.34  4665.1  480.34
  4804.9   482.5  4859.5   482.3  4903.5  481.61  4935.9  478.57  4940.9  479.31
  4957.7  477.74  4972.9  474.89  4994.5  472.93    4995  472.43  5001.1  472.93
  5002.3  473.09  5027.9  475.87  5063.4  483.28  5078.1  484.51  5101.4  489.21
  5173.1  505.48  5178.6  508.07  5208.7  514.13  5238.8  515.08  5282.3  514.34
#Mann= 9 ,-1 , 0
  4220.9     .12       0  4665.1     .07       0  4804.9     .12       0
  4859.5     .07       0  4903.5     .12       0  4994.5     .05       0
  5001.1     .12       0  5002.3     .05       0  5101.4     .07       0
Bank Sta=4994.5,5001.1
XS Rating Curve= 0 ,0
Exp/Cntr=0.3,0.1

Type RM Length L Ch R = 1 ,8944    ,426,426,426
BEGIN DESCRIPTION:
Stream0417 20.0
END DESCRIPTION:
XS GIS Cut Line= 3
      2449125.02     13819075.01        2448925.       13818925.
      2448724.97     13818724.97
#Sta/Elev= 30
    4750  509.17  4757.3  508.64  4771.9  506.29  4786.5  502.62  4813.6  493.96
  4821.9  491.91  4857.3  478.53  4886.5  469.25  4907.3  464.89  4936.5  462.22
  4957.3  462.45  4978.1  457.43  4986.5  456.78  4992.7  455.16  4993.5  454.24
    4994  453.74  4999.7  453.74  5000.2  454.24  5014.2  455.06  5028.3  461.89
  5056.6  463.36  5084.9  465.68    5099  467.79  5127.3   474.6  5183.9  490.32
    5198  493.05  5254.6  507.29  5268.7  509.25  5279.3  511.68  5282.9  511.68
#Mann= 3 ,-1 , 0
    4750     .12       0  4993.5     .05       0  5000.2     .12       0
Bank Sta=4993.5,5000.2
XS Rating Curve= 0 ,0
Exp/Cntr=0.3,0.1

Type RM Length L Ch R = 1 ,8518    ,446,446,446
BEGIN DESCRIPTION:
Stream0417 19.0
END DESCRIPTION:
XS GIS Cut Line= 3
      2449375.02     13818675.01        2449125.       13818575.
      2448875.03     13818475.01
#Sta/Elev= 30
  4730.8  488.57  4752.4  486.07  4763.1  485.72    4793  480.11  4806.2  477.23
    4817  476.05  4838.5  470.25  4877.6  464.64  4893.6  463.33  4978.5     460
  4985.3   456.1  4990.7   455.4  4993.9  452.02  4994.4  451.52  5000.8  452.02
  5002.8  452.02  5009.5  453.77  5039.1  458.75  5053.9   458.9  5068.7  461.04
  5075.5  465.24    5093  471.97  5100.7  473.05  5122.6  477.11  5129.3  479.68
  5152.2   485.1  5193.9  497.55  5200.7  500.52    5237  507.89  5269.3  511.21
#Mann= 7 ,-1 , 0
  4730.8     .12       0    4793     .12       0  4893.6     .12       0
  4993.9     .05       0  5000.8     .12       0  5002.8     .12       0
  5100.7     .12       0
Bank Sta=4993.9,5000.8
XS Rating Curve= 0 ,0
Exp/Cntr=0.3,0.1

Type RM Length L Ch R = 1 ,8072    ,407,407,407
BEGIN DESCRIPTION:
Stream0417 18.0
END DESCRIPTION:
XS GIS Cut Line= 3
      2449425.01     13818625.03        2449325.       13818225.
      2448925.02     13817825.02
#Sta/Elev= 30
  4583.3   488.9  4676.1  478.28    4689  475.37  4725.1  470.09  4766.3  466.75
  4789.5   463.3  4853.9  460.34    4890  460.01  4905.1  458.74  4954.4  458.93
  4964.7  457.61  4972.5  455.27  4977.6  451.62  4989.6  449.96  4990.1  449.46
  4996.6  449.96  5009.8  452.12  5052.2  456.16  5094.6  458.42  5137.1  457.83
  5165.3   453.6    5168   454.3  5193.6   459.9  5235.3   462.5  5391.6  473.63
  5462.3  480.85  5518.9  490.52  5547.2   496.2  5557.8  499.71  5561.3  499.71
#Mann= 6 ,-1 , 0
  4583.3     .12       0  4905.1     .12       0  4989.6     .05       0
  4996.6     .12       0    5168     .12       0  5235.3     .12       0
Bank Sta=4989.6,4996.6
XS Rating Curve= 0 ,0
Exp/Cntr=0.3,0.1

Type RM Length L Ch R = 1 ,7665    ,432,432,432
BEGIN DESCRIPTION:
Stream0417 17.0
END DESCRIPTION:
XS GIS Cut Line= 3
      2449724.97     13818124.98        2449525.       13817975.
      2449425.02     13817825.04
#Sta/Elev= 30
  4740.7   472.3  4769.9  469.82    4798  466.49  4818.8  462.41  4890.7  455.53
  4904.2  452.76  4912.5  452.63  4918.8  455.13  4929.3   455.6    4948  455.85
  4954.2  451.79  4962.5  451.97  4968.8  448.94  4977.1  450.53  4983.4  449.19
  4987.3  450.23  4993.7  450.28  4998.2  449.15  5004.2  449.69  5013.2  449.07
  5019.2     450  5023.1  448.12  5023.6  447.62  5029.9  447.62  5030.4  448.12
  5040.2   448.3  5049.3  451.49  5055.3  451.51  5070.3  461.08  5170.9  466.36
#Mann= 6 ,-1 , 0
  4740.7     .12       0  4769.9     .12       0  4929.3     .12       0
  4987.3     .12       0  5023.1     .05       0  5030.4     .12       0
Bank Sta=5023.1,5030.4
XS Rating Curve= 0 ,0
Exp/Cntr=0.3,0.1

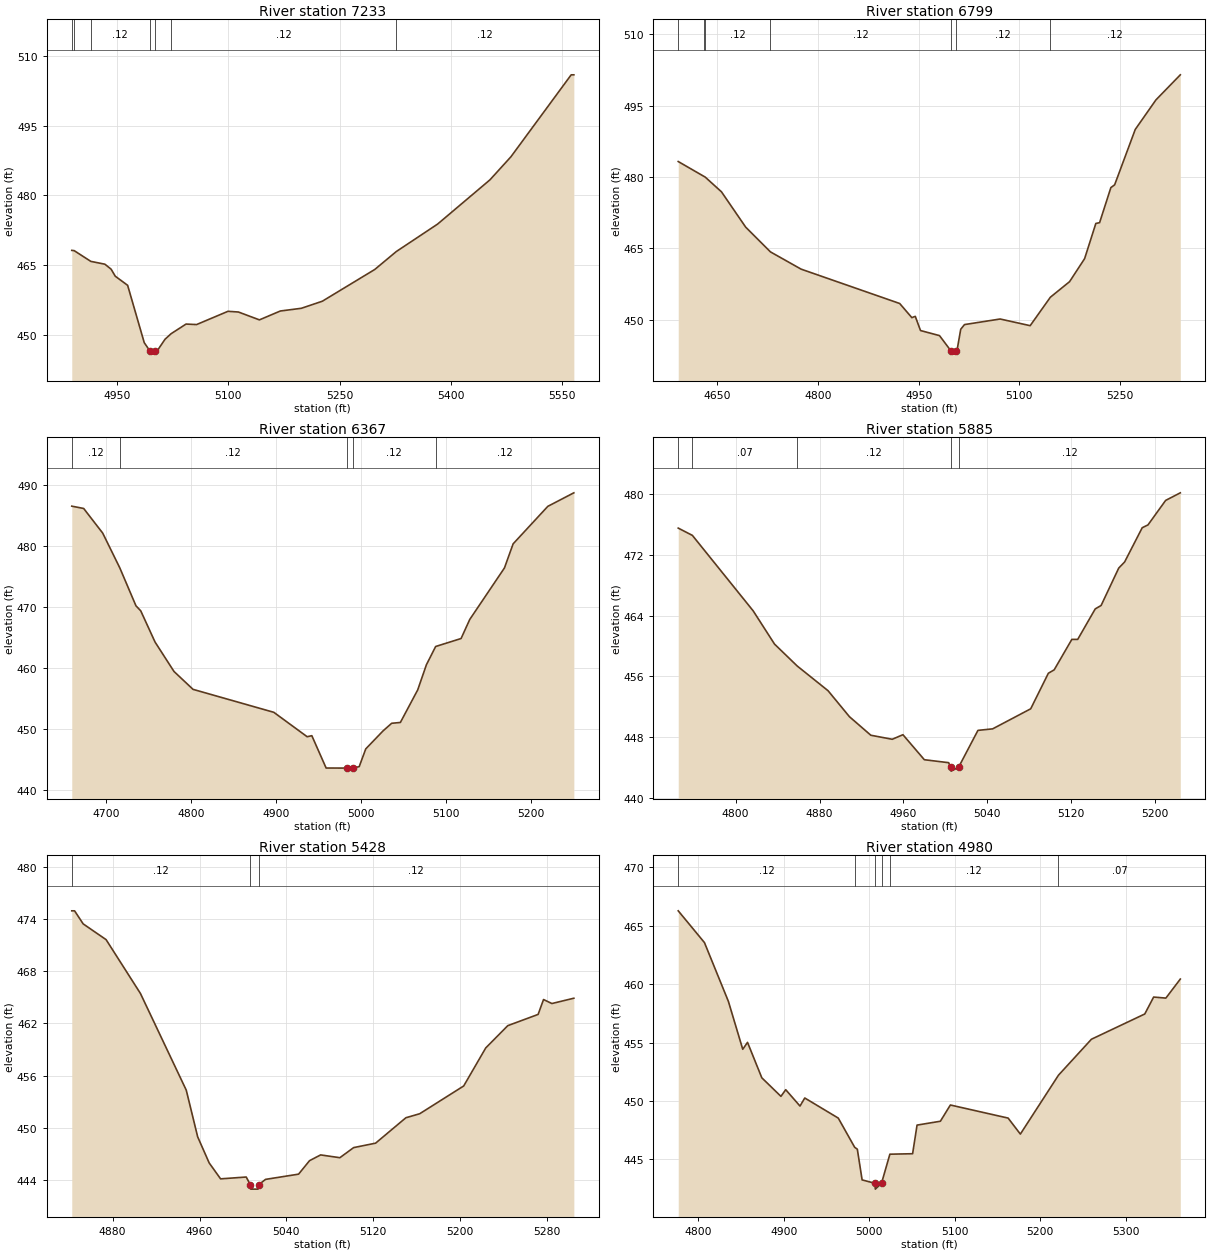
Type RM Length L Ch R = 1 ,7233    ,434,434,434
BEGIN DESCRIPTION:
Stream0417 16.0
END DESCRIPTION:
XS GIS Cut Line= 3
      2449924.99     13817874.98        2449875.       13817775.
      2449474.98     13817374.98
#Sta/Elev= 30
  4888.7  468.15  4891.9   468.1  4914.4  465.79  4933.4  465.18  4941.8  464.11
  4947.4   462.6  4964.1  460.64  4986.5  448.31    4994  446.56  4994.5  446.06
  5000.9  446.06  5001.4  446.56    5004  446.56  5014.6  449.05  5022.7  450.23
  5042.9  452.31  5057.1   452.2  5099.5  455.05  5113.6   454.9  5141.9  453.21
  5170.2  455.12  5198.5   455.7  5226.8  457.22  5297.5  464.04  5326.6   467.9
  5382.3   473.8    5453  483.32  5481.3  488.28  5562.6   505.9  5566.2   505.9
#Mann= 7 ,-1 , 0
  4888.7     .12       0  4891.9     .12       0  4914.4     .12       0
    4994     .05       0  5001.4     .12       0  5022.7     .12       0
  5326.6     .12       0
Bank Sta=4994,5001.4
XS Rating Curve= 0 ,0
Exp/Cntr=0.3,0.1

Type RM Length L Ch R = 1 ,6799    ,432,432,432
BEGIN DESCRIPTION:
Stream0417 15.0
END DESCRIPTION:
XS GIS Cut Line= 3
        2450375.       13817475.        2449975.       13817375.
      2449675.02     13817225.01
#Sta/Elev= 30
  4591.9  483.26    4631  480.07  4631.9  480.01  4656.3  476.89  4692.4  469.46
  4729.2  464.27  4774.9  460.64  4921.7  453.42  4939.8  450.45  4944.9  450.72
  4952.7  447.74    4981  446.67  4997.9  443.49  4998.4  442.99  5005.4  443.49
    5007  443.49  5012.6     448  5018.2  448.99  5071.3  450.16    5116  448.76
  5146.1  454.74  5174.7  458.01  5197.1  462.85  5213.8  470.24  5219.4  470.41
  5236.2  477.78  5241.8  478.36  5272.5     490  5303.3  496.21  5339.6  501.48
#Mann= 7 ,-1 , 0
  4591.9    .035       0    4631     .07       0  4631.9     .12       0
  4729.2     .12       0  4997.9     .05       0  5005.4     .12       0
  5146.1     .12       0
Bank Sta=4997.9,5005.4
XS Rating Curve= 0 ,0
Exp/Cntr=0.3,0.1

Type RM Length L Ch R = 1 ,6367    ,482,482,482
BEGIN DESCRIPTION:
Stream0417 14.0
END DESCRIPTION:
XS GIS Cut Line= 3
      2450325.04     13816874.98        2450025.       13817025.
        2449775.       13816975.
#Sta/Elev= 30
  4659.9  486.54  4673.9  486.16  4696.3  482.11  4716.4   476.4  4735.4  470.17
    4741  469.35  4757.8  464.23  4780.1  459.39  4802.5  456.45  4897.5  452.68
  4936.7  448.67  4942.2  448.84    4959  443.53  4983.2  443.52  4983.7  443.02
  4990.7  443.52  4997.9  443.76  5005.6  446.67  5025.9  449.62  5036.1  450.88
  5046.3  451.01  5066.7  456.36  5076.9  460.48  5087.8  463.49  5117.7   464.8
  5127.9  467.93  5168.7  476.39  5178.9  480.35  5219.7  486.51  5250.3  488.73
#Mann= 5 ,-1 , 0
  4659.9     .12       0  4716.4     .12       0  4983.2     .05       0
  4990.7     .12       0  5087.8     .12       0
Bank Sta=4983.2,4990.7
XS Rating Curve= 0 ,0
Exp/Cntr=0.3,0.1

Type RM Length L Ch R = 1 ,5885    ,457,457,457
BEGIN DESCRIPTION:
Stream0417 13.0
END DESCRIPTION:
XS GIS Cut Line= 3
      2450275.03     13816625.01        2450025.       13816575.
      2449824.99       13816675.
#Sta/Elev= 30
  4745.3   475.5  4758.8  474.54  4816.7  464.62  4837.1  460.24  4858.7  457.36
  4888.1  454.11  4908.5  450.69  4928.9  448.25  4949.3  447.72  4959.5  448.32
  4979.9  445.03  5003.1  444.64  5004.9  444.03  5005.4  443.53  5012.5  444.03
    5031  448.89    5045  449.09  5081.3  451.73  5098.1   456.4  5103.7  456.86
  5120.5  460.86  5126.1  460.86  5142.8  464.87  5148.4  465.32  5165.2  470.24
  5170.8  471.04  5187.6  475.55  5193.1  475.92  5209.9  479.14  5223.9  480.14
#Mann= 5 ,-1 , 0
  4745.3     .12       0  4758.8     .07       0  4858.7     .12       0
  5004.9     .05       0  5012.5     .12       0
Bank Sta=5004.9,5012.5
XS Rating Curve= 0 ,0
Exp/Cntr=0.3,0.1

Type RM Length L Ch R = 1 ,5428    ,448,448,448
BEGIN DESCRIPTION:
Stream0417 12.0
END DESCRIPTION:
XS GIS Cut Line= 3
      2450174.98     13816125.01        2450025.       13816175.
      2449725.03       13816225.
#Sta/Elev= 30
  4842.4  474.92    4845  474.92  4852.9  473.42    4874  471.61  4905.6  465.43
  4947.8  454.32  4958.3  448.96  4968.9  445.96  4979.4  444.13    5003  444.34
  5006.8  443.45  5007.3  442.95  5013.9  442.95  5014.4  443.45  5020.8  444.07
  5051.2  444.67  5061.3  446.22  5071.5  446.88  5089.2  446.56  5101.9  447.72
  5122.1  448.23    5150  451.15  5162.7  451.61  5203.2   454.8  5223.5  459.17
  5243.8  461.73  5271.7  463.02  5276.7  464.73  5284.4  464.27  5304.6  464.88
#Mann= 3 ,-1 , 0
  4842.4     .12       0  5006.8     .05       0  5014.4     .12       0
Bank Sta=5006.8,5014.4
XS Rating Curve= 0 ,0
Exp/Cntr=0.3,0.1

Type RM Length L Ch R = 1 ,4980    ,452,452,452
BEGIN DESCRIPTION:
Stream0417 11.0
END DESCRIPTION:
XS GIS Cut Line= 3
      2450174.99       13815875.        2449975.       13815775.
      2449625.01       13815875.
#Sta/Elev= 30
  4776.4  466.28  4807.1  463.56  4835.1  458.53  4851.9  454.43  4857.5  455.02
  4874.2  451.99  4896.6   450.4  4902.2  450.97  4918.9  449.57  4924.5  450.26
  4963.7  448.54  4982.9  446.04    4986  445.88  4991.6  443.25  5006.6  442.96
  5007.1  442.46  5014.3  442.96  5024.1  445.45  5050.7  445.49  5055.9  447.94
  5083.2  448.27  5094.9  449.66  5162.5  448.54  5176.8  447.17  5221.4  452.21
    5260  455.29  5322.4  457.45  5332.8   458.9  5347.1  458.81    5364  460.44
#Mann= 6 ,-1 , 0
  4776.4     .12       0  4982.9     .12       0  5006.6     .05       0
  5014.3     .12       0  5024.1     .12       0  5221.4     .07       0
Bank Sta=5006.6,5014.3
XS Rating Curve= 0 ,0
Exp/Cntr=0.3,0.1

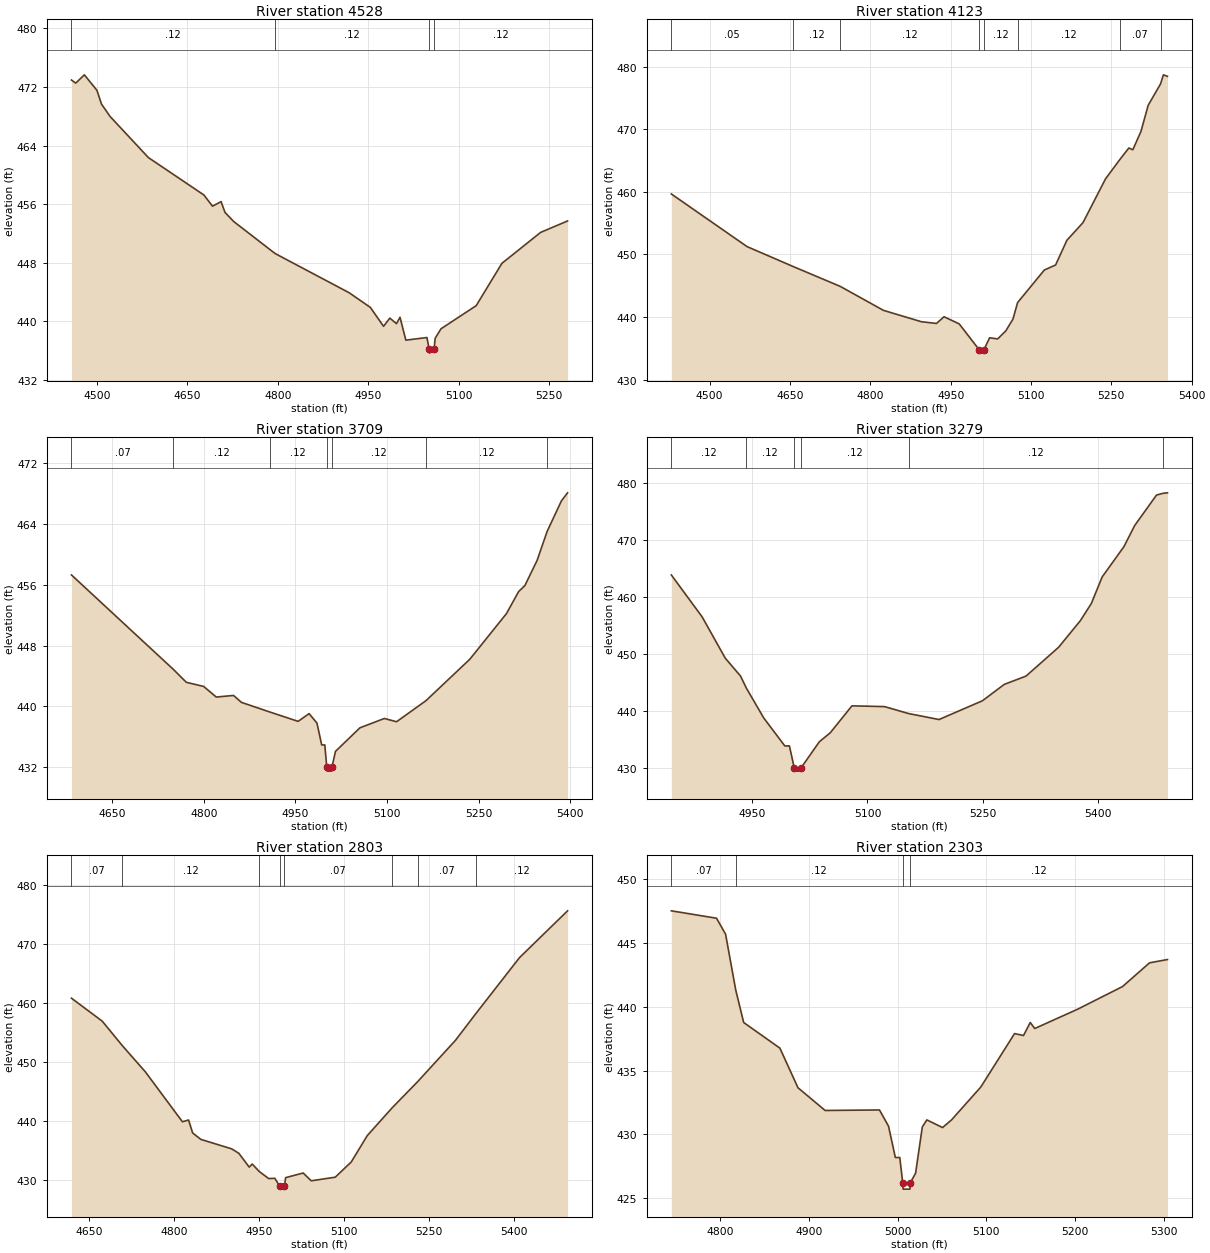
Type RM Length L Ch R = 1 ,4528    ,405,405,405
BEGIN DESCRIPTION:
Stream0417 10.0
END DESCRIPTION:
XS GIS Cut Line= 3
        2450425.       13815725.        2450025.       13815375.
      2449774.97     13815224.98
#Sta/Elev= 30
  4457.7  472.95  4464.8  472.53  4479.1  473.66  4499.9  471.55  4507.5  469.67
  4521.8  467.97  4585.4  462.36  4677.4  457.26  4691.7  455.73  4705.9  456.35
  4712.5  454.87  4726.8  453.64  4795.5  449.27  4918.5  443.91  4953.6  441.91
  4975.5  439.33  4985.9  440.45    4997  439.69  5002.8  440.57  5012.5  437.44
  5047.5   437.8  5051.2  436.17  5051.7  435.67  5059.3  436.17  5061.1  437.69
  5070.8  438.99  5129.2  442.15  5171.9  447.93  5236.1  452.15  5280.8  453.71
#Mann= 4 ,-1 , 0
  4457.7     .12       0  4795.5     .12       0  5051.2     .05       0
  5059.3     .12       0
Bank Sta=5051.2,5059.3
XS Rating Curve= 0 ,0
Exp/Cntr=0.3,0.1

Type RM Length L Ch R = 1 ,4123    ,414,414,414
BEGIN DESCRIPTION:
Stream0417 9.0
END DESCRIPTION:
XS GIS Cut Line= 3
      2450524.99     13815424.99        2450125.       13815025.
      2449925.02     13814725.03
#Sta/Elev= 30
  4428.6  459.64    4570  451.23  4655.8  448.06  4743.9  444.88  4824.6  441.05
  4895.3  439.24  4923.6  438.96  4937.7  440.03    4966  438.89  5003.7  434.72
  5004.2  434.22  5011.9  434.72  5022.8  436.67  5037.8  436.49  5052.9  437.76
  5066.4  439.66    5075  442.29    5125   447.5    5146   448.3    5167  452.24
  5197.1  455.06  5239.2  462.06  5265.8  465.13  5282.7  466.98  5290.2  466.71
  5305.3  469.62  5318.8   473.8  5341.9  477.22  5347.3  478.67  5354.8  478.43
#Mann= 8 ,-1 , 0
  4428.6     .05       0  4655.8     .12       0  4743.9     .12       0
  5003.7     .05       0  5011.9     .12       0    5075     .12       0
  5265.8     .07       0  5341.9     .12       0
Bank Sta=5003.7,5011.9
XS Rating Curve= 0 ,0
Exp/Cntr=0.3,0.1

Type RM Length L Ch R = 1 ,3709    ,430,430,430
BEGIN DESCRIPTION:
Stream0417 8.0
END DESCRIPTION:
XS GIS Cut Line= 3
      2450774.97     13814625.01        2450375.       13814725.
      2449974.98       13814725.
#Sta/Elev= 30
  4583.5  457.29  4750.2  444.87  4771.6  443.16  4799.9  442.62  4820.6  441.22
  4848.9  441.43  4861.8  440.52  4908.4  439.25  4954.6  438.02  4972.6  439.04
  4985.5  437.79  4993.2  434.92  4998.3  434.92  5001.6  431.97  5002.1  431.47
  5009.4  431.47  5009.9  431.97  5015.8  434.07  5055.8  437.17  5095.8   438.4
  5115.8  437.97  5163.9  440.74  5235.8   446.2  5295.8  452.21  5315.8  455.12
  5325.8  455.88  5345.8  459.18  5362.4  463.03  5385.8  467.05  5395.8   468.1
#Mann= 7 ,-1 , 0
  4583.5     .07       0  4750.2     .12       0  4908.4     .12       0
  5001.6     .05       0  5009.9     .12       0  5163.9     .12       0
  5362.4     .07       0
Bank Sta=5001.6,5009.9
XS Rating Curve= 0 ,0
Exp/Cntr=0.3,0.1

Type RM Length L Ch R = 1 ,3279    ,476,476,476
BEGIN DESCRIPTION:
Stream0417 7.0
END DESCRIPTION:
XS GIS Cut Line= 3
      2450424.99       13814325.        2450275.       13814325.
      2449924.98     13814675.02
#Sta/Elev= 30
    4845  463.84    4885  456.51    4915   449.3    4935  446.14  4942.5  444.05
    4965  438.84  4992.5  433.92  4998.5  433.92  5004.9  430.01  5005.4  429.51
  5012.8  429.51  5013.3  430.01  5037.4  434.65  5051.6  436.22  5079.8  440.94
  5122.3   440.8  5153.4  439.59    5193  438.54  5249.5  441.83  5277.8  444.69
  5306.1  446.14  5348.5  451.19  5376.8  455.85    5391  458.84  5405.1  463.49
  5433.4   468.8  5447.5  472.52  5475.8  477.83    5484  478.13    5490  478.22
#Mann= 6 ,-1 , 0
    4845     .12       0  4942.5     .12       0  5004.9     .05       0
  5013.3     .12       0  5153.4     .12       0    5484     .07       0
Bank Sta=5004.9,5013.3
XS Rating Curve= 0 ,0
Exp/Cntr=0.3,0.1

Type RM Length L Ch R = 1 ,2803    ,500,500,500
BEGIN DESCRIPTION:
Stream0417 6.0
END DESCRIPTION:
XS GIS Cut Line= 3
      2450424.96     13813775.02        2450075.       13813925.
      2449725.02     13814274.98
#Sta/Elev= 30
  4619.2   460.8  4673.6   456.9  4709.2  452.74  4749.7  448.32    4815  439.88
  4825.9  440.17  4833.1  437.98  4847.6  436.89    4902  435.29  4914.7  434.53
  4932.9   432.2  4938.3  432.72  4950.6  431.46  4967.3  430.26  4978.2   430.3
  4986.7  428.97  4987.2  428.47  4995.1  428.97  4997.2  430.41  5028.2   431.2
  5042.4  429.88  5084.8  430.49  5113.1  433.07  5141.4  437.54  5185.3  442.24
  5230.3  446.67  5296.9  453.65  5332.7  458.15  5410.1  467.67  5494.9  475.59
#Mann= 8 ,-1 , 0
  4619.2     .07       0  4709.2     .12       0  4950.6     .07       0
  4986.7     .05       0  4995.1     .07       0  5185.3     .12       0
  5230.3     .07       0  5332.7     .12       0
Bank Sta=4986.7,4995.1
XS Rating Curve= 0 ,0
Exp/Cntr=0.3,0.1

Type RM Length L Ch R = 1 ,2303    ,470,470,470
BEGIN DESCRIPTION:
Stream0417 5.0
END DESCRIPTION:
XS GIS Cut Line= 3
      2450324.96     13813474.99        2450075.       13813425.
      2449775.05     13813375.01
#Sta/Elev= 30
    4745  447.53  4795.9  446.95  4806.1   445.7  4817.6   441.3  4826.5  438.77
  4867.3  436.76  4887.7  433.65  4918.3  431.87  4979.5  431.91  4989.7  430.64
  4997.4  428.18  5002.4  428.18  5005.7   426.2  5006.2   425.7  5013.8   425.7
  5014.3   426.2  5020.2  426.95  5027.8  430.58  5032.9  431.13  5050.6  430.53
  5060.7  431.13  5093.7  433.71  5131.7   437.9  5141.8  437.75  5149.4  438.77
  5154.5   438.3  5202.7  439.81  5253.4  441.59  5283.8  443.45    5304  443.71
#Mann= 4 ,-1 , 0
    4745     .07       0  4817.6     .12       0  5005.7     .05       0
  5014.3     .12       0
Bank Sta=5005.7,5014.3
XS Rating Curve= 0 ,0
Exp/Cntr=0.3,0.1

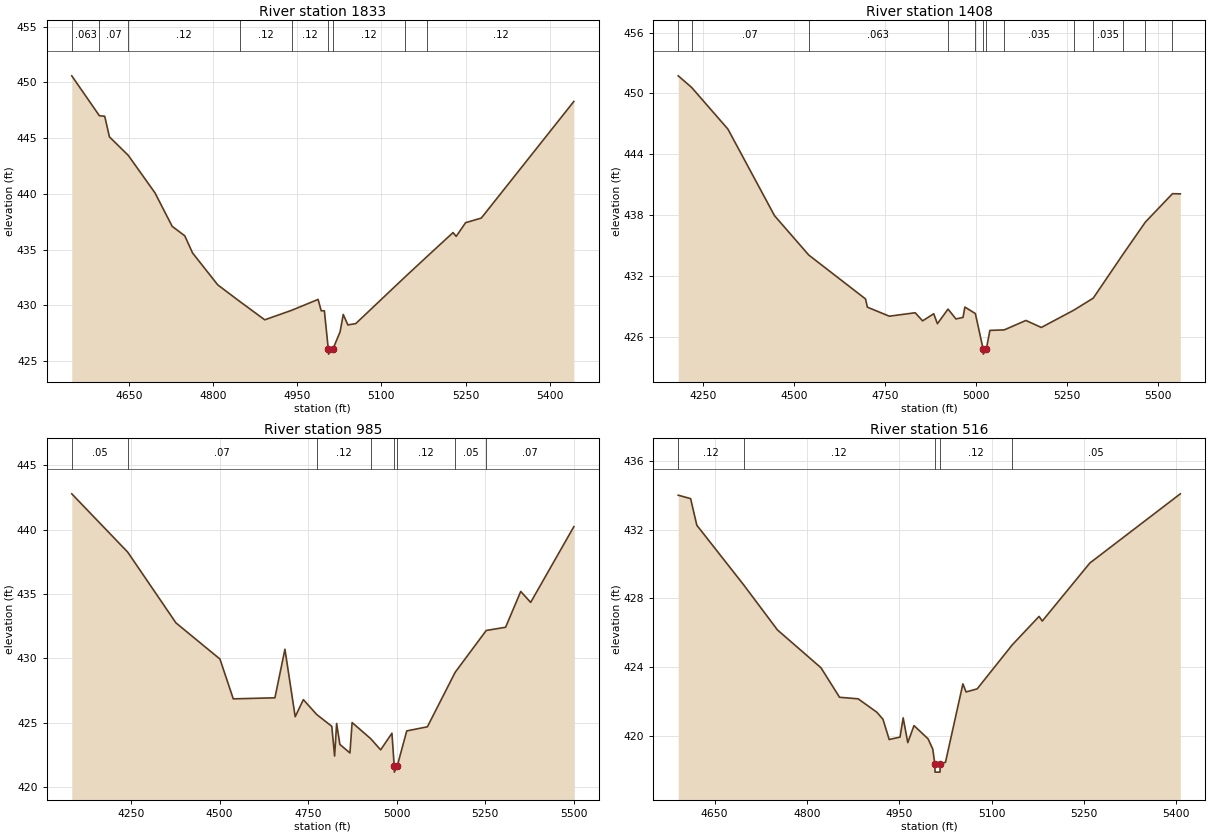
Type RM Length L Ch R = 1 ,1833    ,425,425,425
BEGIN DESCRIPTION:
Stream0417 4.0
END DESCRIPTION:
XS GIS Cut Line= 3
      2450475.01     13813425.01        2450275.       13813025.
      2449875.04     13812825.02
#Sta/Elev= 30
  4548.6  450.59  4597.8  447.01  4607.3  446.96  4615.7  445.11  4649.1  443.46
  4696.8  440.09  4727.5  437.08  4749.9  436.23  4763.8  434.69  4808.6  431.83
  4848.1  430.33  4892.4  428.69  4940.1  429.54  4987.4  430.52    4993   429.5
  4998.6   429.5  5005.5  426.11    5006  425.61  5014.2  426.11  5026.6  427.61
  5032.2  429.17  5040.5  428.23  5054.5  428.35  5141.5   432.5  5182.1   434.4
  5227.8  436.52  5233.4  436.18  5250.2  437.41  5278.1  437.82    5443  448.29
#Mann= 9 ,-1 , 0
  4548.6    .063       0  4597.8     .07       0  4649.1     .12       0
  4848.1     .12       0  4940.1     .12       0  5005.5     .05       0
  5014.2     .12       0  5141.5     .12       0  5182.1     .12       0
Bank Sta=5005.5,5014.2
XS Rating Curve= 0 ,0
Exp/Cntr=0.3,0.1

Type RM Length L Ch R = 1 ,1408    ,423,423,423
BEGIN DESCRIPTION:
Stream0417 3.0
END DESCRIPTION:
XS GIS Cut Line= 3
      2450625.01     13813475.04        2450475.       13812675.
      2450074.97     13812274.97
#Sta/Elev= 30
  4181.2  451.73  4217.9  450.59  4317.7  446.48  4445.8  437.94  4539.9  434.06
  4695.9  429.73    4701  428.92  4761.2  428.03  4832.4  428.37  4852.7  427.57
  4883.3  428.27  4893.4  427.29  4922.6  428.73  4944.3  427.76  4963.8  427.91
  4968.9  428.93  4997.7  428.29  5019.1  424.79  5019.6  424.29  5027.8  424.79
  5037.6  426.63  5077.1  426.68  5136.6  427.61    5179  426.92  5268.5  428.63
  5321.6  429.81  5403.9  434.16  5464.9  437.31  5539.4  440.11  5560.9  440.09
#Mann= 13 ,-1 , 0
  4181.2    .035       0  4217.9     .07       0  4539.9    .063       0
  4922.6    .035       0  4997.7     .12       0  5019.1     .05       0
  5027.8     .12       0  5077.1    .035       0  5268.5     .12       0
  5321.6    .035       0  5403.9     .12       0  5464.9    .035       0
  5539.4     .07       0
Bank Sta=5019.1,5027.8
XS Rating Curve= 0 ,0
Exp/Cntr=0.3,0.1

Type RM Length L Ch R = 1 ,985     ,469,469,469
BEGIN DESCRIPTION:
Stream0417 2.0
END DESCRIPTION:
XS GIS Cut Line= 3
      2451574.99     13812874.99        2450775.       13812425.
      2450374.97     13812124.98
#Sta/Elev= 30
  4082.4  442.77  4240.5  438.24  4376.6  432.75  4500.9  429.94  4538.5  426.85
  4656.1  426.93  4684.4   430.7  4713.4  425.46  4736.4  426.79  4774.3  425.63
  4816.7  424.72  4824.7  422.41  4830.4  424.94  4839.6  423.31    4868  422.65
  4874.1  425.01  4926.5  423.76  4954.7  422.89  4986.6  424.18  4992.9  421.66
  4993.4  421.16  5001.8  421.66  5028.4  424.36  5086.7  424.68  5165.1  428.91
  5252.9  432.16  5307.6  432.41  5350.3  435.19  5378.4  434.34  5500.3  440.22
#Mann= 8 ,-1 , 0
  4082.4     .05       0  4240.5     .07       0  4774.3     .12       0
  4926.5     .12       0  4992.9     .05       0  5001.8     .12       0
  5165.1     .05       0  5252.9     .07       0
Bank Sta=4992.9,5001.8
XS Rating Curve= 0 ,0
Exp/Cntr=0.3,0.1

Type RM Length L Ch R = 1 ,516     ,0,0,0
BEGIN DESCRIPTION:
Stream0417 1.0
END DESCRIPTION:
XS GIS Cut Line= 3
      2451374.96       13812075.        2450975.       13812025.
      2450574.98       13812125.
#Sta/Elev= 30
    4591  434.01  4611.1  433.81  4621.2  432.26    4697   428.8  4752.2  426.16
  4822.8  423.96    4853  422.24  4883.2  422.15  4913.5  421.37  4923.5  420.96
  4933.6  419.78  4951.2  419.92  4956.3  421.04  4963.8   419.6  4973.9  420.59
  4996.7  419.82  5004.4  419.22  5007.6  418.38  5008.1  417.88  5016.1  417.88
  5016.6  418.38    5025  418.45  5053.3  423.02  5058.5  422.55  5076.5  422.73
  5133.4  425.29    5177  426.95  5182.2  426.68  5259.5  430.06  5406.4  434.09
#Mann= 5 ,-1 , 0
    4591     .12       0    4697     .12       0  5007.6     .05       0
  5016.6     .12       0  5133.4     .05       0
Bank Sta=5007.6,5016.6
XS Rating Curve= 0 ,0
Exp/Cntr=0.3,0.1

Chan Stop Cuts=-1
Use User Specified Reach Order=0
Composite Channel Slope=5