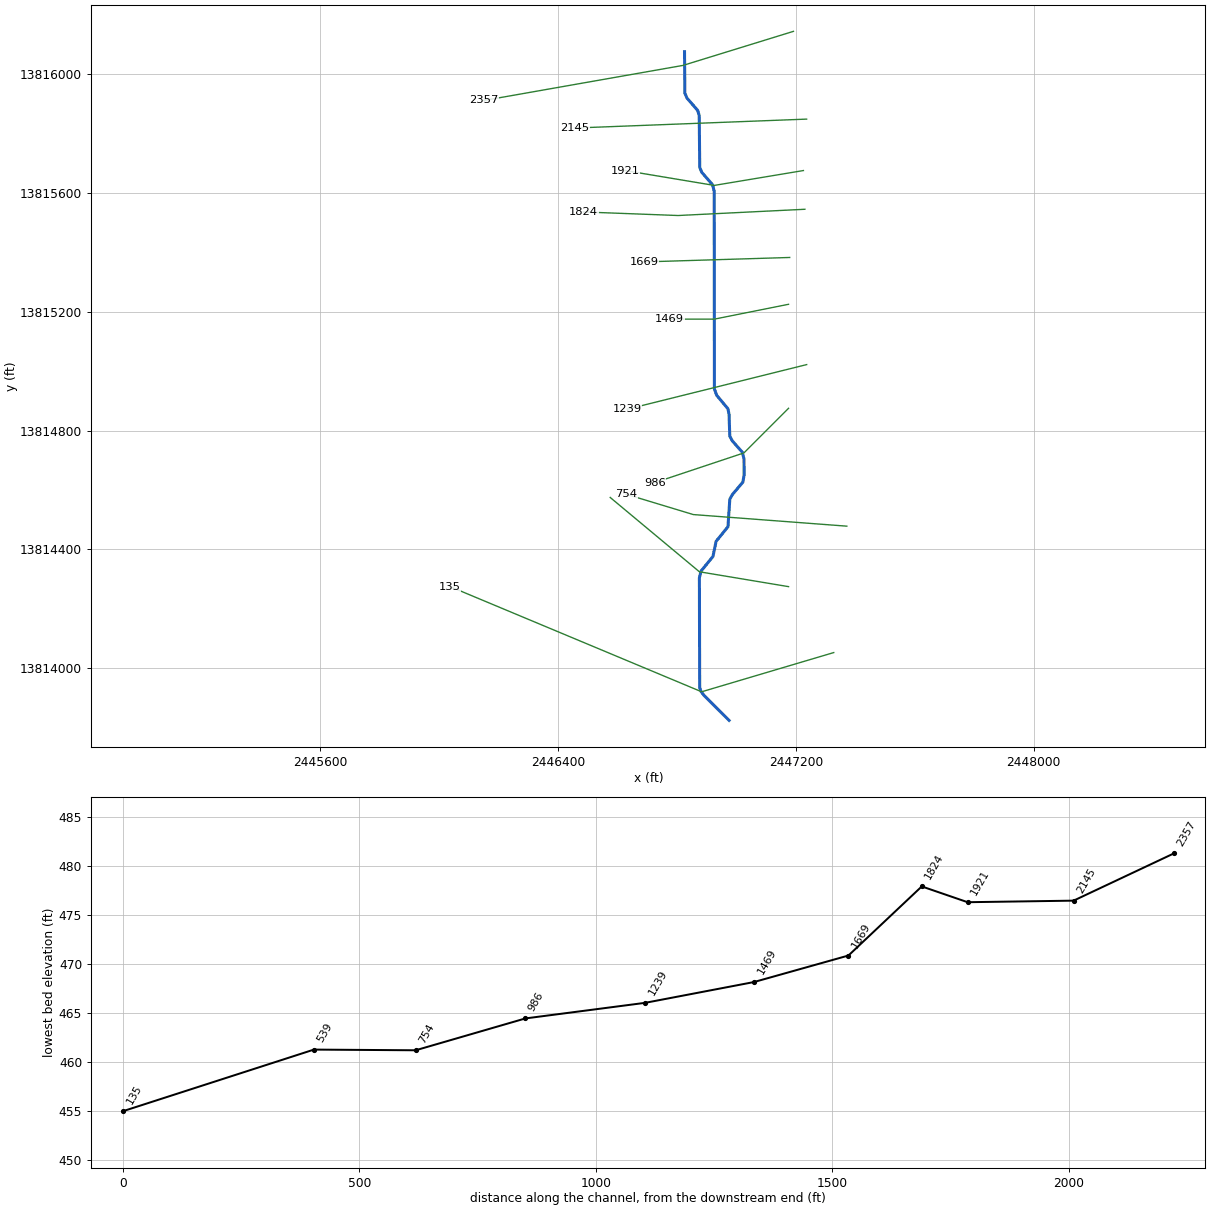
--- Stream0420.prj (project) ---

Proj Title=Stream0420 Base Level Engineering
Current Plan=p01
Default Exp/Contr=0.3,0.1
English Units
Geom File=g01
Flow File=f01
Plan File=p01
BEGIN DESCRIPTION:
Stream0420
END DESCRIPTION:

--- Stream0420.p01 (plan) ---

Plan Title=Multiple Run
Short Identifier=Multiple
Geom File=g01
Flow File=f01
Subcritical Flow
K Sum by GR= 0
Std Step Tol= 0.01
Critical Tol= 0.01
Num of Std Step Trials= 20
Max Error Tol= 0.3
Flow Tol Ratio= 0.001
Split Flow NTrial= 30
Split Flow Tol= 0.02
Split Flow Ratio= 0.02
Log Output Level= 0
Friction Slope Method= 1
Unsteady Friction Slope Method= 2
Unsteady Bridges Friction Slope Method= 1
Parabolic Critical Depth
Global Vel Dist=  1 , 1 , 1
Global Log Level= 0
CheckData=True
Encroach Param= -1, 0, 0, 0
BEGIN DESCRIPTION:
Multiple Run
END DESCRIPTION:

--- Stream0420.f01 (steady flow) ---

Flow Title=Multiple
Number of Profiles=7
Profile Names=10-year,25-year,50-year,1pct_min,100-year,1pct_plu,500-year
River Rch & RM= Stream0420,Reach-1,2357
     210     315     404     252     503    1004     771
River Rch & RM= Stream0420,Reach-1,135
     834    1358    1836    1201    2396    4781    4044
Boundary for River Rch & Prof#=Stream0420,Reach-1,1
Up Type=0
Dn Type=3
Dn Slope=0.005
Boundary for River Rch & Prof#=Stream0420,Reach-1,2
Up Type=0
Dn Type=3
Dn Slope=0.005
Boundary for River Rch & Prof#=Stream0420,Reach-1,3
Up Type=0
Dn Type=3
Dn Slope=0.005
Boundary for River Rch & Prof#=Stream0420,Reach-1,4
Up Type=0
Dn Type=3
Dn Slope=0.005
Boundary for River Rch & Prof#=Stream0420,Reach-1,5
Up Type=0
Dn Type=3
Dn Slope=0.005
Boundary for River Rch & Prof#=Stream0420,Reach-1,6
Up Type=0
Dn Type=3
Dn Slope=0.005
Boundary for River Rch & Prof#=Stream0420,Reach-1,7
Up Type=0
Dn Type=3
Dn Slope=0.005

--- Stream0420.g01 (geometry) ---

Geom Title=Existing Conditions

River Reach=Stream0420,Reach-1
Reach XY= 30
      2446825.00     13816075.00      2446826.17     13815935.48
      2446833.13     13815918.94      2446869.26     13815877.34
      2446874.48     13815859.78      2446876.22     13815685.51
      2446883.14     13815668.94      2446919.25     13815627.33
      2446924.93     13815604.97      2446925.52     13814940.22
      2446933.14     13814918.94      2446971.14     13814873.40
      2446974.76     13814854.90      2446977.36     13814780.97
      2446985.90     13814765.37      2447019.32     13814727.31
      2447025.10     13814704.90      2447025.40     13814650.00
      2447021.30     13814626.60      2446985.90     13814584.63
      2446977.36     13814569.03      2446971.17     13814476.58
      2446931.11     13814427.18      2446920.81     13814376.74
      2446880.71     13814327.35      2446875.06     13814304.97
      2446876.02     13813935.42      2446880.40     13813922.52
      2446891.33     13813908.19      2446975.00     13813825.00

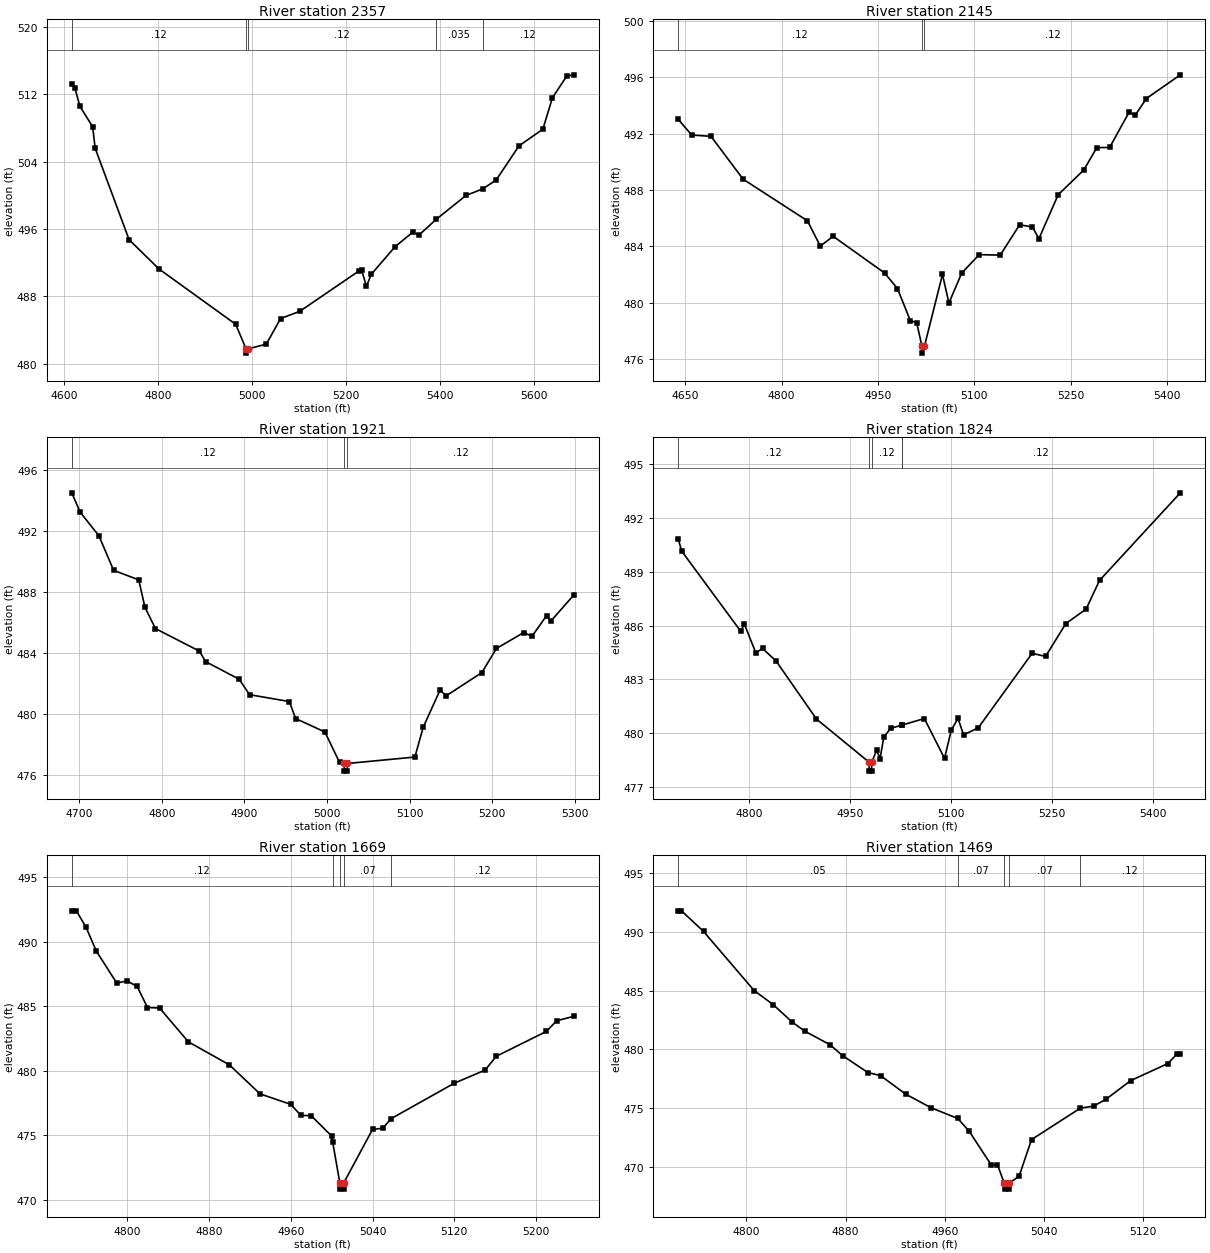
Type RM Length L Ch R = 1,2357,212,212,212
BEGIN DESCRIPTION:
XS6764
END DESCRIPTION:
XS GIS Cut Line= 3
      2447191.65     13816143.40      2446820.14     13816028.82
      2446150.04     13815910.77
#Sta/Elev= 30
  4616.2  513.23  4622.8  512.75  4633.6  510.56  4660.7  508.14  4666.0  505.59
  4738.3  494.73  4801.8  491.26  4965.2  484.69  4987.4  481.76  4987.7  481.26
  4991.4  481.76  5030.5  482.33  5061.0  485.37  5101.6  486.22  5228.6  491.05
  5233.7  491.09  5243.7  489.20  5253.9  490.61  5304.7  493.90  5342.1  495.61
  5355.4  495.27  5391.9  497.13  5455.6  499.98  5491.4  500.77  5519.9  501.81
  5568.7  505.88  5619.4  507.85  5639.7  511.57  5670.2  514.16  5685.4  514.31
#Mann=5,-1,0
  4616.2    0.12       0  4987.4    0.05       0  4991.4    0.12       0
  5391.9   0.035       0  5491.4    0.12       0
Bank Sta=4987.4,4991.4
Exp/Cntr=0.3,0.1

Type RM Length L Ch R = 1,2145,224,224,224
BEGIN DESCRIPTION:
E21017
END DESCRIPTION:
XS GIS Cut Line= 2
      2447235.97     13815848.09      2446455.05     13815818.05
#Sta/Elev= 30
  4639.2  493.01  4660.2  491.90  4690.2  491.81  4740.2  488.77  4840.3  485.82
  4860.3  484.03  4880.4  484.72  4960.4  482.12  4980.4  481.02  5000.4  478.75
  5010.4  478.59  5018.5  476.94  5018.7  476.44  5022.5  476.94  5050.5  482.02
  5060.5  479.99  5080.5  482.12  5107.7  483.42  5140.5  483.39  5170.6  485.54
  5190.6  485.38  5200.6  484.55  5230.6  487.67  5270.6  489.43  5290.7  491.01
  5310.7  491.02  5340.7  493.50  5350.7  493.32  5367.9  494.49  5420.7  496.17
#Mann=3,-1,0
  4639.2    0.12       0  5018.5    0.05       0  5022.5    0.12       0
Bank Sta=5018.5,5022.5
Exp/Cntr=0.3,0.1

Type RM Length L Ch R = 1,1921,97,97,97
BEGIN DESCRIPTION:
Stream0420 4.0
END DESCRIPTION:
XS GIS Cut Line= 3
      2447225.00     13815675.00      2446925.00     13815625.00
      2446624.98     13815675.00
#Sta/Elev= 30
  4690.8  494.48  4700.9  493.22  4723.8  491.66  4741.5  489.41  4771.9  488.79
  4779.5  486.99  4792.2  485.60  4845.4  484.13  4853.0  483.44  4893.6  482.29
  4906.2  481.28  4954.4  480.83  4962.0  479.72  4997.5  478.84  5015.2  476.85
  5020.8  476.78  5021.1  476.28  5024.6  476.28  5024.8  476.78  5106.5  477.20
  5116.6  479.15  5136.9  481.57  5144.5  481.21  5187.6  482.72  5205.3  484.30
  5238.3  485.34  5248.4  485.10  5266.1  486.45  5271.2  486.09  5299.1  487.80
#Mann=3,-1,0
  4690.8    0.12       0  5020.8    0.05       0  5024.8    0.12       0
Bank Sta=5020.8,5024.8
Exp/Cntr=0.3,0.1

Type RM Length L Ch R = 1,1824,155,155,155
BEGIN DESCRIPTION:
E21016
END DESCRIPTION:
XS GIS Cut Line= 3
      2447230.03     13815544.72      2446803.50     13815523.70
      2446485.08     13815535.71
#Sta/Elev= 30
  4694.7  490.83  4699.7  490.15  4787.7  485.67  4792.7  486.10  4809.9  484.48
  4819.9  484.72  4839.9  484.03  4900.0  480.79  4978.1  478.39  4978.3  477.89
  4981.8  477.89  4982.1  478.39  4989.4  479.05  4994.4  478.59  5000.1  479.79
  5010.1  480.27  5027.4  480.46  5027.6  480.46  5060.2  480.82  5090.2  478.60
  5100.2  480.17  5110.2  480.83  5118.5  479.91  5140.3  480.30  5220.3  484.45
  5240.3  484.28  5270.4  486.11  5300.4  486.91  5320.4  488.51  5440.4  493.39
#Mann=5,-1,0
  4694.7    0.12       0  4978.1    0.05       0  4982.1    0.12       0
  5027.4    0.07       0  5027.6    0.12       0
Bank Sta=4978.1,4982.1
Exp/Cntr=0.3,0.1

Type RM Length L Ch R = 1,1669,200,200,200
BEGIN DESCRIPTION:
E21015
END DESCRIPTION:
XS GIS Cut Line= 2
      2447178.99     13815382.53      2446688.22     13815367.56
#Sta/Elev= 30
  4745.9  492.40  4750.4  492.40  4759.9  491.12  4769.9  489.28  4789.9  486.80
  4799.9  486.97  4809.9  486.54  4819.9  484.91  4831.8  484.87  4859.9  482.25
  4900.0  480.47  4930.0  478.22  4960.0  477.41  4970.0  476.55  4980.0  476.53
  5000.0  474.96  5001.0  474.51  5008.0  471.34  5008.3  470.84  5011.8  470.84
  5012.0  471.34  5040.0  475.46  5050.0  475.56  5058.4  476.31  5120.1  479.05
  5150.1  480.06  5161.0  481.13  5210.1  483.06  5220.1  483.88  5236.9  484.23
#Mann=5,-1,0
  4745.9    0.12       0  5001.0    0.07       0  5008.0    0.05       0
  5012.0    0.07       0  5058.4    0.12       0
Bank Sta=5008,5012
Exp/Cntr=0.3,0.1

Type RM Length L Ch R = 1,1469,230,230,230
BEGIN DESCRIPTION:
Stream0420 3.0
END DESCRIPTION:
XS GIS Cut Line= 3
      2447175.03     13815225.01      2446925.00     13815175.00
      2446774.98     13815175.00
#Sta/Elev= 30
  4745.0  491.77  4747.6  491.77  4765.4  490.02  4806.2  485.00  4821.5  483.81
  4836.8  482.33  4847.0  481.55  4867.4  480.40  4877.6  479.47  4898.0  478.03
  4908.2  477.77  4928.6  476.19  4949.0  475.04  4970.5  474.13  4979.6  473.06
  4997.4  470.20  5002.5  470.20  5008.0  468.63  5008.2  468.13  5011.7  468.13
  5012.0  468.63  5020.0  469.24  5030.0  472.34  5069.4  475.01  5080.0  475.18
  5090.0  475.76  5110.0  477.35  5140.0  478.80  5147.5  479.63  5150.0  479.63
#Mann=5,-1,0
  4745.0    0.05       0  4970.5    0.07       0  5008.0    0.05       0
  5012.0    0.07       0  5069.4    0.12       0
Bank Sta=5008,5012
Exp/Cntr=0.3,0.1

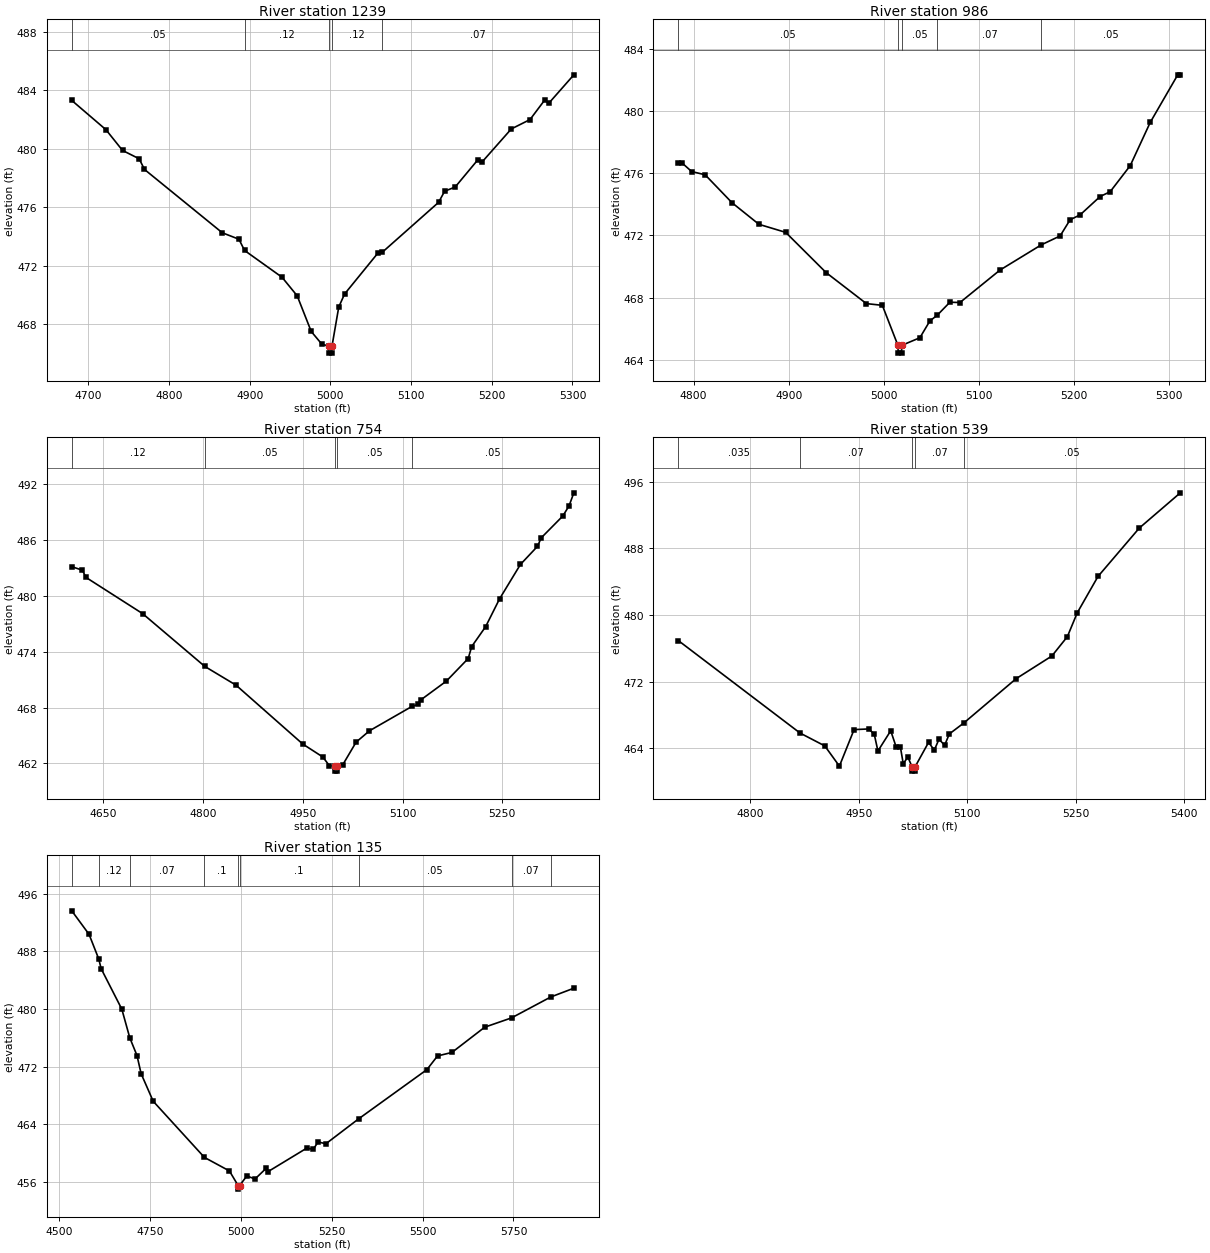
Type RM Length L Ch R = 1,1239,253,253,253
BEGIN DESCRIPTION:
E21014
END DESCRIPTION:
XS GIS Cut Line= 2
      2447236.02     13815022.09      2446632.32     13814871.91
#Sta/Elev= 30
  4679.6  483.29  4721.9  481.29  4742.5  479.87  4763.1  479.30  4769.7  478.57
  4866.1  474.24  4886.7  473.80  4893.7  473.03  4940.1  471.20  4958.9  469.93
  4976.3  467.49  4989.8  466.60  4998.1  466.51  4998.4  466.01  5001.9  466.01
  5002.1  466.51  5010.4  469.16  5017.6  470.05  5058.9  472.85  5064.4  472.91
  5134.1  476.32  5141.6  477.08  5154.7  477.37  5182.9  479.24  5188.0  479.08
  5224.2  481.34  5247.4  481.98  5265.5  483.31  5270.7  483.10  5301.7  485.04
#Mann=5,-1,0
  4679.6    0.05       0  4893.7    0.12       0  4998.1    0.05       0
  5002.1    0.12       0  5064.4    0.07       0
Bank Sta=4998.1,5002.1
Exp/Cntr=0.3,0.1

Type RM Length L Ch R = 1,986,232,232,232
BEGIN DESCRIPTION:
Stream0420 2.0
END DESCRIPTION:
XS GIS Cut Line= 3
      2447175.00     13814875.00      2447025.00     13814725.00
      2446724.96     13814624.99
#Sta/Elev= 30
  4783.8  476.70  4787.3  476.70  4797.9  476.12  4812.1  475.91  4840.4  474.11
  4868.7  472.72  4896.9  472.20  4939.4  469.61  4981.8  467.61  4998.6  467.50
  5015.0  464.92  5015.3  464.42  5018.8  464.42  5019.0  464.92  5038.1  465.41
  5048.6  466.49  5056.5  466.87  5069.7  467.70  5080.3  467.68  5122.4  469.77
  5166.0  471.40  5185.7  471.97  5196.2  473.01  5206.8  473.33  5227.8  474.51
  5238.4  474.82  5259.5  476.50  5280.5  479.28  5309.5  482.35  5312.2  482.35
#Mann=5,-1,0
  4783.8    0.05       0  5015.0    0.05       0  5019.0    0.05       0
  5056.5    0.07       0  5166.0    0.05       0
Bank Sta=5015,5019
Exp/Cntr=0.3,0.1

Type RM Length L Ch R = 1,754,215,215,215
BEGIN DESCRIPTION:
E21013
END DESCRIPTION:
XS GIS Cut Line= 3
      2447371.20     13814478.43      2446854.56     13814517.48
      2446628.12     13814586.00
#Sta/Elev= 30
  4602.8  483.12  4618.9  482.74  4623.9  481.98  4709.3  478.08  4802.8  472.41
  4849.7  470.40  4950.0  464.08  4980.1  462.69  4990.1  461.75  4998.1  461.67
  4998.4  461.17  5001.9  461.17  5002.1  461.67  5010.2  461.86  5030.2  464.28
  5050.3  465.50  5114.2  468.12  5123.3  468.33  5127.7  468.83  5165.8  470.83
  5198.7  473.26  5204.0  474.55  5224.9  476.68  5245.8  479.66  5277.2  483.36
  5302.8  485.30  5308.5  486.22  5340.9  488.56  5350.3  489.65  5357.5  491.05
#Mann=5,-1,0
  4602.8    0.12       0  4802.8    0.05       0  4998.1    0.05       0
  5002.1    0.05       0  5114.2    0.05       0
Bank Sta=4998.1,5002.1
Exp/Cntr=0.3,0.1

Type RM Length L Ch R = 1,539,404,404,404
BEGIN DESCRIPTION:
Stream0420 1.0
END DESCRIPTION:
XS GIS Cut Line= 3
      2447175.00     13814275.00      2446875.00     13814325.00
      2446574.96     13814575.03
#Sta/Elev= 30
  4700.1  476.94  4868.6  465.82  4902.9  464.27  4923.1  461.84  4943.4  466.23
  4963.7  466.31  4971.3  465.68  4976.4  463.66  4994.1  466.09  5001.7  464.13
  5007.5  464.13  5011.4  462.15  5017.9  462.92  5023.7  461.74  5024.0  461.24
  5027.5  461.24  5027.7  461.74  5046.5  464.70  5054.4  463.76  5060.9  465.08
  5068.7  464.35  5075.2  465.71  5095.0  467.01  5167.6  472.35  5217.1  475.08
  5238.5  477.40  5252.2  480.27  5280.9  484.64  5338.1  490.46  5394.8  494.69
#Mann=5,-1,0
  4700.1   0.035       0  4868.6    0.07       0  5023.7    0.05       0
  5027.7    0.07       0  5095.0    0.05       0
Bank Sta=5023.7,5027.7
Exp/Cntr=0.3,0.1

Type RM Length L Ch R = 1,135,0,0,0
BEGIN DESCRIPTION:
XS6763
END DESCRIPTION:
XS GIS Cut Line= 3
      2447327.10     13814053.13      2446882.64     13813921.18
      2446035.42     13814275.34
#Sta/Elev= 30
  4534.3  493.65  4581.9  490.38  4608.5  486.96  4615.2  485.60  4672.1  479.97
  4694.0  475.99  4713.8  473.53  4725.2  471.00  4758.4  467.17  4899.4  459.36
  4968.2  457.48  4992.1  455.45  4992.3  454.95  4996.1  455.45  5016.2  456.78
  5038.7  456.36  5069.2  457.84  5074.7  457.39  5180.7  460.64  5199.1  460.49
  5212.2  461.51  5233.8  461.26  5323.5  464.71  5511.8  471.57  5541.0  473.47
  5580.7  473.96  5670.9  477.47  5744.6  478.76  5852.7  481.67  5916.2  482.89
#Mann=9,-1,0
  4534.3    0.07       0  4608.5    0.12       0  4694.0    0.07       0
  4899.4     0.1       0  4992.1    0.05       0  4996.1     0.1       0
  5323.5    0.05       0  5744.6    0.07       0  5852.7   0.035       0
Bank Sta=4992.1,4996.1
Exp/Cntr=0.3,0.1

Chan Stop Cuts=-1