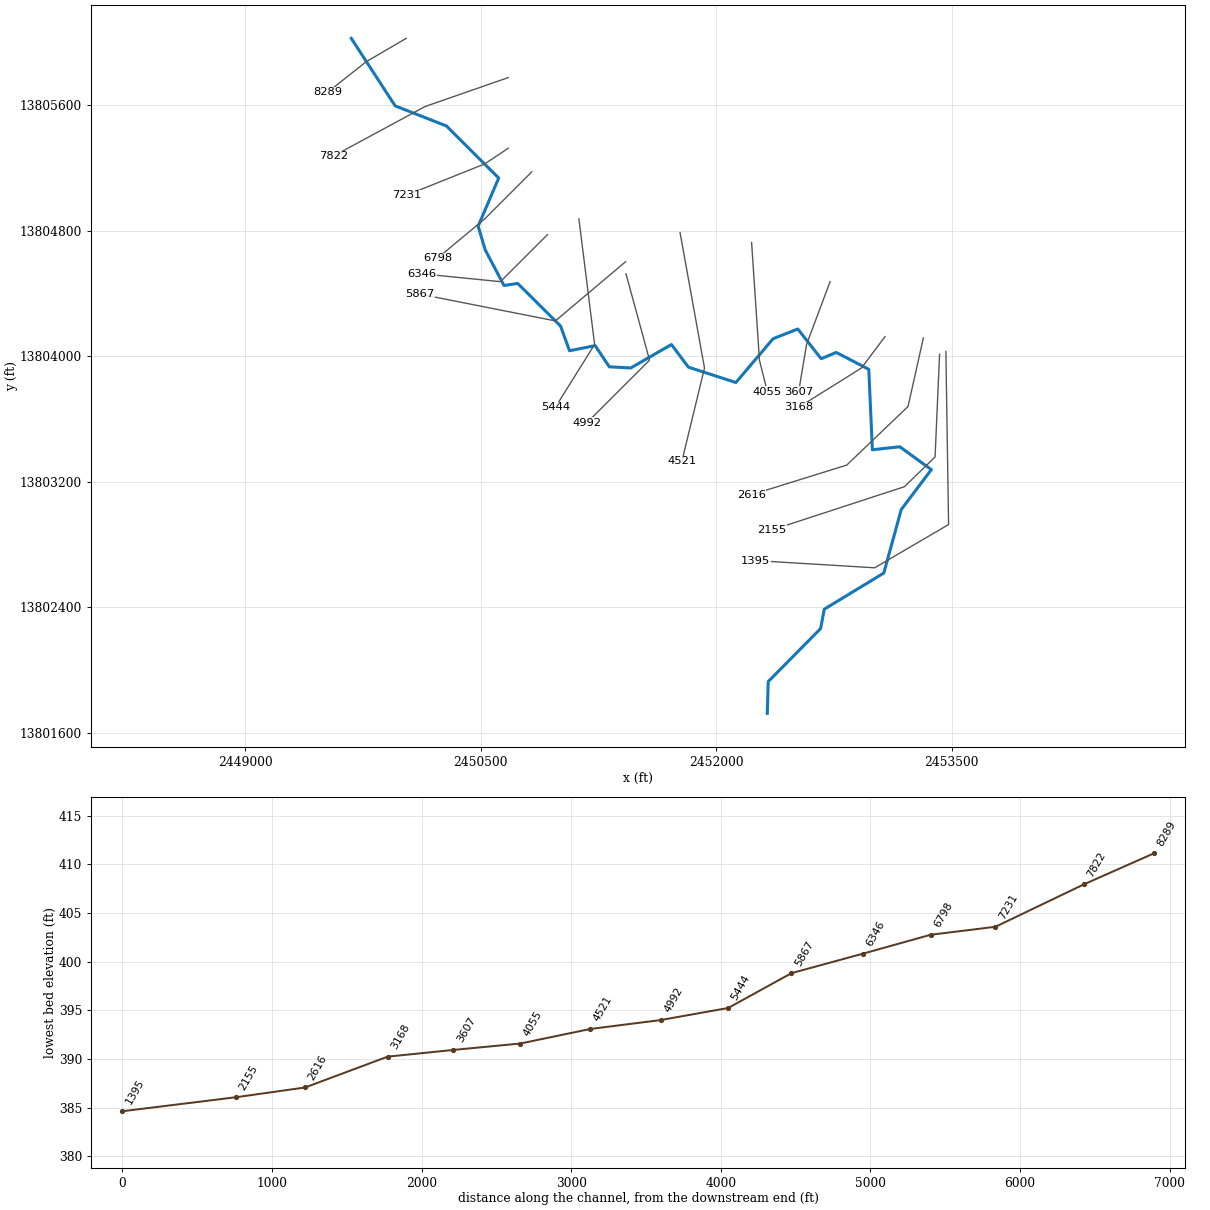
--- Stream0422.prj (project) ---

Proj Title=Stream0422 Base Level Engineering
Current Plan=p01
Default Exp/Contr=0.3,0.1
English Units
Geom File=g01
Flow File=f01
Plan File=p01
BEGIN DESCRIPTION:
Stream0422
END DESCRIPTION:

--- Stream0422.p01 (plan) ---

Plan Title=Multiple Run
Short Identifier=Multiple
Geom File=g01
Flow File=f01
Subcritical Flow
K Sum by GR= 0
Std Step Tol= 0.01
Critical Tol= 0.01
Num of Std Step Trials= 20
Max Error Tol= 0.3
Flow Tol Ratio= 0.001
Split Flow NTrial= 30
Split Flow Tol= 0.02
Split Flow Ratio= 0.02
Log Output Level= 0
Friction Slope Method= 1
Unsteady Friction Slope Method= 2
Unsteady Bridges Friction Slope Method= 1
Parabolic Critical Depth
Global Vel Dist=  1 , 1 , 1
Global Log Level= 0
CheckData=True
Encroach Param= -1, 0, 0, 0
BEGIN DESCRIPTION:
Multiple Run
END DESCRIPTION:

--- Stream0422.f01 (steady flow) ---

Flow Title=Multiple
Number of Profiles=7
Profile Names=10-year,25-year,50-year,1pct_min,100-year,1pct_plu,500-year
River Rch & RM= Stream0422,Reach-1,8289
     460     724     957     614    1224    2443    1981
River Rch & RM= Stream0422,Reach-1,5444
     814    1318    1775    1156    2307    4604    3861
Boundary for River Rch & Prof#=Stream0422,Reach-1,1
Up Type=0
Dn Type=3
Dn Slope=0.005
Boundary for River Rch & Prof#=Stream0422,Reach-1,2
Up Type=0
Dn Type=3
Dn Slope=0.005
Boundary for River Rch & Prof#=Stream0422,Reach-1,3
Up Type=0
Dn Type=3
Dn Slope=0.005
Boundary for River Rch & Prof#=Stream0422,Reach-1,4
Up Type=0
Dn Type=3
Dn Slope=0.005
Boundary for River Rch & Prof#=Stream0422,Reach-1,5
Up Type=0
Dn Type=3
Dn Slope=0.005
Boundary for River Rch & Prof#=Stream0422,Reach-1,6
Up Type=0
Dn Type=3
Dn Slope=0.005
Boundary for River Rch & Prof#=Stream0422,Reach-1,7
Up Type=0
Dn Type=3
Dn Slope=0.005

--- Stream0422.g01 (geometry) ---

Geom Title=Existing Conditions

River Reach=Stream0422,Reach-1
Reach XY= 30
      2449675.00     13806025.00      2449954.53     13805594.62
      2450281.06     13805466.86      2450614.04     13805135.00
      2450483.08     13804828.30      2450528.62     13804676.50
      2450647.88     13804450.59      2450734.99     13804463.75
      2451008.65     13804191.67      2451065.05     13804034.99
      2451228.67     13804067.31      2451318.53     13803932.69
      2451454.97     13803925.04      2451714.51     13804074.51
      2451822.33     13803930.42      2452125.04     13803832.52
      2452361.76     13804111.39      2452519.15     13804173.46
      2452668.25     13803984.14      2452764.30     13804024.20
      2452971.50     13803916.54      2452994.44     13803404.24
      2453168.96     13803423.37      2453370.02     13803277.55
      2453178.46     13803023.75      2453067.15     13802618.81
      2452688.23     13802388.72      2452664.49     13802265.19
      2452330.81     13801927.29      2452325.00     13801725.00

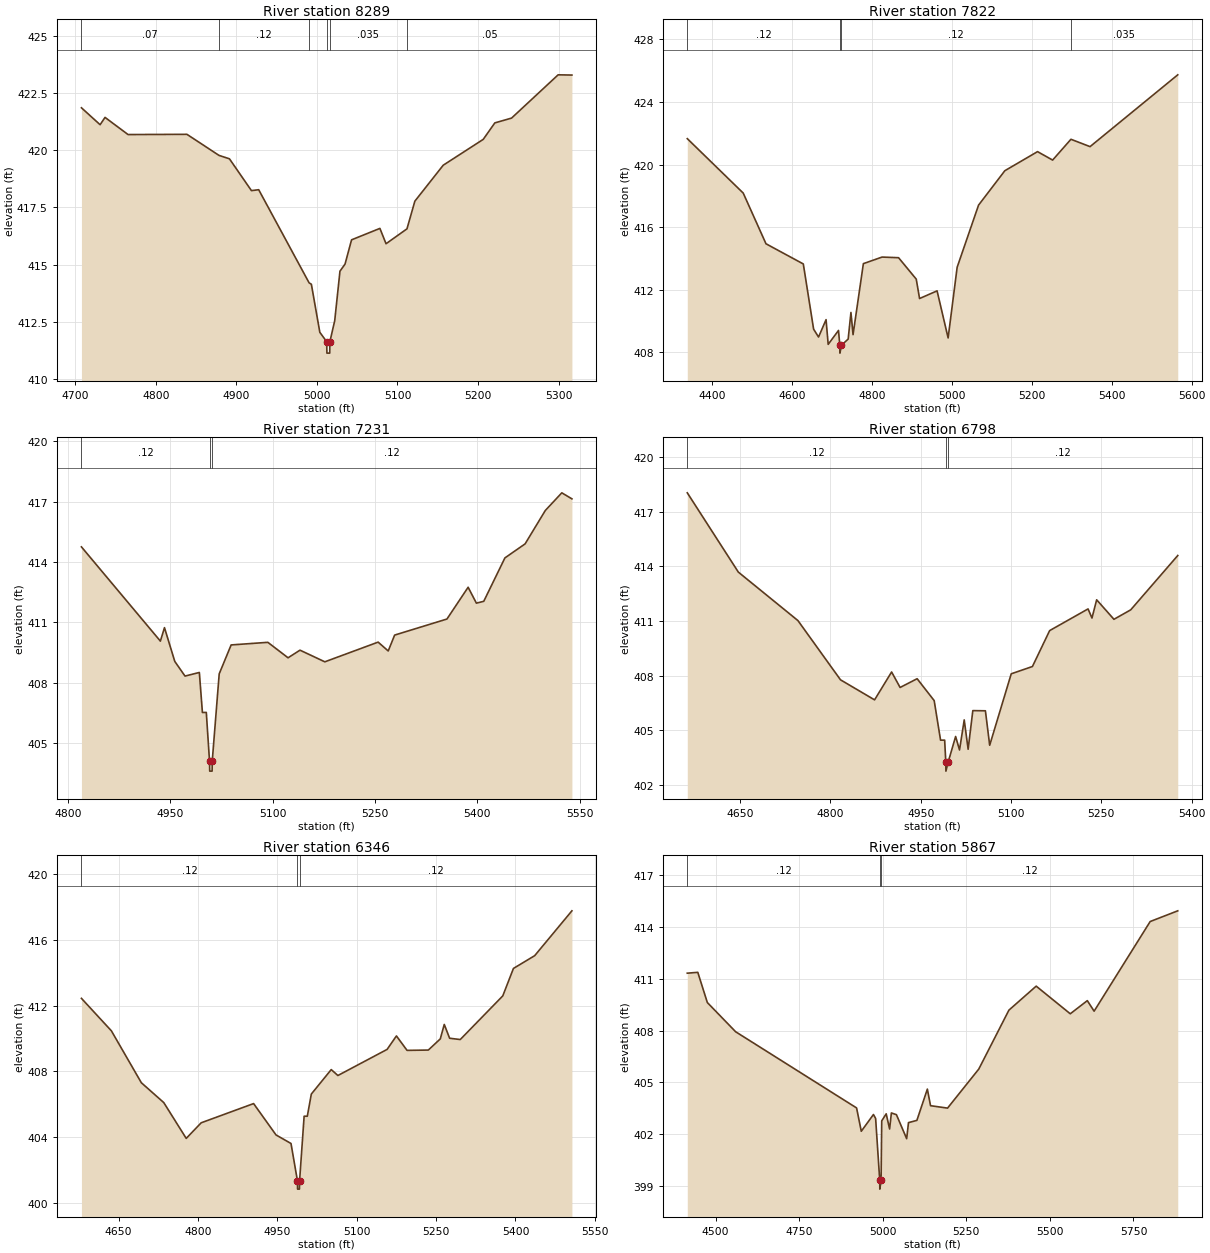
Type RM Length L Ch R = 1,8289,467,467,467
BEGIN DESCRIPTION:
Stream0422 14.0
END DESCRIPTION:
XS GIS Cut Line= 3
      2450024.99     13806024.99      2449769.10     13805875.26
      2449523.91     13805681.48
#Sta/Elev= 30
  4707.6  421.85  4730.8  421.11  4736.9  421.43  4765.5  420.68  4838.6  420.69
  4878.4  419.77  4891.4  419.62  4918.7  418.23  4927.7  418.27  4990.3  414.20
  4993.1  414.14  5003.6  412.04  5012.1  411.63  5012.4  411.13  5015.9  411.13
  5016.1  411.63  5022.1  412.55  5028.6  414.71  5034.9  415.02  5043.0  416.08
  5078.2  416.58  5085.8  415.91  5111.8  416.56  5121.6  417.77  5156.8  419.34
  5206.5  420.47  5220.9  421.19  5241.7  421.40  5299.5  423.29  5316.6  423.28
#Mann=6,-1,0
  4707.6    0.07       0  4878.4    0.12       0  4990.3   0.035       0
  5012.1   0.035       0  5016.1   0.035       0  5111.8    0.05       0
Bank Sta=5012.1,5016.1
Exp/Cntr=0.3,0.1

Type RM Length L Ch R = 1,7822,591,591,591
BEGIN DESCRIPTION:
Stream0422 13.0
END DESCRIPTION:
XS GIS Cut Line= 3
      2450675.00     13805775.00      2450144.80     13805590.52
      2449559.77     13805274.29
#Sta/Elev= 30
  4338.9  421.66  4478.8  418.18  4535.7  414.94  4629.0  413.65  4654.8  409.48
  4667.1  408.98  4685.9  410.09  4691.2  408.51  4717.0  409.40  4720.3  408.45
  4720.6  407.95  4724.3  408.45  4741.2  408.85  4748.1  410.55  4753.4  409.13
  4779.2  413.67  4825.9  414.09  4867.2  414.05  4911.4  412.68  4919.7  411.44
  4963.5  411.93  4991.1  408.92  5013.7  413.44  5067.2  417.41  5132.9  419.61
  5214.7  420.83  5252.4  420.29  5298.2  421.62  5346.0  421.15  5565.3  425.74
#Mann=4,-1,0
  4338.9    0.12       0  4720.3    0.05       0  4724.3    0.12       0
  5298.2   0.035       0
Bank Sta=4720.3,4724.3
Exp/Cntr=0.3,0.1

Type RM Length L Ch R = 1,7231,433,433,433
BEGIN DESCRIPTION:
Stream0422 12.0
END DESCRIPTION:
XS GIS Cut Line= 3
      2450675.03     13805325.02      2450525.00     13805225.00
      2450025.03     13805025.01
#Sta/Elev= 30
  4819.7  414.75  4935.4  410.06  4941.4  410.73  4956.5  409.05  4971.5  408.32
  4992.5  408.50  4997.0  406.51  5002.7  406.51  5007.4  404.09  5007.7  403.59
  5011.2  403.59  5011.4  404.09  5021.6  408.43  5039.1  409.87  5092.9  410.00
  5122.5  409.23  5140.0  409.61  5176.4  409.03  5254.5  410.01  5269.3  409.57
  5278.7  410.36  5355.4  411.16  5386.4  412.74  5398.5  411.95  5409.3  412.04
  5440.3  414.20  5469.9  414.90  5499.5  416.56  5523.7  417.44  5538.5  417.14
#Mann=3,-1,0
  4819.7    0.12       0  5007.4    0.05       0  5011.4    0.12       0
Bank Sta=5007.4,5011.4
Exp/Cntr=0.3,0.1

Type RM Length L Ch R = 1,6798,452,452,452
BEGIN DESCRIPTION:
Stream0422 11.0
END DESCRIPTION:
XS GIS Cut Line= 3
      2450824.97     13805174.97      2450525.00     13804875.00
      2450225.03     13804625.03
#Sta/Elev= 30
  4562.4  418.04  4647.2  413.69  4746.2  411.03  4816.9  407.78  4873.5  406.68
  4901.8  408.21  4915.9  407.36  4944.2  407.84  4972.5  406.64  4983.1  404.47
  4989.9  404.47  4991.8  403.27  4992.0  402.77  4995.8  403.27  5008.1  404.67
  5014.6  403.93  5022.4  405.58  5028.9  403.97  5036.7  406.09  5057.6  406.08
  5064.7  404.19  5100.5  408.11  5135.7  408.51  5164.3  410.48  5228.1  411.67
  5234.6  411.17  5242.4  412.17  5271.1  411.10  5299.0  411.62  5377.1  414.60
#Mann=3,-1,0
  4562.4    0.12       0  4991.8    0.05       0  4995.8    0.12       0
Bank Sta=4991.8,4995.8
Exp/Cntr=0.3,0.1

Type RM Length L Ch R = 1,6346,479,479,479
BEGIN DESCRIPTION:
Stream0422 10.0
END DESCRIPTION:
XS GIS Cut Line= 3
      2450925.03     13804775.03      2450625.00     13804475.00
      2450125.00     13804525.00
#Sta/Elev= 30
  4579.9  412.45  4636.5  410.47  4693.1  407.31  4735.5  406.10  4777.9  403.92
  4806.2  404.87  4905.2  406.04  4947.6  404.13  4975.9  403.61  4988.1  401.33
  4988.3  400.83  4991.8  400.83  4992.1  401.33  5000.7  405.27  5006.7  405.27
  5014.3  406.62  5051.9  408.11  5064.5  407.75  5157.5  409.34  5175.1  410.16
  5195.2  409.28  5235.4  409.30  5258.0  409.98  5265.5  410.86  5275.6  410.02
  5295.7  409.94  5376.1  412.60  5396.2  414.27  5436.4  415.05  5506.7  417.78
#Mann=3,-1,0
  4579.9    0.12       0  4988.1    0.05       0  4992.1    0.12       0
Bank Sta=4988.1,4992.1
Exp/Cntr=0.3,0.1

Type RM Length L Ch R = 1,5867,423,423,423
BEGIN DESCRIPTION:
Stream0422 9.0
END DESCRIPTION:
XS GIS Cut Line= 3
      2451422.14     13804601.81      2450975.00     13804225.00
      2450109.59     13804396.12
#Sta/Elev= 30
  4415.6  411.32  4447.0  411.37  4475.6  409.62  4560.2  407.93  4921.9  403.52
  4936.0  402.17  4972.4  403.14  4978.9  402.91  4991.2  399.32  4991.4  398.82
  4995.2  399.32  4997.1  402.77  5010.5  403.18  5020.7  402.30  5026.0  403.23
  5041.1  403.13  5071.7  401.74  5077.2  402.67  5102.3  402.80  5133.6  404.61
  5143.1  403.65  5194.0  403.51  5287.4  405.77  5377.5  409.18  5459.1  410.57
  5561.0  408.97  5612.0  409.73  5632.3  409.12  5800.0  414.31  5882.5  414.93
#Mann=3,-1,0
  4415.6    0.12       0  4991.2    0.05       0  4995.2    0.12       0
Bank Sta=4991.2,4995.2
Exp/Cntr=0.3,0.1

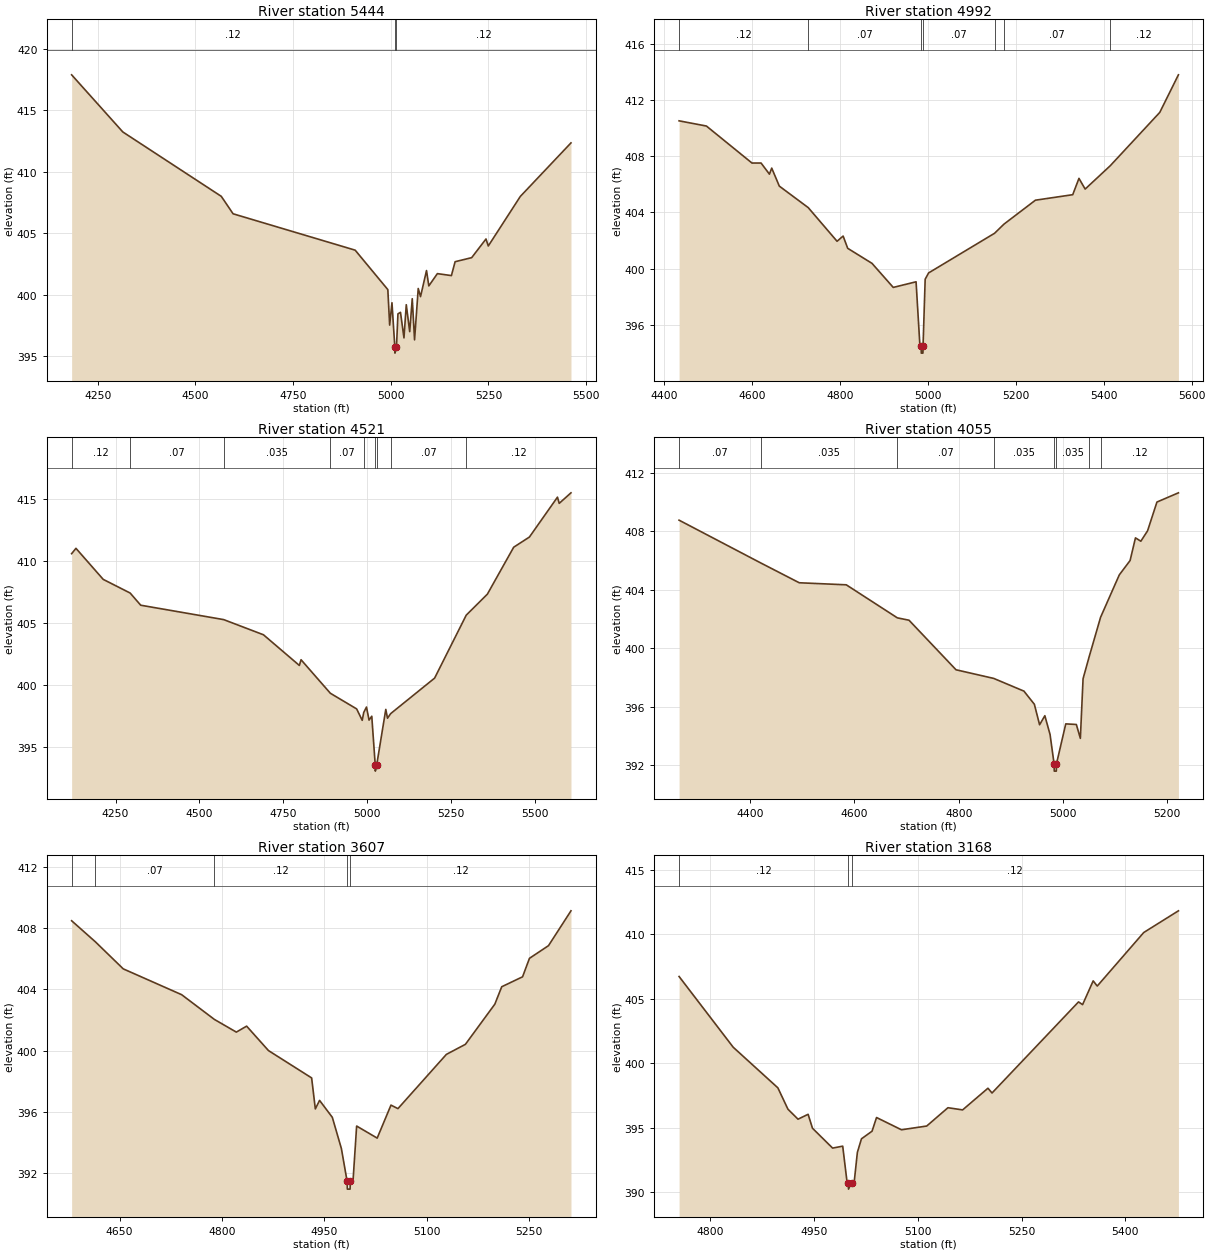
Type RM Length L Ch R = 1,5444,452,452,452
BEGIN DESCRIPTION:
Stream0422 8.0
END DESCRIPTION:
XS GIS Cut Line= 3
      2451125.00     13804875.02      2451225.00     13804075.00
      2450975.02     13803675.04
#Sta/Elev= 30
  4183.3  417.89  4314.3  413.24  4566.3  408.00  4596.5  406.58  4908.9  403.62
  4992.5  400.41  4997.2  397.52  5003.1  399.34  5010.4  395.74  5010.7  395.24
  5014.6  395.74  5018.4  398.44  5024.9  398.56  5033.8  396.48  5039.7  399.18
  5048.5  396.99  5055.0  399.67  5060.9  396.32  5070.3  400.50  5076.2  399.84
  5091.5  401.96  5097.4  400.71  5119.3  401.71  5155.2  401.55  5164.7  402.68
  5207.1  403.01  5243.7  404.53  5249.6  403.96  5331.5  407.99  5461.2  412.35
#Mann=3,-1,0
  4183.3    0.12       0  5010.4    0.05       0  5014.6    0.12       0
Bank Sta=5010.4,5014.6
Exp/Cntr=0.3,0.1

Type RM Length L Ch R = 1,4992,471,471,471
BEGIN DESCRIPTION:
Stream0422 7.0
END DESCRIPTION:
XS GIS Cut Line= 3
      2451425.01     13804524.96      2451575.00     13803975.00
      2451175.02     13803575.02
#Sta/Elev= 30
  4434.3  410.51  4496.5  410.14  4600.1  407.51  4620.8  407.51  4639.8  406.72
  4645.0  407.15  4662.3  405.87  4728.1  404.34  4793.6  401.95  4807.4  402.32
  4817.8  401.45  4873.1  400.38  4921.4  398.67  4973.3  399.07  4981.9  394.61
  4984.9  394.50  4985.2  394.00  4988.9  394.00  4989.2  394.50  4994.0  399.25
  5001.8  399.70  5151.9  402.52  5173.3  403.17  5244.8  404.87  5329.6  405.26
  5343.8  406.42  5357.9  405.66  5415.0  407.32  5527.6  411.11  5570.0  413.78
#Mann=7,-1,0
  4434.3    0.12       0  4728.1    0.07       0  4984.9    0.05       0
  4989.2    0.07       0  5151.9    0.12       0  5173.3    0.07       0
  5415.0    0.12       0
Bank Sta=4984.9,4989.2
Exp/Cntr=0.3,0.1

Type RM Length L Ch R = 1,4521,466,466,466
BEGIN DESCRIPTION:
Stream0422 6.0
END DESCRIPTION:
XS GIS Cut Line= 3
      2451769.24     13804787.68      2451925.00     13803925.00
      2451780.76     13803329.86
#Sta/Elev= 30
  4119.1  410.59  4132.0  411.02  4213.3  408.52  4293.6  407.42  4325.1  406.44
  4572.6  405.28  4691.1  404.06  4798.2  401.59  4803.2  402.05  4890.6  399.35
  4969.0  398.09  4985.6  397.17  4990.1  397.80  4998.3  398.24  5006.0  397.19
  5014.1  397.50  5024.4  393.58  5024.7  393.08  5028.8  393.58  5055.9  398.05
  5061.0  397.34  5070.4  397.71  5201.5  400.57  5295.8  405.64  5358.8  407.33
  5437.3  411.11  5484.2  411.93  5567.8  415.14  5573.0  414.64  5608.1  415.49
#Mann=9,-1,0
  4119.1    0.12       0  4293.6    0.07       0  4572.6   0.035       0
  4890.6    0.07       0  4990.1   0.035       0  5024.4   0.035       0
  5028.8   0.035       0  5070.4    0.07       0  5295.8    0.12       0
Bank Sta=5024.4,5028.8
Exp/Cntr=0.3,0.1

Type RM Length L Ch R = 1,4055,448,448,448
BEGIN DESCRIPTION:
Stream0422 5.0
END DESCRIPTION:
XS GIS Cut Line= 3
      2452225.00     13804725.01      2452275.00     13803975.00
      2452324.99     13803775.03
#Sta/Elev= 30
  4263.6  408.75  4420.0  405.83  4494.1  404.47  4584.3  404.33  4682.3  402.07
  4704.6  401.91  4794.8  398.52  4867.1  397.93  4925.1  397.06  4945.1  396.16
  4955.1  394.76  4965.2  395.38  4975.2  394.09  4982.9  392.09  4983.3  391.59
  4987.2  391.59  4987.5  392.09  5005.3  394.82  5025.6  394.78  5033.3  393.83
  5038.5  397.91  5050.5  399.45  5072.1  402.11  5108.0  405.01  5128.7  405.99
  5139.0  407.54  5149.3  407.31  5162.2  408.02  5180.2  409.99  5221.4  410.62
#Mann=8,-1,0
  4263.6    0.07       0  4420.0   0.035       0  4682.3    0.07       0
  4867.1   0.035       0  4982.9   0.035       0  4987.5   0.035       0
  5050.5    0.07       0  5072.1    0.12       0
Bank Sta=4982.9,4987.5
Exp/Cntr=0.3,0.1

Type RM Length L Ch R = 1,3607,439,439,439
BEGIN DESCRIPTION:
Stream0422 4.0
END DESCRIPTION:
XS GIS Cut Line= 3
      2452724.99     13804474.98      2452575.00     13804075.00
      2452525.00     13803775.02
#Sta/Elev= 30
  4579.8  408.50  4614.6  407.12  4655.4  405.35  4740.9  403.66  4788.9  402.04
  4821.0  401.21  4836.1  401.60  4868.1  400.00  4931.3  398.21  4936.7  396.18
  4942.9  396.74  4961.6  395.63  4974.9  393.58  4983.3  391.43  4983.6  390.93
  4987.6  390.93  4987.9  391.43  4991.9  391.46  4997.2  395.06  5027.3  394.27
  5047.5  396.43  5057.7  396.20  5128.6  399.75  5156.5  400.41  5199.6  403.04
  5209.7  404.18  5240.2  404.83  5250.3  406.04  5278.2  406.87  5311.1  409.15
#Mann=5,-1,0
  4579.8    0.12       0  4614.6    0.07       0  4788.9    0.12       0
  4983.3    0.05       0  4987.9    0.12       0
Bank Sta=4983.3,4987.9
Exp/Cntr=0.3,0.1

Type RM Length L Ch R = 1,3168,552,552,552
BEGIN DESCRIPTION:
Stream0422 3.0
END DESCRIPTION:
XS GIS Cut Line= 3
      2453075.03     13804125.03      2452925.00     13803925.00
      2452525.03     13803675.02
#Sta/Elev= 30
  4755.0  406.72  4833.2  401.24  4897.8  398.09  4912.3  396.44  4926.9  395.66
  4941.5  396.04  4947.8  394.96  4976.9  393.42  4991.5  393.57  4997.8  390.77
  4999.6  390.74  4999.9  390.24  5004.3  390.74  5008.0  390.74  5012.7  393.09
  5018.6  394.14  5033.9  394.73  5040.4  395.79  5076.4  394.84  5112.9  395.13
  5143.6  396.55  5164.8  396.38  5201.4  398.06  5207.3  397.69  5332.3  404.75
  5338.2  404.54  5353.5  406.38  5359.4  405.98  5426.6  410.13  5476.7  411.81
#Mann=3,-1,0
  4755.0    0.12       0  4999.6    0.05       0  5004.3    0.12       0
Bank Sta=4999.6,5004.3
Exp/Cntr=0.3,0.1

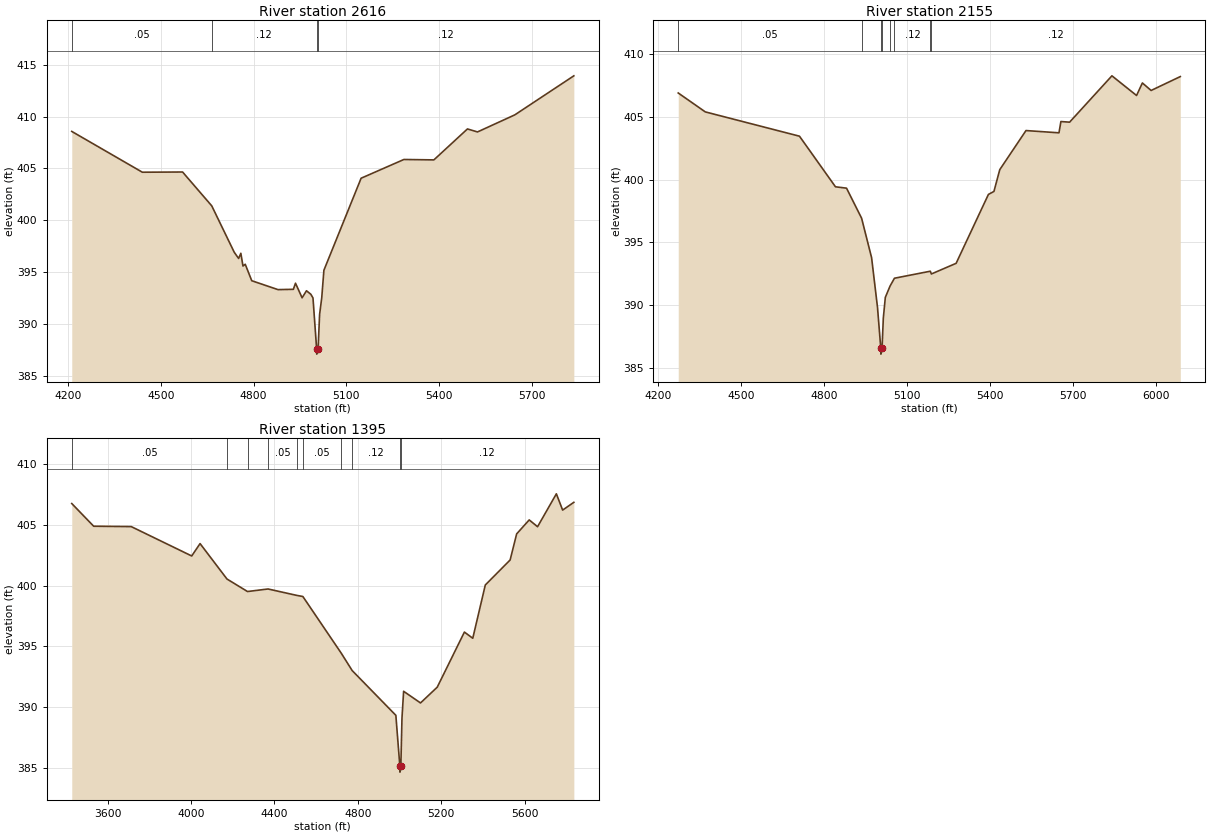
Type RM Length L Ch R = 1,2616,461,461,461
BEGIN DESCRIPTION:
E21025
END DESCRIPTION:
XS GIS Cut Line= 4
      2453319.11     13804116.08      2453221.53     13803679.83
      2452831.19     13803306.71      2452222.70     13803117.28
#Sta/Elev= 30
  4211.9  408.58  4440.2  404.64  4570.4  404.66  4664.8  401.39  4737.5  396.91
  4751.7  396.31  4758.9  396.81  4765.8  395.58  4773.1  395.75  4794.2  394.16
  4879.1  393.30  4928.8  393.33  4935.7  393.92  4957.1  392.51  4971.2  393.19
  4985.4  392.85  4992.3  392.49  5004.1  387.57  5004.4  387.07  5008.8  387.57
  5013.7  390.91  5020.6  392.51  5027.6  395.17  5148.0  404.06  5286.4  405.87
  5383.4  405.83  5492.0  408.82  5524.5  408.53  5645.3  410.18  5836.2  413.95
#Mann=4,-1,0
  4211.9    0.05       0  4664.8    0.12       0  5004.1    0.05       0
  5008.8    0.12       0
Bank Sta=5004.1,5008.8
Exp/Cntr=0.3,0.1

Type RM Length L Ch R = 1,2155,760,760,760
BEGIN DESCRIPTION:
E21024
END DESCRIPTION:
XS GIS Cut Line= 4
      2453422.44     13804012.75      2453393.74     13803358.37
      2453198.57     13803168.94      2452354.71     13802893.40
#Sta/Elev= 30
  4273.3  406.92  4371.1  405.41  4711.5  403.47  4841.6  399.43  4881.6  399.32
  4936.1  396.92  4972.2  393.77  4993.5  389.81  5005.3  386.57  5005.7  386.07
  5010.0  386.57  5014.6  388.95  5021.8  390.60  5038.8  391.50  5054.8  392.13
  5184.4  392.69  5188.3  392.47  5277.7  393.32  5394.4  398.82  5414.4  399.06
  5435.5  400.80  5530.2  403.92  5649.5  403.74  5656.4  404.64  5687.9  404.59
  5840.8  408.29  5929.9  406.72  5950.9  407.72  5982.5  407.12  6088.0  408.23
#Mann=8,-1,0
  4273.3    0.05       0  4936.1    0.12       0  5005.3    0.05       0
  5010.0    0.12       0  5038.8    0.07       0  5054.8    0.12       0
  5184.4    0.07       0  5188.3    0.12       0
Bank Sta=5005.3,5010
Exp/Cntr=0.3,0.1

Type RM Length L Ch R = 1,1395,0,0,0
BEGIN DESCRIPTION:
E21023
END DESCRIPTION:
XS GIS Cut Line= 4
      2453462.62     13804029.97      2453479.84     13802927.85
      2453009.14     13802652.32      2452251.40     13802698.24
#Sta/Elev= 30
  3428.5  406.76  3533.5  404.89  3713.5  404.86  4003.5  402.44  4043.5  403.46
  4172.6  400.54  4271.0  399.51  4369.4  399.72  4507.7  399.19  4536.3  399.10
  4721.1  394.41  4772.6  393.00  4982.1  389.31  5001.2  385.13  5001.6  384.63
  5006.0  385.13  5011.4  389.08  5019.3  391.29  5100.3  390.33  5180.5  391.63
  5310.7  396.17  5350.8  395.66  5410.9  400.05  5529.9  402.11  5561.2  404.26
  5621.3  405.41  5661.4  404.85  5751.5  407.56  5781.6  406.22  5835.3  406.86
#Mann=10,-1,0
  3428.5    0.05       0  4172.6    0.12       0  4271.0    0.07       0
  4369.4    0.05       0  4507.7    0.07       0  4536.3    0.05       0
  4721.1    0.07       0  4772.6    0.12       0  5001.2    0.05       0
  5006.0    0.12       0
Bank Sta=5001.2,5006
Exp/Cntr=0.3,0.1

Chan Stop Cuts=-1