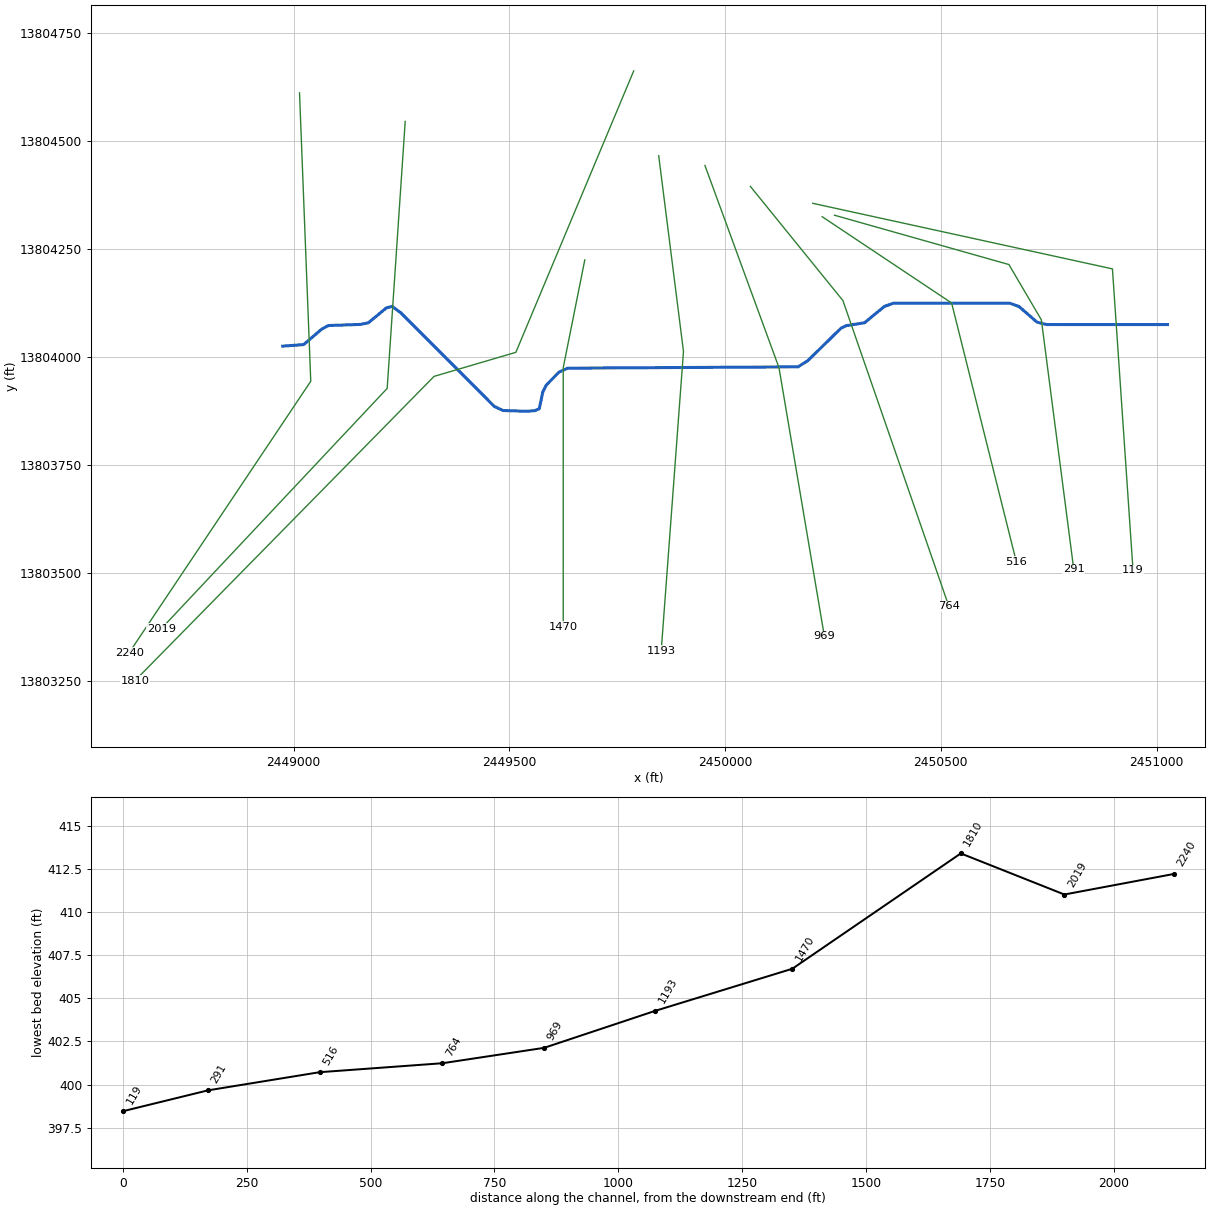
--- Stream0423.prj (project) ---

Proj Title=Stream0423 Base Level Engineering
Current Plan=p01
Default Exp/Contr=0.3,0.1
English Units
Geom File=g01
Flow File=f01
Plan File=p01
BEGIN DESCRIPTION:
Stream0423
END DESCRIPTION:

--- Stream0423.p01 (plan) ---

Plan Title=Multiple Run
Short Identifier=Multiple
Geom File=g01
Flow File=f01
Subcritical Flow
K Sum by GR= 0
Std Step Tol= 0.01
Critical Tol= 0.01
Num of Std Step Trials= 20
Max Error Tol= 0.3
Flow Tol Ratio= 0.001
Split Flow NTrial= 30
Split Flow Tol= 0.02
Split Flow Ratio= 0.02
Log Output Level= 0
Friction Slope Method= 1
Unsteady Friction Slope Method= 2
Unsteady Bridges Friction Slope Method= 1
Parabolic Critical Depth
Global Vel Dist=  1 , 1 , 1
Global Log Level= 0
CheckData=True
Encroach Param= -1, 0, 0, 0
BEGIN DESCRIPTION:
Multiple Run
END DESCRIPTION:

--- Stream0423.f01 (steady flow) ---

Flow Title=Multiple
Number of Profiles=7
Profile Names=10-year,25-year,50-year,1pct_min,100-year,1pct_plu,500-year
River Rch & RM= Stream0423,Reach-1,2240
     373     578     757     482     961    1918    1529
River Rch & RM= Stream0423,Reach-1,119
     814    1318    1775    1156    2307    4604    3861
Boundary for River Rch & Prof#=Stream0423,Reach-1,1
Up Type=0
Dn Type=3
Dn Slope=0.005
Boundary for River Rch & Prof#=Stream0423,Reach-1,2
Up Type=0
Dn Type=3
Dn Slope=0.005
Boundary for River Rch & Prof#=Stream0423,Reach-1,3
Up Type=0
Dn Type=3
Dn Slope=0.005
Boundary for River Rch & Prof#=Stream0423,Reach-1,4
Up Type=0
Dn Type=3
Dn Slope=0.005
Boundary for River Rch & Prof#=Stream0423,Reach-1,5
Up Type=0
Dn Type=3
Dn Slope=0.005
Boundary for River Rch & Prof#=Stream0423,Reach-1,6
Up Type=0
Dn Type=3
Dn Slope=0.005
Boundary for River Rch & Prof#=Stream0423,Reach-1,7
Up Type=0
Dn Type=3
Dn Slope=0.005

--- Stream0423.g01 (geometry) ---

Geom Title=Existing Conditions

River Reach=Stream0423,Reach-1
Reach XY= 30
      2448975.00     13804025.00      2449023.49     13804028.64
      2449065.26     13804064.39      2449080.92     13804072.78
      2449154.95     13804075.35      2449173.51     13804079.10
      2449215.15     13804113.68      2449228.42     13804117.21
      2449248.36     13804102.55      2449465.25     13803885.42
      2449485.59     13803875.89      2449540.42     13803874.08
      2449559.10     13803875.53      2449569.51     13803880.14
      2449577.64     13803918.67      2449585.75     13803934.75
      2449614.90     13803964.60      2449635.29     13803973.99
      2450169.14     13803977.06      2450191.75     13803991.46
      2450268.95     13804066.84      2450281.04     13804072.50
      2450323.25     13804079.22      2450368.92     13804116.91
      2450390.21     13804124.49      2450659.78     13804124.48
      2450681.06     13804116.86      2450722.67     13804080.75
      2450745.03     13804075.07      2451025.00     13804075.00

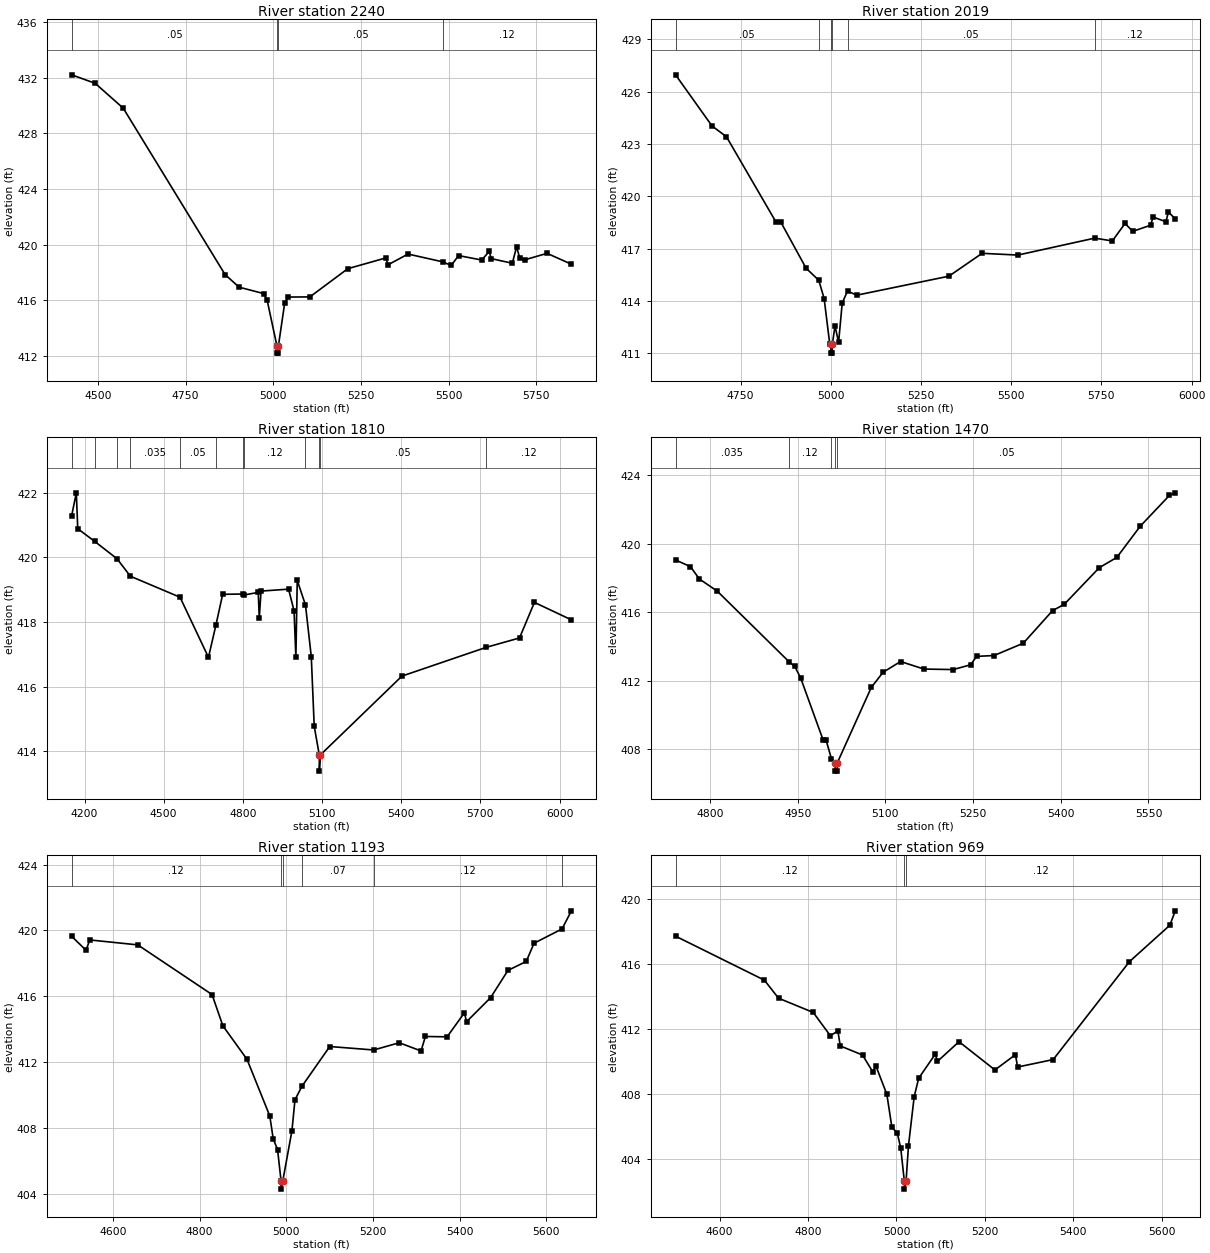
Type RM Length L Ch R = 1,2240,221,221,221
BEGIN DESCRIPTION:
XS6767
END DESCRIPTION:
XS GIS Cut Line= 3
      2449013.93     13804612.04      2449039.97     13803943.66
      2448619.50     13803315.12
#Sta/Elev= 30
  4425.1  432.20  4492.2  431.59  4572.3  429.80  4862.5  417.85  4902.5  416.94
  4972.6  416.48  4982.6  416.00  5010.6  412.70  5010.8  412.20  5014.3  412.20
  5014.6  412.70  5032.6  415.80  5042.6  416.23  5104.4  416.24  5212.7  418.27
  5321.0  419.04  5327.4  418.55  5384.4  419.32  5483.2  418.76  5507.5  418.50
  5528.5  419.21  5594.6  418.89  5615.6  419.51  5621.8  418.99  5681.7  418.66
  5693.9  419.84  5702.7  419.05  5717.7  418.91  5780.8  419.37  5850.2  418.59
#Mann=4,-1,0
  4425.1    0.05       0  5010.6    0.05       0  5014.6    0.05       0
  5483.2    0.12       0
Bank Sta=5010.6,5014.6
Exp/Cntr=0.3,0.1

Type RM Length L Ch R = 1,2019,209,209,209
BEGIN DESCRIPTION:
E21027
END DESCRIPTION:
XS GIS Cut Line= 3
      2449258.86     13804545.75      2449217.06     13803927.11
      2448693.28     13803369.89
#Sta/Elev= 30
  4569.9  426.96  4670.9  424.03  4711.0  423.41  4848.0  418.53  4861.3  418.53
  4931.5  415.88  4966.9  415.18  4981.6  414.14  4997.3  411.51  5000.3  411.51
  5000.6  411.01  5004.1  411.01  5004.3  411.51  5011.7  412.57  5021.7  411.63
  5031.7  413.88  5046.4  414.57  5071.8  414.33  5327.4  415.42  5419.3  416.73
  5518.4  416.63  5731.3  417.60  5780.2  417.44  5815.4  418.44  5836.9  417.99
  5886.2  418.34  5893.1  418.81  5928.7  418.54  5935.6  419.10  5954.7  418.70
#Mann=6,-1,0
  4569.9    0.05       0  4966.9    0.12       0  5000.3    0.05       0
  5004.3    0.12       0  5046.4    0.05       0  5731.3    0.12       0
Bank Sta=5000.3,5004.3
Exp/Cntr=0.3,0.1

Type RM Length L Ch R = 1,1810,340,340,340
BEGIN DESCRIPTION:
Stream0423 4.0
END DESCRIPTION:
XS GIS Cut Line= 4
      2449788.32     13804662.79      2449515.22     13804010.70
      2449325.74     13803954.97      2448632.34     13803249.58
#Sta/Elev= 30
  4151.3  421.29  4169.0  422.00  4174.4  420.89  4238.2  420.50  4323.3  419.96
  4373.8  419.42  4562.0  418.77  4669.7  416.91  4697.7  417.90  4723.5  418.86
  4800.7  418.87  4805.7  418.84  4858.3  418.92  4862.2  418.13  4868.9  418.96
  4973.2  419.02  4994.0  418.35  5000.9  416.91  5006.1  419.29  5037.3  418.53
  5059.3  416.93  5070.4  414.78  5089.6  413.89  5089.9  413.39  5093.6  413.89
  5402.8  416.33  5722.2  417.22  5848.3  417.51  5904.8  418.61  6044.9  418.07
#Mann=12,-1,0
  4151.3    0.05       0  4238.2    0.12       0  4323.3    0.05       0
  4373.8   0.035       0  4562.0    0.05       0  4697.7    0.12       0
  4800.7    0.05       0  4805.7    0.12       0  5037.3    0.05       0
  5089.6    0.05       0  5093.6    0.05       0  5722.2    0.12       0
Bank Sta=5089.6,5093.6
Exp/Cntr=0.3,0.1

Type RM Length L Ch R = 1,1470,277,277,277
BEGIN DESCRIPTION:
Stream0423 3.0
END DESCRIPTION:
XS GIS Cut Line= 3
      2449674.99     13804224.96      2449625.00     13803975.00
      2449625.00     13803375.01
#Sta/Elev= 30
  4741.0  419.04  4766.5  418.65  4781.7  417.93  4812.3  417.22  4935.6  413.08
  4944.9  412.83  4955.1  412.14  4993.4  408.53  4998.4  408.53  5007.6  407.44
  5013.9  407.21  5014.2  406.71  5017.7  406.71  5017.9  407.21  5075.9  411.60
  5095.9  412.48  5125.9  413.11  5165.9  412.67  5215.9  412.64  5245.9  412.92
  5255.9  413.41  5285.9  413.46  5335.9  414.18  5385.9  416.08  5405.9  416.45
  5465.9  418.59  5495.9  419.19  5535.9  421.01  5585.9  422.81  5595.9  422.96
#Mann=5,-1,0
  4741.0   0.035       0  4935.6    0.12       0  5007.6    0.05       0
  5013.9    0.05       0  5017.9    0.05       0
Bank Sta=5013.9,5017.9
Exp/Cntr=0.3,0.1

Type RM Length L Ch R = 1,1193,224,224,224
BEGIN DESCRIPTION:
E21026
END DESCRIPTION:
XS GIS Cut Line= 3
      2449846.23     13804466.28      2449903.64     13804012.77
      2449852.05     13803319.12
#Sta/Elev= 30
  4505.0  419.64  4538.3  418.79  4546.6  419.42  4657.5  419.12  4828.8  416.10
  4853.8  414.20  4909.5  412.16  4962.1  408.71  4969.9  407.33  4980.0  406.67
  4988.0  404.77  4988.2  404.27  4992.0  404.77  5013.1  407.82  5020.1  409.70
  5036.1  410.52  5100.3  412.94  5201.6  412.73  5260.7  413.17  5310.9  412.67
  5320.9  413.55  5371.0  413.53  5410.9  414.99  5415.9  414.45  5471.3  415.91
  5511.4  417.57  5553.5  418.11  5571.6  419.22  5636.1  420.09  5657.7  421.19
#Mann=6,-1,0
  4505.0    0.12       0  4988.0    0.05       0  4992.0    0.12       0
  5036.1    0.07       0  5201.6    0.12       0  5636.1    0.05       0
Bank Sta=4988,4992
Exp/Cntr=0.3,0.1

Type RM Length L Ch R = 1,969,205,205,205
BEGIN DESCRIPTION:
Stream0423 2.0
END DESCRIPTION:
XS GIS Cut Line= 3
      2449953.40     13804443.63      2450125.00     13803975.00
      2450230.12     13803352.78
#Sta/Elev= 30
  4500.5  417.71  4701.4  415.00  4733.3  413.89  4811.9  413.01  4850.5  411.58
  4867.6  411.87  4872.9  410.95  4923.3  410.39  4946.3  409.36  4953.8  409.70
  4978.3  407.97  4989.6  405.96  5002.1  405.56  5009.7  404.66  5017.8  402.63
  5018.1  402.13  5021.8  402.63  5027.2  404.80  5040.1  407.82  5050.3  408.96
  5087.7  410.44  5092.8  410.00  5141.5  411.21  5222.7  409.47  5269.0  410.41
  5274.1  409.65  5354.5  410.11  5526.9  416.14  5618.2  418.38  5630.6  419.27
#Mann=3,-1,0
  4500.5    0.12       0  5017.8    0.05       0  5021.8    0.12       0
Bank Sta=5017.8,5021.8
Exp/Cntr=0.3,0.1

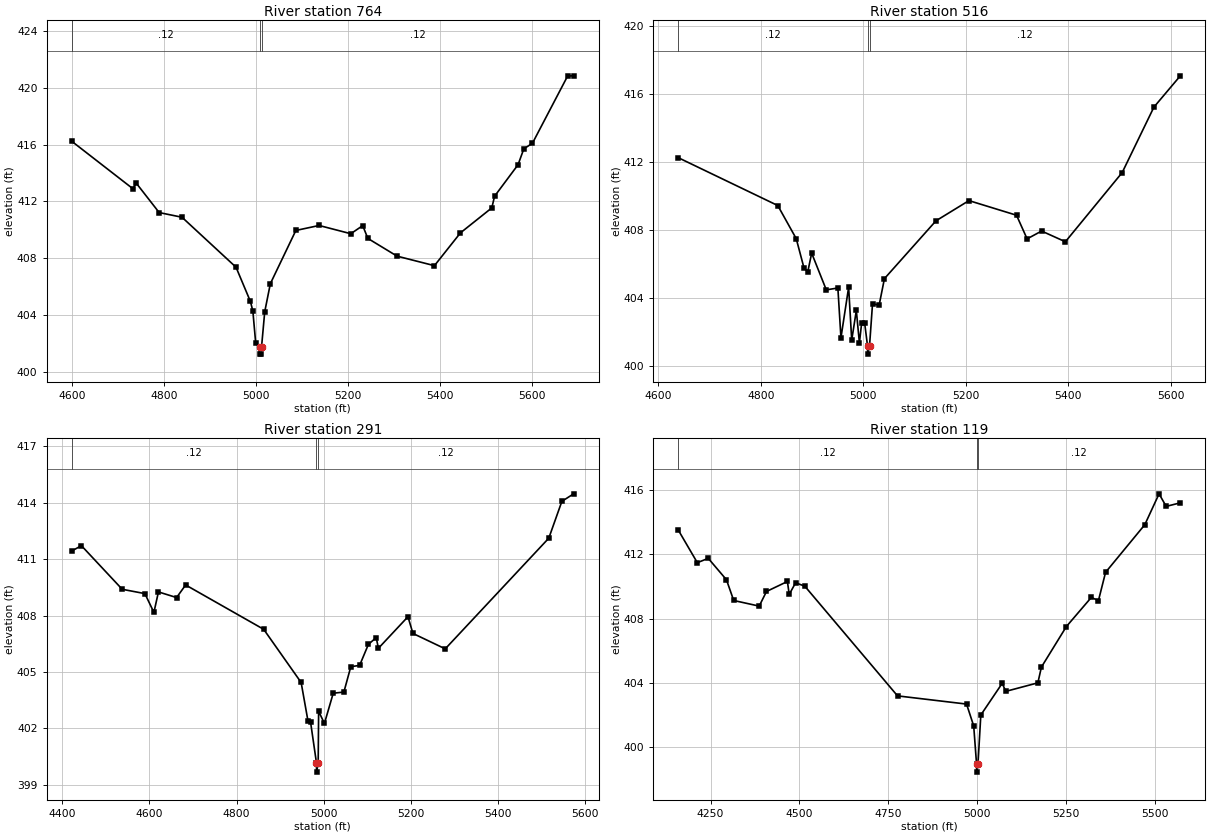
Type RM Length L Ch R = 1,764,248,248,248
BEGIN DESCRIPTION:
E21028
END DESCRIPTION:
XS GIS Cut Line= 3
      2450058.62     13804395.22      2450273.16     13804130.53
      2450518.39     13803422.72
#Sta/Elev= 30
  4599.9  416.23  4732.2  412.90  4740.2  413.27  4789.7  411.21  4839.3  410.88
  4956.6  407.36  4987.8  404.95  4993.1  404.28  4999.4  401.99  5008.0  401.74
  5008.2  401.24  5011.7  401.24  5012.0  401.74  5018.9  404.22  5031.1  406.20
  5086.5  409.95  5137.0  410.30  5205.8  409.72  5231.7  410.29  5242.8  409.39
  5306.3  408.14  5387.4  407.47  5443.9  409.78  5512.0  411.54  5518.0  412.36
  5569.0  414.58  5581.5  415.70  5600.2  416.09  5676.7  420.83  5689.7  420.84
#Mann=3,-1,0
  4599.9    0.12       0  5008.0    0.05       0  5012.0    0.12       0
Bank Sta=5008,5012
Exp/Cntr=0.3,0.1

Type RM Length L Ch R = 1,516,225,225,225
BEGIN DESCRIPTION:
Stream0423 1.0
END DESCRIPTION:
XS GIS Cut Line= 3
      2450225.02     13804324.99      2450525.00     13804125.00
      2450675.00     13803524.99
#Sta/Elev= 30
  4639.5  412.27  4833.3  409.46  4869.3  407.51  4884.4  405.79  4891.9  405.58
  4899.4  406.66  4927.9  404.50  4950.5  404.61  4956.5  401.68  4971.5  404.65
  4977.5  401.54  4986.5  403.29  4992.5  401.38  4997.0  402.58  5002.6  402.58
  5008.3  401.22  5008.6  400.72  5012.3  401.22  5018.1  403.68  5031.0  403.60
  5041.3  405.16  5141.8  408.56  5206.2  409.75  5299.0  408.89  5319.6  407.50
  5347.9  407.96  5394.3  407.33  5505.1  411.40  5567.0  415.25  5618.5  417.09
#Mann=3,-1,0
  4639.5    0.12       0  5008.3    0.05       0  5012.3    0.12       0
Bank Sta=5008.3,5012.3
Exp/Cntr=0.3,0.1

Type RM Length L Ch R = 1,291,172,172,172
BEGIN DESCRIPTION:
E21029
END DESCRIPTION:
XS GIS Cut Line= 4
      2450253.67     13804328.37      2450657.71     13804214.12
      2450732.94     13804085.94      2450807.94     13803508.19
#Sta/Elev= 30
  4422.0  411.44  4444.2  411.72  4537.7  409.40  4589.7  409.17  4610.4  408.17
  4620.8  409.26  4662.4  408.96  4683.2  409.63  4862.2  407.27  4948.1  404.44
  4963.8  402.39  4969.6  402.35  4983.2  400.17  4983.5  399.67  4987.2  400.17
  4988.2  402.91  5001.5  402.26  5021.7  403.87  5046.1  403.93  5062.0  405.28
  5082.2  405.35  5102.4  406.47  5120.3  406.83  5125.3  406.26  5193.1  407.94
  5204.5  407.05  5278.6  406.23  5516.1  412.12  5546.1  414.08  5573.1  414.48
#Mann=3,-1,0
  4422.0    0.12       0  4983.2    0.05       0  4987.2    0.12       0
Bank Sta=4983.2,4987.2
Exp/Cntr=0.3,0.1

Type RM Length L Ch R = 1,119,0,0,0
BEGIN DESCRIPTION:
XS6768
END DESCRIPTION:
XS GIS Cut Line= 3
      2450203.14     13804356.00      2450897.61     13804204.08
      2450945.36     13803505.30
#Sta/Elev= 30
  4159.7  413.49  4212.8  411.48  4243.5  411.75  4294.7  410.42  4315.1  409.13
  4386.8  408.78  4407.3  409.69  4466.1  410.31  4471.2  409.51  4489.2  410.23
  4515.0  410.02  4775.8  403.20  4969.9  402.69  4990.0  401.33  4998.0  398.96
  4998.2  398.46  5002.0  398.96  5010.0  402.01  5070.1  403.98  5080.2  403.48
  5170.4  404.01  5180.4  404.99  5250.6  407.51  5320.7  409.32  5340.7  409.12
  5360.8  410.88  5471.1  413.84  5511.2  415.76  5531.2  414.98  5571.0  415.20
#Mann=3,-1,0
  4159.7    0.12       0  4998.0    0.05       0  5002.0    0.12       0
Bank Sta=4998,5002
Exp/Cntr=0.3,0.1

Chan Stop Cuts=-1