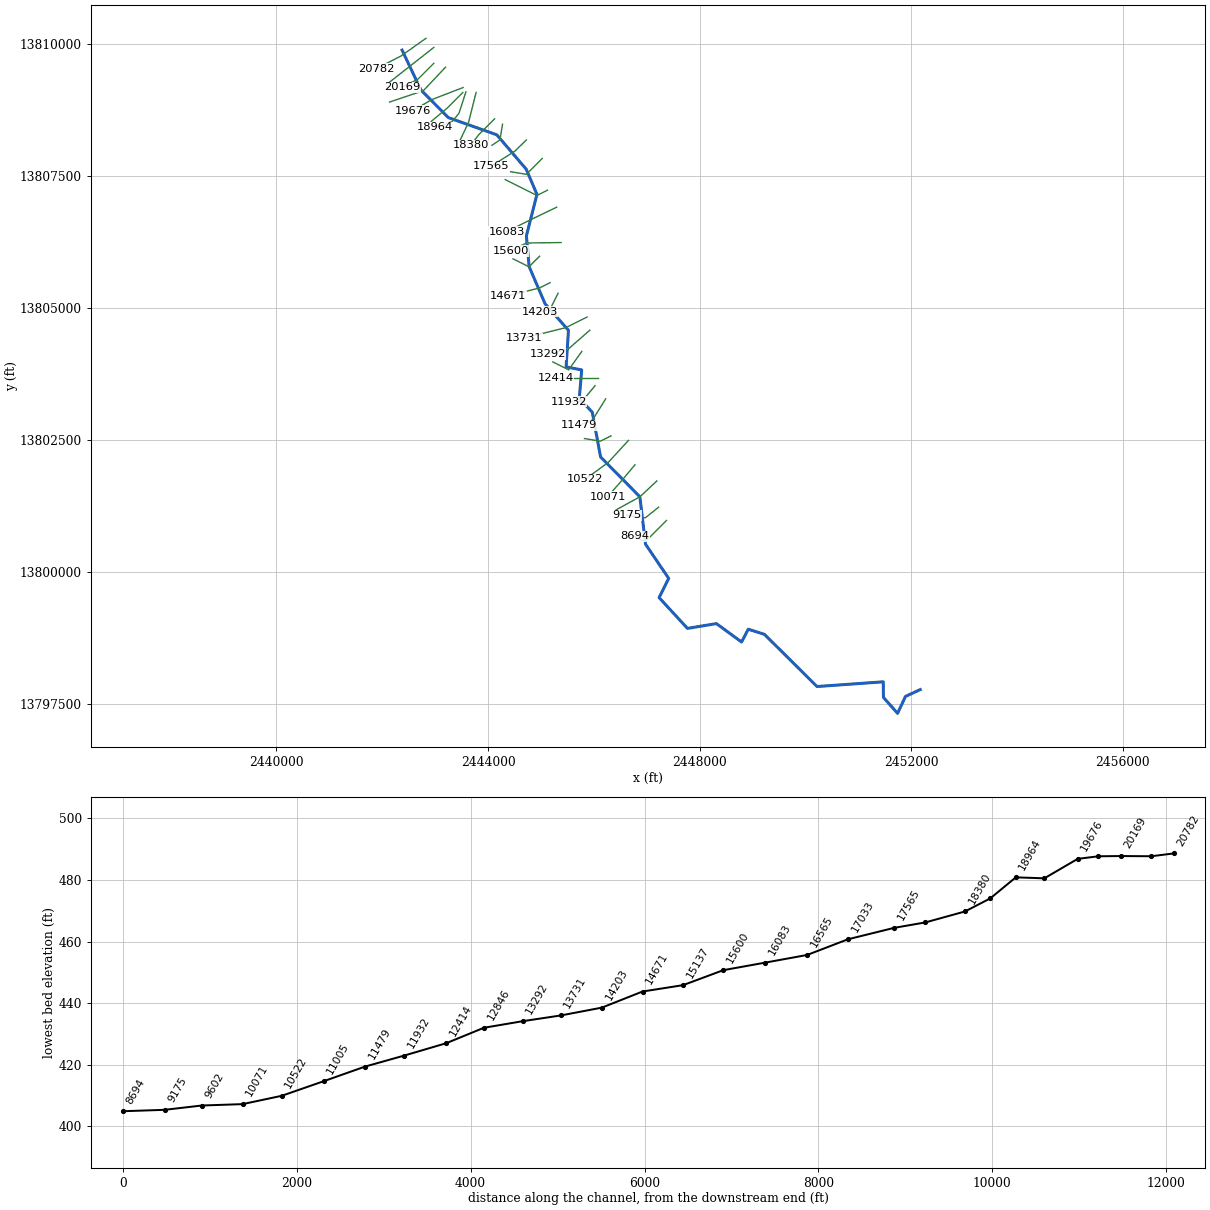
--- Stream0424.prj (project) ---

Proj Title=Stream0424 Base Level Engineering
Current Plan=p01
Default Exp/Contr=0.3,0.1
English Units
Geom File=g01
Flow File=f01
Plan File=p01
BEGIN DESCRIPTION:
Stream0424
END DESCRIPTION:

--- Stream0424.p01 (plan) ---

Plan Title=Multiple Run
Short Identifier=Multiple
Geom File=g01
Flow File=f01
Subcritical Flow
K Sum by GR= 0
Std Step Tol= 0.01
Critical Tol= 0.01
Num of Std Step Trials= 20
Max Error Tol= 0.3
Flow Tol Ratio= 0.001
Split Flow NTrial= 30
Split Flow Tol= 0.02
Split Flow Ratio= 0.02
Log Output Level= 0
Friction Slope Method= 1
Unsteady Friction Slope Method= 2
Unsteady Bridges Friction Slope Method= 1
Parabolic Critical Depth
Global Vel Dist=  1 , 1 , 1
Global Log Level= 0
CheckData=True
Encroach Param= -1, 0, 0, 0
BEGIN DESCRIPTION:
Multiple Run
END DESCRIPTION:

--- Stream0424.f01 (steady flow) ---

Flow Title=Multiple
Number of Profiles=7
Profile Names=10-year,25-year,50-year,1pct_min,100-year,1pct_plu,500-year
River Rch & RM= Stream0424,Reach-1,20782
     523     828    1099     707    1411    2816    2300
River Rch & RM= Stream0424,Reach-1,16565
     736    1192    1605    1047    2089    4168    3504
River Rch & RM= Stream0424,Reach-1,13731
    1183    1967    2696    1787    3565    7114    6177
River Rch & RM= Stream0424,Reach-1,4144
    1396    2336    3216    2139    4268    8516    7448
Boundary for River Rch & Prof#=Stream0424,Reach-1,1
Up Type=0
Dn Type=3
Dn Slope=0.005
Boundary for River Rch & Prof#=Stream0424,Reach-1,2
Up Type=0
Dn Type=3
Dn Slope=0.005
Boundary for River Rch & Prof#=Stream0424,Reach-1,3
Up Type=0
Dn Type=3
Dn Slope=0.005
Boundary for River Rch & Prof#=Stream0424,Reach-1,4
Up Type=0
Dn Type=3
Dn Slope=0.005
Boundary for River Rch & Prof#=Stream0424,Reach-1,5
Up Type=0
Dn Type=3
Dn Slope=0.005
Boundary for River Rch & Prof#=Stream0424,Reach-1,6
Up Type=0
Dn Type=3
Dn Slope=0.005
Boundary for River Rch & Prof#=Stream0424,Reach-1,7
Up Type=0
Dn Type=3
Dn Slope=0.005

--- Stream0424.g01 (geometry) ---

Geom Title=Existing Conditions

River Reach=Stream0424,Reach-1
Reach XY= 30
      2442375.00     13809875.00      2442732.82     13809118.81
      2443250.59     13808597.99      2444166.69     13808271.91
      2444721.24     13807623.44      2444925.60     13807145.05
      2444725.51     13806359.78      2444777.26     13805780.94
      2445080.54     13805072.58      2445521.39     13804573.50
      2445476.97     13803880.63      2445771.56     13803823.78
      2445726.08     13803285.54      2445971.47     13803023.55
      2446128.53     13802176.45      2446871.39     13801423.52
      2446978.54     13800526.46      2447417.21     13799878.03
      2447235.48     13799515.20      2447771.84     13798932.54
      2448319.15     13799023.46      2448795.11     13798674.89
      2448921.26     13798917.31      2449227.71     13798819.60
      2450221.57     13797832.79      2451473.78     13797921.57
      2451478.47     13797626.50      2451745.16     13797324.52
      2451894.41     13797645.13      2452175.00     13797775.00

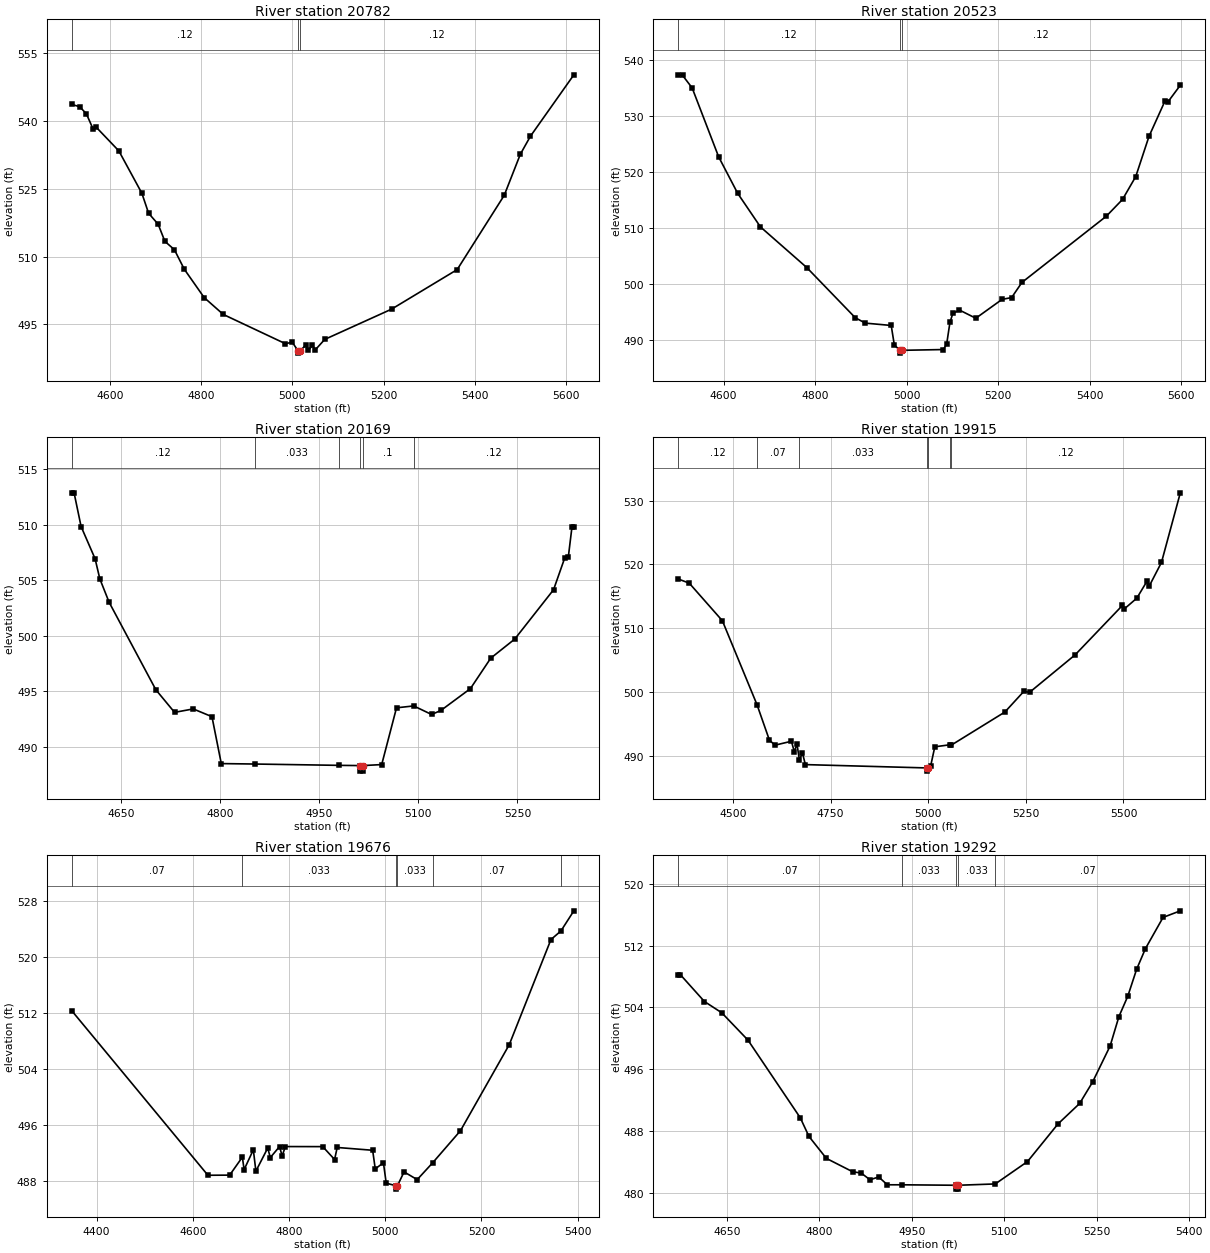
Type RM Length L Ch R = 1,20782,259,259,259
BEGIN DESCRIPTION:
Stream0424 41.0
END DESCRIPTION:
XS GIS Cut Line= 3
      2442826.48     13810098.14      2442352.16     13809762.91
      2441889.25     13809524.33
#Sta/Elev= 30
  4516.0  543.65  4533.1  543.17  4547.9  541.62  4562.7  538.24  4568.8  538.71
  4619.3  533.38  4669.8  524.01  4684.6  519.58  4705.5  517.16  4720.3  513.37
  4741.2  511.52  4762.7  507.23  4806.5  500.93  4848.4  497.20  4984.9  490.72
  4999.7  491.07  5012.5  489.14  5012.7  488.64  5016.5  489.14  5029.3  490.37
  5035.4  489.28  5044.1  490.37  5050.2  489.35  5071.1  491.68  5217.7  498.37
  5361.6  507.12  5464.9  523.56  5500.2  532.64  5522.3  536.62  5617.6  550.21
#Mann=3,-1,0
  4516.0    0.12       0  5012.5    0.05       0  5016.5    0.12       0
Bank Sta=5012.5,5016.5
Exp/Cntr=0.3,0.1

Type RM Length L Ch R = 1,20523,354,354,354
BEGIN DESCRIPTION:
XS6772
END DESCRIPTION:
XS GIS Cut Line= 2
      2442976.27     13809926.97      2442113.67     13809249.72
#Sta/Elev= 30
  4501.1  537.42  4510.7  537.31  4531.5  535.08  4589.4  522.77  4631.0  516.25
  4680.7  510.26  4781.9  503.00  4887.7  494.05  4909.6  493.08  4966.3  492.66
  4973.1  489.19  4985.1  488.22  4985.3  487.72  4989.1  488.22  5080.2  488.36
  5087.5  489.36  5094.6  493.22  5101.0  494.82  5115.4  495.41  5151.1  493.95
  5208.5  497.32  5229.3  497.64  5251.9  500.35  5436.3  512.18  5471.6  515.17
  5500.5  519.26  5529.4  526.43  5564.6  532.80  5571.0  532.61  5597.8  535.56
#Mann=3,-1,0
  4501.1    0.12       0  4985.1    0.05       0  4989.1    0.12       0
Bank Sta=4985.1,4989.1
Exp/Cntr=0.3,0.1

Type RM Length L Ch R = 1,20169,254,254,254
BEGIN DESCRIPTION:
Stream0424 40.0
END DESCRIPTION:
XS GIS Cut Line= 3
      2442974.97     13809624.97      2442675.00     13809325.00
      2442375.03     13809175.02
#Sta/Elev= 30
  4575.8  512.88  4579.3  512.88  4589.9  509.84  4611.1  506.93  4618.2  505.13
  4632.3  503.01  4703.0  495.12  4731.3  493.08  4759.6  493.39  4787.9  492.69
  4802.0  488.46  4852.8  488.42  4980.7  488.30  5012.0  488.28  5012.3  487.78
  5015.8  487.78  5016.0  488.28  5044.7  488.37  5067.1  493.49  5093.1  493.66
  5120.2  492.89  5134.2  493.25  5178.9  495.22  5209.7  497.97  5246.0  499.69
  5304.7  504.14  5321.5  506.99  5327.1  507.12  5332.6  509.82  5335.4  509.82
#Mann=6,-1,0
  4575.8    0.12       0  4852.8   0.033       0  4980.7     0.1       0
  5012.0    0.05       0  5016.0     0.1       0  5093.1    0.12       0
Bank Sta=5012,5016
Exp/Cntr=0.3,0.1

Type RM Length L Ch R = 1,19915,239,239,239
BEGIN DESCRIPTION:
XS6771
END DESCRIPTION:
XS GIS Cut Line= 3
      2443197.33     13809552.47      2442776.54     13809106.72
      2442139.08     13808893.05
#Sta/Elev= 30
  4360.2  517.73  4388.3  517.09  4473.2  511.21  4561.8  498.10  4593.4  492.59
  4607.5  491.76  4650.0  492.38  4657.3  490.74  4664.2  491.95  4670.3  489.48
  4678.3  490.53  4685.6  488.73  4995.8  488.21  4996.0  487.71  4999.8  488.21
  5006.5  488.55  5017.0  491.51  5057.0  491.84  5058.1  491.73  5196.3  496.94
  5244.9  500.17  5259.6  500.02  5376.4  505.89  5497.3  513.60  5502.6  513.08
  5534.2  514.74  5560.4  517.41  5565.7  516.60  5597.3  520.33  5645.5  531.20
#Mann=7,-1,0
  4360.2    0.12       0  4561.8    0.07       0  4670.3   0.033       0
  4995.8   0.033       0  4999.8   0.033       0  5057.0     0.1       0
  5058.1    0.12       0
Bank Sta=4995.8,4999.8
Exp/Cntr=0.3,0.1

Type RM Length L Ch R = 1,19676,384,384,384
BEGIN DESCRIPTION:
Stream0424 39.0
END DESCRIPTION:
XS GIS Cut Line= 3
      2443528.97     13809167.33      2442929.89     13808935.55
      2442583.95     13808732.26
#Sta/Elev= 30
  4348.4  512.35  4631.4  488.85  4676.6  488.87  4703.0  491.44  4706.6  489.65
  4725.8  492.49  4731.1  489.44  4755.7  492.74  4761.1  491.38  4780.3  492.95
  4785.7  491.60  4792.3  492.95  4870.1  492.94  4894.7  491.10  4900.1  492.82
  4973.8  492.42  4979.2  489.76  4996.2  490.64  5002.0  487.72  5021.4  487.37
  5021.7  486.87  5025.4  487.37  5039.1  489.33  5066.4  488.23  5098.8  490.65
  5156.3  495.21  5257.8  507.51  5344.4  522.52  5365.1  523.74  5392.0  526.62
#Mann=6,-1,0
  4348.4    0.07       0  4703.0   0.033       0  5021.4   0.033       0
  5025.4   0.033       0  5098.8    0.07       0  5365.1    0.12       0
Bank Sta=5021.4,5025.4
Exp/Cntr=0.3,0.1

Type RM Length L Ch R = 1,19292,328,328,328
BEGIN DESCRIPTION:
Stream0424 38.0
END DESCRIPTION:
XS GIS Cut Line= 3
      2443525.02     13809075.02      2443225.00     13808775.00
      2442925.00     13808525.00
#Sta/Elev= 30
  4570.8  508.22  4574.4  508.22  4613.3  504.77  4641.5  503.31  4684.0  499.78
  4768.8  489.76  4783.0  487.34  4811.2  484.51  4853.7  482.79  4867.8  482.61
  4882.0  481.75  4896.1  482.11  4910.2  481.10  4933.6  481.10  5021.1  481.04
  5021.3  480.54  5024.8  480.54  5025.1  481.04  5085.3  481.21  5137.6  484.10
  5187.1  488.96  5222.2  491.60  5243.1  494.35  5271.7  499.03  5286.0  502.83
  5300.3  505.44  5314.7  508.93  5329.0  511.60  5357.6  515.63  5385.6  516.48
#Mann=5,-1,0
  4570.8    0.07       0  4933.6   0.033       0  5021.1   0.033       0
  5025.1   0.033       0  5085.3    0.07       0
Bank Sta=5021.1,5025.1
Exp/Cntr=0.3,0.1

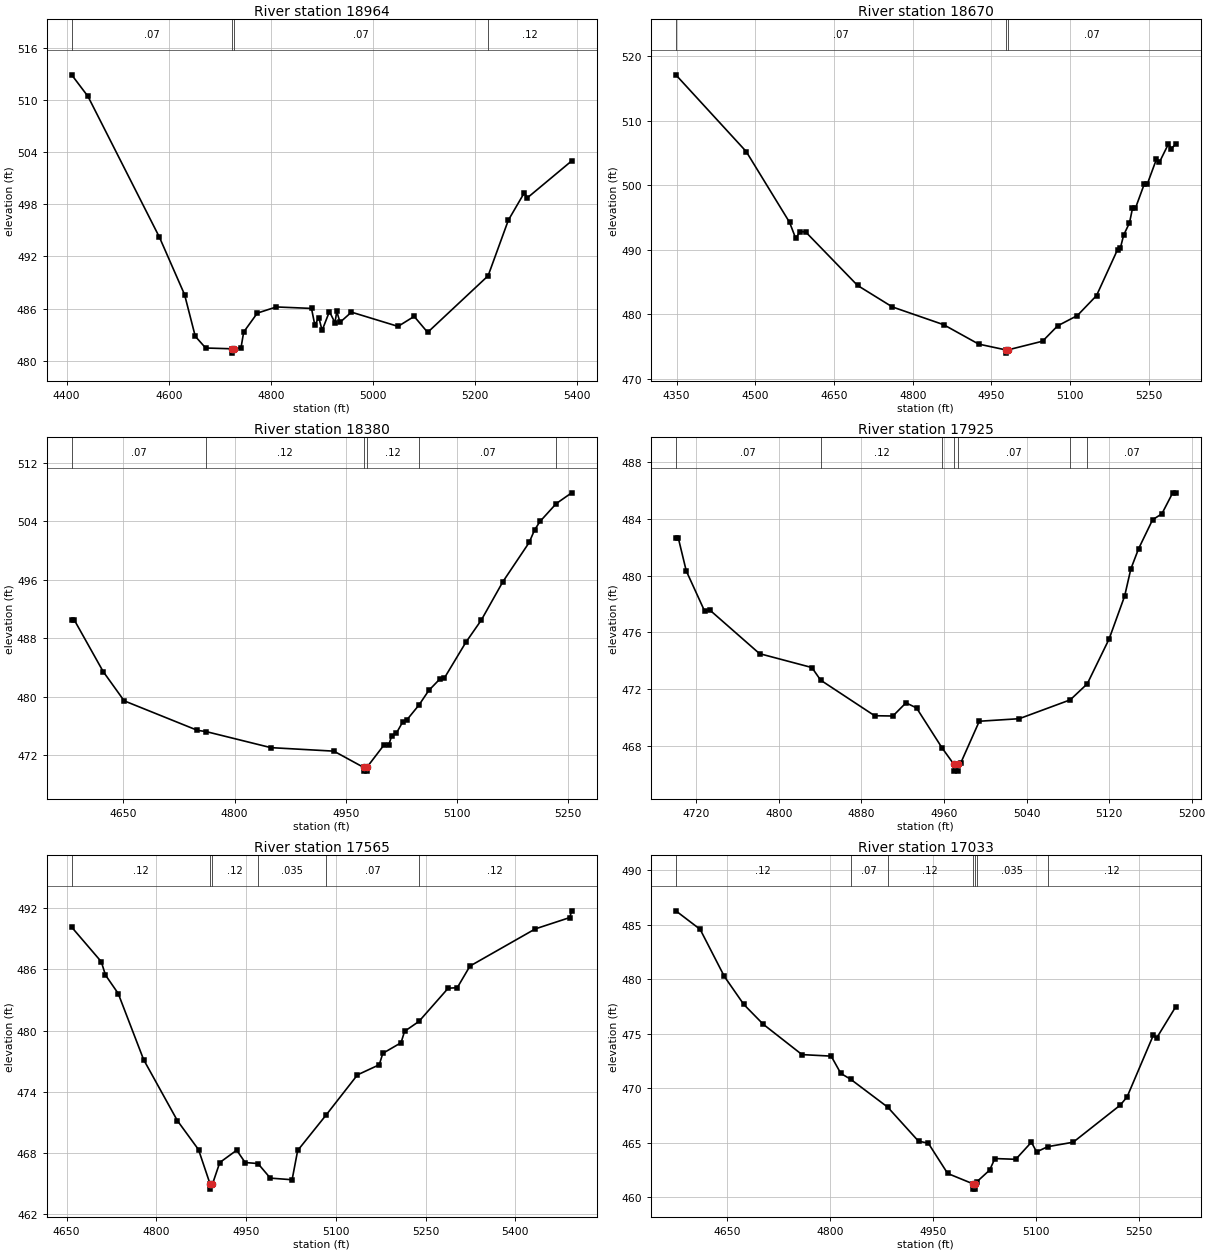
Type RM Length L Ch R = 1,18964,294,294,294
BEGIN DESCRIPTION:
XS6770
END DESCRIPTION:
XS GIS Cut Line= 5
      2443582.52     13809085.36      2443450.56     13808678.78
      2443393.50     13808611.02      2443322.17     13808521.86
      2442990.53     13808411.32
#Sta/Elev= 30
  4409.8  512.92  4441.7  510.44  4581.8  494.21  4631.0  487.61  4652.0  482.80
  4672.4  481.45  4723.6  481.36  4723.8  480.86  4727.6  481.36  4741.6  481.46
  4746.9  483.29  4773.6  485.47  4810.8  486.18  4879.8  486.01  4886.3  484.09
  4894.1  484.95  4900.6  483.48  4914.9  485.65  4925.8  484.36  4929.3  485.67
  4935.7  484.41  4958.1  485.58  5049.4  483.94  5081.0  485.09  5107.4  483.25
  5225.9  489.77  5265.5  496.17  5297.1  499.36  5302.4  498.73  5389.6  503.00
#Mann=4,-1,0
  4409.8    0.07       0  4723.6    0.05       0  4727.6    0.07       0
  5225.9    0.12       0
Bank Sta=4723.6,4727.6
Exp/Cntr=0.3,0.1

Type RM Length L Ch R = 1,18670,290,290,290
BEGIN DESCRIPTION:
Stream0424 37.0
END DESCRIPTION:
XS GIS Cut Line= 3
      2443775.01     13809075.04      2443632.44     13808511.17
      2443475.01     13808175.02
#Sta/Elev= 30
  4348.5  517.15  4482.6  505.26  4565.2  494.29  4576.8  491.83  4585.8  492.86
  4596.1  492.78  4694.7  484.51  4761.1  481.17  4858.8  478.42  4925.6  475.41
  4977.3  474.51  4977.5  474.01  4981.3  474.51  5047.4  475.86  5076.1  478.24
  5113.6  479.83  5150.2  482.93  5190.3  490.06  5195.8  490.35  5201.9  492.31
  5213.0  494.20  5218.7  496.43  5224.2  496.44  5241.5  500.29  5247.0  500.23
  5264.3  504.05  5269.8  503.56  5287.2  506.43  5292.7  505.72  5301.3  506.42
#Mann=3,-1,0
  4348.5    0.07       0  4977.3    0.05       0  4981.3    0.07       0
Bank Sta=4977.3,4981.3
Exp/Cntr=0.3,0.1

Type RM Length L Ch R = 1,18380,455,455,455
BEGIN DESCRIPTION:
Stream0424 36.0
END DESCRIPTION:
XS GIS Cut Line= 3
      2444125.03     13808575.03      2443825.00     13808275.00
      2443675.00     13808075.00
#Sta/Elev= 30
  4580.2  490.48  4583.8  490.48  4622.7  483.42  4651.0  479.41  4749.9  475.36
  4761.6  475.19  4848.9  472.99  4933.8  472.51  4974.2  470.27  4974.5  469.77
  4978.0  469.77  4978.2  470.27  5001.0  473.30  5007.6  473.30  5011.8  474.59
  5018.0  474.96  5026.4  476.46  5032.6  476.84  5048.5  478.82  5061.8  480.83
  5076.4  482.36  5082.6  482.49  5111.8  487.43  5132.6  490.47  5161.8  495.75
  5197.2  501.12  5204.5  502.84  5211.8  504.00  5233.8  506.46  5254.5  507.93
#Mann=6,-1,0
  4580.2    0.07       0  4761.6    0.12       0  4974.2    0.05       0
  4978.2    0.12       0  5048.5    0.07       0  5233.8   0.035       0
Bank Sta=4974.2,4978.2
Exp/Cntr=0.3,0.1

Type RM Length L Ch R = 1,17925,360,360,360
BEGIN DESCRIPTION:
Stream0424 35.0
END DESCRIPTION:
XS GIS Cut Line= 3
      2444275.00     13808474.99      2444225.00     13808175.00
      2444075.00     13808075.00
#Sta/Elev= 30
  4700.2  482.63  4702.7  482.63  4710.3  480.34  4728.1  477.50  4733.1  477.58
  4781.3  474.50  4832.0  473.52  4840.5  472.63  4892.8  470.12  4910.5  470.10
  4923.2  471.03  4933.4  470.67  4958.3  467.83  4969.4  466.71  4969.6  466.21
  4973.1  466.21  4973.4  466.71  4976.4  466.81  4994.2  469.73  5032.9  469.91
  5082.3  471.24  5098.8  472.37  5120.0  475.54  5135.0  478.56  5141.0  480.47
  5148.5  481.90  5162.1  483.95  5171.1  484.37  5181.6  485.85  5184.6  485.85
#Mann=7,-1,0
  4700.2    0.07       0  4840.5    0.12       0  4958.3    0.07       0
  4969.4    0.05       0  4973.4    0.07       0  5082.3    0.12       0
  5098.8    0.07       0
Bank Sta=4969.4,4973.4
Exp/Cntr=0.3,0.1

Type RM Length L Ch R = 1,17565,532,532,532
BEGIN DESCRIPTION:
Stream0424 34.0
END DESCRIPTION:
XS GIS Cut Line= 3
      2444725.01     13808175.01      2444506.16     13807961.97
      2444058.40     13807677.68
#Sta/Elev= 30
  4658.4  490.14  4707.9  486.75  4714.9  485.44  4736.2  483.63  4778.7  477.14
  4835.2  471.15  4870.5  468.31  4889.8  464.94  4890.1  464.44  4893.8  464.94
  4906.0  467.05  4934.3  468.26  4948.4  467.05  4969.8  466.95  4990.5  465.52
  5026.9  465.36  5036.2  468.23  5084.3  471.75  5136.2  475.65  5172.6  476.64
  5178.5  477.76  5209.0  478.80  5214.9  479.92  5238.9  480.89  5287.8  484.15
  5303.0  484.20  5324.2  486.32  5433.5  489.97  5491.1  491.08  5494.2  491.74
#Mann=6,-1,0
  4658.4    0.12       0  4889.8   0.035       0  4893.8    0.12       0
  4969.8   0.035       0  5084.3    0.07       0  5238.9    0.12       0
Bank Sta=4889.8,4893.8
Exp/Cntr=0.3,0.1

Type RM Length L Ch R = 1,17033,468,468,468
BEGIN DESCRIPTION:
Stream0424 33.0
END DESCRIPTION:
XS GIS Cut Line= 3
      2445025.00     13807825.00      2444725.00     13807525.00
      2444425.00     13807575.00
#Sta/Elev= 30
  4575.4  486.29  4610.8  484.59  4646.1  480.26  4674.4  477.69  4702.7  475.87
  4759.2  473.08  4801.7  472.94  4815.8  471.35  4830.2  470.81  4884.1  468.25
  4929.0  465.12  4943.1  464.95  4971.4  462.16  5007.8  461.22  5008.1  460.72
  5011.6  460.72  5011.8  461.22  5014.4  461.42  5032.6  462.47  5040.2  463.53
  5070.6  463.46  5093.4  465.03  5101.0  464.14  5117.1  464.62  5154.3  465.03
  5222.7  468.43  5232.8  469.19  5270.9  474.84  5275.9  474.61  5303.8  477.49
#Mann=7,-1,0
  4575.4    0.12       0  4830.2    0.07       0  4884.1    0.12       0
  5007.8    0.05       0  5011.8    0.12       0  5014.4   0.035       0
  5117.1    0.12       0
Bank Sta=5007.8,5011.8
Exp/Cntr=0.3,0.1

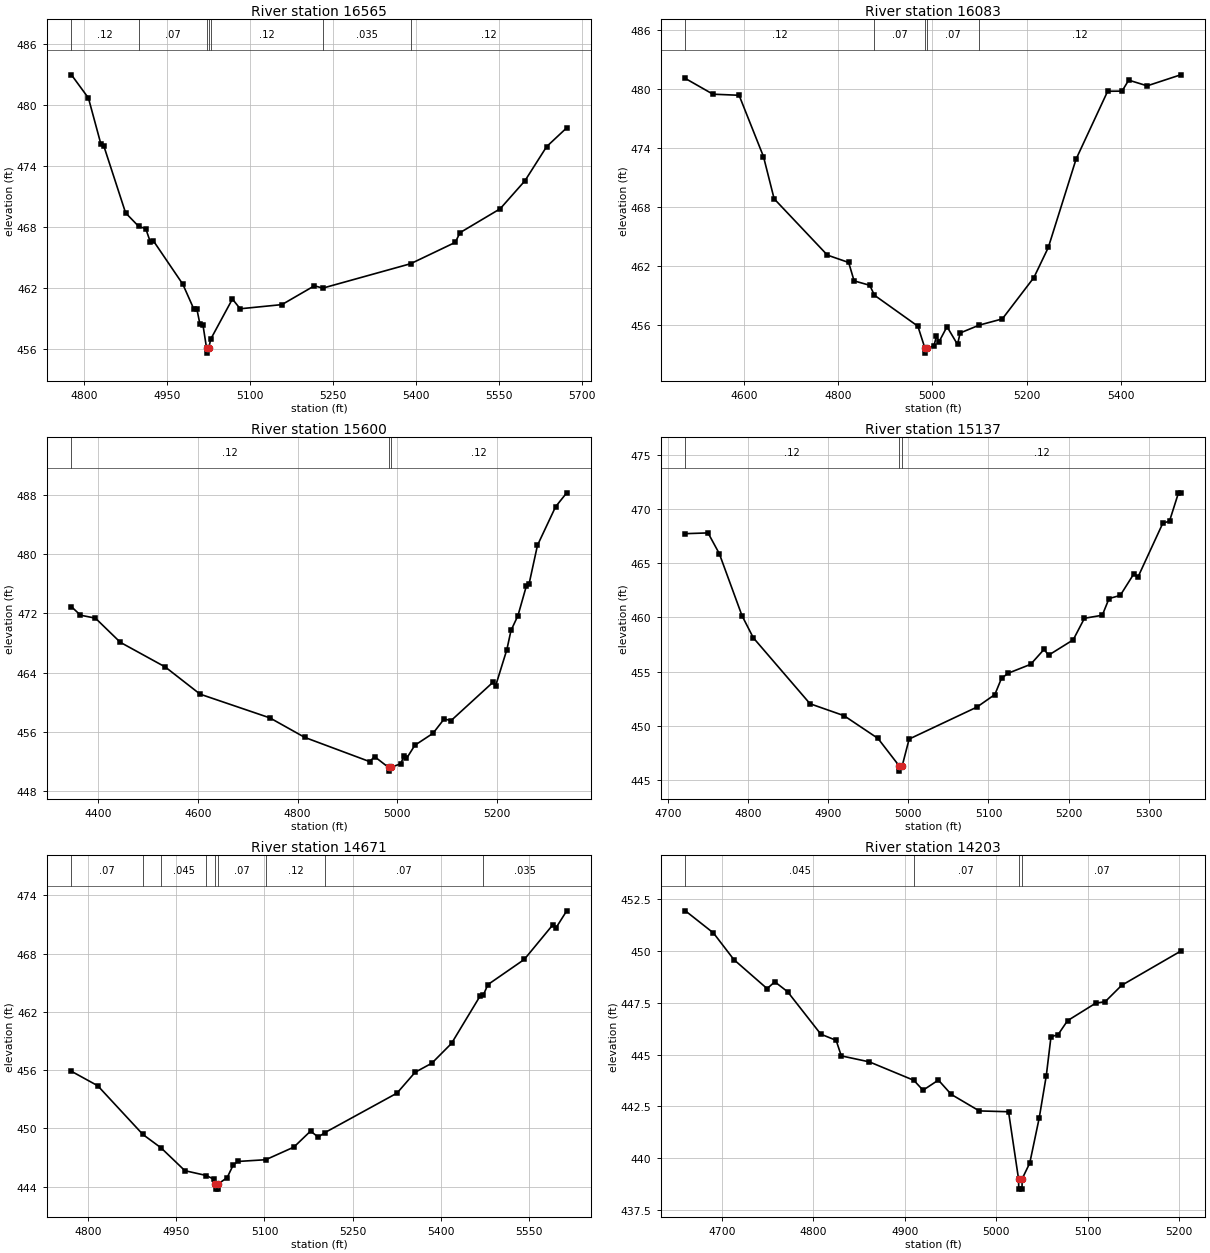
Type RM Length L Ch R = 1,16565,482,482,482
BEGIN DESCRIPTION:
Stream0424 32.0
END DESCRIPTION:
XS GIS Cut Line= 3
      2445124.99     13807224.99      2444925.00     13807125.00
      2444325.01     13807424.99
#Sta/Elev= 30
  4777.3  482.99  4808.0  480.71  4830.4  476.20  4836.0  475.96  4875.1  469.42
  4898.9  468.08  4911.5  467.87  4919.8  466.55  4925.4  466.66  4978.5  462.40
  4998.1  459.99  5003.7  459.99  5009.3  458.50  5014.9  458.37  5021.3  456.13
  5021.5  455.63  5025.3  456.13  5028.8  457.00  5068.0  460.95  5082.0  459.99
  5157.4  460.40  5216.1  462.25  5231.1  462.02  5389.8  464.42  5470.5  466.52
  5478.9  467.47  5551.5  469.82  5596.2  472.57  5635.4  475.93  5671.7  477.78
#Mann=7,-1,0
  4777.3    0.12       0  4898.9    0.07       0  5021.3    0.05       0
  5025.3    0.07       0  5028.8    0.12       0  5231.1   0.035       0
  5389.8    0.12       0
Bank Sta=5021.3,5025.3
Exp/Cntr=0.3,0.1

Type RM Length L Ch R = 1,16083,483,483,483
BEGIN DESCRIPTION:
Stream0424 31.0
END DESCRIPTION:
XS GIS Cut Line= 3
      2445297.81     13806902.78      2444825.00     13806675.00
      2444353.63     13806439.60
#Sta/Elev= 30
  4475.6  481.08  4534.2  479.48  4589.7  479.37  4641.5  473.13  4664.1  468.84
  4777.2  463.11  4822.4  462.36  4833.9  460.49  4867.2  460.04  4877.1  459.03
  4969.3  455.88  4984.3  453.64  4984.6  453.14  4988.3  453.64  5003.2  453.86
  5008.8  454.85  5014.4  454.31  5031.2  455.83  5053.5  454.02  5059.1  455.19
  5099.7  455.99  5148.6  456.62  5215.7  460.83  5246.3  463.89  5305.2  472.87
  5372.3  479.78  5402.8  479.79  5417.0  480.91  5456.2  480.33  5527.3  481.45
#Mann=5,-1,0
  4475.6    0.12       0  4877.1    0.07       0  4984.3    0.05       0
  4988.3    0.07       0  5099.7    0.12       0
Bank Sta=4984.3,4988.3
Exp/Cntr=0.3,0.1

Type RM Length L Ch R = 1,15600,463,463,463
BEGIN DESCRIPTION:
Stream0424 30.0
END DESCRIPTION:
XS GIS Cut Line= 3
      2445383.07     13806234.26      2444725.00     13806225.00
      2444425.04     13806075.02
#Sta/Elev= 30
  4346.4  472.92  4364.5  471.77  4394.5  471.37  4444.5  468.10  4534.5  464.77
  4604.5  461.09  4744.5  457.88  4814.5  455.24  4944.5  451.97  4954.5  452.64
  4982.5  451.18  4982.8  450.68  4986.5  451.18  5007.3  451.68  5012.9  452.75
  5018.5  452.39  5035.3  454.18  5071.6  455.79  5094.0  457.73  5108.0  457.52
  5191.8  462.69  5197.4  462.24  5219.8  467.11  5228.1  469.70  5242.1  471.72
  5258.9  475.71  5264.5  476.04  5281.2  481.22  5317.6  486.44  5339.9  488.32
#Mann=3,-1,0
  4346.4    0.12       0  4982.5    0.05       0  4986.5    0.12       0
Bank Sta=4982.5,4986.5
Exp/Cntr=0.3,0.1

Type RM Length L Ch R = 1,15137,466,466,466
BEGIN DESCRIPTION:
Stream0424 29.0
END DESCRIPTION:
XS GIS Cut Line= 3
      2444975.00     13805975.00      2444775.00     13805775.00
      2444475.04     13805924.98
#Sta/Elev= 30
  4721.7  467.73  4750.0  467.80  4764.1  465.88  4792.4  460.16  4806.5  458.12
  4877.3  452.03  4919.7  450.93  4962.1  448.83  4988.4  446.31  4988.6  445.81
  4992.4  446.31  5001.0  448.77  5085.6  451.72  5108.0  452.88  5116.3  454.38
  5124.7  454.85  5152.7  455.67  5169.4  457.05  5175.0  456.51  5205.8  457.93
  5219.8  459.92  5242.1  460.20  5250.5  461.74  5264.5  462.03  5281.2  463.99
  5286.8  463.75  5317.6  468.69  5326.0  468.89  5337.2  471.50  5339.9  471.50
#Mann=3,-1,0
  4721.7    0.12       0  4988.4    0.05       0  4992.4    0.12       0
Bank Sta=4988.4,4992.4
Exp/Cntr=0.3,0.1

Type RM Length L Ch R = 1,14671,468,468,468
BEGIN DESCRIPTION:
Stream0424 28.0
END DESCRIPTION:
XS GIS Cut Line= 3
      2445175.00     13805475.00      2444975.00     13805375.00
      2444374.97     13805224.99
#Sta/Elev= 30
  4771.8  455.88  4816.5  454.39  4893.3  449.37  4924.4  447.98  4964.7  445.64
  5001.4  445.14  5013.4  444.77  5016.6  444.24  5016.8  443.74  5020.3  443.74
  5020.6  444.24  5036.6  444.93  5046.9  446.23  5054.7  446.59  5102.2  446.77
  5150.0  448.07  5178.4  449.72  5191.3  449.10  5203.0  449.57  5325.3  453.63
  5356.2  455.78  5384.5  456.71  5418.0  458.75  5467.0  463.67  5472.2  463.75
  5479.9  464.81  5541.7  467.40  5590.7  471.00  5595.8  470.67  5613.9  472.41
#Mann=9,-1,0
  4771.8    0.07       0  4893.3    0.12       0  4924.4   0.045       0
  5001.4    0.07       0  5016.6   0.045       0  5020.6    0.07       0
  5102.2    0.12       0  5203.0    0.07       0  5472.2   0.035       0
Bank Sta=5016.6,5020.6
Exp/Cntr=0.3,0.1

Type RM Length L Ch R = 1,14203,472,472,472
BEGIN DESCRIPTION:
Stream0424 27.0
END DESCRIPTION:
XS GIS Cut Line= 3
      2445325.00     13805274.99      2445175.00     13804975.00
      2444974.96     13804924.99
#Sta/Elev= 30
  4660.2  451.95  4690.9  450.88  4713.3  449.59  4749.6  448.19  4758.0  448.52
  4772.0  448.04  4808.3  445.99  4825.1  445.69  4830.7  444.94  4861.4  444.65
  4910.0  443.76  4920.1  443.28  4936.9  443.77  4950.9  443.08  4981.6  442.28
  5013.6  442.24  5024.5  439.00  5024.8  438.50  5028.3  438.50  5028.5  439.00
  5036.8  439.76  5047.1  441.93  5054.9  443.99  5060.0  445.86  5067.8  445.97
  5078.1  446.64  5109.0  447.49  5119.3  447.56  5137.3  448.35  5201.8  450.00
#Mann=4,-1,0
  4660.2   0.045       0  4910.0    0.07       0  5024.5    0.05       0
  5028.5    0.07       0
Bank Sta=5024.5,5028.5
Exp/Cntr=0.3,0.1

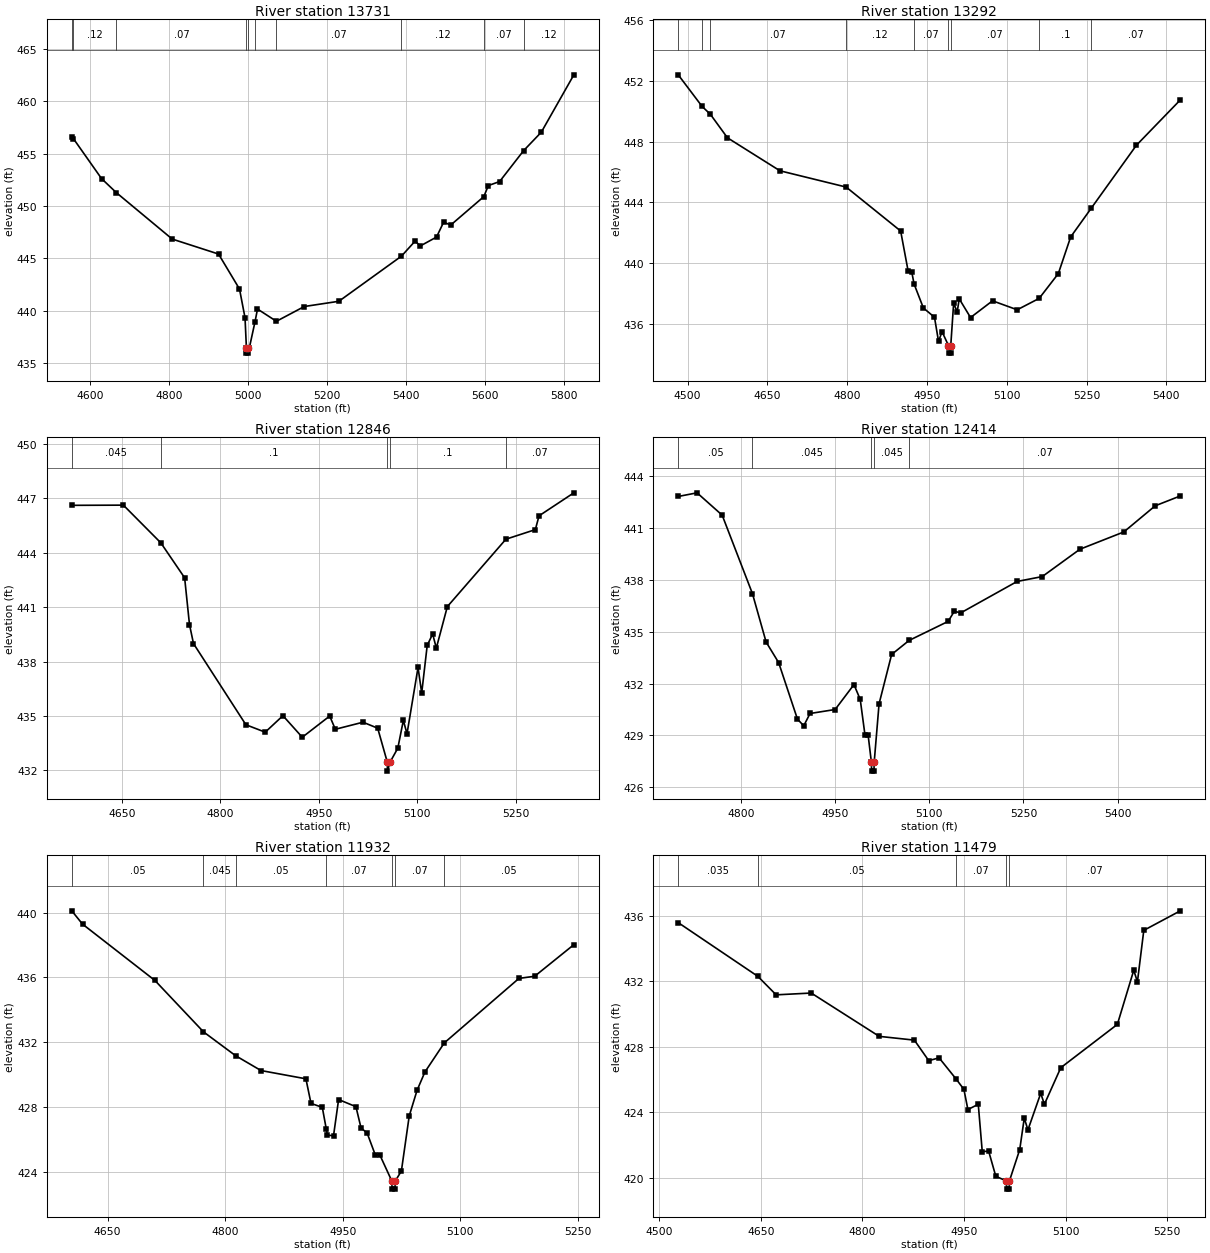
Type RM Length L Ch R = 1,13731,439,439,439
BEGIN DESCRIPTION:
Stream0424 26.0
END DESCRIPTION:
XS GIS Cut Line= 3
      2445875.04     13804825.02      2445475.00     13804625.00
      2444674.99     13804425.00
#Sta/Elev= 30
  4553.0  456.62  4557.1  456.44  4628.5  452.62  4665.7  451.29  4807.4  446.85
  4924.8  445.42  4977.9  442.08  4991.9  439.34  4995.4  436.46  4995.6  435.96
  4999.3  435.96  4999.6  436.46  5002.8  436.46  5017.3  438.97  5023.5  440.17
  5071.4  439.00  5142.0  440.41  5229.6  440.91  5388.2  445.22  5422.9  446.66
  5435.8  446.19  5477.0  447.04  5495.0  448.46  5513.1  448.19  5596.8  450.90
  5608.4  451.96  5636.8  452.34  5697.6  455.29  5742.4  457.05  5824.9  462.53
#Mann=10,-1,0
  4553.0    0.07       0  4557.1    0.12       0  4665.7    0.07       0
  4995.4    0.05       0  4999.6    0.07       0  5017.3    0.12       0
  5071.4    0.07       0  5388.2    0.12       0  5596.8    0.07       0
  5697.6    0.12       0
Bank Sta=4995.4,4999.6
Exp/Cntr=0.3,0.1

Type RM Length L Ch R = 1,13292,446,446,446
BEGIN DESCRIPTION:
Stream0424 25.0
END DESCRIPTION:
XS GIS Cut Line= 3
      2445925.00     13804575.00      2445525.00     13804225.00
      2445125.01     13804125.00
#Sta/Elev= 30
  4482.5  452.39  4527.4  450.31  4542.8  449.80  4575.0  448.25  4673.7  446.08
  4798.1  445.01  4900.6  442.12  4914.8  439.46  4921.5  439.42  4925.8  438.64
  4943.3  437.06  4964.2  436.45  4971.8  434.86  4978.4  435.50  4990.5  434.59
  4990.8  434.09  4994.5  434.09  4994.8  434.59  5000.2  437.37  5006.9  436.80
  5010.7  437.66  5032.0  436.43  5073.3  437.53  5119.7  436.94  5161.0  437.69
  5197.0  439.32  5220.2  441.73  5259.1  443.63  5343.8  447.76  5426.3  450.74
#Mann=9,-1,0
  4482.5    0.07       0  4527.4    0.12       0  4542.8    0.07       0
  4798.1    0.12       0  4925.8    0.07       0  4990.5    0.05       0
  4994.8    0.07       0  5161.0     0.1       0  5259.1    0.07       0
Bank Sta=4990.5,4994.8
Exp/Cntr=0.3,0.1

Type RM Length L Ch R = 1,12846,432,432,432
BEGIN DESCRIPTION:
Stream0424 24.0
END DESCRIPTION:
XS GIS Cut Line= 3
      2445775.03     13804175.04      2445525.00     13803825.00
      2445224.97     13803975.01
#Sta/Elev= 30
  4573.3  446.62  4652.0  446.63  4709.1  444.55  4745.4  442.62  4752.8  440.04
  4758.9  438.99  4838.8  434.51  4868.3  434.10  4895.3  435.01  4924.8  433.82
  4966.6  434.99  4975.2  434.26  5017.4  434.65  5039.8  434.32  5054.4  432.45
  5054.7  431.95  5058.7  432.45  5070.5  433.22  5078.9  434.75  5084.5  434.01
  5101.3  437.67  5106.9  436.26  5115.3  438.89  5123.6  439.52  5129.2  438.74
  5146.0  441.03  5235.3  444.75  5280.2  445.28  5285.8  446.04  5338.9  447.31
#Mann=5,-1,0
  4573.3   0.045       0  4709.1     0.1       0  5054.4    0.05       0
  5058.7     0.1       0  5235.3    0.07       0
Bank Sta=5054.4,5058.7
Exp/Cntr=0.3,0.1

Type RM Length L Ch R = 1,12414,482,482,482
BEGIN DESCRIPTION:
Stream0424 23.0
END DESCRIPTION:
XS GIS Cut Line= 3
      2446075.02     13803675.00      2445775.00     13803675.00
      2445275.02     13803675.00
#Sta/Elev= 30
  4700.0  442.81  4730.0  443.02  4770.0  441.73  4818.3  437.19  4840.0  434.40
  4860.0  433.21  4890.0  429.94  4900.0  429.56  4910.0  430.27  4950.0  430.50
  4980.0  431.94  4990.0  431.08  4997.5  429.04  5002.5  429.04  5007.8  427.44
  5008.1  426.94  5011.9  426.94  5012.2  427.44  5020.0  430.83  5040.0  433.68
  5067.8  434.49  5130.0  435.59  5140.0  436.18  5150.0  436.08  5240.0  437.90
  5280.0  438.18  5340.0  439.76  5410.0  440.76  5460.0  442.27  5500.0  442.84
#Mann=5,-1,0
  4700.0    0.05       0  4818.3   0.045       0  5007.8   0.045       0
  5012.2   0.045       0  5067.8    0.07       0
Bank Sta=5007.8,5012.2
Exp/Cntr=0.3,0.1

Type RM Length L Ch R = 1,11932,453,453,453
BEGIN DESCRIPTION:
Stream0424 22.0
END DESCRIPTION:
XS GIS Cut Line= 3
      2446024.99     13803524.99      2445775.00     13803225.00
      2445525.00     13803225.00
#Sta/Elev= 30
  4604.4  440.11  4618.1  439.29  4710.5  435.81  4772.4  432.64  4813.3  431.17
  4845.8  430.25  4903.1  429.74  4909.6  428.22  4924.0  427.98  4929.0  426.66
  4930.5  426.27  4938.3  426.22  4944.8  428.46  4966.9  428.02  4973.4  426.71
  4981.2  426.39  4991.6  425.04  4997.4  425.04  5012.7  423.43  5013.0  422.93
  5016.8  422.93  5017.1  423.43  5024.9  424.05  5034.9  427.45  5044.9  429.03
  5054.9  430.16  5079.7  431.96  5174.9  435.94  5194.9  436.07  5244.9  438.02
#Mann=7,-1,0
  4604.4    0.05       0  4772.4   0.045       0  4813.3    0.05       0
  4929.0    0.07       0  5012.7    0.05       0  5017.1    0.07       0
  5079.7    0.05       0
Bank Sta=5012.7,5017.1
Exp/Cntr=0.3,0.1

Type RM Length L Ch R = 1,11479,474,474,474
BEGIN DESCRIPTION:
Stream0424 21.0
END DESCRIPTION:
XS GIS Cut Line= 3
      2446225.00     13803274.99      2445975.00     13802875.00
      2445724.95     13802774.98
#Sta/Elev= 30
  4528.3  435.57  4645.7  432.30  4672.8  431.17  4724.6  431.28  4824.9  428.64
  4876.8  428.41  4898.0  427.16  4913.3  427.33  4938.6  426.03  4949.9  425.41
  4955.8  424.18  4971.1  424.50  4977.0  421.61  4986.4  421.65  4997.0  420.11
  5012.6  419.83  5012.9  419.33  5016.8  419.33  5017.1  419.83  5032.3  421.74
  5039.0  423.66  5044.4  422.94  5063.3  425.17  5068.7  424.50  5092.9  426.73
  5176.4  429.37  5200.6  432.67  5206.0  431.96  5215.4  435.10  5269.3  436.29
#Mann=5,-1,0
  4528.3   0.035       0  4645.7    0.05       0  4938.6    0.07       0
  5012.6    0.05       0  5017.1    0.07       0
Bank Sta=5012.6,5017.1
Exp/Cntr=0.3,0.1

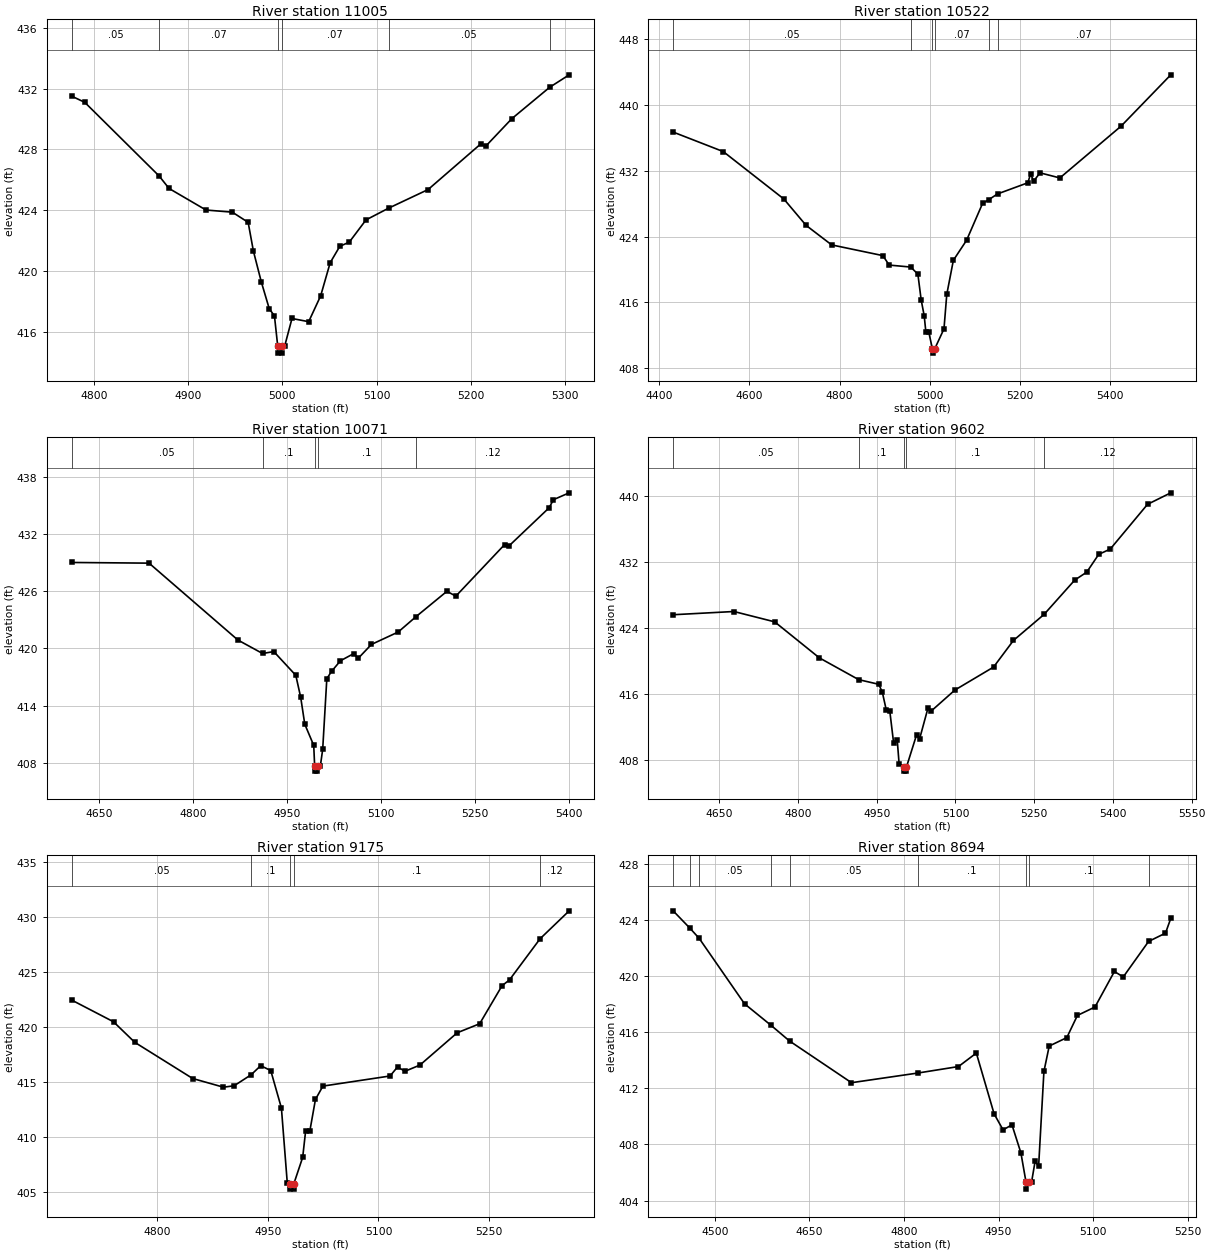
Type RM Length L Ch R = 1,11005,483,483,483
BEGIN DESCRIPTION:
Stream0424 20.0
END DESCRIPTION:
XS GIS Cut Line= 3
      2446325.02     13802575.01      2446125.00     13802475.00
      2445824.97     13802525.01
#Sta/Elev= 30
  4776.5  431.51  4790.5  431.10  4869.4  426.25  4879.9  425.43  4919.1  424.01
  4947.0  423.87  4963.8  423.20  4969.4  421.30  4977.8  419.27  4986.2  417.51
  4991.7  417.04  4995.1  415.09  4995.4  414.59  4999.3  414.59  4999.6  415.09
  5002.7  415.09  5010.3  416.87  5028.0  416.66  5040.7  418.36  5050.8  420.54
  5061.0  421.62  5071.1  421.90  5088.8  423.36  5112.7  424.13  5154.7  425.36
  5210.5  428.36  5215.6  428.20  5243.4  430.02  5283.6  432.09  5304.3  432.91
#Mann=6,-1,0
  4776.5    0.05       0  4869.4    0.07       0  4995.1    0.05       0
  4999.6    0.07       0  5112.7    0.05       0  5283.6    0.07       0
Bank Sta=4995.1,4999.6
Exp/Cntr=0.3,0.1

Type RM Length L Ch R = 1,10522,451,451,451
BEGIN DESCRIPTION:
Stream0424 19.0
END DESCRIPTION:
XS GIS Cut Line= 3
      2446656.60     13802490.33      2446275.00     13802075.00
      2445839.93     13801755.68
#Sta/Elev= 30
  4430.7  436.68  4541.9  434.31  4676.3  428.55  4725.6  425.35  4782.3  422.98
  4895.8  421.68  4909.9  420.53  4957.7  420.29  4973.5  419.43  4980.8  416.31
  4987.6  414.35  4991.3  412.36  4997.8  412.36  5005.8  410.34  5006.2  409.84
  5010.7  410.34  5031.4  412.79  5037.6  416.97  5052.2  421.11  5081.5  423.54
  5117.0  428.02  5130.6  428.47  5150.2  429.17  5217.3  430.52  5223.5  431.58
  5230.4  430.73  5244.4  431.73  5288.4  431.11  5424.2  437.40  5534.4  443.63
#Mann=6,-1,0
  4430.7    0.05       0  4957.7    0.07       0  5005.8    0.05       0
  5010.7    0.07       0  5130.6     0.1       0  5150.2    0.07       0
Bank Sta=5005.8,5010.7
Exp/Cntr=0.3,0.1

Type RM Length L Ch R = 1,10071,469,469,469
BEGIN DESCRIPTION:
Stream0424 18.0
END DESCRIPTION:
XS GIS Cut Line= 3
      2446777.85     13802026.73      2446525.00     13801725.00
      2446260.73     13801424.02
#Sta/Elev= 30
  4606.3  429.00  4730.0  428.93  4871.8  420.87  4911.2  419.46  4929.1  419.66
  4964.2  417.17  4972.0  414.87  4978.5  412.05  4992.8  409.83  4994.3  407.63
  4994.6  407.13  4998.8  407.13  4999.2  407.63  5003.3  407.63  5007.1  409.41
  5013.7  416.82  5021.3  417.59  5035.5  418.70  5056.4  419.44  5064.0  418.97
  5084.9  420.41  5127.6  421.71  5155.5  423.29  5205.4  425.98  5219.6  425.47
  5297.5  430.88  5305.0  430.77  5368.6  434.74  5375.3  435.58  5400.5  436.30
#Mann=5,-1,0
  4606.3    0.05       0  4911.2     0.1       0  4994.3    0.05       0
  4999.2     0.1       0  5155.5    0.12       0
Bank Sta=4994.3,4999.2
Exp/Cntr=0.3,0.1

Type RM Length L Ch R = 1,9602,427,427,427
BEGIN DESCRIPTION:
Stream0424 17.0
END DESCRIPTION:
XS GIS Cut Line= 3
      2447191.63     13801721.88      2446875.00     13801425.00
      2446424.79     13801176.67
#Sta/Elev= 30
  4562.0  425.59  4677.8  425.98  4755.5  424.73  4840.5  420.38  4915.6  417.74
  4953.8  417.18  4960.6  416.22  4967.9  414.13  4974.8  413.96  4982.1  410.09
  4989.0  410.41  4992.6  407.55  5001.6  407.18  5002.0  406.68  5006.2  406.68
  5006.6  407.18  5025.8  411.06  5031.6  410.58  5047.6  414.31  5053.3  413.92
  5098.8  416.48  5172.5  419.26  5210.4  422.48  5268.8  425.63  5327.2  429.78
  5350.1  430.74  5372.9  432.89  5394.9  433.53  5465.9  438.94  5510.2  440.33
#Mann=5,-1,0
  4562.0    0.05       0  4915.6     0.1       0  5001.6    0.05       0
  5006.6     0.1       0  5268.8    0.12       0
Bank Sta=5001.6,5006.6
Exp/Cntr=0.3,0.1

Type RM Length L Ch R = 1,9175,481,481,481
BEGIN DESCRIPTION:
Stream0424 16.0
END DESCRIPTION:
XS GIS Cut Line= 3
      2447224.97     13801224.98      2446975.00     13801025.00
      2446624.97     13801075.00
#Sta/Elev= 30
  4684.5  422.48  4741.3  420.50  4770.1  418.63  4848.5  415.34  4890.2  414.55
  4904.6  414.68  4927.6  415.68  4940.6  416.51  4954.2  416.06  4968.6  412.66
  4976.6  405.80  4980.5  405.78  4980.9  405.28  4985.1  405.28  4985.5  405.78
  4997.4  408.17  5001.4  410.57  5007.1  410.57  5014.7  413.44  5024.8  414.65
  5115.7  415.57  5125.8  416.39  5135.9  416.00  5156.1  416.56  5206.6  419.50
  5237.0  420.32  5267.3  423.78  5277.4  424.31  5318.8  428.05  5358.2  430.59
#Mann=5,-1,0
  4684.5    0.05       0  4927.6     0.1       0  4980.5    0.05       0
  4985.5     0.1       0  5318.8    0.12       0
Bank Sta=4980.5,4985.5
Exp/Cntr=0.3,0.1

Type RM Length L Ch R = 1,8694,397,397,397
BEGIN DESCRIPTION:
Stream0424 15.0
END DESCRIPTION:
XS GIS Cut Line= 3
      2447375.02     13800975.02      2446975.00     13800575.00
      2446775.02     13800674.99
#Sta/Elev= 30
  4433.8  424.64  4460.7  423.39  4475.1  422.68  4547.0  418.02  4589.2  416.48
  4618.4  415.37  4716.7  412.40  4822.2  413.09  4886.4  413.55  4914.7  414.51
  4942.9  410.18  4957.1  409.04  4971.2  409.40  4985.4  407.40  4993.5  405.32
  4993.8  404.82  4998.5  405.32  5002.3  405.32  5007.9  406.80  5013.5  406.46
  5021.9  413.20  5030.3  415.01  5058.2  415.61  5075.0  417.19  5102.9  417.79
  5133.7  420.32  5147.7  419.93  5187.9  422.46  5214.7  423.05  5223.1  424.10
#Mann=9,-1,0
  4433.8    0.12       0  4460.7    0.07       0  4475.1    0.05       0
  4589.2    0.07       0  4618.4    0.05       0  4822.2     0.1       0
  4993.5    0.05       0  4998.5     0.1       0  5187.9    0.12       0
Bank Sta=4993.5,4998.5
Exp/Cntr=0.3,0.1