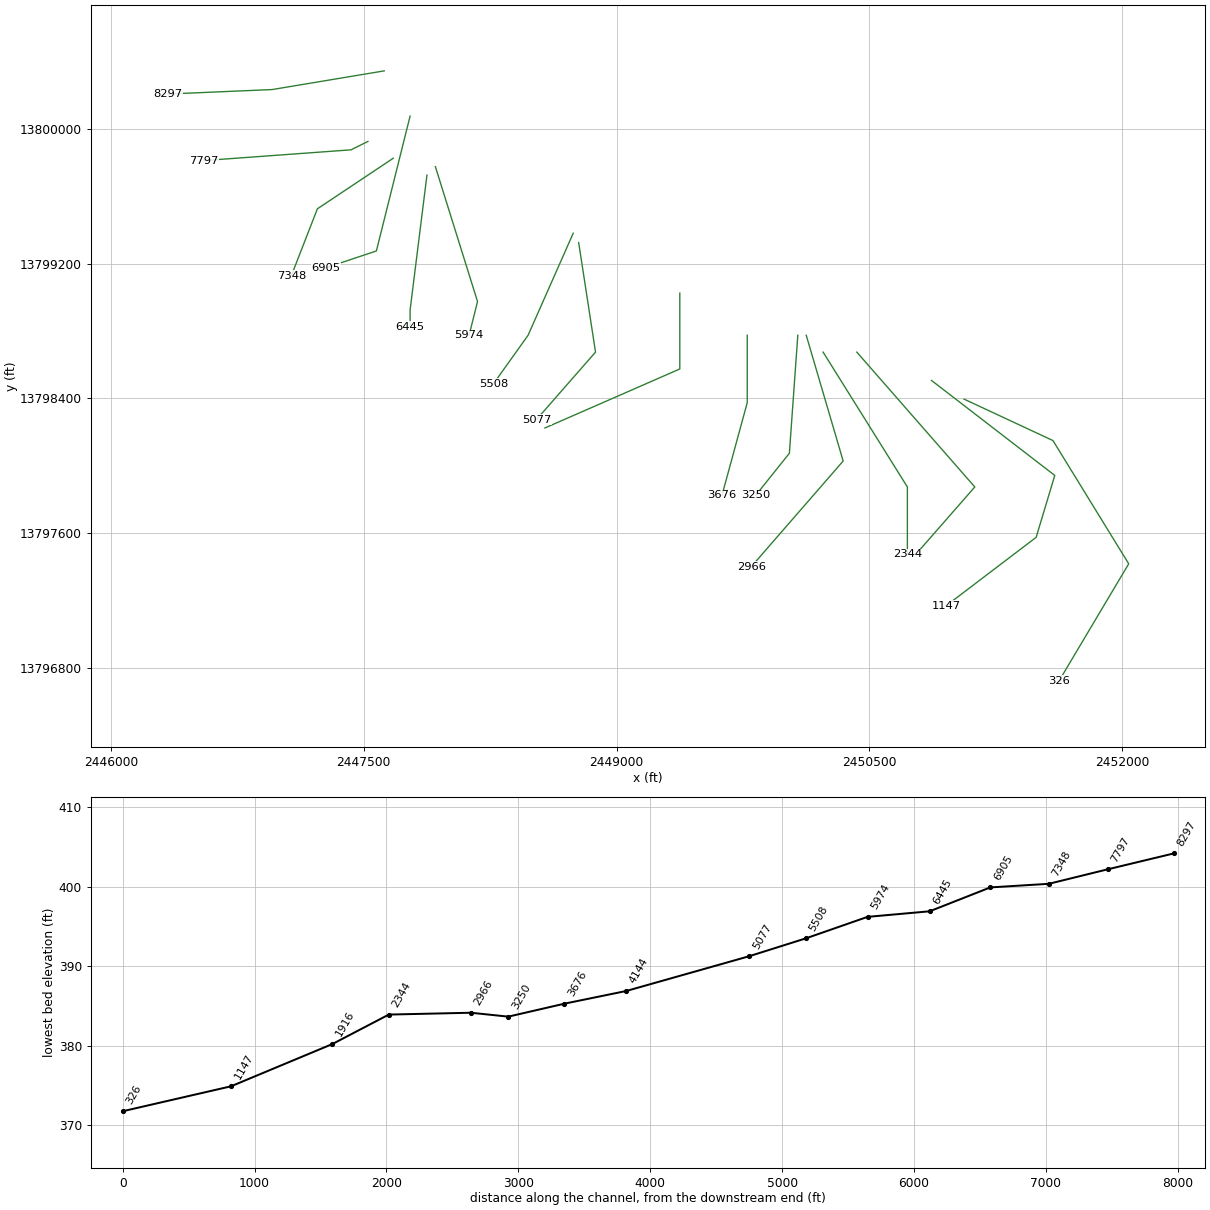
HEC-RAS study Stream0424.prj: Stream0424 Base Level Engineering

--- Stream0424.g01 (geometry) --- (continued)

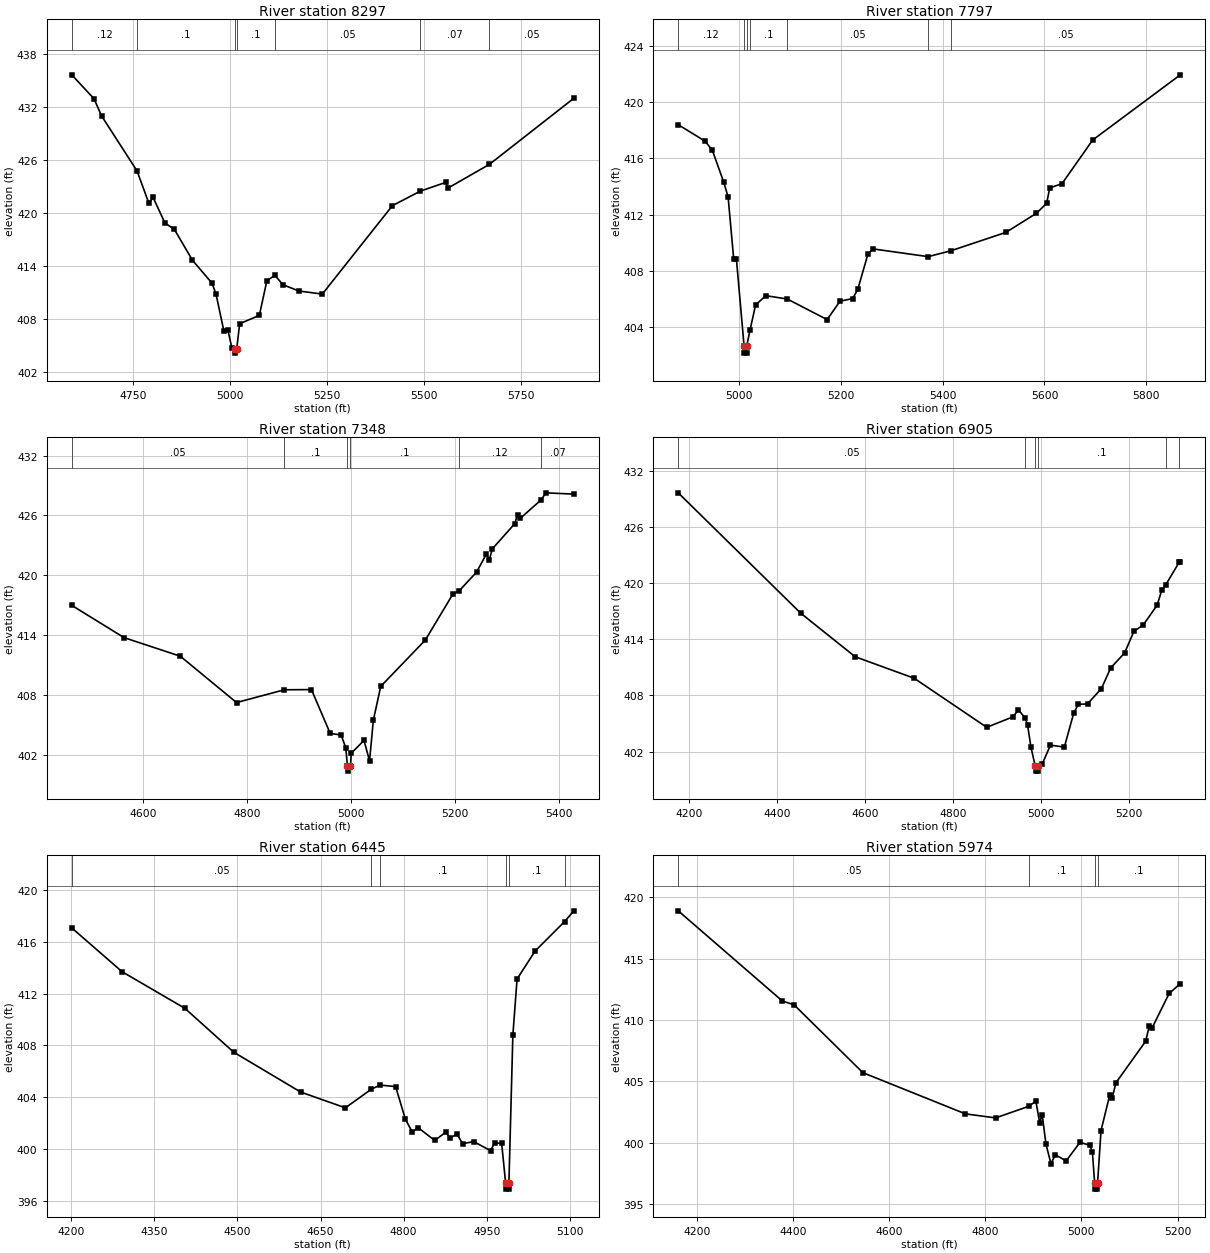
Type RM Length L Ch R = 1,8297,500,500,500
BEGIN DESCRIPTION:
E21030
END DESCRIPTION:
XS GIS Cut Line= 3
      2447621.61     13800343.33      2446956.69     13800232.51
      2446338.05     13800206.00
#Sta/Elev= 30
  4592.9  435.65  4650.3  432.94  4669.7  431.00  4761.0  424.78  4791.4  421.14
  4802.4  421.78  4832.8  418.90  4857.3  418.16  4903.7  414.68  4954.4  412.07
  4964.6  410.82  4984.8  406.65  4995.0  406.80  5005.1  404.79  5012.7  404.67
  5013.1  404.17  5017.8  404.67  5025.4  407.50  5076.1  408.44  5095.5  412.37
  5116.3  412.96  5136.9  411.91  5177.5  411.20  5238.3  410.85  5418.8  420.85
  5490.6  422.49  5556.6  423.49  5561.6  422.83  5668.9  425.53  5886.2  433.00
#Mann=7,-1,0
  4592.9    0.12       0  4761.0     0.1       0  5012.7    0.05       0
  5017.8     0.1       0  5116.3    0.05       0  5490.6    0.07       0
  5668.9    0.05       0
Bank Sta=5012.7,5017.8
Exp/Cntr=0.3,0.1

Type RM Length L Ch R = 1,7797,449,449,449
BEGIN DESCRIPTION:
Stream0424 14.0
END DESCRIPTION:
XS GIS Cut Line= 3
      2447525.02     13799925.01      2447425.00     13799875.00
      2446553.34     13799811.42
#Sta/Elev= 30
  4880.9  418.40  4934.0  417.22  4948.0  416.57  4970.4  414.30  4978.8  413.27
  4989.9  408.83  4995.2  408.83  5010.2  402.68  5010.6  402.18  5015.0  402.18
  5015.3  402.68  5021.7  403.79  5032.8  405.60  5052.9  406.26  5095.2  406.02
  5173.2  404.56  5198.6  405.87  5223.3  406.05  5233.4  406.70  5253.4  409.22
  5263.4  409.58  5371.5  409.03  5415.6  409.44  5524.1  410.75  5584.3  412.11
  5604.3  412.82  5610.3  413.91  5634.4  414.21  5694.6  417.31  5866.7  421.94
#Mann=7,-1,0
  4880.9    0.12       0  5010.2    0.05       0  5015.3    0.12       0
  5021.7     0.1       0  5095.2    0.05       0  5371.5    0.07       0
  5415.6    0.05       0
Bank Sta=5010.2,5015.3
Exp/Cntr=0.3,0.1

Type RM Length L Ch R = 1,7348,443,443,443
BEGIN DESCRIPTION:
Stream0424 13.0
END DESCRIPTION:
XS GIS Cut Line= 3
      2447675.02     13799825.01      2447225.00     13799525.00
      2447070.78     13799128.70
#Sta/Elev= 30
  4463.1  416.98  4563.8  413.74  4671.9  411.88  4780.1  407.23  4872.0  408.51
  4924.3  408.53  4960.4  404.13  4981.4  403.98  4990.4  402.68  4993.5  400.85
  4994.0  400.35  4999.4  400.85  5000.9  402.15  5025.4  403.43  5036.1  401.38
  5043.4  405.46  5057.6  408.85  5143.4  413.50  5197.1  418.17  5207.9  418.40
  5241.9  420.31  5261.0  422.13  5266.4  421.50  5272.2  422.64  5315.1  425.15
  5320.8  426.03  5326.1  425.71  5366.4  427.57  5375.2  428.27  5429.2  428.14
#Mann=6,-1,0
  4463.1    0.05       0  4872.0     0.1       0  4993.5    0.05       0
  4999.4     0.1       0  5207.9    0.12       0  5366.4    0.07       0
Bank Sta=4993.5,4999.4
Exp/Cntr=0.3,0.1

Type RM Length L Ch R = 1,6905,460,460,460
BEGIN DESCRIPTION:
Stream0424 12.0
END DESCRIPTION:
XS GIS Cut Line= 3
      2447774.99     13800074.96      2447575.00     13799275.00
      2447275.01     13799175.00
#Sta/Elev= 30
  4175.7  429.68  4454.0  416.80  4577.7  412.14  4711.7  409.84  4876.6  404.59
  4935.9  405.70  4948.7  406.45  4963.9  405.59  4969.4  404.84  4977.1  402.48
  4987.0  400.40  4987.5  399.90  4992.4  399.90  4992.9  400.40  5002.9  400.68
  5021.4  402.68  5053.0  402.47  5074.1  406.07  5084.6  407.05  5105.7  407.09
  5137.3  408.74  5158.4  410.95  5190.0  412.55  5211.1  414.87  5232.2  415.53
  5263.8  417.66  5274.3  419.25  5282.9  419.79  5314.3  422.28  5316.5  422.28
#Mann=6,-1,0
  4175.7    0.05       0  4963.9     0.1       0  4987.0    0.05       0
  4992.9     0.1       0  5282.9    0.12       0  5314.3    0.07       0
Bank Sta=4987,4992.9
Exp/Cntr=0.3,0.1

Type RM Length L Ch R = 1,6445,471,471,471
BEGIN DESCRIPTION:
Stream0424 11.0
END DESCRIPTION:
XS GIS Cut Line= 3
      2447875.01     13799725.05      2447775.00     13798925.00
      2447775.00     13798824.97
#Sta/Elev= 30
  4200.9  417.08  4291.6  413.70  4405.0  410.87  4493.2  407.48  4614.1  404.40
  4694.8  403.18  4741.3  404.61  4757.3  404.94  4785.5  404.82  4803.1  402.30
  4815.7  401.30  4825.8  401.66  4856.0  400.66  4876.2  401.30  4883.7  400.84
  4896.3  401.16  4906.4  400.41  4926.6  400.57  4956.8  399.87  4964.3  400.47
  4976.9  400.43  4984.0  397.40  4984.5  396.90  4989.5  396.90  4990.0  397.40
  4997.1  408.79  5004.7  413.13  5037.2  415.29  5090.5  417.57  5107.2  418.40
#Mann=6,-1,0
  4200.9    0.05       0  4741.3    0.07       0  4757.3     0.1       0
  4984.0    0.05       0  4990.0     0.1       0  5090.5    0.12       0
Bank Sta=4984,4990
Exp/Cntr=0.3,0.1

Type RM Length L Ch R = 1,5974,466,466,466
BEGIN DESCRIPTION:
Stream0424 10.0
END DESCRIPTION:
XS GIS Cut Line= 3
      2447924.99     13799775.03      2448175.00     13798975.00
      2448125.01     13798775.04
#Sta/Elev= 30
  4161.4  418.90  4377.8  411.55  4402.4  411.23  4545.4  405.70  4758.6  402.34
  4821.5  402.01  4890.0  402.95  4905.3  403.37  4913.1  401.63  4918.4  402.27
  4926.2  399.89  4936.7  398.26  4945.6  399.01  4968.2  398.50  4997.0  400.01
  5017.6  399.78  5022.8  399.25  5027.5  396.70  5028.0  396.20  5033.1  396.20
  5033.6  396.70  5040.8  400.98  5058.9  403.87  5064.0  403.64  5071.7  404.87
  5133.6  408.26  5141.3  409.53  5146.5  409.31  5182.5  412.16  5205.7  412.96
#Mann=4,-1,0
  4161.4    0.05       0  4890.0     0.1       0  5027.5    0.05       0
  5033.6     0.1       0
Bank Sta=5027.5,5033.6
Exp/Cntr=0.3,0.1

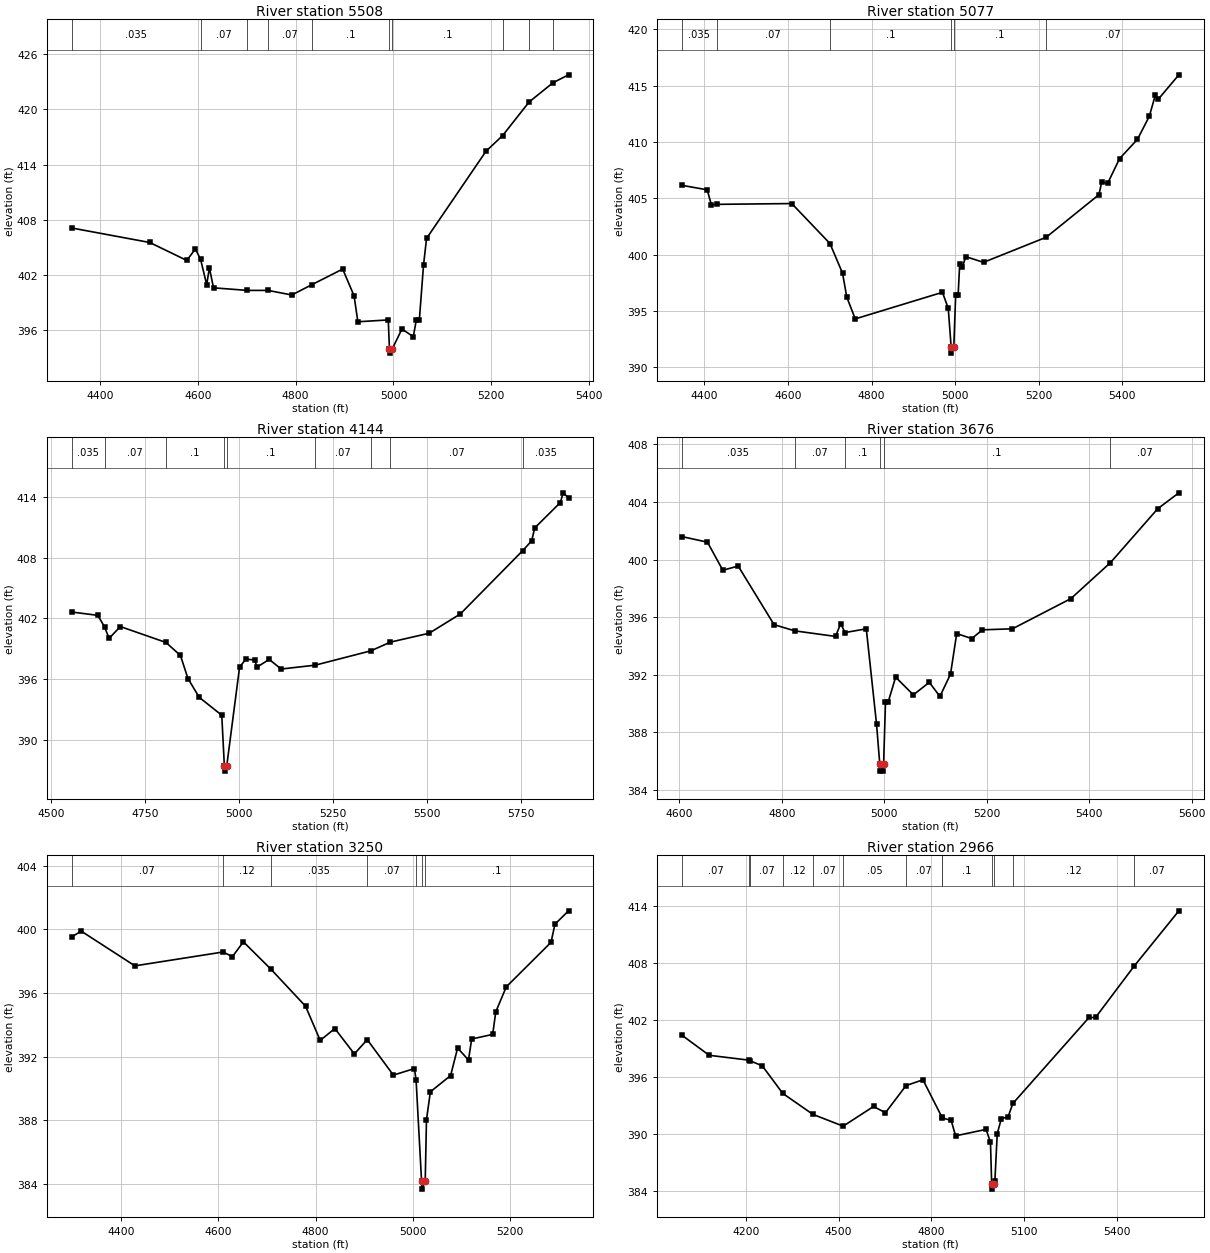
Type RM Length L Ch R = 1,5508,431,431,431
BEGIN DESCRIPTION:
Stream0424 9.0
END DESCRIPTION:
XS GIS Cut Line= 3
      2448742.83     13799380.58      2448475.00     13798775.00
      2448269.27     13798486.51
#Sta/Elev= 30
  4341.6  407.12  4501.6  405.54  4577.3  403.59  4594.8  404.83  4605.5  403.73
  4618.1  400.94  4623.5  402.79  4632.0  400.61  4701.1  400.33  4743.7  400.33
  4792.1  399.83  4833.4  400.96  4896.2  402.65  4919.5  399.73  4927.2  396.92
  4989.4  397.12  4991.8  394.01  4992.3  393.51  4998.0  394.01  5017.3  396.13
  5040.6  395.30  5046.8  397.13  5052.9  397.08  5061.5  403.08  5067.7  405.98
  5189.4  415.47  5223.2  417.16  5277.3  420.81  5326.3  422.91  5358.1  423.77
#Mann=10,-1,0
  4341.6   0.035       0  4605.5    0.07       0  4701.1    0.05       0
  4743.7    0.07       0  4833.4     0.1       0  4991.8    0.05       0
  4998.0     0.1       0  5223.2    0.07       0  5277.3     0.1       0
  5326.3    0.07       0
Bank Sta=4991.8,4998
Exp/Cntr=0.3,0.1

Type RM Length L Ch R = 1,5077,933,933,933
BEGIN DESCRIPTION:
Stream0424 8.0
END DESCRIPTION:
XS GIS Cut Line= 3
      2448775.00     13799324.98      2448875.00     13798675.00
      2448525.02     13798275.03
#Sta/Elev= 30
  4346.1  406.16  4406.8  405.76  4416.9  404.41  4429.3  404.47  4609.1  404.54
  4700.5  400.99  4730.6  398.35  4740.7  396.24  4760.9  394.30  4969.6  396.66
  4983.5  395.23  4990.5  391.76  4991.0  391.26  4996.7  391.76  5001.2  396.40
  5007.1  396.40  5010.8  399.13  5017.5  398.89  5025.1  399.83  5067.8  399.32
  5217.9  401.55  5344.0  405.33  5350.6  406.45  5364.9  406.34  5393.3  408.53
  5436.1  410.24  5464.5  412.29  5478.8  414.16  5485.4  413.78  5535.2  415.97
#Mann=6,-1,0
  4346.1   0.035       0  4429.3    0.07       0  4700.5     0.1       0
  4990.5    0.05       0  4996.7     0.1       0  5217.9    0.07       0
Bank Sta=4990.5,4996.7
Exp/Cntr=0.3,0.1

Type RM Length L Ch R = 1,4144,468,468,468
BEGIN DESCRIPTION:
Stream0424 7.0
END DESCRIPTION:
XS GIS Cut Line= 3
      2449375.00     13799025.03      2449375.00     13798575.00
      2448575.04     13798225.02
#Sta/Elev= 30
  4554.3  402.63  4624.3  402.30  4642.2  401.16  4654.3  400.02  4684.3  401.19
  4805.7  399.62  4844.3  398.33  4864.3  396.05  4894.3  394.19  4954.3  392.42
  4961.2  387.39  4961.7  386.89  4967.5  387.39  5001.8  397.21  5018.8  397.96
  5042.1  397.89  5048.0  397.18  5080.7  397.94  5112.3  396.99  5202.9  397.37
  5351.2  398.79  5403.2  399.65  5506.4  400.53  5589.5  402.44  5755.7  408.71
  5779.3  409.67  5787.5  410.95  5855.7  413.46  5863.1  414.42  5877.5  413.92
#Mann=9,-1,0
  4554.3   0.035       0  4642.2    0.07       0  4805.7     0.1       0
  4961.2    0.05       0  4967.5     0.1       0  5202.9    0.07       0
  5351.2   0.035       0  5403.2    0.07       0  5755.7   0.035       0
Bank Sta=4961.2,4967.5
Exp/Cntr=0.3,0.1

Type RM Length L Ch R = 1,3676,426,426,426
BEGIN DESCRIPTION:
Stream0424 6.0
END DESCRIPTION:
XS GIS Cut Line= 3
      2449775.00     13798775.04      2449775.00     13798375.00
      2449625.01     13797825.02
#Sta/Elev= 30
  4605.0  401.60  4655.0  401.21  4685.0  399.26  4715.0  399.55  4785.0  395.48
  4825.2  395.05  4905.0  394.66  4915.0  395.55  4923.6  394.93  4965.0  395.19
  4985.0  388.58  4991.3  385.80  4991.8  385.30  4998.3  385.30  4998.8  385.80
  5002.5  390.09  5007.6  390.09  5022.3  391.83  5056.9  390.60  5088.0  391.47
  5108.7  390.49  5129.4  392.04  5141.5  394.86  5170.9  394.51  5191.6  395.12
  5250.3  395.19  5364.4  397.29  5441.6  399.79  5533.7  403.53  5575.1  404.64
#Mann=6,-1,0
  4605.0   0.035       0  4825.2    0.07       0  4923.6     0.1       0
  4991.3    0.05       0  4998.8     0.1       0  5441.6    0.07       0
Bank Sta=4991.3,4998.8
Exp/Cntr=0.3,0.1

Type RM Length L Ch R = 1,3250,284,284,284
BEGIN DESCRIPTION:
Stream0424 5.0
END DESCRIPTION:
XS GIS Cut Line= 3
      2450075.00     13798775.01      2450025.00     13798075.00
      2449825.03     13797825.04
#Sta/Elev= 30
  4298.2  399.53  4318.3  399.89  4428.5  397.71  4609.6  398.58  4629.0  398.29
  4651.6  399.22  4708.5  397.49  4779.4  395.17  4809.5  393.02  4839.6  393.77
  4879.7  392.17  4906.2  393.07  4959.9  390.84  5003.2  391.25  5006.6  390.55
  5017.9  384.17  5018.4  383.67  5025.4  384.17  5028.0  388.03  5036.0  389.79
  5077.6  390.81  5092.0  392.54  5114.4  391.79  5120.9  393.11  5164.1  393.40
  5170.5  394.82  5192.1  396.39  5284.1  399.19  5292.1  400.33  5320.1  401.17
#Mann=7,-1,0
  4298.2    0.07       0  4609.6    0.12       0  4708.5   0.035       0
  4906.2    0.07       0  5006.6     0.1       0  5017.9    0.05       0
  5025.4     0.1       0
Bank Sta=5017.9,5025.4
Exp/Cntr=0.3,0.1

Type RM Length L Ch R = 1,2966,622,622,622
BEGIN DESCRIPTION:
Stream0424 4.0
END DESCRIPTION:
XS GIS Cut Line= 3
      2450125.01     13798774.97      2450344.06     13798028.98
      2449798.45     13797401.36
#Sta/Elev= 30
  3992.8  400.37  4081.4  398.25  4209.9  397.74  4213.8  397.67  4253.3  397.14
  4319.4  394.24  4417.1  392.03  4515.1  390.79  4613.4  392.86  4652.0  392.20
  4718.5  395.06  4773.4  395.67  4833.8  391.80  4836.0  391.66  4864.8  391.39
  4879.0  389.77  4977.8  390.45  4992.0  389.08  4995.9  384.66  4996.4  384.16
  5003.4  384.66  5006.3  385.04  5013.9  390.01  5027.3  391.58  5049.0  391.77
  5064.5  393.18  5311.1  402.23  5332.1  402.23  5456.4  407.61  5601.9  413.46
#Mann=13,-1,0
  3992.8    0.07       0  4209.9    0.12       0  4213.8    0.07       0
  4319.4    0.12       0  4417.1    0.07       0  4515.1    0.05       0
  4718.5    0.07       0  4833.8   0.035       0  4836.0     0.1       0
  4995.9    0.05       0  5003.4     0.1       0  5064.5    0.12       0
  5456.4    0.07       0
Bank Sta=4995.9,5003.4
Exp/Cntr=0.3,0.1

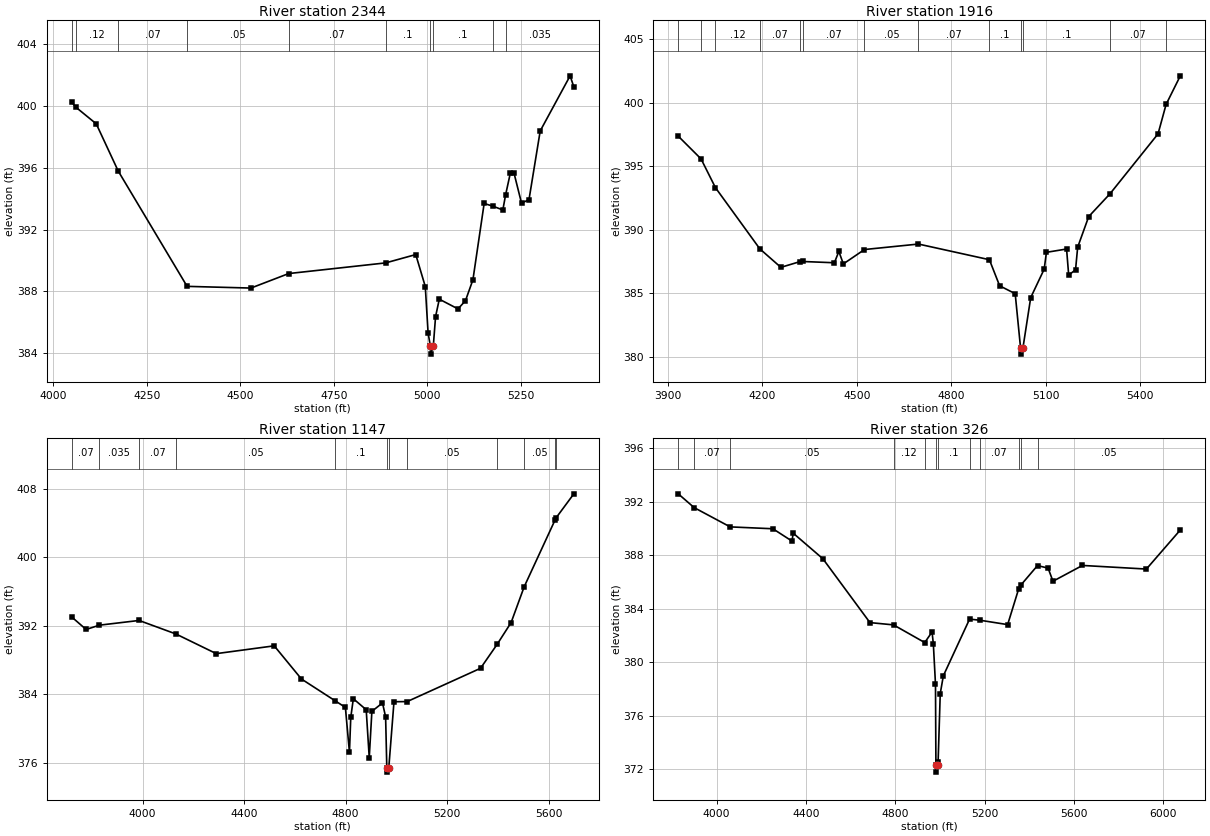
Type RM Length L Ch R = 1,2344,428,428,428
BEGIN DESCRIPTION:
Stream0424 3.0
END DESCRIPTION:
XS GIS Cut Line= 3
      2450224.98     13798675.03      2450725.00     13797875.00
      2450725.00     13797475.04
#Sta/Elev= 30
  4049.0  400.26  4059.3  399.94  4114.5  398.85  4173.3  395.79  4357.6  388.32
  4528.4  388.21  4629.4  389.15  4888.7  389.84  4969.4  390.38  4994.9  388.31
  5002.4  385.31  5008.6  384.43  5009.1  383.93  5016.3  384.43  5022.4  386.36
  5032.4  387.49  5082.4  386.86  5102.4  387.39  5122.4  388.75  5152.4  393.69
  5175.3  393.52  5202.4  393.27  5209.9  394.26  5222.4  395.65  5232.4  395.65
  5252.4  393.71  5272.4  393.94  5302.4  398.39  5382.4  401.96  5392.4  401.24
#Mann=10,-1,0
  4049.0    0.07       0  4059.3    0.12       0  4173.3    0.07       0
  4357.6    0.05       0  4629.4    0.07       0  4888.7     0.1       0
  5008.6    0.05       0  5016.3     0.1       0  5175.3    0.07       0
  5209.9   0.035       0
Bank Sta=5008.6,5016.3
Exp/Cntr=0.3,0.1

Type RM Length L Ch R = 1,1916,769,769,769
BEGIN DESCRIPTION:
Stream0424 2.0
END DESCRIPTION:
XS GIS Cut Line= 3
      2450425.03     13798674.96      2451125.00     13797875.00
      2450774.98     13797474.98
#Sta/Elev= 30
  3932.6  397.36  4005.1  395.57  4050.8  393.31  4191.8  388.50  4258.6  387.05
  4319.4  387.50  4327.4  387.51  4428.5  387.41  4442.7  388.30  4456.9  387.32
  4524.1  388.45  4695.5  388.88  4920.8  387.65  4953.3  385.60  5002.7  384.98
  5019.7  380.73  5020.2  380.23  5027.4  380.73  5052.0  384.67  5094.8  386.91
  5101.9  388.23  5165.9  388.49  5172.6  386.44  5194.4  386.86  5201.1  388.63
  5236.2  391.04  5303.8  392.83  5456.4  397.54  5481.9  399.85  5527.1  402.10
#Mann=13,-1,0
  3932.6    0.12       0  4005.1    0.07       0  4050.8    0.12       0
  4191.8    0.07       0  4319.4    0.12       0  4327.4    0.07       0
  4524.1    0.05       0  4695.5    0.07       0  4920.8     0.1       0
  5019.7    0.05       0  5027.4     0.1       0  5303.8    0.07       0
  5481.9   0.035       0
Bank Sta=5019.7,5027.4
Exp/Cntr=0.3,0.1

Type RM Length L Ch R = 1,1147,821,821,821
BEGIN DESCRIPTION:
XS6769
END DESCRIPTION:
XS GIS Cut Line= 4
      2450868.27     13798506.87      2451599.36     13797943.40
      2451488.81     13797576.07      2450954.22     13797169.78
#Sta/Elev= 30
  3721.1  393.01  3777.6  391.56  3830.1  392.06  3986.3  392.61  4130.9  391.04
  4290.4  388.74  4518.7  389.65  4626.0  385.78  4758.8  383.24  4799.1  382.47
  4815.1  377.23  4820.3  381.30  4830.4  383.48  4881.1  382.20  4893.1  376.60
  4903.5  382.01  4945.3  382.99  4957.6  381.36  4962.3  375.42  4962.8  374.92
  4970.1  375.42  4990.6  383.13  5042.6  383.15  5331.5  387.03  5397.1  389.83
  5452.1  392.37  5503.4  396.53  5624.4  404.28  5628.8  404.56  5699.2  407.38
#Mann=12,-1,0
  3721.1    0.07       0  3830.1   0.035       0  3986.3    0.07       0
  4130.9    0.05       0  4758.8     0.1       0  4962.3    0.05       0
  4970.1     0.1       0  5042.6    0.05       0  5397.1    0.07       0
  5503.4    0.05       0  5624.4   0.035       0  5628.8    0.07       0
Bank Sta=4962.3,4970.1
Exp/Cntr=0.3,0.1

Type RM Length L Ch R = 1,326,0,0,0
BEGIN DESCRIPTION:
Stream0424 1.0
END DESCRIPTION:
XS GIS Cut Line= 4
      2451060.82     13798396.33      2451588.67     13798150.24
      2452038.01     13797419.16      2451624.98     13796724.96
#Sta/Elev= 30
  3828.2  392.58  3899.5  391.55  4060.8  390.11  4252.1  389.97  4337.5  389.05
  4343.0  389.64  4475.9  387.73  4686.7  382.96  4792.2  382.79  4932.0  381.47
  4964.8  382.26  4970.6  381.37  4980.2  378.35  4982.1  372.29  4982.6  371.79
  4989.9  372.29  4991.9  372.56  5001.5  377.66  5015.4  378.99  5132.8  383.22
  5178.2  383.14  5303.3  382.81  5353.0  385.50  5362.3  385.76  5437.0  387.22
  5484.4  387.03  5506.3  386.05  5638.3  387.23  5924.6  386.96  6076.5  389.88
#Mann=12,-1,0
  3828.2   0.035       0  3899.5    0.07       0  4060.8    0.05       0
  4792.2    0.12       0  4932.0     0.1       0  4982.1    0.05       0
  4989.9     0.1       0  5132.8    0.05       0  5178.2    0.07       0
  5353.0    0.05       0  5362.3    0.07       0  5437.0    0.05       0
Bank Sta=4982.1,4989.9
Exp/Cntr=0.3,0.1

Chan Stop Cuts=-1