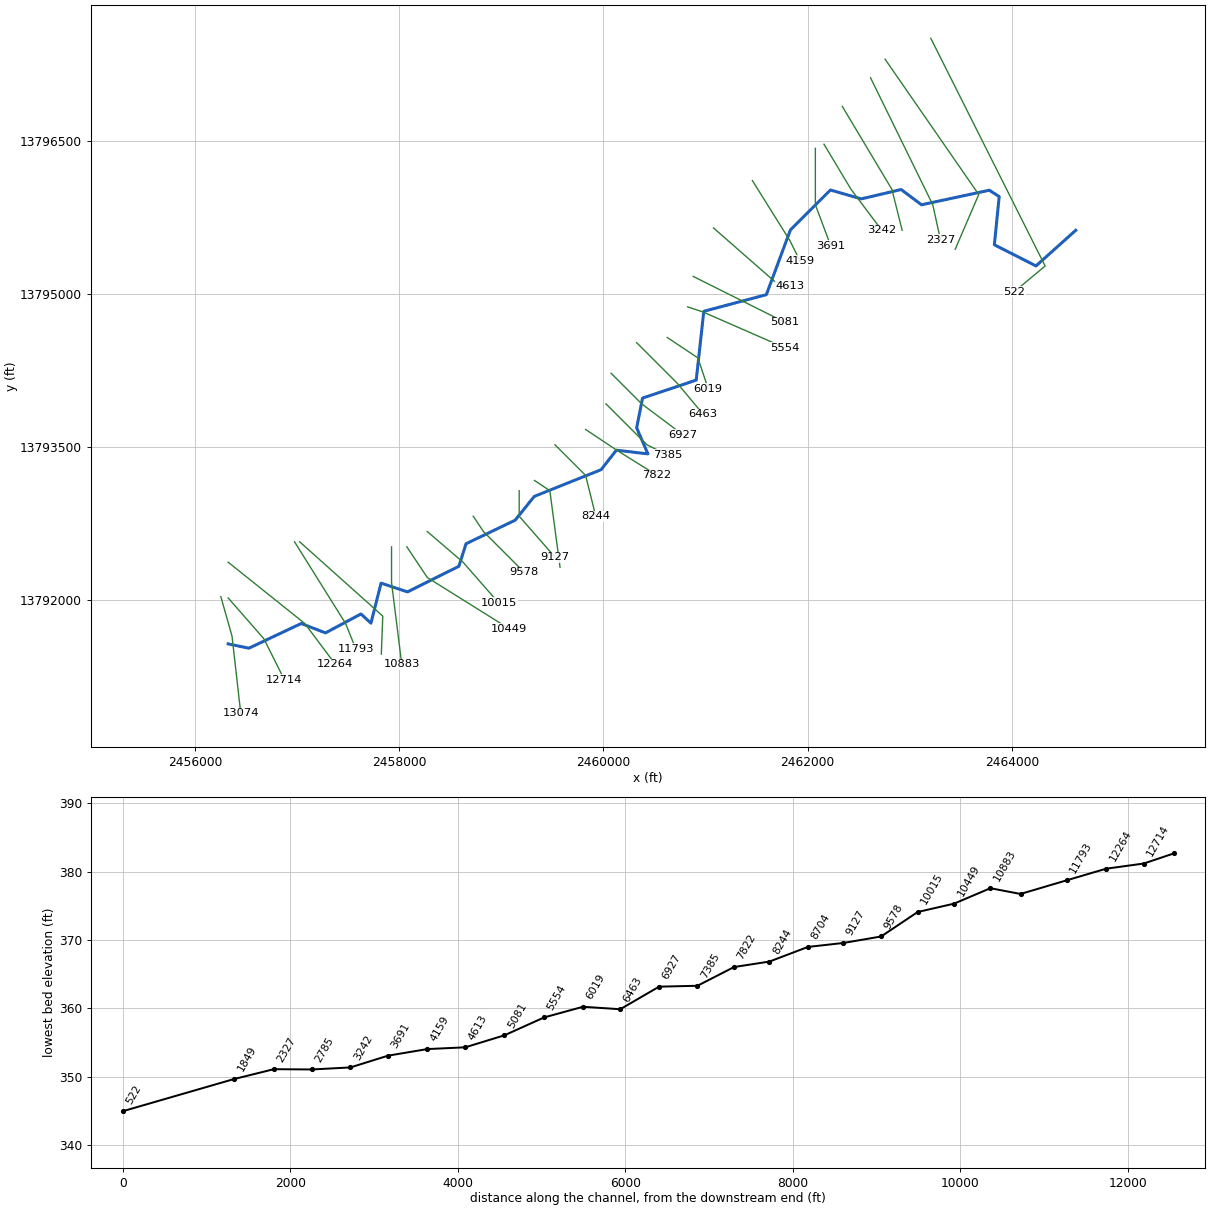
--- Stream0427.prj (project) ---

Proj Title=Stream0427 Base Level Engineering
Current Plan=p01
Default Exp/Contr=0.3,0.1
English Units
Geom File=g01
Flow File=f01
Plan File=p01
Y Axis Title=Elevation
X Axis Title(PF)=Main Channel Distance
X Axis Title(XS)=Station
BEGIN DESCRIPTION:
Stream0427
END DESCRIPTION:
DSS Export Rating Curves= 0
DSS Export Rating Curve Sorted= 0
DSS Export Volume Flow Curves= 0
DXF OffsetX= 0
DXF OffsetY= 0
DXF ScaleX= 1
DXF ScaleY= 10

--- Stream0427.p01 (plan) ---

Plan Title=Multiple Run
Short Identifier=Multiple
Geom File=g01
Flow File=f01
Subcritical Flow
K Sum by GR= 0
Std Step Tol= 0.01
Critical Tol= 0.01
Num of Std Step Trials= 20
Max Error Tol= 0.3
Flow Tol Ratio= 0.001
Split Flow NTrial= 30
Split Flow Tol= 0.02
Split Flow Ratio= 0.02
Log Output Level= 0
Friction Slope Method= 1
Unsteady Friction Slope Method= 2
Unsteady Bridges Friction Slope Method= 1
Parabolic Critical Depth
Global Vel Dist=  1 , 1 , 1
Global Log Level= 0
CheckData=True
Encroach Param= -1, 0, 0, 0
BEGIN DESCRIPTION:
Multiple Run
END DESCRIPTION:

--- Stream0427.f01 (steady flow) ---

Flow Title=Multiple
Number of Profiles=7
Profile Names=10-year,25-year,50-year,1pct_min,100-year,1pct_plu,500-year
River Rch & RM= Stream0427,Reach-1,13074
     834    1356    1832    1197    2389    4767    4024
River Rch & RM= Stream0427,Reach-1,10449
    1218    2020    2764    1828    3648    7278    6293
River Rch & RM= Stream0427,Reach-1,9127
    1473    2457    3375    2237    4464    8908    7744
Boundary for River Rch & Prof#=Stream0427,Reach-1,1
Up Type=0
Dn Type=3
Dn Slope=0.005
Boundary for River Rch & Prof#=Stream0427,Reach-1,2
Up Type=0
Dn Type=3
Dn Slope=0.005
Boundary for River Rch & Prof#=Stream0427,Reach-1,3
Up Type=0
Dn Type=3
Dn Slope=0.005
Boundary for River Rch & Prof#=Stream0427,Reach-1,4
Up Type=0
Dn Type=3
Dn Slope=0.005
Boundary for River Rch & Prof#=Stream0427,Reach-1,5
Up Type=0
Dn Type=3
Dn Slope=0.005
Boundary for River Rch & Prof#=Stream0427,Reach-1,6
Up Type=0
Dn Type=3
Dn Slope=0.005
Boundary for River Rch & Prof#=Stream0427,Reach-1,7
Up Type=0
Dn Type=3
Dn Slope=0.005

--- Stream0427.g01 (geometry) ---

Geom Title=Existing Conditions
Program Version=4.10

River Reach=Stream0427      ,Reach-1
Reach XY= 30
        2456325.       13791575.       2456528.4     13791532.83
      2457040.22     13791774.51      2457278.33     13791682.61
      2457625.21     13791867.97      2457723.27     13791777.86
      2457822.29     13792169.72      2458081.61     13792084.39
      2458584.72      13792335.2      2458654.32     13792555.37
      2459135.07     13792786.11      2459322.69     13793019.18
      2459977.31     13793280.83      2460126.28     13793471.63
      2460435.54     13793435.46      2460325.25     13793690.22
      2460382.68     13793981.52      2460908.58      13794158.2
      2460982.68     13794831.53      2461595.13     13794994.41
      2461830.45     13795627.47      2462222.71     13796019.19
      2462524.92      13795932.3      2462914.57     13796023.95
      2463114.79      13795874.5      2463778.35       13796017.
      2463874.98     13795954.83      2463827.91     13795482.91
      2464235.49     13795275.93        2464625.       13795625.

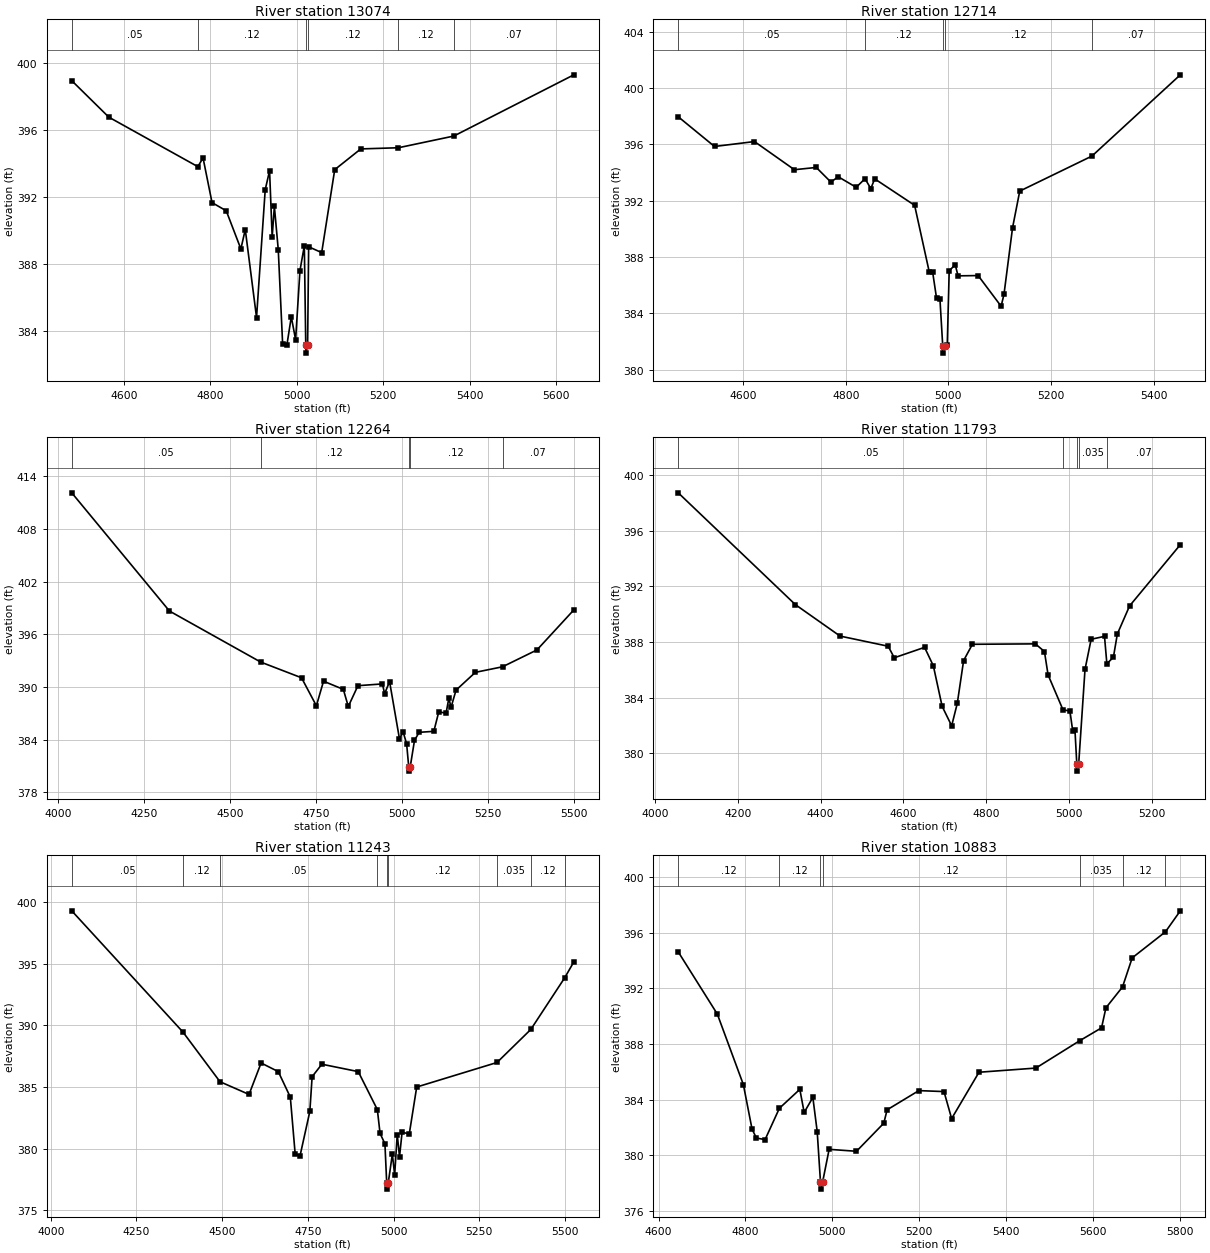
Type RM Length L Ch R = 1 ,13074   ,360,360,360
BEGIN DESCRIPTION:
XS6774
END DESCRIPTION:
XS GIS Cut Line= 3
      2456253.24     13792037.55      2456362.77     13791651.83
      2456448.49     13790894.63
#Sta/Elev= 30
  4478.7  398.94  4564.5  396.76  4770.7   393.8  4782.8  394.32  4803.6  391.65
  4836.5  391.16  4870.4  388.88  4880.6  390.04  4906.7  384.78  4926.8  392.42
  4936.9  393.56  4942.9  389.59    4948  391.42    4957  388.84  4967.1  383.22
  4977.1  383.15  4987.2  384.82  4997.2  383.45  5007.3  387.59  5017.4  389.07
  5020.7  383.15    5021  382.65    5025  383.15  5027.4  389.01  5057.6  388.66
  5087.8  393.62  5148.2  394.86  5235.3  394.93  5363.7  395.63  5641.7  399.29
#Mann= 6 ,-1 , 0
  4478.7     .05       0  4770.7     .12       0  5020.7     .05       0
    5025     .12       0  5235.3     .12       0  5363.7     .07       0
Bank Sta=5020.7,5025
XS Rating Curve= 0 ,0
Exp/Cntr=0.3,0.1

Type RM Length L Ch R = 1 ,12714   ,450,450,450
BEGIN DESCRIPTION:
Stream0427 26.0
END DESCRIPTION:
XS GIS Cut Line= 3
      2456324.98     13792025.02        2456675.       13791625.
      2456874.98     13791225.04
#Sta/Elev= 30
  4473.4  397.96  4544.1  395.85    4622   396.2  4699.8   394.2  4742.5  394.36
    4771  393.32  4785.2   393.7  4820.3  392.95  4837.5  393.56  4848.8  392.86
  4856.4  393.55  4934.2  391.67  4962.7  386.94  4969.3  386.93  4976.9  385.08
  4983.6  384.98    4989  381.67  4989.3  381.17  4993.4  381.67  4997.8  381.74
  5001.6  387.02  5013.3  387.45  5018.9  386.66    5058  386.68  5102.8   384.5
  5108.4  385.35  5125.1  390.08  5139.1  392.68  5279.9  395.17  5452.1  400.94
#Mann= 5 ,-1 , 0
  4473.4     .05       0  4837.5     .12       0    4989     .05       0
  4993.4     .12       0  5279.9     .07       0
Bank Sta=4989,4993.4
XS Rating Curve= 0 ,0
Exp/Cntr=0.3,0.1

Type RM Length L Ch R = 1 ,12264   ,471,471,471
BEGIN DESCRIPTION:
Stream0427 25.0
END DESCRIPTION:
XS GIS Cut Line= 3
      2456325.03     13792374.97        2457075.       13791775.
      2457374.98     13791375.02
#Sta/Elev= 30
  4040.3   412.1  4324.4  398.64  4589.8  392.83  4708.6  391.04  4751.8  387.85
  4772.6  390.65  4830.2  389.72  4844.6  387.77  4872.7  390.14  4943.9  390.34
  4950.3  389.22  4964.7  390.61  4993.5  384.08  5003.9  384.91  5014.3  383.52
  5020.4  380.91  5020.7  380.41  5024.8  380.91  5037.2  383.91  5050.7  384.83
  5093.4  384.94    5108  387.19  5128.9  386.98  5137.2  388.73  5143.4  387.66
    5158  389.63  5214.3  391.66  5293.2  392.29  5393.4  394.21  5500.7  398.77
#Mann= 5 ,-1 , 0
  4040.3     .05       0  4589.8     .12       0  5020.4     .05       0
  5024.8     .12       0  5293.2     .07       0
Bank Sta=5020.4,5024.8
XS Rating Curve= 0 ,0
Exp/Cntr=0.3,0.1

Type RM Length L Ch R = 1 ,11793   ,550,550,550
BEGIN DESCRIPTION:
Stream0427 24.0
END DESCRIPTION:
XS GIS Cut Line= 3
      2456974.98     13792575.02        2457475.       13791775.
      2457575.01     13791524.99
#Sta/Elev= 30
  4056.2  398.72  4339.2  390.68  4447.1  388.42  4563.3  387.69    4578  386.86
  4651.2  387.61  4672.4  386.28  4693.6  383.37  4716.6  381.97  4730.2  383.58
  4745.5  386.66  4766.7  387.83  4918.8  387.86  4940.7  387.31  4949.5  385.63
  4985.5  383.12  5002.3  383.03  5009.1  381.58  5014.4  381.68  5018.9  379.21
  5019.2  378.71  5023.4  379.21  5038.7  386.02  5053.5  388.19  5085.8   388.4
  5091.5  386.43  5107.3   386.9  5116.8  388.57  5146.4  390.59  5268.9  394.99
#Mann= 5 ,-1 , 0
  4056.2     .05       0  4985.5    .035       0  5018.9    .035       0
  5023.4    .035       0  5091.5     .07       0
Bank Sta=5018.9,5023.4
XS Rating Curve= 0 ,0
Exp/Cntr=0.3,0.1

Type RM Length L Ch R = 1 ,11243   ,360,360,360
BEGIN DESCRIPTION:
Stream0427 23.0
END DESCRIPTION:
XS GIS Cut Line= 3
      2457024.98     13792575.01      2457838.98     13791847.07
        2457825.     13791475.05
#Sta/Elev= 30
  4061.4  399.29  4385.9  389.45  4493.7  385.43  4578.4   384.4  4613.6  386.95
  4663.7  386.25  4698.8  384.18    4713  379.55  4727.2  379.43  4755.7  383.02
  4762.4  385.84  4790.8  386.85  4896.9  386.25  4952.6  383.17  4960.5  381.24
  4974.7   380.4  4979.9  377.22  4980.2  376.72  4984.4  377.22  4996.4  379.56
  5003.1  377.86  5010.6  381.15  5017.3  379.35  5024.8  381.34  5045.7  381.19
  5067.4     385  5301.6  386.99  5400.2  389.67  5498.8  393.85  5525.7  395.15
#Mann= 9 ,-1 , 0
  4061.4     .05       0  4385.9     .12       0  4493.7     .05       0
  4952.6     .12       0  4979.9     .05       0  4984.4     .12       0
  5301.6    .035       0  5400.2     .12       0  5498.8     .12       0
Bank Sta=4979.9,4984.4
XS Rating Curve= 0 ,0
Exp/Cntr=0.3,0.1

Type RM Length L Ch R = 1 ,10883   ,434,434,434
BEGIN DESCRIPTION:
Stream0427 22.0
END DESCRIPTION:
XS GIS Cut Line= 3
        2457925.     13792524.99        2457925.       13792175.
        2458025.     13791375.01
#Sta/Elev= 30
  4645.2  394.61  4735.2  390.14  4795.2  385.07  4815.2  381.87  4825.2  381.23
  4845.2  381.12  4878.1  383.37  4925.2  384.73  4935.2  383.07  4955.2  384.15
  4965.2   381.7  4972.8  378.06  4973.1  377.56  4977.6  378.06  4992.7  380.42
  5055.7  380.28  5118.6   382.3  5126.2  383.26  5199.3  384.64  5257.2  384.57
  5274.8  382.63  5337.8  385.96  5468.8  386.26  5569.4  388.22    5620  389.15
  5630.1  390.59  5668.3  392.09  5690.6  394.18  5767.1  396.05  5801.4  397.56
#Mann= 7 ,-1 , 0
  4645.2     .12       0  4878.1     .12       0  4972.8     .05       0
  4977.6     .12       0  5569.4    .035       0  5668.3     .12       0
  5767.1     .12       0
Bank Sta=4972.8,4977.6
XS Rating Curve= 0 ,0
Exp/Cntr=0.3,0.1

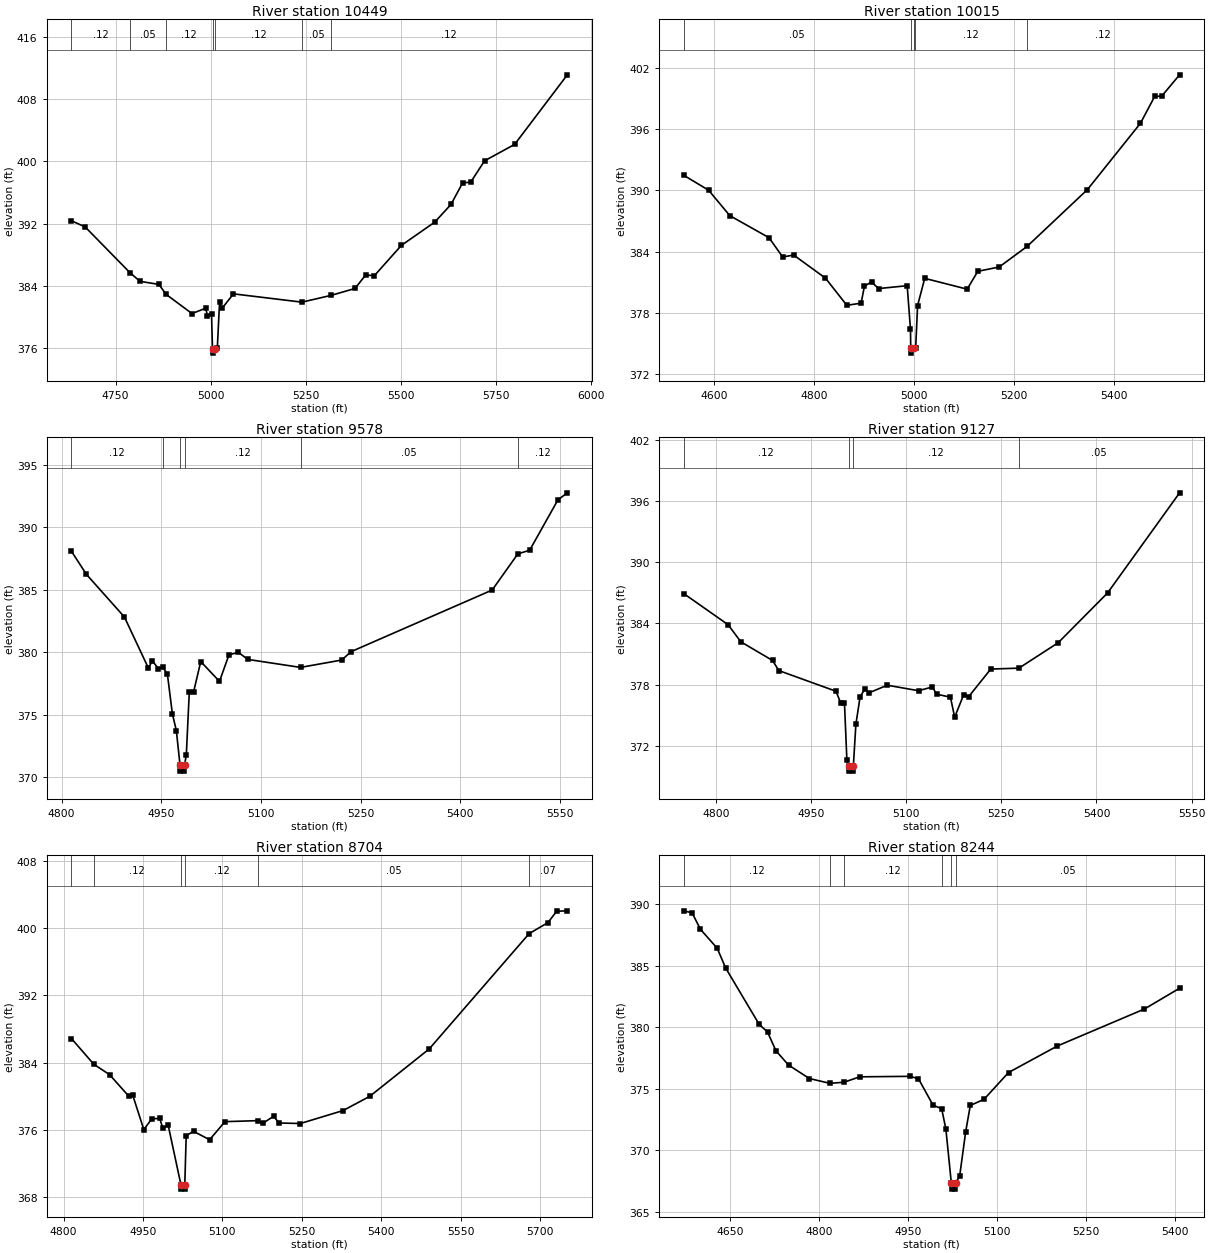
Type RM Length L Ch R = 1 ,10449   ,434,434,434
BEGIN DESCRIPTION:
Stream0427 21.0
END DESCRIPTION:
XS GIS Cut Line= 3
      2458074.98     13792525.03        2458275.       13792225.
      2459075.01       13791725.
#Sta/Elev= 30
  4633.8  392.36  4669.9  391.56  4787.4  385.68  4814.1  384.55  4863.7  384.16
  4882.8  382.87  4950.8   380.4  4986.9  381.09  4991.4  380.09  5002.1  380.37
  5004.7   375.8  5005.2   375.3  5011.3   375.8  5017.4  375.97  5023.3  381.91
  5029.8  381.07  5059.8  382.94  5239.9  381.87  5316.2  382.74  5379.4  383.63
  5407.1  385.35  5430.7   385.3  5501.5  389.19  5589.3  392.19  5631.8  394.46
  5662.4  397.24  5683.7  397.34  5720.2  400.09  5799.2   402.2  5937.8  411.17
#Mann= 7 ,-1 , 0
  4633.8     .12       0  4787.4     .05       0  4882.8     .12       0
  5004.7     .05       0  5011.3     .12       0  5239.9     .05       0
  5316.2     .12       0
Bank Sta=5004.7,5011.3
XS Rating Curve= 0 ,0
Exp/Cntr=0.3,0.1

Type RM Length L Ch R = 1 ,10015   ,437,437,437
BEGIN DESCRIPTION:
Stream0427 20.0
END DESCRIPTION:
XS GIS Cut Line= 3
      2458274.98     13792675.02        2458625.       13792375.
      2458974.99     13791975.01
#Sta/Elev= 30
  4538.4  391.49  4588.4  390.02  4630.6  387.54  4709.1  385.38  4736.5  383.49
  4758.5  383.68  4822.1  381.42  4864.9  378.76  4893.5  378.97  4900.1  380.64
  4914.3  381.04  4928.6   380.4  4985.7  380.68  4992.3   376.4  4992.8  374.58
  4993.3  374.08  4999.5  374.58  5001.1  374.58  5002.7  374.58  5006.5  378.73
  5020.8   381.4  5105.7  380.34  5127.1  382.09  5169.8  382.51  5225.6  384.52
  5346.3  390.08  5452.6  396.58  5481.1  399.21  5495.3  399.24  5530.9  401.32
#Mann= 5 ,-1 , 0
  4538.4     .05       0  4992.8     .05       0  4999.5     .05       0
  5001.1     .12       0  5225.6     .12       0
Bank Sta=4992.8,4999.5
XS Rating Curve= 0 ,0
Exp/Cntr=0.3,0.1

Type RM Length L Ch R = 1 ,9578    ,451,451,451
BEGIN DESCRIPTION:
Stream0427 19.0
END DESCRIPTION:
XS GIS Cut Line= 3
      2458724.98     13792825.03        2458825.       13792675.
        2459225.       13792275.
#Sta/Elev= 30
  4814.9  388.09  4837.5  386.24  4894.6  382.83  4930.6  378.75  4936.6  379.32
  4945.6  378.71  4952.2  378.82  4959.2  378.27  4966.7   375.1  4972.7  373.74
  4978.2     371  4978.7   370.5  4984.6   370.5  4985.1     371  4987.7  371.81
  4992.2  376.85  4998.7  376.85  5009.4  379.27  5037.6  377.68  5051.8   379.8
  5065.9  380.01  5080.1  379.44  5159.5   378.8  5221.5  379.39  5235.6  380.06
  5447.8  384.99  5486.4  387.88  5504.3  388.18  5546.8  392.21  5560.9  392.77
#Mann= 6 ,-1 , 0
  4814.9     .12       0  4952.2     .12       0  4978.2     .05       0
  4985.1     .12       0  5159.5     .05       0  5486.4     .12       0
Bank Sta=4978.2,4985.1
XS Rating Curve= 0 ,0
Exp/Cntr=0.3,0.1

Type RM Length L Ch R = 1 ,9127    ,423,423,423
BEGIN DESCRIPTION:
Stream0427 18.0
END DESCRIPTION:
XS GIS Cut Line= 3
        2459175.     13793075.04        2459175.       13792825.
      2459525.03     13792424.96
#Sta/Elev= 30
  4749.4  386.93  4819.4  383.88  4839.4  382.21  4889.4  380.38  4899.4  379.39
  4989.4  377.37  4996.9  376.22  5002.8  376.22  5006.6  370.63  5009.7  370.05
  5010.2  369.55  5016.3  369.55  5016.8  370.05  5020.8  374.14  5027.4  376.81
    5035  377.61  5041.7  377.22  5070.2  377.96  5119.5  377.42  5141.3  377.79
    5148  377.08  5169.8  376.79  5176.5  374.83  5190.7  377.03  5198.3  376.82
  5233.4  379.54  5277.8  379.63  5339.7  382.12  5417.5  386.99    5531  396.79
#Mann= 4 ,-1 , 0
  4749.4     .12       0  5009.7     .05       0  5016.8     .12       0
  5277.8     .05       0
Bank Sta=5009.7,5016.8
XS Rating Curve= 0 ,0
Exp/Cntr=0.3,0.1

Type RM Length L Ch R = 1 ,8704    ,460,460,460
BEGIN DESCRIPTION:
Stream0427 17.0
END DESCRIPTION:
XS GIS Cut Line= 3
      2459325.01     13793174.99        2459475.       13793075.
        2459575.       13792325.
#Sta/Elev= 30
  4814.9  386.87    4857  383.82    4887  382.57    4923  380.03  4930.6  380.15
  4951.6  376.05  4966.6  377.32  4981.6  377.38  4987.6   376.2  4997.7  376.55
  5021.8  369.47  5022.3  368.97  5028.5  368.97    5029  369.47  5031.7  375.33
  5045.6  375.84  5075.9  374.84  5104.9  376.99  5167.5  377.11  5176.8  376.81
  5196.9  377.63    5207  376.83  5247.4  376.77  5328.1  378.31  5378.5     380
  5490.8  385.63  5679.6  399.34  5715.2  400.65  5731.6     402  5751.8  402.05
#Mann= 6 ,-1 , 0
  4814.9     .12       0    4857     .12       0  5021.8     .05       0
    5029     .12       0  5167.5     .05       0  5679.6     .07       0
Bank Sta=5021.8,5029
XS Rating Curve= 0 ,0
Exp/Cntr=0.3,0.1

Type RM Length L Ch R = 1 ,8244    ,422,422,422
BEGIN DESCRIPTION:
Stream0427 16.0
END DESCRIPTION:
XS GIS Cut Line= 3
        2459525.       13793525.        2459825.       13793225.
      2459925.01     13792824.98
#Sta/Elev= 30
  4571.1  389.48  4585.2  389.32  4599.4  387.97  4627.7  386.43  4641.8  384.83
  4698.4  380.24  4712.5  379.62  4726.7  378.09  4747.9  376.93  4783.2  375.83
  4817.8  375.44  4841.5  375.53  4868.1  375.97  4952.9  376.01  4967.1  375.82
  4991.8  373.66  5006.3  373.38  5013.4  371.72  5022.6  367.33  5023.1  366.83
  5029.4  366.83  5029.9  367.33  5036.6  367.87  5046.9  371.52  5054.6  373.64
  5077.8  374.14  5119.1  376.32  5201.5  378.48  5348.4  381.49  5407.7  383.18
#Mann= 6 ,-1 , 0
  4571.1     .12       0  4817.8     .07       0  4841.5     .12       0
  5006.3     .05       0  5022.6     .05       0  5029.9     .05       0
Bank Sta=5022.6,5029.9
XS Rating Curve= 0 ,0
Exp/Cntr=0.3,0.1

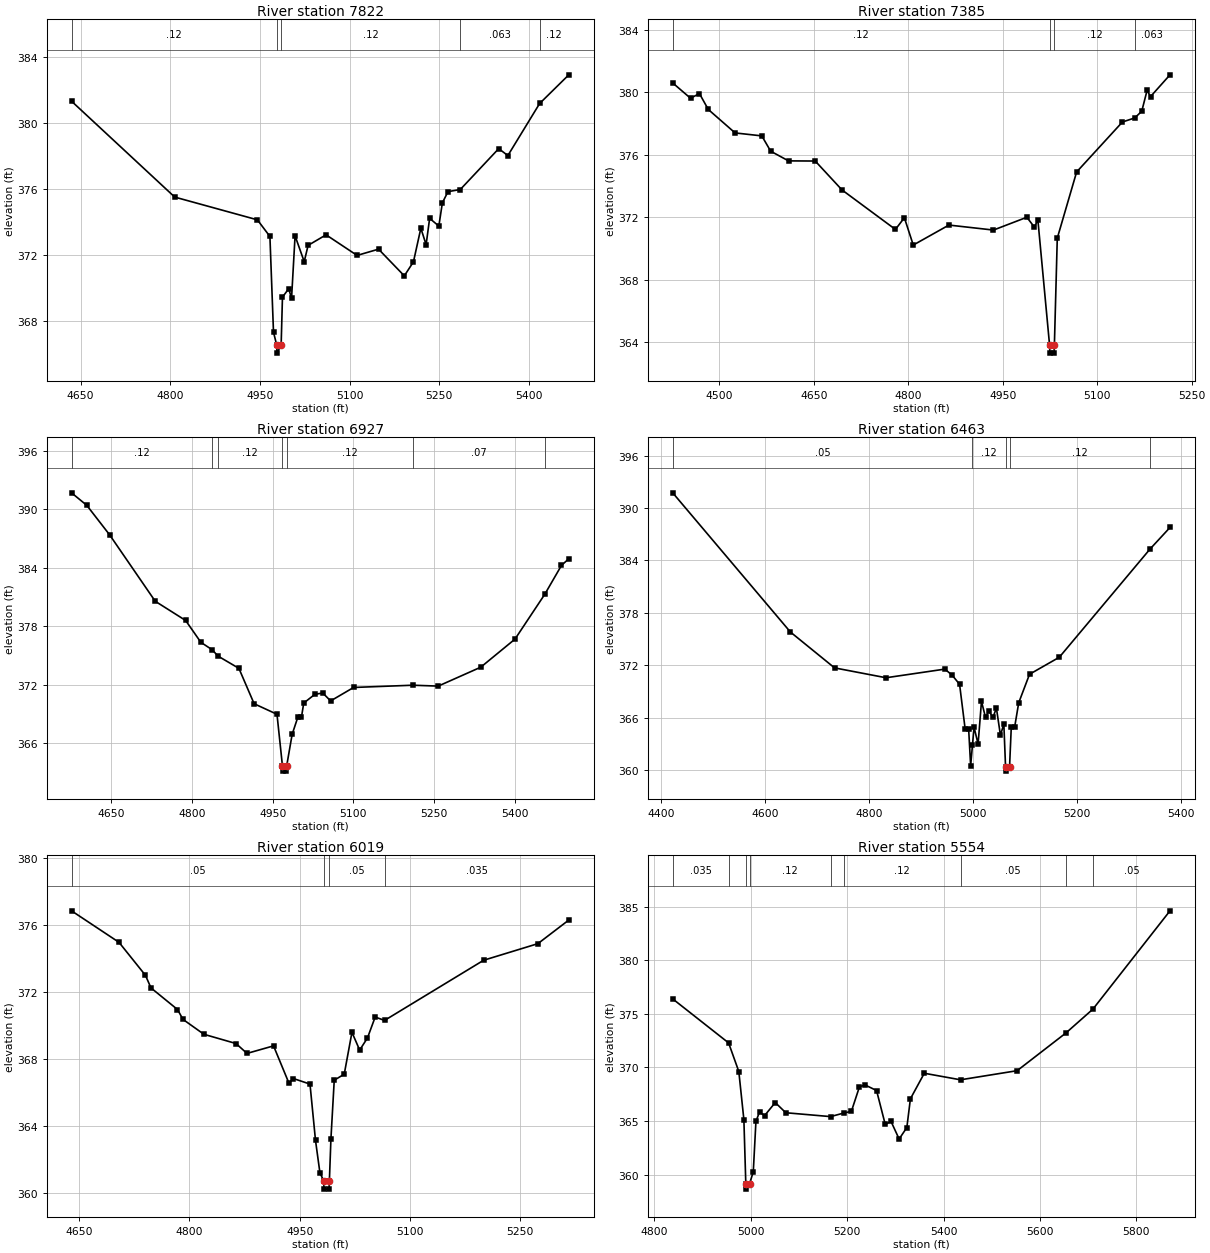
Type RM Length L Ch R = 1 ,7822    ,437,437,437
BEGIN DESCRIPTION:
Stream0427 15.0
END DESCRIPTION:
XS GIS Cut Line= 3
      2459825.02     13793674.99        2460125.       13793475.
      2460524.97     13793225.02
#Sta/Elev= 30
  4634.8  381.32  4807.5   375.5  4945.8  374.12  4966.8  373.11  4972.8   367.3
  4978.1  366.53  4978.6  366.03  4985.6  366.53  4987.8  369.43  4998.3  369.94
    5003  369.35  5008.9  373.15  5024.2  371.58  5030.7  372.57  5060.8  373.21
  5112.7  371.96  5148.6  372.34  5191.7  370.72    5207  371.57  5219.4  373.61
  5228.2  372.61  5234.1  374.21  5249.5  373.74  5255.4  375.15  5264.8  375.83
  5285.4  375.96  5349.7  378.44    5365  378.02  5418.2  381.18    5467  382.92
#Mann= 5 ,-1 , 0
  4634.8     .12       0  4978.1     .05       0  4985.6     .12       0
  5285.4    .063       0  5418.2     .12       0
Bank Sta=4978.1,4985.6
XS Rating Curve= 0 ,0
Exp/Cntr=0.3,0.1

Type RM Length L Ch R = 1 ,7385    ,458,458,458
BEGIN DESCRIPTION:
Stream0427 14.0
END DESCRIPTION:
XS GIS Cut Line= 3
      2460025.02     13793924.98        2460425.       13793525.
      2460625.04     13793424.98
#Sta/Elev= 30
  4426.2  380.59  4454.5  379.61  4468.6  379.91  4482.7  378.89  4525.2  377.39
  4567.6   377.2  4581.7  376.22    4610   375.6  4652.4  375.59  4694.9  373.74
  4779.7  371.21  4793.9  371.96    4808  370.21  4864.6  371.49  4935.3  371.17
  4988.3  371.99  5000.2  371.36  5005.8  371.82  5024.4  363.79  5024.9  363.29
  5031.5  363.29    5032  363.79  5036.6  370.65  5067.3  374.89    5140  378.09
  5159.6  378.35  5170.7  378.78  5179.1  380.11  5184.7  379.72  5215.5  381.11
#Mann= 4 ,-1 , 0
  4426.2     .12       0  5024.4     .05       0    5032     .12       0
  5159.6    .063       0
Bank Sta=5024.4,5032
XS Rating Curve= 0 ,0
Exp/Cntr=0.3,0.1

Type RM Length L Ch R = 1 ,6927    ,464,464,464
BEGIN DESCRIPTION:
Stream0427 13.0
END DESCRIPTION:
XS GIS Cut Line= 3
      2460074.99     13794225.01        2460375.       13793925.
      2460775.01     13793624.99
#Sta/Elev= 30
  4576.2   391.7  4604.5  390.42  4646.9   387.4  4731.8  380.58  4788.3  378.61
  4816.6  376.37  4837.8   375.6  4848.4  374.96  4887.3   373.7  4915.6  370.07
  4958.1  368.99  4968.3  363.66  4968.8  363.16  4975.5  363.16    4976  363.66
  4986.3  366.94  4996.9   368.7  5003.6   368.7  5007.8  370.14  5028.6  371.04
  5043.2  371.17  5057.8  370.36  5100.5  371.74  5210.4  371.97  5257.8  371.88
  5336.9  373.82  5400.5   376.7  5455.9   381.3  5486.9  384.26  5500.5  384.94
#Mann= 7 ,-1 , 0
  4576.2     .12       0  4837.8     .05       0  4848.4     .12       0
  4968.3     .05       0    4976     .12       0  5210.4     .07       0
  5455.9     .12       0
Bank Sta=4968.3,4976
XS Rating Curve= 0 ,0
Exp/Cntr=0.3,0.1

Type RM Length L Ch R = 1 ,6463    ,444,444,444
BEGIN DESCRIPTION:
Stream0427 12.0
END DESCRIPTION:
XS GIS Cut Line= 3
      2460324.97     13794525.03        2460725.       13794125.
      2460974.97     13793825.03
#Sta/Elev= 30
  4422.4  391.75  4648.7   375.8  4733.6  371.69  4832.6  370.56  4945.7  371.55
  4959.8  370.85    4974  369.81  4984.6  364.74  4991.4  364.74  4995.3  360.47
  4998.8  362.86  5001.8   364.9  5009.6  362.96  5016.1  367.84  5023.9  366.02
  5030.4  366.76  5038.2  366.01  5044.8  367.09  5052.6  363.96  5059.1  365.29
  5062.4  360.36  5062.9  359.86  5070.1  360.36  5073.4  364.88  5079.9  364.91
  5087.7  367.69  5108.5  370.96  5165.8  372.91  5340.1   385.3  5378.6  387.78
#Mann= 5 ,-1 , 0
  4422.4     .05       0  4998.8     .12       0  5062.4     .05       0
  5070.1     .12       0  5340.1    .035       0
Bank Sta=5062.4,5070.1
XS Rating Curve= 0 ,0
Exp/Cntr=0.3,0.1

Type RM Length L Ch R = 1 ,6019    ,465,465,465
BEGIN DESCRIPTION:
Stream0427 11.0
END DESCRIPTION:
XS GIS Cut Line= 3
      2460625.03     13794574.98        2460925.       13794375.
      2461024.98     13794075.05
#Sta/Elev= 30
  4639.5  376.83  4704.1  374.95  4740.1  372.98  4747.6  372.23  4783.7  370.94
  4791.2  370.35  4819.7  369.46  4863.3  368.91  4878.3  368.32  4914.4  368.77
  4935.4  366.54  4941.4  366.82    4964  366.49  4971.5  363.13  4977.5   361.2
  4982.6  360.72  4983.1  360.22  4989.9  360.22  4990.4  360.72  4992.5  363.23
    4997  366.72  5010.6  367.08  5021.1  369.58  5031.6  368.52  5042.2  369.24
  5052.7  370.49  5065.5  370.29  5200.3  373.88  5274.1  374.87  5316.2  376.28
#Mann= 4 ,-1 , 0
  4639.5     .05       0  4982.6     .05       0  4990.4     .05       0
  5065.5    .035       0
Bank Sta=4982.6,4990.4
XS Rating Curve= 0 ,0
Exp/Cntr=0.3,0.1

Type RM Length L Ch R = 1 ,5554    ,473,473,473
BEGIN DESCRIPTION:
Stream0427 10.0
END DESCRIPTION:
XS GIS Cut Line= 3
      2460824.97     13794875.01        2460975.       13794825.
      2461775.04     13794474.98
#Sta/Elev= 30
  4838.2  376.39  4954.1  372.29  4975.3  369.62  4985.8  365.14  4989.8  359.16
  4990.3  358.66  4997.6  359.16  5005.3  360.28  5010.8  364.97  5018.2  365.85
  5028.7  365.51  5050.9  366.73  5072.7  365.78  5165.5  365.42  5192.9  365.75
  5208.8  365.91  5225.6  368.21  5237.6  368.36    5261  367.85    5279  364.69
    5291  364.97  5307.8  363.33  5323.8   364.4  5331.2  367.08    5360  369.46
  5435.1  368.85  5552.6   369.7  5653.9  373.22  5709.8  375.44  5869.6   384.6
#Mann= 9 ,-1 , 0
  4838.2    .035       0  4954.1     .12       0  4989.8     .05       0
  4997.6     .12       0  5165.5    .035       0  5192.9     .12       0
  5435.1     .05       0  5653.9     .07       0  5709.8     .05       0
Bank Sta=4989.8,4997.6
XS Rating Curve= 0 ,0
Exp/Cntr=0.3,0.1

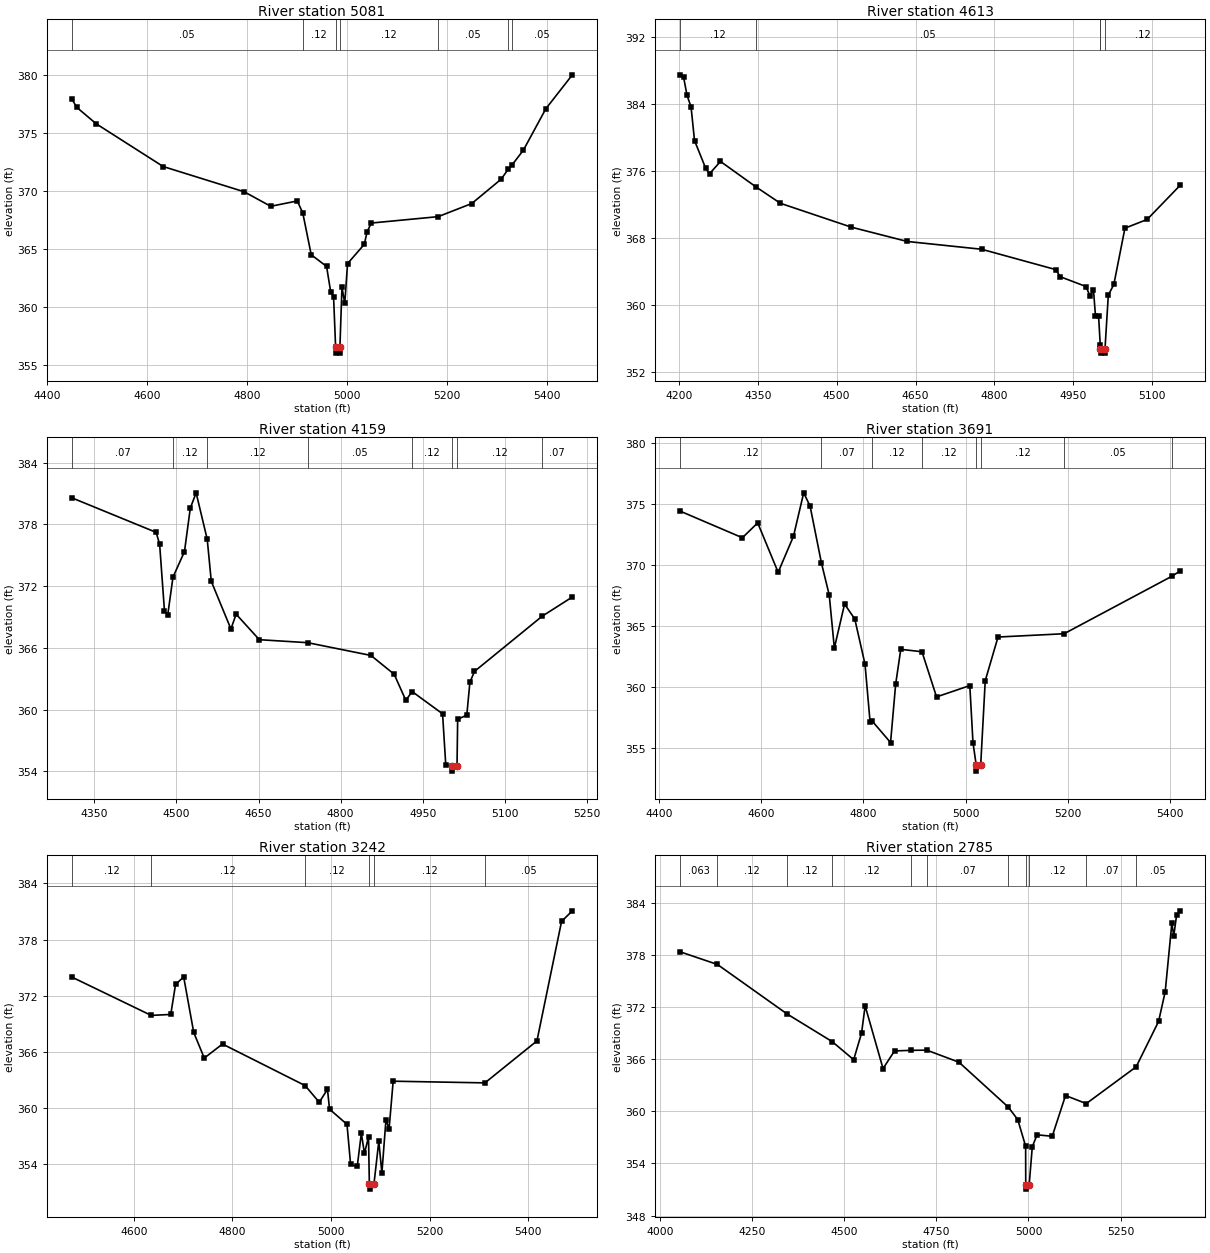
Type RM Length L Ch R = 1 ,5081    ,468,468,468
BEGIN DESCRIPTION:
Stream0427 9.0
END DESCRIPTION:
XS GIS Cut Line= 4
      2460878.64     13795173.18        2461075.       13795075.
        2461375.       13794925.      2461775.03     13794724.98
#Sta/Elev= 30
  4449.4  377.94  4459.3   377.2  4498.4  375.78  4632.6   372.1  4794.7  369.93
  4847.8  368.68  4900.9  369.14  4911.9  368.12  4928.9  364.51  4959.6  363.51
    4968  361.28  4973.6  360.91  4977.7  356.55  4978.2  356.05  4985.8  356.05
  4986.3  356.55  4990.4  361.73    4996  360.32  5001.6  363.75  5035.1  365.41
  5040.7  366.48  5049.1  367.24    5183  367.79  5250.3  368.92    5309  371.01
  5323.3  371.87  5331.3  372.26  5353.7  373.52  5398.5  377.07  5451.6  379.99
#Mann= 7 ,-1 , 0
  4449.4     .05       0  4911.9     .12       0  4977.7     .05       0
  4986.3     .12       0    5183     .05       0  5323.3     .07       0
  5331.3     .05       0
Bank Sta=4977.7,4986.3
XS Rating Curve= 0 ,0
Exp/Cntr=0.3,0.1

Type RM Length L Ch R = 1 ,4613    ,454,454,454
BEGIN DESCRIPTION:
Stream0427 8.0
END DESCRIPTION:
XS GIS Cut Line= 4
      2461077.76     13795647.59        2461275.       13795475.
        2461675.       13795125.      2461824.99       13795075.
#Sta/Elev= 30
  4201.8  387.54  4209.1  387.28  4215.7  385.08  4223.3  383.73  4229.9  379.69
  4251.3  376.35  4258.4  375.72  4279.3  377.19  4346.3  374.17  4393.2  372.19
    4528  369.34  4634.3  367.63  4775.7   366.7  4917.1  364.26  4924.7  363.43
    4974  362.25  4981.6  361.13  4988.3  361.83  4992.1  358.75    4998  358.75
  5001.2  355.23  5001.6  354.79  5002.1  354.29  5009.7  354.29  5010.2  354.79
  5016.5  361.22    5027  362.49  5048.1  369.22  5090.3  370.26  5153.5  374.37
#Mann= 5 ,-1 , 0
  4201.8     .12       0  4346.3     .05       0  5001.2     .12       0
  5001.6     .05       0  5010.2     .12       0
Bank Sta=5001.6,5010.2
XS Rating Curve= 0 ,0
Exp/Cntr=0.3,0.1

Type RM Length L Ch R = 1 ,4159    ,468,468,468
BEGIN DESCRIPTION:
Stream0427 7.0
END DESCRIPTION:
XS GIS Cut Line= 4
      2461458.56     13796111.31        2461575.       13795925.
        2461825.       13795525.        2461925.     13795325.01
#Sta/Elev= 30
  4308.6  380.59  4462.9  377.23  4469.3  376.08  4478.2  369.56  4484.1   369.2
  4493.7  372.88  4514.7  375.36  4525.4  379.59    4536  381.07  4556.3  376.55
  4563.7  372.47  4599.6  367.84  4609.1  369.28  4651.5   366.8  4739.9  366.51
  4855.5  365.27    4898  363.44  4919.2  360.91  4930.8  361.76  4986.4   359.6
  4992.3  354.59    5004  354.53  5004.5  354.03  5012.8  354.53    5014  359.07
  5030.7  359.47  5036.3  362.65  5044.7  363.72  5168.4  369.08  5223.6  370.95
#Mann= 8 ,-1 , 0
  4308.6     .07       0  4493.7     .12       0  4556.3     .12       0
  4739.9     .05       0  4930.8     .12       0    5004     .05       0
  5012.8     .12       0  5168.4     .07       0
Bank Sta=5004,5012.8
XS Rating Curve= 0 ,0
Exp/Cntr=0.3,0.1

Type RM Length L Ch R = 1 ,3691    ,449,449,449
BEGIN DESCRIPTION:
Stream0427 6.0
END DESCRIPTION:
XS GIS Cut Line= 4
        2462075.     13796427.56        2462075.       13796175.
        2462075.       13795875.      2462225.02     13795474.96
#Sta/Elev= 30
  4440.5  374.45  4563.1  372.25  4593.1  373.47  4633.1  369.41  4663.1  372.37
  4683.1  375.94  4695.6  374.85  4717.8  370.18  4733.1  367.54  4743.1  363.18
  4763.1   366.8  4783.1  365.57  4803.1  361.86  4813.1  357.08  4816.2  357.23
  4853.1  355.42  4863.1  360.22  4873.1  363.08  4914.6  362.88  4943.1  359.17
  5008.2   360.1  5014.4  355.42  5020.7  353.57  5021.2  353.07  5029.5  353.57
  5038.4   360.5  5063.4  364.09  5192.7  364.36  5403.5  369.08  5420.3  369.53
#Mann= 8 ,-1 , 0
  4440.5     .12       0  4717.8     .07       0  4816.2     .12       0
  4914.6     .12       0  5020.7     .05       0  5029.5     .12       0
  5192.7     .05       0  5403.5     .07       0
Bank Sta=5020.7,5029.5
XS Rating Curve= 0 ,0
Exp/Cntr=0.3,0.1

Type RM Length L Ch R = 1 ,3242    ,457,457,457
BEGIN DESCRIPTION:
Stream0427 5.0
END DESCRIPTION:
XS GIS Cut Line= 4
      2462159.59     13796467.35        2462275.       13796275.
        2462425.       13796025.      2462725.02     13795624.97
#Sta/Elev= 30
  4473.8  374.01  4635.1  369.91  4674.8  370.01  4684.5  373.21    4701  374.02
  4721.4  368.09  4742.8  365.35  4779.8  366.85  4947.5  362.41  4976.1  360.63
  4992.8  362.01    4997  359.89  5032.4  358.27  5039.7     354  5053.2  353.77
  5061.5  357.31  5067.8  355.18  5076.1  356.91  5077.8  351.85  5078.3  351.35
    5087  351.85    5097  356.47  5103.2  353.06  5111.5  358.78  5117.8  357.77
  5126.1  362.88  5312.3   362.7  5417.8  367.18  5467.8  379.95  5489.7  381.08
#Mann= 6 ,-1 , 0
  4473.8     .12       0  4635.1     .12       0  4947.5     .12       0
  5077.8     .05       0    5087     .12       0  5312.3     .05       0
Bank Sta=5077.8,5087
XS Rating Curve= 0 ,0
Exp/Cntr=0.3,0.1

Type RM Length L Ch R = 1 ,2785    ,458,458,458
BEGIN DESCRIPTION:
Stream0427 4.0
END DESCRIPTION:
XS GIS Cut Line= 3
      2462339.05     13796837.61        2462825.       13796025.
      2462924.99     13795625.03
#Sta/Elev= 30
  4053.3  378.37  4155.6   376.9  4344.5  371.21  4467.6  368.01  4525.5  365.94
  4546.9     369  4556.6  372.14  4605.2  364.92  4636.4  366.95  4682.4  367.02
  4724.1  367.04  4811.4  365.65  4944.9   360.5  4970.9  359.05  4992.3  355.99
  4992.6  351.55  4993.1  351.05  5001.9  351.55  5010.4  355.92  5023.3   357.3
  5064.5  357.13  5100.6  361.82  5156.9  360.89  5292.3  365.12  5353.2  370.34
  5371.2  373.77  5389.2  381.64  5394.4  380.17  5402.1  382.58  5412.4  383.07
#Mann= 11 ,-1 , 0
  4053.3    .063       0  4155.6     .12       0  4344.5     .12       0
  4467.6     .12       0  4682.4     .05       0  4724.1     .07       0
  4944.9     .12       0  4992.6     .05       0  5001.9     .12       0
  5156.9     .07       0  5292.3     .05       0
Bank Sta=4992.6,5001.9
XS Rating Curve= 0 ,0
Exp/Cntr=0.3,0.1

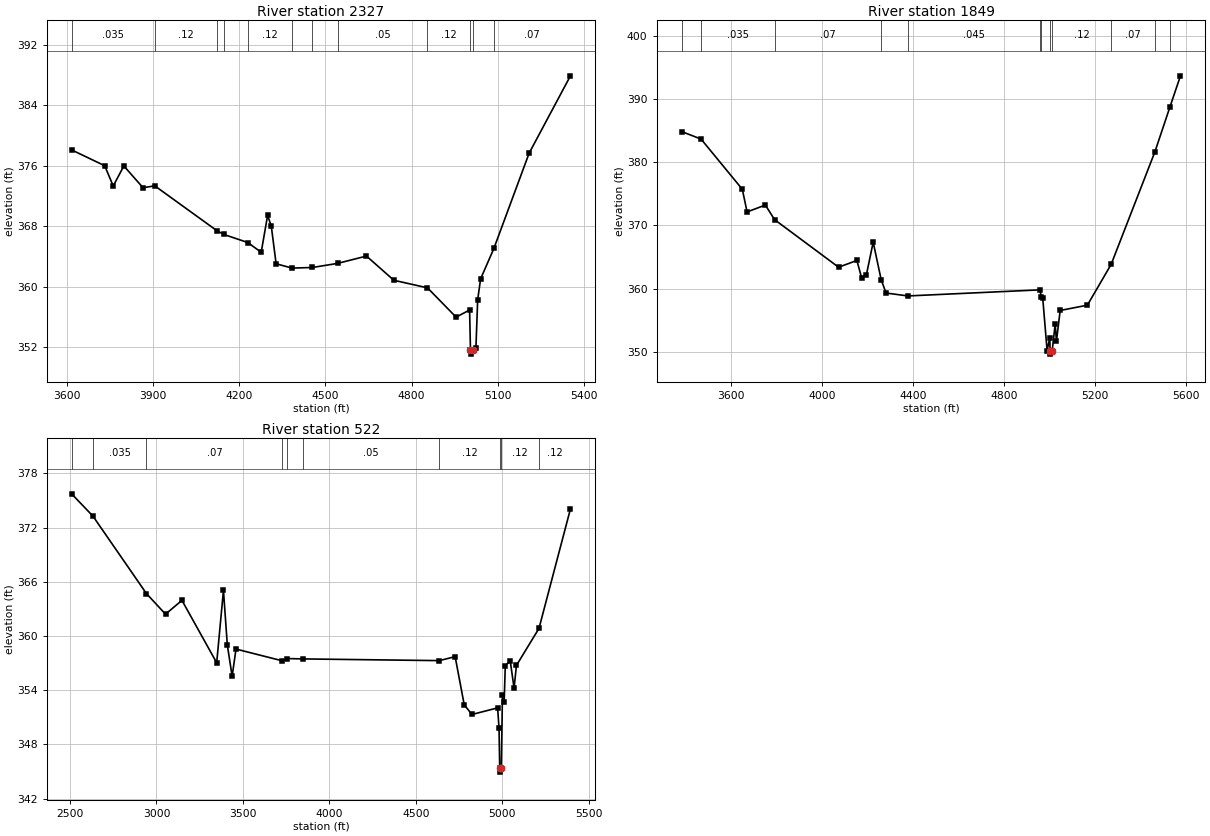
Type RM Length L Ch R = 1 ,2327    ,478,478,478
BEGIN DESCRIPTION:
Stream0427 3.0
END DESCRIPTION:
XS GIS Cut Line= 3
      2462615.26     13797118.54        2463225.       13795875.
      2463300.75     13795529.08
#Sta/Elev= 30
    3615  378.08  3730.3  375.99  3760.1  373.31  3797.1  375.96    3864  373.08
    3905  373.33  4122.8  367.37  4146.1   366.9  4229.2  365.84    4276  364.55
  4298.3  369.42  4311.1  368.01    4328  363.03  4383.7  362.46  4454.5  362.54
  4542.1  363.08    4643  364.05  4738.5  360.85  4855.7  359.85  4955.4  355.98
  5002.5  356.92  5005.6  351.59  5006.1  351.09  5014.9  351.59  5024.5  351.85
  5030.7  358.28  5040.9  361.03  5087.1  365.05  5210.1  377.65  5354.1  387.87
#Mann= 12 ,-1 , 0
    3615    .035       0    3905     .12       0  4122.8     .12       0
  4146.1     .07       0  4229.2     .12       0  4383.7     .05       0
  4454.5     .12       0  4542.1     .05       0  4855.7     .12       0
  5005.6     .05       0  5014.9     .12       0  5087.1     .07       0
Bank Sta=5005.6,5014.9
XS Rating Curve= 0 ,0
Exp/Cntr=0.3,0.1

Type RM Length L Ch R = 1 ,1849    ,1327,1327,1327
BEGIN DESCRIPTION:
Stream0427 2.0
END DESCRIPTION:
XS GIS Cut Line= 3
      2462758.09     13797299.55        2463675.       13795975.
      2463444.33     13795438.76
#Sta/Elev= 30
    3382  384.83  3467.5  383.64    3649   375.7  3669.9  372.12  3750.3  373.21
    3791   370.9  4072.6  363.38    4153  364.45    4174  361.68  4194.9  362.18
  4224.7  367.34    4260  361.39  4281.4   359.3  4377.4  358.84  4958.2   359.8
    4965  358.62  4970.7   358.5  4989.9  350.21    5002  352.26  5002.7  350.14
  5003.2  349.64  5012.1  350.14  5025.5  354.38    5031   351.7  5047.4  356.54
  5167.1  357.38  5271.7  363.83  5464.4  381.64    5531  388.79  5576.7  393.64
#Mann= 12 ,-1 , 0
    3382     .05       0  3467.5    .035       0    3791     .07       0
    4260     .12       0  4377.4    .045       0  4958.2     .05       0
    4965     .12       0  5002.7     .05       0  5012.1     .12       0
  5271.7     .07       0  5464.4     .12       0    5531     .07       0
Bank Sta=5002.7,5012.1
XS Rating Curve= 0 ,0
Exp/Cntr=0.3,0.1

Type RM Length L Ch R = 1 ,522     ,0,0,0
BEGIN DESCRIPTION:
Stream0427 1.0
END DESCRIPTION:
XS GIS Cut Line= 3
      2463205.72     13797504.31        2464325.       13795275.
      2464025.02     13795025.02
#Sta/Elev= 30
  2509.1  375.74  2632.5  373.27  2941.9   364.7  3052.3  362.42  3147.2  363.95
  3348.2  357.04  3387.3  365.05  3409.6  359.02  3437.5  355.55  3459.9  358.56
  3727.2  357.26  3755.5  357.51  3844.5  357.47  4635.3  357.28  4727.3  357.72
  4779.8  352.39  4824.6  351.32  4972.9  352.05  4981.2  349.78    4985  345.44
  4985.5  344.94  4994.4  345.44  5000.8  353.44  5010.8  352.75  5017.3  356.72
  5045.9  357.26  5068.1  354.22  5081.7  356.75  5212.2  360.85  5394.1  374.07
#Mann= 10 ,-1 , 0
  2509.1     .05       0  2632.5    .035       0  2941.9     .07       0
  3727.2     .05       0  3755.5     .07       0  3844.5     .05       0
  4635.3     .12       0    4985     .05       0  4994.4     .12       0
  5212.2     .12       0
Bank Sta=4985,4994.4
XS Rating Curve= 0 ,0
Exp/Cntr=0.3,0.1

Chan Stop Cuts=-1
Use User Specified Reach Order=0
Composite Channel Slope=5