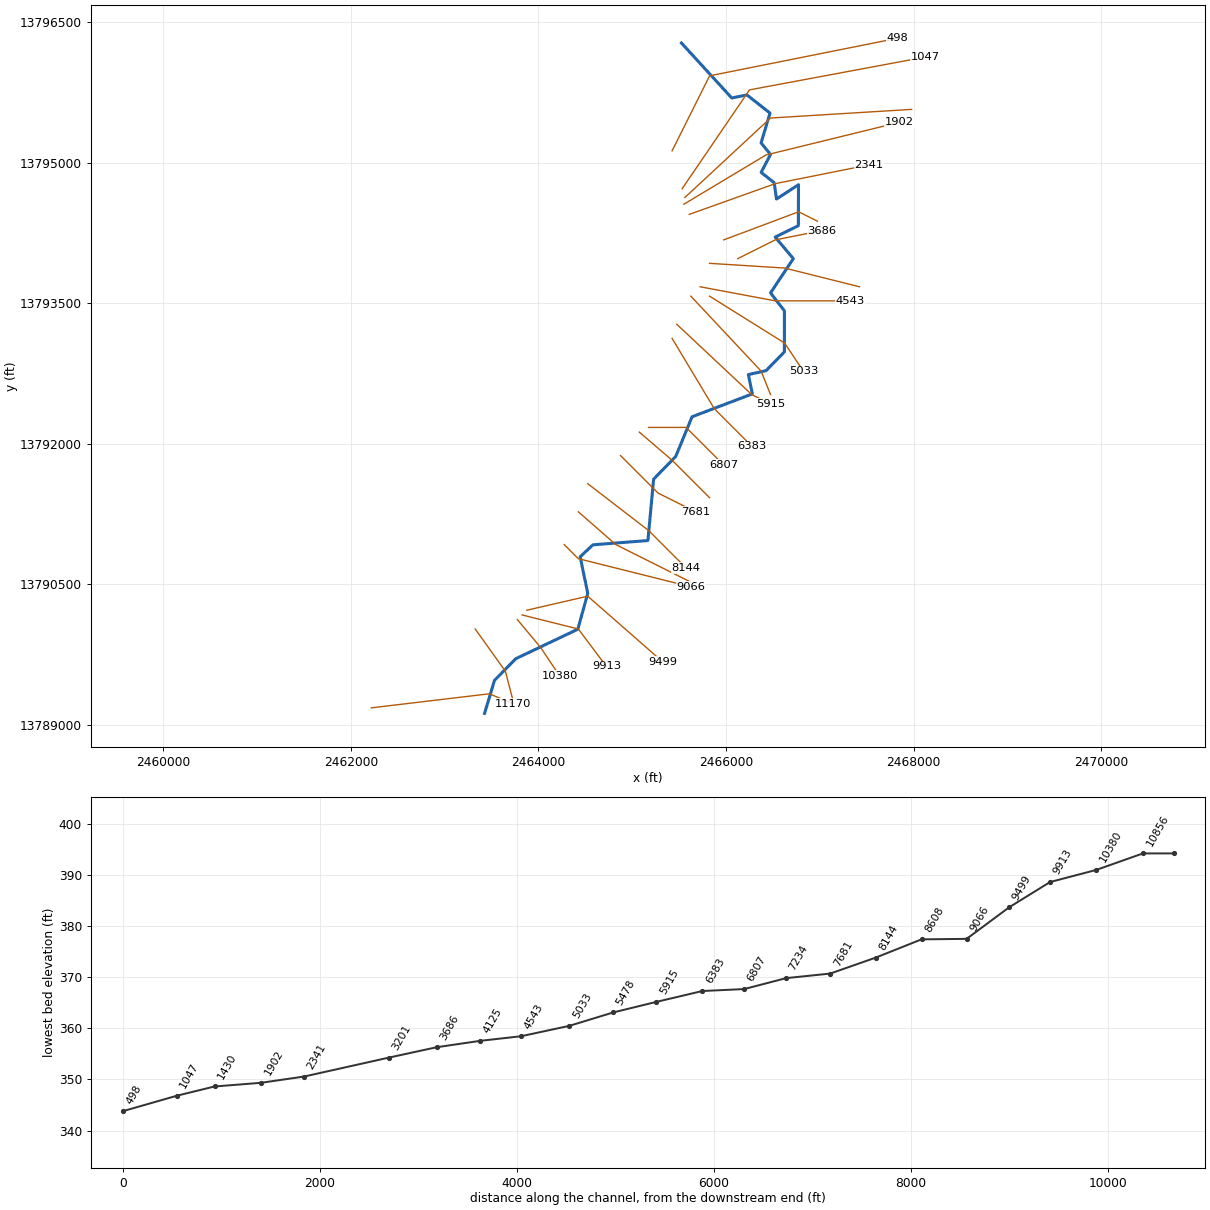
--- Stream0428.prj (project) ---

Proj Title=Stream0428 Base Level Engineering
Current Plan=p01
Default Exp/Contr=0.3,0.1
English Units
Geom File=g01
Flow File=f01
Plan File=p01
BEGIN DESCRIPTION:
Stream0428
END DESCRIPTION:

--- Stream0428.p01 (plan) ---

Plan Title=Multiple Run
Short Identifier=Multiple
Geom File=g01
Flow File=f01
Subcritical Flow
K Sum by GR= 0
Std Step Tol= 0.01
Critical Tol= 0.01
Num of Std Step Trials= 20
Max Error Tol= 0.3
Flow Tol Ratio= 0.001
Split Flow NTrial= 30
Split Flow Tol= 0.02
Split Flow Ratio= 0.02
Log Output Level= 0
Friction Slope Method= 1
Unsteady Friction Slope Method= 2
Unsteady Bridges Friction Slope Method= 1
Parabolic Critical Depth
Global Vel Dist=  1 , 1 , 1
Global Log Level= 0
CheckData=True
Encroach Param= -1, 0, 0, 0
BEGIN DESCRIPTION:
Multiple Run
END DESCRIPTION:

--- Stream0428.f01 (steady flow) ---

Flow Title=Multiple
Number of Profiles=7
Profile Names=10-year,25-year,50-year,1pct_min,100-year,1pct_plu,500-year
River Rch & RM= Stream0428,Reach-1,11170
     748    1212    1633    1066    2126    4243    3567
River Rch & RM= Stream0428,Reach-1,8144
    1223    2039    2800    1859    3709    7401    6448
River Rch & RM= Stream0428,Reach-1,6383
    1350    2250    3090    2050    4091    8162    7102
Boundary for River Rch & Prof#=Stream0428,Reach-1,1
Up Type=0
Dn Type=3
Dn Slope=0.005
Boundary for River Rch & Prof#=Stream0428,Reach-1,2
Up Type=0
Dn Type=3
Dn Slope=0.005
Boundary for River Rch & Prof#=Stream0428,Reach-1,3
Up Type=0
Dn Type=3
Dn Slope=0.005
Boundary for River Rch & Prof#=Stream0428,Reach-1,4
Up Type=0
Dn Type=3
Dn Slope=0.005
Boundary for River Rch & Prof#=Stream0428,Reach-1,5
Up Type=0
Dn Type=3
Dn Slope=0.005
Boundary for River Rch & Prof#=Stream0428,Reach-1,6
Up Type=0
Dn Type=3
Dn Slope=0.005
Boundary for River Rch & Prof#=Stream0428,Reach-1,7
Up Type=0
Dn Type=3
Dn Slope=0.005

--- Stream0428.g01 (geometry) ---

Geom Title=Existing Conditions

River Reach=Stream0428,Reach-1
Reach XY= 30
      2463425.00     13789125.00      2463530.83     13789477.30
      2463758.25     13789708.54      2464419.60     13790022.29
      2464525.67     13790404.92      2464444.60     13790795.16
      2464580.85     13790922.94      2465167.28     13790968.50
      2465228.13     13791623.37      2465463.76     13791865.00
      2465638.24     13792288.70      2466281.57     13792532.70
      2466238.41     13792738.39      2466427.29     13792780.12
      2466622.94     13792980.85      2466622.94     13793419.15
      2466475.02     13793609.59      2466718.02     13793975.21
      2466524.73     13794205.06      2466771.57     13794326.22
      2466773.35     13794763.86      2466538.61     13794610.94
      2466513.89     13794785.32      2466374.74     13794894.95
      2466474.60     13795086.02      2466374.21     13795209.86
      2466469.61     13795527.44      2466223.50     13795721.53
      2466061.59     13795688.52      2465525.00     13796275.00

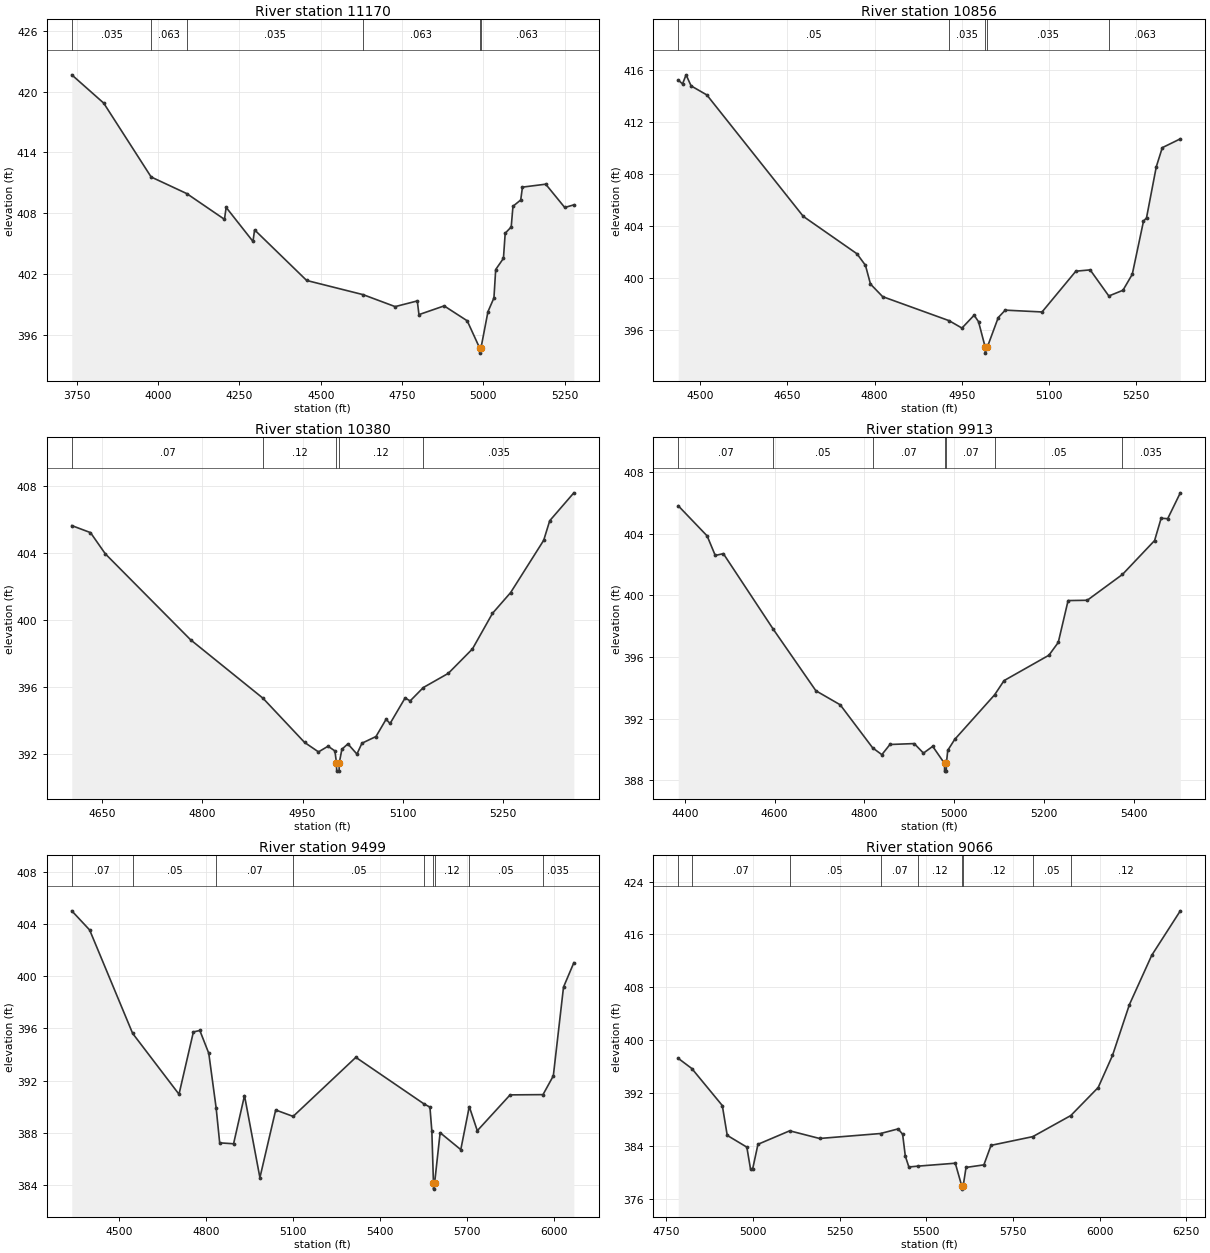
Type RM Length L Ch R = 1,11170,314,314,314
BEGIN DESCRIPTION:
Stream0428 24.0
END DESCRIPTION:
XS GIS Cut Line= 3
      2462217.53     13789183.98      2463475.53     13789333.86
      2463731.23     13789227.32
#Sta/Elev= 30
  3734.4  421.65  3832.6  418.86  3978.5  411.57  4088.1  409.93  4204.0  407.39
  4209.1  408.57  4291.6  405.21  4296.6  406.35  4456.7  401.36  4630.3  399.96
  4728.8  398.78  4796.9  399.34  4802.0  397.99  4879.5  398.85  4950.4  397.38
  4988.7  394.69  4988.9  394.19  4992.7  394.69  5014.2  398.28  5032.6  399.64
  5038.0  402.44  5061.8  403.54  5067.2  406.02  5085.7  406.64  5091.1  408.68
  5114.9  409.30  5120.3  410.57  5191.8  410.86  5250.3  408.56  5278.3  408.82
#Mann=6,-1,0
  3734.4   0.035       0  3978.5   0.063       0  4088.1   0.035       0
  4630.3   0.063       0  4988.7    0.05       0  4992.7   0.063       0
Bank Sta=4988.7,4992.7
Exp/Cntr=0.3,0.1

Type RM Length L Ch R = 1,10856,476,476,476
BEGIN DESCRIPTION:
Stream0428 23.0
END DESCRIPTION:
XS GIS Cut Line= 3
      2463325.00     13790025.01      2463646.84     13789574.76
      2463724.99     13789275.03
#Sta/Elev= 30
  4462.4  415.22  4469.8  414.92  4475.9  415.62  4484.5  414.77  4511.6  414.07
  4677.4  404.72  4769.7  401.84  4784.3  400.95  4792.9  399.51  4813.8  398.54
  4928.0  396.69  4950.2  396.12  4971.1  397.11  4978.7  396.61  4989.9  394.69
  4990.2  394.19  4994.1  394.69  5012.6  396.93  5024.6  397.50  5087.9  397.36
  5146.0  400.50  5170.6  400.60  5202.7  398.59  5227.0  399.03  5243.0  400.26
  5262.3  404.35  5267.5  404.61  5284.3  408.54  5294.6  410.01  5325.6  410.69
#Mann=5,-1,0
  4462.4    0.05       0  4928.0   0.035       0  4989.9   0.035       0
  4994.1   0.035       0  5202.7   0.063       0
Bank Sta=4989.9,4994.1
Exp/Cntr=0.3,0.1

Type RM Length L Ch R = 1,10380,467,467,467
BEGIN DESCRIPTION:
Stream0428 22.0
END DESCRIPTION:
XS GIS Cut Line= 3
      2463774.98     13790125.03      2464025.00     13789825.00
      2464225.00     13789525.00
#Sta/Elev= 30
  4604.8  405.64  4632.8  405.22  4655.0  403.95  4782.5  398.81  4890.9  395.31
  4953.0  392.67  4973.9  392.10  4988.2  392.44  4998.4  392.16  5000.8  391.45
  5001.1  390.95  5004.7  390.95  5005.0  391.45  5008.9  392.26  5017.9  392.58
  5031.4  391.97  5038.9  392.62  5059.9  393.02  5075.0  394.05  5081.0  393.80
  5103.5  395.33  5111.0  395.15  5130.7  395.95  5168.1  396.80  5204.2  398.26
  5234.2  400.39  5261.3  401.63  5310.8  404.76  5319.8  405.93  5355.9  407.60
#Mann=5,-1,0
  4604.8    0.07       0  4890.9    0.12       0  5000.8    0.05       0
  5005.0    0.12       0  5130.7   0.035       0
Bank Sta=5000.8,5005
Exp/Cntr=0.3,0.1

Type RM Length L Ch R = 1,9913,414,414,414
BEGIN DESCRIPTION:
Stream0428 21.0
END DESCRIPTION:
XS GIS Cut Line= 3
      2463824.98     13790175.00      2464425.00     13790025.00
      2464725.01     13789624.99
#Sta/Elev= 30
  4385.3  405.83  4449.7  403.87  4467.8  402.60  4485.8  402.72  4597.2  397.80
  4692.0  393.81  4746.1  392.90  4818.5  390.10  4838.9  389.66  4856.9  390.32
  4911.0  390.38  4931.6  389.76  4952.2  390.20  4978.5  389.09  4978.7  388.59
  4982.4  388.59  4982.7  389.09  4985.7  389.94  5001.2  390.65  5090.2  393.55
  5111.1  394.47  5211.1  396.12  5231.9  396.95  5253.8  399.67  5296.5  399.69
  5375.0  401.37  5446.5  403.57  5461.1  405.02  5475.7  404.99  5503.8  406.67
#Mann=7,-1,0
  4385.3    0.07       0  4597.2    0.05       0  4818.5    0.07       0
  4978.5    0.05       0  4982.7    0.07       0  5090.2    0.05       0
  5375.0   0.035       0
Bank Sta=4978.5,4982.7
Exp/Cntr=0.3,0.1

Type RM Length L Ch R = 1,9499,433,433,433
BEGIN DESCRIPTION:
Stream0428 20.0
END DESCRIPTION:
XS GIS Cut Line= 3
      2463875.00     13790225.00      2464525.00     13790375.00
      2465325.00     13789675.00
#Sta/Elev= 30
  4337.8  405.02  4399.4  403.55  4547.5  395.62  4707.3  390.95  4756.9  395.73
  4779.1  395.84  4809.9  394.09  4835.4  389.88  4847.5  387.22  4895.4  387.15
  4933.0  390.85  4986.1  384.55  5040.5  389.74  5100.6  389.25  5316.7  393.78
  5550.8  390.22  5572.0  389.96  5578.6  388.12  5584.1  384.17  5584.4  383.67
  5588.3  384.17  5607.1  388.00  5678.3  386.70  5707.6  390.00  5735.2  388.15
  5848.2  390.90  5961.6  390.92  5997.2  392.36  6032.3  399.17  6067.9  401.04
#Mann=9,-1,0
  4337.8    0.07       0  4547.5    0.05       0  4835.4    0.07       0
  5100.6    0.05       0  5550.8    0.12       0  5584.1    0.05       0
  5588.3    0.12       0  5707.6    0.05       0  5961.6   0.035       0
Bank Sta=5584.1,5588.3
Exp/Cntr=0.3,0.1

Type RM Length L Ch R = 1,9066,458,458,458
BEGIN DESCRIPTION:
Stream0428 19.0
END DESCRIPTION:
XS GIS Cut Line= 3
      2464275.02     13790924.98      2464425.00     13790775.00
      2465624.97     13790475.01
#Sta/Elev= 30
  4784.0  397.26  4823.2  395.72  4911.2  390.12  4925.4  385.61  4982.0  383.83
  4992.6  380.52  4998.7  380.52  5014.1  384.26  5105.7  386.30  5191.9  385.14
  5367.8  385.89  5418.7  386.59  5431.6  385.78  5439.3  382.49  5449.6  380.83
  5476.4  380.96  5583.6  381.40  5602.1  377.98  5602.4  377.48  5606.4  377.98
  5614.6  380.76  5666.1  381.15  5686.7  384.10  5807.3  385.42  5917.0  388.61
  5996.0  392.85  6037.2  397.69  6086.1  405.39  6150.6  412.85  6233.0  419.57
#Mann=9,-1,0
  4784.0    0.05       0  4823.2    0.07       0  5105.7    0.05       0
  5367.8    0.07       0  5476.4    0.12       0  5602.1    0.05       0
  5606.4    0.12       0  5807.3    0.05       0  5917.0    0.12       0
Bank Sta=5602.1,5606.4
Exp/Cntr=0.3,0.1

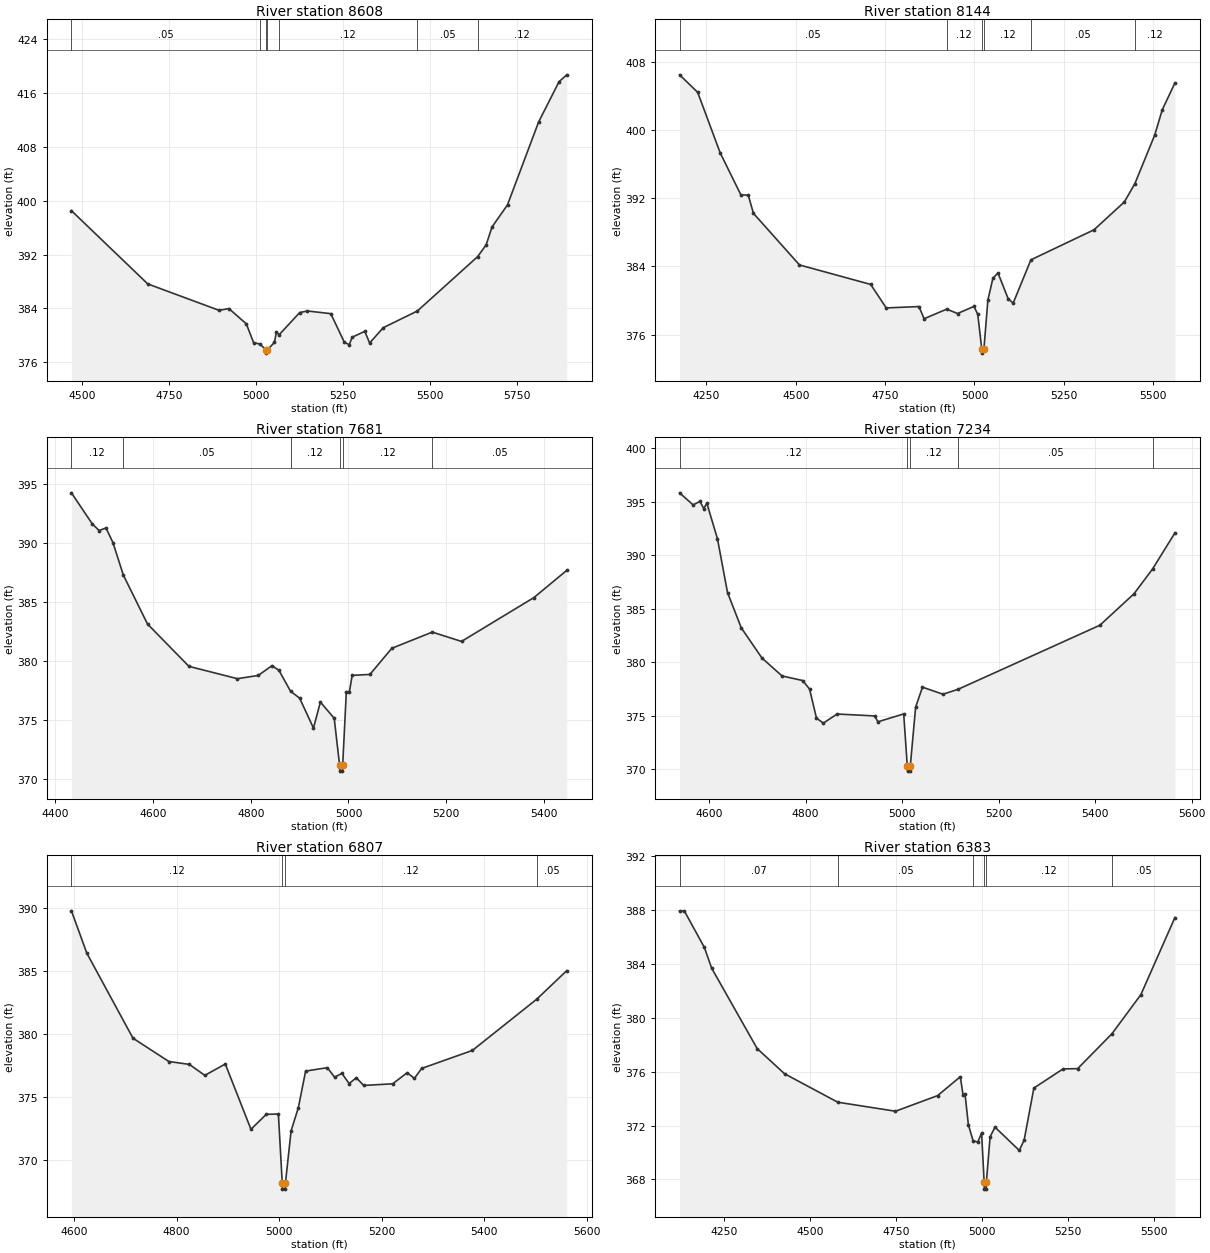
Type RM Length L Ch R = 1,8608,464,464,464
BEGIN DESCRIPTION:
Stream0428 18.0
END DESCRIPTION:
XS GIS Cut Line= 3
      2464425.01     13791274.99      2464825.00     13790925.00
      2465624.98     13790525.01
#Sta/Elev= 30
  4468.5  398.50  4688.2  387.64  4893.7  383.72  4921.7  383.99  4972.0  381.72
  4992.9  378.94  5011.1  378.72  5028.6  377.88  5028.9  377.38  5032.9  377.88
  5053.1  378.98  5058.7  380.56  5066.2  380.09  5125.8  383.40  5148.1  383.63
  5215.2  383.23  5254.3  378.98  5268.3  378.64  5276.7  379.74  5313.0  380.61
  5327.0  378.88  5366.2  381.15  5464.5  383.63  5637.8  391.68  5662.4  393.43
  5679.2  396.07  5723.9  399.37  5813.4  411.64  5872.1  417.61  5894.4  418.64
#Mann=7,-1,0
  4468.5    0.05       0  5011.1    0.07       0  5028.6    0.05       0
  5032.9    0.07       0  5066.2    0.12       0  5464.5    0.05       0
  5637.8    0.12       0
Bank Sta=5028.6,5032.9
Exp/Cntr=0.3,0.1

Type RM Length L Ch R = 1,8144,463,463,463
BEGIN DESCRIPTION:
Stream0428 17.0
END DESCRIPTION:
XS GIS Cut Line= 3
      2464525.00     13791575.00      2465175.00     13791075.00
      2465574.97     13790675.03
#Sta/Elev= 30
  4175.1  406.51  4225.6  404.46  4288.6  397.35  4346.4  392.42  4367.2  392.37
  4381.7  390.24  4510.4  384.18  4709.7  381.89  4753.2  379.13  4844.7  379.29
  4859.2  377.86  4922.6  378.99  4952.6  378.47  4998.7  379.31  5009.3  378.37
  5020.4  374.32  5020.9  373.82  5026.5  374.32  5037.6  380.05  5051.7  382.63
  5065.9  383.23  5094.2  380.22  5108.3  379.69  5158.0  384.78  5334.6  388.31
  5419.4  391.58  5448.8  393.73  5504.3  399.43  5525.5  402.41  5560.8  405.55
#Mann=6,-1,0
  4175.1    0.05       0  4922.6    0.12       0  5020.4    0.05       0
  5026.5    0.12       0  5158.0    0.05       0  5448.8    0.12       0
Bank Sta=5020.4,5026.5
Exp/Cntr=0.3,0.1

Type RM Length L Ch R = 1,7681,447,447,447
BEGIN DESCRIPTION:
Stream0428 16.0
END DESCRIPTION:
XS GIS Cut Line= 3
      2464874.98     13791875.02      2465275.00     13791475.00
      2465674.98     13791275.01
#Sta/Elev= 30
  4433.4  394.23  4475.9  391.61  4490.0  391.04  4504.1  391.26  4518.3  390.02
  4539.5  387.28  4589.0  383.13  4673.8  379.55  4772.8  378.51  4815.3  378.78
  4843.5  379.61  4857.7  379.22  4881.5  377.45  4900.1  376.86  4928.4  374.33
  4942.5  376.53  4970.8  375.16  4981.8  371.19  4982.3  370.69  4987.6  370.69
  4988.1  371.19  4995.6  377.41  5001.9  377.41  5007.5  378.79  5043.8  378.87
  5088.6  381.08  5171.3  382.45  5231.1  381.66  5379.2  385.37  5446.3  387.67
#Mann=6,-1,0
  4433.4    0.12       0  4539.5    0.05       0  4881.5    0.12       0
  4981.8    0.05       0  4988.1    0.12       0  5171.3    0.05       0
Bank Sta=4981.8,4988.1
Exp/Cntr=0.3,0.1

Type RM Length L Ch R = 1,7234,427,427,427
BEGIN DESCRIPTION:
Stream0428 15.0
END DESCRIPTION:
XS GIS Cut Line= 3
      2465075.03     13792124.98      2465425.00     13791825.00
      2465824.98     13791425.02
#Sta/Elev= 30
  4538.7  395.82  4566.7  394.69  4580.9  395.02  4588.6  394.35  4595.2  394.84
  4617.1  391.54  4638.0  386.50  4666.5  383.20  4709.3  380.38  4751.0  378.70
  4793.8  378.27  4808.1  377.47  4822.4  374.75  4836.7  374.29  4865.2  375.14
  4943.1  374.96  4949.7  374.41  5003.2  375.15  5010.6  370.30  5011.1  369.80
  5016.4  369.80  5016.9  370.30  5027.9  375.78  5042.1  377.65  5084.5  376.99
  5115.9  377.45  5409.8  383.44  5480.5  386.38  5519.0  388.70  5565.3  392.07
#Mann=5,-1,0
  4538.7    0.12       0  5010.6    0.05       0  5016.9    0.12       0
  5115.9    0.05       0  5519.0    0.12       0
Bank Sta=5010.6,5016.9
Exp/Cntr=0.3,0.1

Type RM Length L Ch R = 1,6807,424,424,424
BEGIN DESCRIPTION:
Stream0428 14.0
END DESCRIPTION:
XS GIS Cut Line= 3
      2465175.00     13792175.00      2465575.00     13792175.00
      2465975.01     13791774.99
#Sta/Elev= 30
  4595.0  389.75  4625.0  386.39  4715.0  379.64  4785.0  377.79  4825.0  377.56
  4855.0  376.69  4895.0  377.59  4945.0  372.41  4975.0  373.60  4998.5  373.62
  5006.0  368.16  5006.5  367.66  5011.8  367.66  5012.3  368.16  5023.3  372.29
  5037.4  374.12  5051.6  377.03  5094.0  377.30  5108.1  376.54  5122.3  376.85
  5136.4  376.04  5150.6  376.50  5164.7  375.89  5221.3  376.02  5249.6  376.90
  5263.7  376.45  5277.8  377.24  5376.8  378.67  5502.0  382.73  5560.7  385.00
#Mann=4,-1,0
  4595.0    0.12       0  5006.0    0.05       0  5012.3    0.12       0
  5502.0    0.05       0
Bank Sta=5006,5012.3
Exp/Cntr=0.3,0.1

Type RM Length L Ch R = 1,6383,468,468,468
BEGIN DESCRIPTION:
Stream0428 13.0
END DESCRIPTION:
XS GIS Cut Line= 3
      2465424.99     13793125.01      2465875.00     13792375.00
      2466274.97     13791975.03
#Sta/Elev= 30
  4120.3  387.92  4133.9  387.93  4192.2  385.22  4213.6  383.67  4345.8  377.71
  4425.5  375.84  4580.2  373.73  4748.1  373.06  4870.6  374.22  4936.6  375.62
  4944.4  374.30  4950.3  374.34  4960.0  372.06  4973.6  370.88  4987.2  370.77
  4998.5  371.44  5005.9  367.78  5006.4  367.28  5011.8  367.28  5012.3  367.78
  5023.2  371.16  5037.4  371.88  5108.1  370.15  5122.2  370.92  5150.5  374.78
  5235.4  376.20  5277.8  376.22  5377.6  378.81  5461.6  381.71  5560.6  387.43
#Mann=6,-1,0
  4120.3    0.07       0  4580.2    0.05       0  4973.6    0.12       0
  5005.9    0.05       0  5012.3    0.12       0  5377.6    0.05       0
Bank Sta=5005.9,5012.3
Exp/Cntr=0.3,0.1

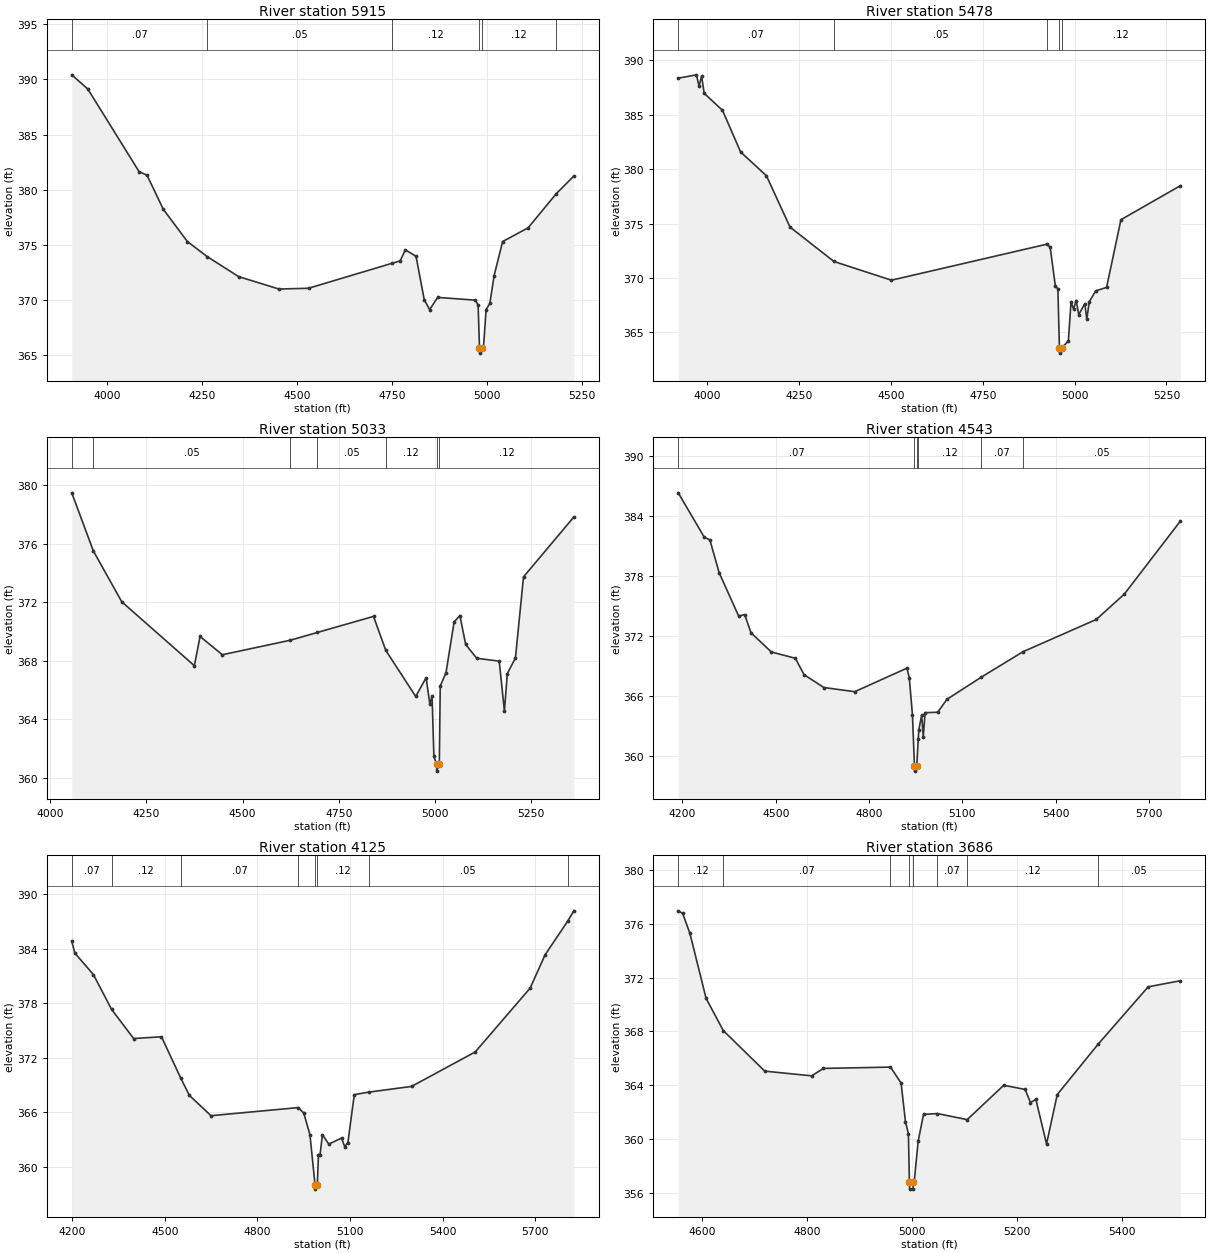
Type RM Length L Ch R = 1,5915,437,437,437
BEGIN DESCRIPTION:
Stream0428 12.0
END DESCRIPTION:
XS GIS Cut Line= 3
      2465475.02     13793274.98      2466275.00     13792525.00
      2466475.03     13792424.99
#Sta/Elev= 30
  3907.6  390.42  3949.8  389.13  4084.6  381.63  4105.6  381.30  4148.1  378.22
  4211.6  375.28  4263.5  373.92  4346.2  372.10  4452.4  370.97  4530.1  371.04
  4749.0  373.30  4770.9  373.52  4784.8  374.53  4812.9  373.94  4834.4  370.00
  4848.6  369.10  4869.6  370.21  4968.8  369.96  4976.1  369.52  4979.7  365.65
  4980.2  365.15  4986.1  365.65  4990.2  365.67  4997.1  369.10  5007.0  369.67
  5018.1  372.18  5040.5  375.28  5107.6  376.53  5181.9  379.64  5227.8  381.23
#Mann=6,-1,0
  3907.6    0.07       0  4263.5    0.05       0  4749.0    0.12       0
  4979.7    0.05       0  4986.1    0.12       0  5181.9    0.05       0
Bank Sta=4979.7,4986.1
Exp/Cntr=0.3,0.1

Type RM Length L Ch R = 1,5478,445,445,445
BEGIN DESCRIPTION:
Stream0428 11.0
END DESCRIPTION:
XS GIS Cut Line= 3
      2465625.02     13793574.98      2466375.00     13792775.00
      2466474.99     13792525.02
#Sta/Elev= 30
  3921.8  388.35  3971.4  388.66  3978.2  387.63  3985.5  388.52  3992.4  386.96
  4042.2  385.40  4091.5  381.57  4161.7  379.39  4225.9  374.67  4345.4  371.51
  4501.8  369.79  4924.6  373.10  4933.6  372.81  4947.8  369.23  4954.6  369.01
  4958.7  363.59  4959.2  363.09  4965.2  363.59  4983.0  364.19  4990.3  367.78
  4997.1  367.16  5004.4  367.92  5011.3  366.63  5027.8  367.64  5033.2  366.20
  5039.9  367.81  5057.4  368.81  5087.0  369.13  5126.1  375.35  5287.6  378.47
#Mann=5,-1,0
  3921.8    0.07       0  4345.4    0.05       0  4924.6    0.12       0
  4958.7    0.05       0  4965.2    0.12       0
Bank Sta=4958.7,4965.2
Exp/Cntr=0.3,0.1

Type RM Length L Ch R = 1,5033,490,490,490
BEGIN DESCRIPTION:
Stream0428 10.0
END DESCRIPTION:
XS GIS Cut Line= 3
      2465824.97     13793575.02      2466625.00     13793075.00
      2466825.00     13792775.00
#Sta/Elev= 30
  4056.4  379.48  4112.3  375.52  4186.2  372.04  4374.8  367.67  4389.6  369.67
  4447.4  368.42  4623.8  369.41  4694.0  369.94  4840.1  371.04  4871.9  368.72
  4949.7  365.57  4976.8  366.85  4986.3  365.06  4992.2  365.60  4996.9  361.47
  5003.7  360.97  5004.2  360.47  5011.0  360.97  5013.4  366.28  5028.4  367.20
  5049.4  370.66  5064.4  371.10  5079.5  369.12  5108.0  368.18  5166.6  367.98
  5180.1  364.57  5187.6  367.13  5208.7  368.20  5229.7  373.74  5360.4  377.83
#Mann=7,-1,0
  4056.4    0.07       0  4112.3    0.05       0  4623.8    0.07       0
  4694.0    0.05       0  4871.9    0.12       0  5003.7    0.05       0
  5011.0    0.12       0
Bank Sta=5003.7,5011
Exp/Cntr=0.3,0.1

Type RM Length L Ch R = 1,4543,418,418,418
BEGIN DESCRIPTION:
Stream0428 9.0
END DESCRIPTION:
XS GIS Cut Line= 3
      2465725.03     13793675.00      2466525.00     13793525.00
      2467324.99     13793525.00
#Sta/Elev= 30
  4186.6  386.33  4270.5  381.87  4288.3  381.62  4318.0  378.33  4380.7  373.99
  4400.2  374.12  4420.6  372.30  4485.9  370.38  4563.0  369.75  4591.0  368.11
  4654.6  366.82  4753.8  366.40  4921.7  368.76  4929.3  367.79  4939.5  364.07
  4945.9  358.94  4946.4  358.44  4953.3  358.94  4958.1  361.62  4959.8  362.57
  4969.1  364.06  4974.2  361.89  4980.2  364.30  5020.5  364.34  5050.5  365.64
  5161.4  367.87  5295.1  370.41  5530.5  373.64  5620.5  376.18  5800.5  383.49
#Mann=6,-1,0
  4186.6    0.07       0  4945.9    0.05       0  4953.3    0.07       0
  4958.1    0.12       0  5161.4    0.07       0  5295.1    0.05       0
Bank Sta=4945.9,4953.3
Exp/Cntr=0.3,0.1

Type RM Length L Ch R = 1,4125,439,439,439
BEGIN DESCRIPTION:
Stream0428 8.0
END DESCRIPTION:
XS GIS Cut Line= 3
      2465824.97     13793925.00      2466625.00     13793875.00
      2467424.99     13793675.00
#Sta/Elev= 30
  4198.7  384.81  4208.7  383.50  4268.9  381.13  4327.6  377.31  4399.1  374.10
  4489.3  374.29  4551.2  369.78  4579.5  367.85  4649.6  365.61  4932.0  366.50
  4950.2  365.90  4970.2  363.50  4986.6  358.03  4987.1  357.53  4994.0  358.03
  4997.8  361.33  5002.9  361.33  5010.6  363.52  5031.2  362.48  5072.4  363.15
  5082.8  362.20  5093.1  362.66  5113.7  367.92  5159.8  368.20  5299.2  368.83
  5505.4  372.62  5683.2  379.64  5732.1  383.33  5804.7  387.00  5824.9  388.15
#Mann=8,-1,0
  4198.7    0.07       0  4327.6    0.12       0  4551.2    0.07       0
  4932.0    0.12       0  4986.6    0.05       0  4994.0    0.12       0
  5159.8    0.05       0  5804.7    0.12       0
Bank Sta=4986.6,4994
Exp/Cntr=0.3,0.1

Type RM Length L Ch R = 1,3686,485,485,485
BEGIN DESCRIPTION:
Stream0428 7.0
END DESCRIPTION:
XS GIS Cut Line= 3
      2466125.03     13793975.02      2466525.00     13794175.00
      2467025.02     13794275.00
#Sta/Elev= 30
  4553.8  376.95  4562.2  376.76  4576.1  375.27  4606.9  370.45  4639.7  368.06
  4718.7  365.05  4808.1  364.70  4830.5  365.25  4958.4  365.35  4978.6  364.17
  4987.0  361.29  4992.6  360.40  4994.5  356.79  4995.0  356.29  5001.4  356.29
  5001.9  356.79  5003.5  356.79  5011.2  359.86  5021.4  361.84  5047.9  361.90
  5104.6  361.45  5174.3  364.00  5215.1  363.69  5225.3  362.71  5235.5  362.96
  5255.9  359.65  5276.3  363.31  5354.0  367.04  5449.7  371.31  5510.9  371.76
#Mann=8,-1,0
  4553.8    0.12       0  4639.7    0.07       0  4958.4    0.12       0
  4994.5    0.05       0  5001.9    0.12       0  5047.9    0.07       0
  5104.6    0.12       0  5354.0    0.05       0
Bank Sta=4994.5,5001.9
Exp/Cntr=0.3,0.1

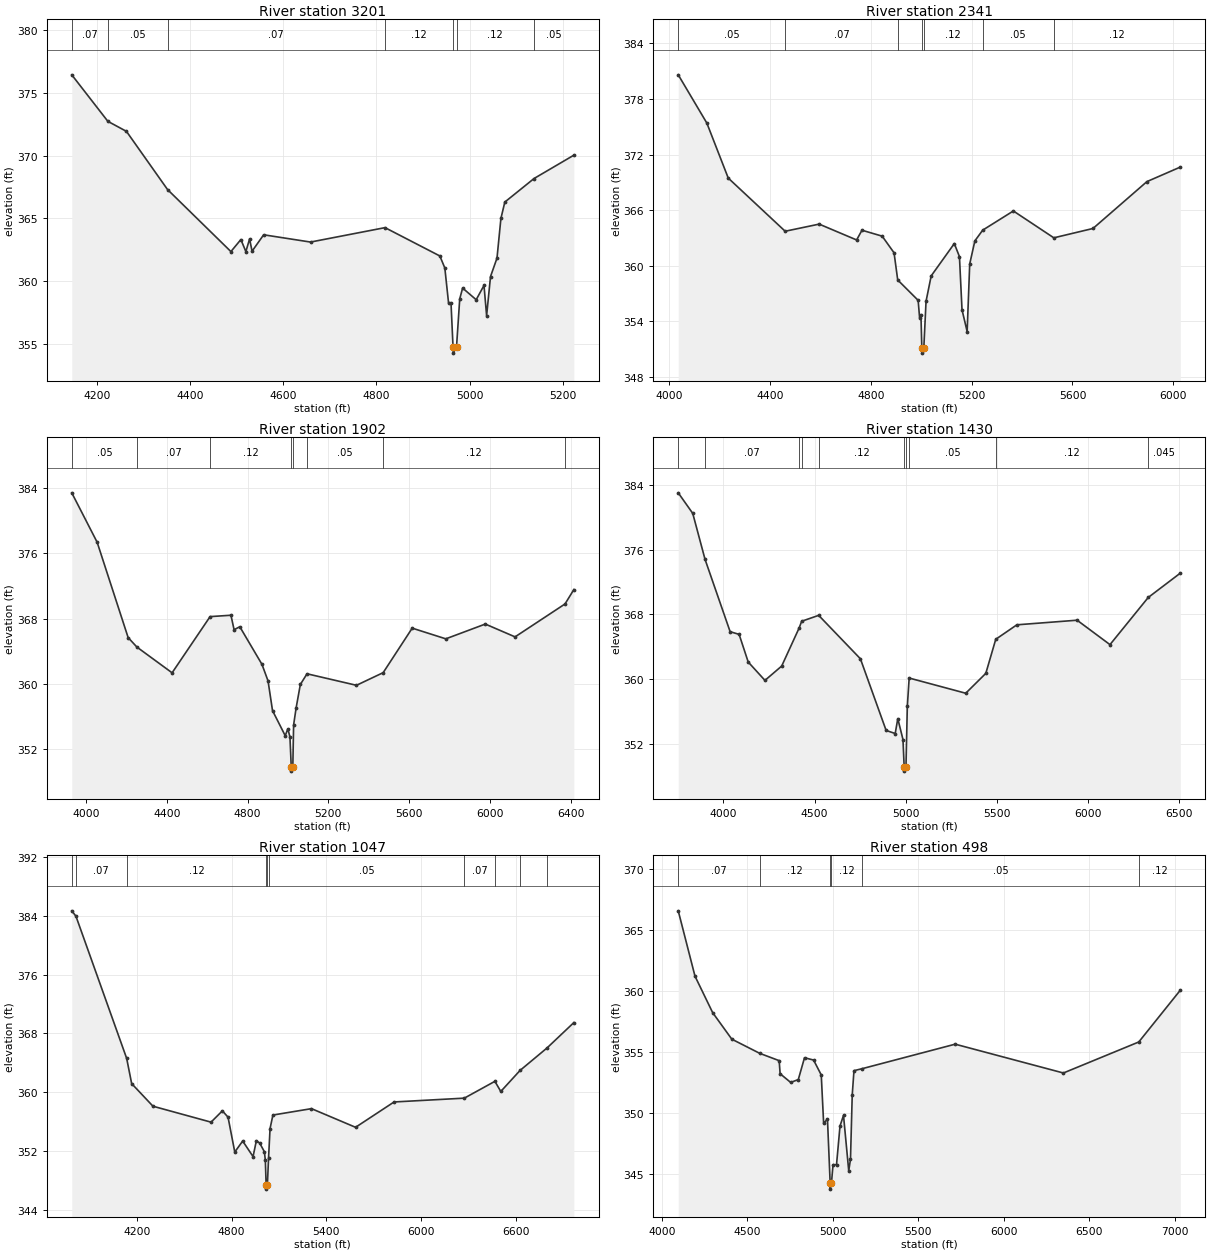
Type RM Length L Ch R = 1,3201,860,860,860
BEGIN DESCRIPTION:
Stream0428 6.0
END DESCRIPTION:
XS GIS Cut Line= 3
      2465975.05     13794175.02      2466775.00     13794475.00
      2466975.04     13794374.98
#Sta/Elev= 30
  4146.0  376.46  4223.5  372.75  4263.4  371.95  4351.6  367.31  4487.7  362.36
  4509.1  363.32  4519.8  362.36  4527.8  363.37  4533.1  362.39  4558.0  363.70
  4658.6  363.12  4818.6  364.27  4936.3  362.01  4947.0  361.05  4955.0  358.26
  4960.3  358.23  4964.6  354.76  4965.1  354.26  4972.1  354.76  4979.0  358.59
  4985.2  359.45  5014.3  358.52  5031.1  359.66  5036.7  357.25  5045.1  360.37
  5059.0  361.84  5067.4  365.00  5075.8  366.31  5138.6  368.19  5224.0  370.05
#Mann=7,-1,0
  4146.0    0.07       0  4223.5    0.05       0  4351.6    0.07       0
  4818.6    0.12       0  4964.6    0.05       0  4972.1    0.12       0
  5138.6    0.05       0
Bank Sta=4964.6,4972.1
Exp/Cntr=0.3,0.1

Type RM Length L Ch R = 1,2341,439,439,439
BEGIN DESCRIPTION:
Stream0428 5.0
END DESCRIPTION:
XS GIS Cut Line= 3
      2465608.02     13794447.18      2466525.00     13794775.00
      2467524.98     13794975.00
#Sta/Elev= 30
  4034.7  380.61  4148.3  375.40  4233.3  369.46  4459.3  363.72  4594.3  364.49
  4743.0  362.78  4764.3  363.83  4844.5  363.19  4891.7  361.39  4906.2  358.46
  4987.3  356.26  4993.1  354.38  4998.4  354.72  5002.0  351.06  5002.5  350.56
  5009.7  351.06  5018.7  356.16  5039.1  358.90  5130.9  362.39  5151.3  360.98
  5161.5  355.24  5181.9  352.89  5192.1  360.19  5212.5  362.68  5243.7  363.84
  5365.4  365.91  5526.1  363.01  5681.6  364.02  5895.7  369.08  6028.3  370.65
#Mann=7,-1,0
  4034.7    0.05       0  4459.3    0.07       0  4906.2    0.12       0
  5002.0    0.05       0  5009.7    0.12       0  5243.7    0.05       0
  5526.1    0.12       0
Bank Sta=5002,5009.7
Exp/Cntr=0.3,0.1

Type RM Length L Ch R = 1,1902,472,472,472
BEGIN DESCRIPTION:
Stream0428 4.0
END DESCRIPTION:
XS GIS Cut Line= 3
      2465551.26     13794555.86      2466425.63     13795080.48
      2467850.98     13795429.74
#Sta/Elev= 30
  3929.1  383.41  4054.8  377.36  4208.4  365.68  4251.9  364.52  4426.1  361.37
  4614.3  368.25  4717.6  368.42  4733.2  366.65  4761.5  367.01  4871.2  362.41
  4901.4  360.38  4923.6  356.74  4986.5  353.67  4999.6  354.51  5009.9  353.51
  5016.4  349.83  5016.9  349.33  5024.1  349.83  5028.1  354.99  5040.8  357.11
  5061.4  359.94  5094.5  361.25  5339.4  359.84  5471.8  361.39  5615.6  366.84
  5782.0  365.53  5977.7  367.34  6125.1  365.77  6372.5  369.80  6416.3  371.56
#Mann=8,-1,0
  3929.1    0.05       0  4251.9    0.07       0  4614.3    0.12       0
  5016.4    0.05       0  5024.1    0.12       0  5094.5    0.05       0
  5471.8    0.12       0  6372.5   0.045       0
Bank Sta=5016.4,5024.1
Exp/Cntr=0.3,0.1

Type RM Length L Ch R = 1,1430,383,383,383
BEGIN DESCRIPTION:
Stream0428 3.0
END DESCRIPTION:
XS GIS Cut Line= 3
      2465560.73     13794626.75      2466475.00     13795475.00
      2467980.31     13795567.26
#Sta/Elev= 30
  3752.0  383.02  3831.6  380.48  3899.0  374.80  4036.8  365.85  4086.1  365.52
  4136.0  362.10  4227.9  359.83  4319.7  361.60  4415.9  366.33  4429.4  367.14
  4522.7  367.87  4751.7  362.50  4892.9  353.64  4942.7  353.26  4956.9  355.10
  4985.3  352.52  4991.9  349.11  4992.4  348.61  4999.6  349.11  5001.7  349.11
  5009.2  356.62  5019.3  360.12  5329.8  358.24  5440.0  360.70  5494.4  364.91
  5610.3  366.70  5940.9  367.27  6121.3  364.25  6331.2  370.08  6507.3  373.09
#Mann=10,-1,0
  3752.0    0.05       0  3899.0    0.07       0  4415.9    0.12       0
  4429.4    0.07       0  4522.7    0.12       0  4991.9    0.05       0
  4999.6    0.12       0  5019.3    0.05       0  5494.4    0.12       0
  6331.2   0.045       0
Bank Sta=4991.9,4999.6
Exp/Cntr=0.3,0.1

Type RM Length L Ch R = 1,1047,549,549,549
BEGIN DESCRIPTION:
Stream0428 2.0
END DESCRIPTION:
XS GIS Cut Line= 3
      2465532.40     13794721.31      2466250.76     13795775.22
      2468124.96     13796124.99
#Sta/Elev= 30
  3786.8  384.70  3813.2  383.97  4134.8  364.60  4166.4  361.17  4301.5  358.09
  4669.5  355.92  4741.3  357.46  4777.2  356.60  4819.9  351.85  4870.0  353.35
  4935.8  351.23  4956.7  353.40  4977.7  353.07  5007.6  351.89  5013.6  350.73
  5018.7  347.30  5019.2  346.80  5026.4  347.30  5033.9  351.03  5043.5  355.05
  5061.6  356.89  5306.0  357.76  5585.4  355.22  5829.5  358.67  6274.7  359.19
  6468.4  361.48  6505.8  360.10  6628.2  362.97  6798.6  366.02  6968.8  369.48
#Mann=10,-1,0
  3786.8    0.05       0  3813.2    0.07       0  4134.8    0.12       0
  5018.7    0.05       0  5026.4    0.12       0  5033.9    0.05       0
  6274.7    0.07       0  6468.4    0.12       0  6628.2   0.045       0
  6798.6    0.07       0
Bank Sta=5018.7,5026.4
Exp/Cntr=0.3,0.1

Type RM Length L Ch R = 1,498,0,0,0
BEGIN DESCRIPTION:
Stream0428 1.0
END DESCRIPTION:
XS GIS Cut Line= 3
      2465424.99     13795124.98      2465825.00     13795925.00
      2467825.04     13796325.01
#Sta/Elev= 30
  4096.7  366.56  4194.6  361.21  4298.0  358.22  4409.8  356.05  4572.9  354.89
  4686.5  354.29  4692.1  353.22  4753.6  352.51  4798.3  352.74  4834.6  354.53
  4887.7  354.34  4932.5  353.12  4946.4  349.16  4968.8  349.51  4984.5  344.27
  4985.0  343.77  4992.2  344.27  5001.3  345.77  5021.7  345.77  5042.1  348.94
  5062.5  349.81  5093.1  345.27  5103.3  346.21  5113.5  351.48  5123.7  353.47
  5173.2  353.64  5715.2  355.64  6347.5  353.28  6788.1  355.82  7030.8  360.06
#Mann=6,-1,0
  4096.7    0.07       0  4572.9    0.12       0  4984.5    0.05       0
  4992.2    0.12       0  5173.2    0.05       0  6788.1    0.12       0
Bank Sta=4984.5,4992.2
Exp/Cntr=0.3,0.1

Chan Stop Cuts=-1