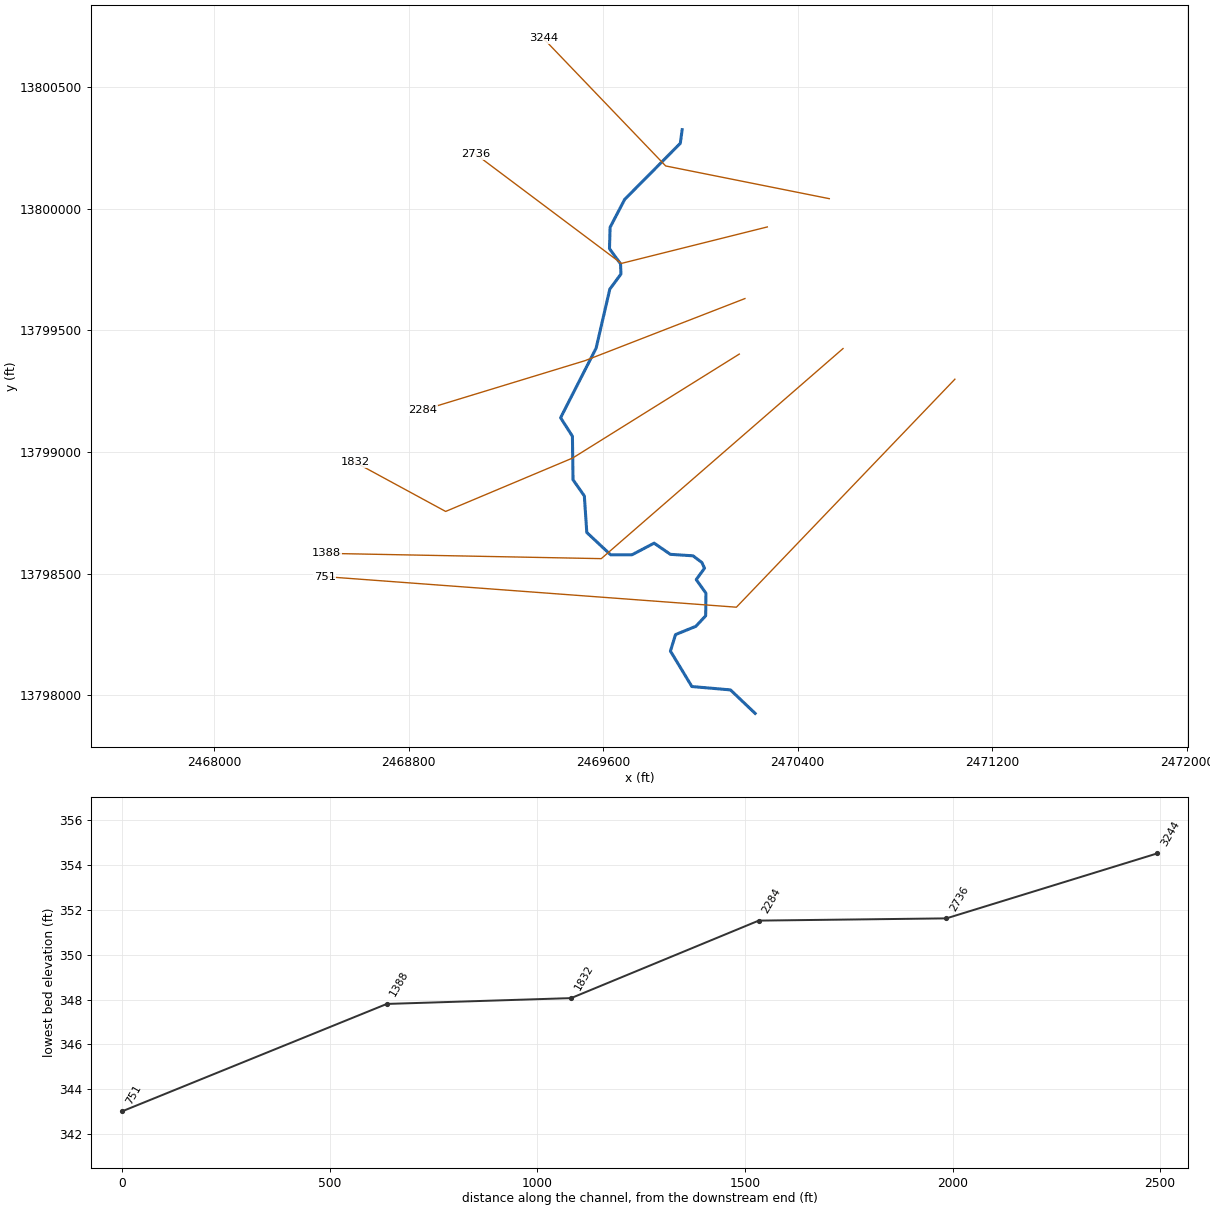
--- Stream0429.prj (project) ---

Proj Title=Stream0429 Base Level Engineering
Current Plan=p01
Default Exp/Contr=0.3,0.1
English Units
Geom File=g01
Flow File=f01
Plan File=p01
BEGIN DESCRIPTION:
Stream0429
END DESCRIPTION:

--- Stream0429.p01 (plan) ---

Plan Title=Multiple Run
Short Identifier=Multiple
Geom File=g01
Flow File=f01
Subcritical Flow
K Sum by GR= 0
Std Step Tol= 0.01
Critical Tol= 0.01
Num of Std Step Trials= 20
Max Error Tol= 0.3
Flow Tol Ratio= 0.001
Split Flow NTrial= 30
Split Flow Tol= 0.02
Split Flow Ratio= 0.02
Log Output Level= 0
Friction Slope Method= 1
Unsteady Friction Slope Method= 2
Unsteady Bridges Friction Slope Method= 1
Parabolic Critical Depth
Global Vel Dist=  1 , 1 , 1
Global Log Level= 0
CheckData=True
Encroach Param= -1, 0, 0, 0
BEGIN DESCRIPTION:
Multiple Run
END DESCRIPTION:

--- Stream0429.f01 (steady flow) ---

Flow Title=Multiple
Number of Profiles=7
Profile Names=10-year,25-year,50-year,1pct_min,100-year,1pct_plu,500-year
River Rch & RM= Stream0429,Reach-1,3244
     766    1237    1663    1082    2160    4310    3606
Boundary for River Rch & Prof#=Stream0429,Reach-1,1
Up Type=0
Dn Type=3
Dn Slope=0.005
Boundary for River Rch & Prof#=Stream0429,Reach-1,2
Up Type=0
Dn Type=3
Dn Slope=0.005
Boundary for River Rch & Prof#=Stream0429,Reach-1,3
Up Type=0
Dn Type=3
Dn Slope=0.005
Boundary for River Rch & Prof#=Stream0429,Reach-1,4
Up Type=0
Dn Type=3
Dn Slope=0.005
Boundary for River Rch & Prof#=Stream0429,Reach-1,5
Up Type=0
Dn Type=3
Dn Slope=0.005
Boundary for River Rch & Prof#=Stream0429,Reach-1,6
Up Type=0
Dn Type=3
Dn Slope=0.005
Boundary for River Rch & Prof#=Stream0429,Reach-1,7
Up Type=0
Dn Type=3
Dn Slope=0.005

--- Stream0429.g01 (geometry) ---

Geom Title=Existing Conditions

River Reach=Stream0429,Reach-1
Reach XY= 30
      2469925.00     13800325.00      2469917.24     13800268.79
      2469688.62     13800038.22      2469628.67     13799923.42
      2469626.12     13799835.54      2469671.62     13799773.27
      2469673.18     13799731.12      2469627.38     13799669.03
      2469571.17     13799426.58      2469425.09     13799140.40
      2469473.76     13799064.50      2469476.22     13798885.51
      2469522.73     13798819.06      2469532.81     13798668.79
      2469630.88     13798576.96      2469719.03     13798577.19
      2469809.61     13798624.91      2469876.59     13798578.89
      2469969.50     13798572.85      2470005.83     13798545.48
      2470016.94     13798521.88      2469982.81     13798475.11
      2470022.65     13798419.10      2470021.62     13798326.28
      2469981.36     13798283.03      2469897.56     13798248.84
      2469876.74     13798181.16      2469964.88     13798035.35
      2470123.55     13798021.51      2470225.00     13797925.00

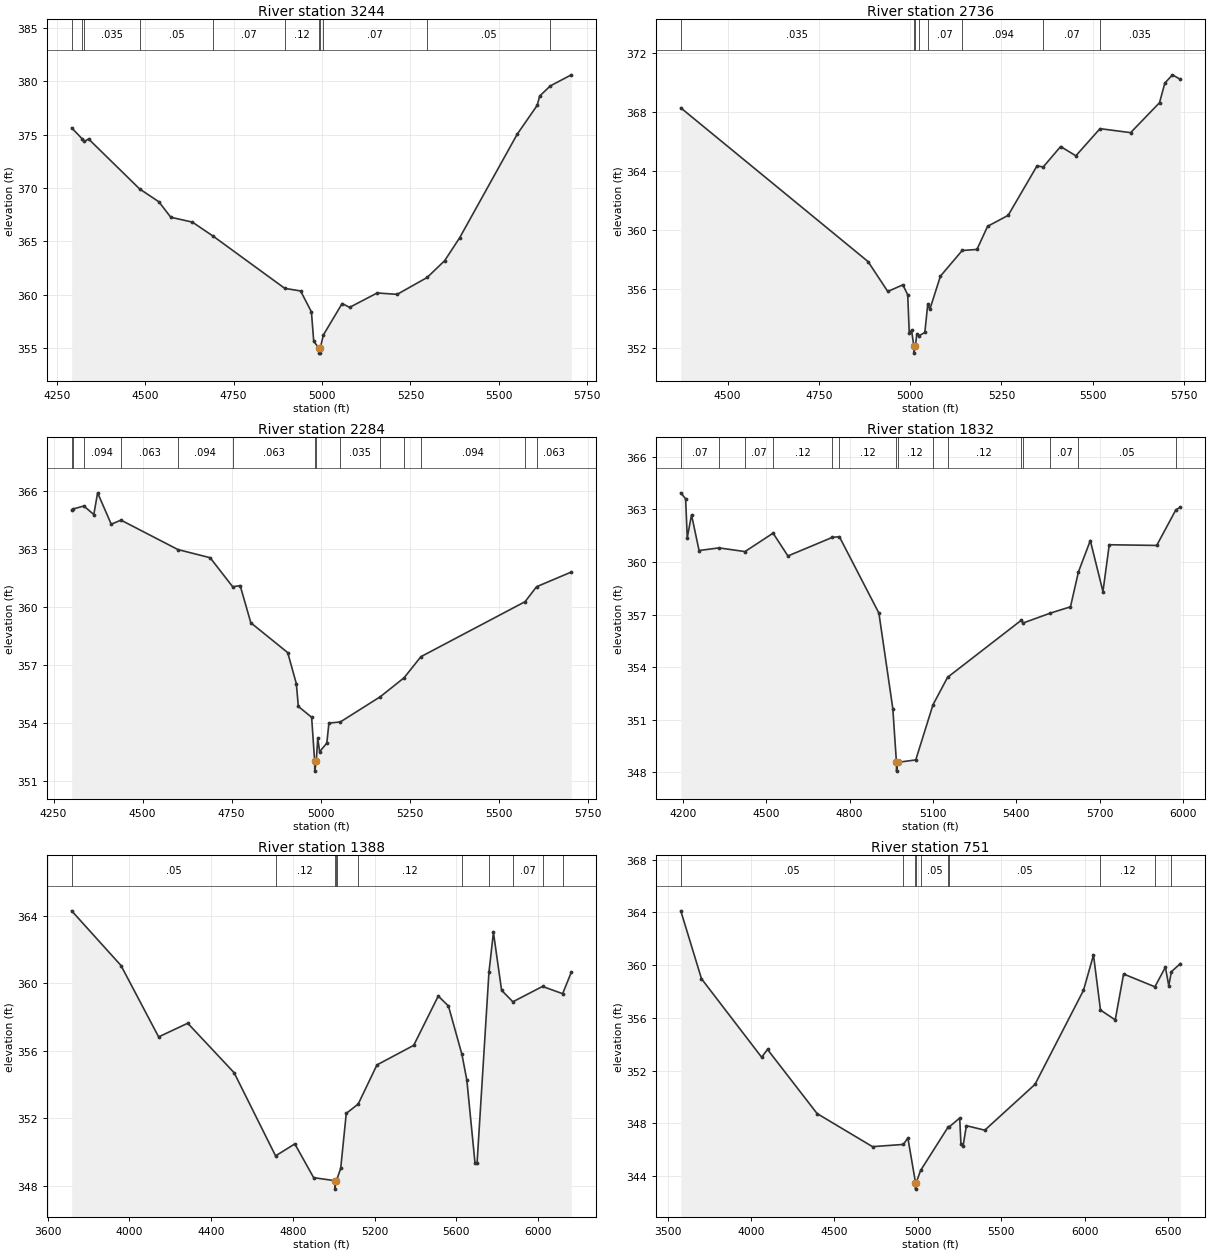
Type RM Length L Ch R = 1,3244,508,508,508
BEGIN DESCRIPTION:
Stream0429 5.0
END DESCRIPTION:
XS GIS Cut Line= 3
      2470529.87     13800041.23      2469857.12     13800175.78
      2469354.13     13800700.45
#Sta/Elev= 30
  4291.8  375.65  4321.3  374.63  4327.8  374.37  4339.6  374.61  4484.1  369.92
  4538.4  368.72  4572.1  367.27  4633.3  366.81  4692.6  365.48  4894.6  360.60
  4939.2  360.36  4969.8  358.40  4976.4  355.63  4990.7  355.03  4991.0  354.53
  4994.7  354.53  4995.0  355.03  5003.6  356.23  5056.7  359.18  5077.8  358.82
  5155.8  360.17  5212.3  360.04  5297.0  361.62  5346.7  363.20  5389.1  365.35
  5551.7  375.05  5608.3  377.76  5615.2  378.63  5645.3  379.58  5704.7  380.62
#Mann=11,-1,0
  4291.8   0.035       0  4321.3   0.063       0  4327.8   0.035       0
  4484.1    0.05       0  4692.6    0.07       0  4894.6    0.12       0
  4990.7    0.05       0  4995.0    0.12       0  5003.6    0.07       0
  5297.0    0.05       0  5645.3   0.035       0
Bank Sta=4990.7,4995
Exp/Cntr=0.3,0.1

Type RM Length L Ch R = 1,2736,452,452,452
BEGIN DESCRIPTION:
Stream0429 4.0
END DESCRIPTION:
XS GIS Cut Line= 3
      2470274.96     13799924.99      2469675.00     13799775.00
      2469075.02     13800224.99
#Sta/Elev= 30
  4371.9  368.26  4884.7  357.84  4938.8  355.81  4980.0  356.26  4993.4  355.59
  4997.6  352.99  5003.9  353.18  5010.0  352.13  5010.3  351.63  5014.4  352.13
  5018.4  352.92  5024.3  352.81  5040.3  353.03  5048.4  354.98  5053.9  354.59
  5083.0  356.85  5142.6  358.59  5183.0  358.66  5212.2  360.23  5268.4  360.97
  5347.6  364.33  5364.5  364.25  5412.2  365.64  5453.9  365.01  5520.0  366.85
  5603.9  366.58  5683.0  368.61  5697.6  369.94  5718.4  370.50  5740.3  370.19
#Mann=8,-1,0
  4371.9   0.035       0  5010.0   0.035       0  5014.4   0.035       0
  5024.3   0.094       0  5048.4    0.07       0  5142.6   0.094       0
  5364.5    0.07       0  5520.0   0.035       0
Bank Sta=5010,5014.4
Exp/Cntr=0.3,0.1

Type RM Length L Ch R = 1,2284,452,452,452
BEGIN DESCRIPTION:
Stream0429 3.0
END DESCRIPTION:
XS GIS Cut Line= 3
      2470182.98     13799630.48      2469525.00     13799375.00
      2468858.57     13799171.64
#Sta/Elev= 30
  4300.9  365.02  4305.9  365.07  4335.0  365.22  4363.1  364.78  4373.8  365.90
  4412.0  364.28  4439.5  364.49  4599.3  362.97  4689.6  362.55  4753.0  361.05
  4774.0  361.11  4803.9  359.19  4907.4  357.65  4931.6  356.05  4937.3  354.87
  4974.6  354.31  4983.1  352.03  4983.4  351.53  4987.5  352.03  4991.8  353.23
  4997.1  352.53  5017.2  352.98  5023.1  354.01  5055.2  354.07  5167.2  355.37
  5234.1  356.35  5281.4  357.44  5573.8  360.28  5605.9  361.05  5703.5  361.81
#Mann=14,-1,0
  4300.9   0.063       0  4305.9   0.035       0  4335.0   0.094       0
  4439.5   0.063       0  4599.3   0.094       0  4753.0   0.063       0
  4983.1    0.05       0  4987.5   0.063       0  5055.2   0.035       0
  5167.2   0.063       0  5234.1     0.1       0  5281.4   0.094       0
  5573.8   0.035       0  5605.9   0.063       0
Bank Sta=4983.1,4987.5
Exp/Cntr=0.3,0.1

Type RM Length L Ch R = 1,1832,444,444,444
BEGIN DESCRIPTION:
Stream0429 2.0
END DESCRIPTION:
XS GIS Cut Line= 4
      2470159.84     13799402.28      2469475.00     13798975.00
      2468952.50     13798755.28      2468579.93     13798957.45
#Sta/Elev= 30
  4192.8  363.94  4210.2  363.60  4216.1  361.38  4231.4  362.68  4258.6  360.65
  4330.1  360.80  4423.8  360.59  4524.9  361.64  4578.3  360.34  4738.2  361.40
  4763.4  361.44  4905.7  357.08  4955.8  351.63  4968.8  348.57  4969.1  348.07
  4973.3  348.57  5038.3  348.71  5100.2  351.85  5152.8  353.42  5416.9  356.66
  5425.2  356.52  5522.5  357.08  5595.0  357.44  5623.7  359.43  5666.4  361.22
  5711.9  358.31  5734.6  360.98  5905.3  360.94  5974.3  362.97  5990.7  363.12
#Mann=15,-1,0
  4192.8    0.07       0  4330.1    0.12       0  4423.8    0.07       0
  4524.9    0.12       0  4738.2    0.07       0  4763.4    0.12       0
  4968.8    0.05       0  4973.3    0.12       0  5100.2   0.094       0
  5152.8    0.12       0  5416.9    0.05       0  5425.2    0.12       0
  5522.5    0.07       0  5623.7    0.05       0  5974.3   0.035       0
Bank Sta=4968.8,4973.3
Exp/Cntr=0.3,0.1

Type RM Length L Ch R = 1,1388,637,637,637
BEGIN DESCRIPTION:
XS6775
END DESCRIPTION:
XS GIS Cut Line= 3
      2470586.28     13799424.91      2469592.36     13798561.20
      2468463.93     13798582.90
#Sta/Elev= 30
  3717.1  364.30  3958.6  361.06  4142.8  356.83  4285.3  357.64  4512.2  354.71
  4715.2  349.78  4809.4  350.49  4901.5  348.49  5005.5  348.31  5005.9  347.81
  5010.1  348.31  5016.4  348.43  5033.9  349.04  5061.2  352.30  5119.5  352.85
  5211.3  355.17  5391.3  356.33  5511.3  359.25  5561.3  358.66  5627.3  355.79
  5651.3  354.27  5691.3  349.35  5701.3  349.35  5759.5  360.66  5781.4  363.02
  5821.4  359.59  5876.6  358.91  6021.6  359.82  6120.1  359.39  6162.5  360.66
#Mann=11,-1,0
  3717.1    0.05       0  4715.2    0.12       0  5005.5    0.05       0
  5010.1    0.12       0  5016.4    0.05       0  5119.5    0.12       0
  5627.3    0.07       0  5759.5    0.12       0  5876.6    0.07       0
  6021.6   0.035       0  6120.1    0.07       0
Bank Sta=5005.5,5010.1
Exp/Cntr=0.3,0.1

Type RM Length L Ch R = 1,751,0,0,0
BEGIN DESCRIPTION:
Stream0429 1.0
END DESCRIPTION:
XS GIS Cut Line= 3
      2471046.34     13799299.03      2470147.92     13798361.55
      2468455.17     13798487.42
#Sta/Elev= 30
  3579.1  364.12  3703.2  358.97  4063.9  353.02  4099.1  353.61  4396.3  348.75
  4728.7  346.24  4913.8  346.41  4940.7  346.90  4986.4  343.52  4986.7  343.02
  4991.0  343.52  5017.2  344.44  5183.7  347.76  5186.8  347.72  5251.5  348.41
  5258.9  346.43  5271.6  346.28  5291.6  347.83  5401.9  347.49  5702.8  350.96
  5993.6  358.09  6053.7  360.77  6095.6  356.60  6184.1  355.85  6234.2  359.33
  6421.9  358.36  6484.9  359.85  6505.0  358.44  6520.9  359.51  6575.0  360.12
#Mann=10,-1,0
  3579.1    0.05       0  4913.8     0.1       0  4986.4    0.05       0
  4991.0     0.1       0  5017.2    0.05       0  5183.7    0.12       0
  5186.8    0.05       0  6095.6    0.12       0  6421.9   0.035       0
  6520.9    0.07       0
Bank Sta=4986.4,4991
Exp/Cntr=0.3,0.1

Chan Stop Cuts=-1