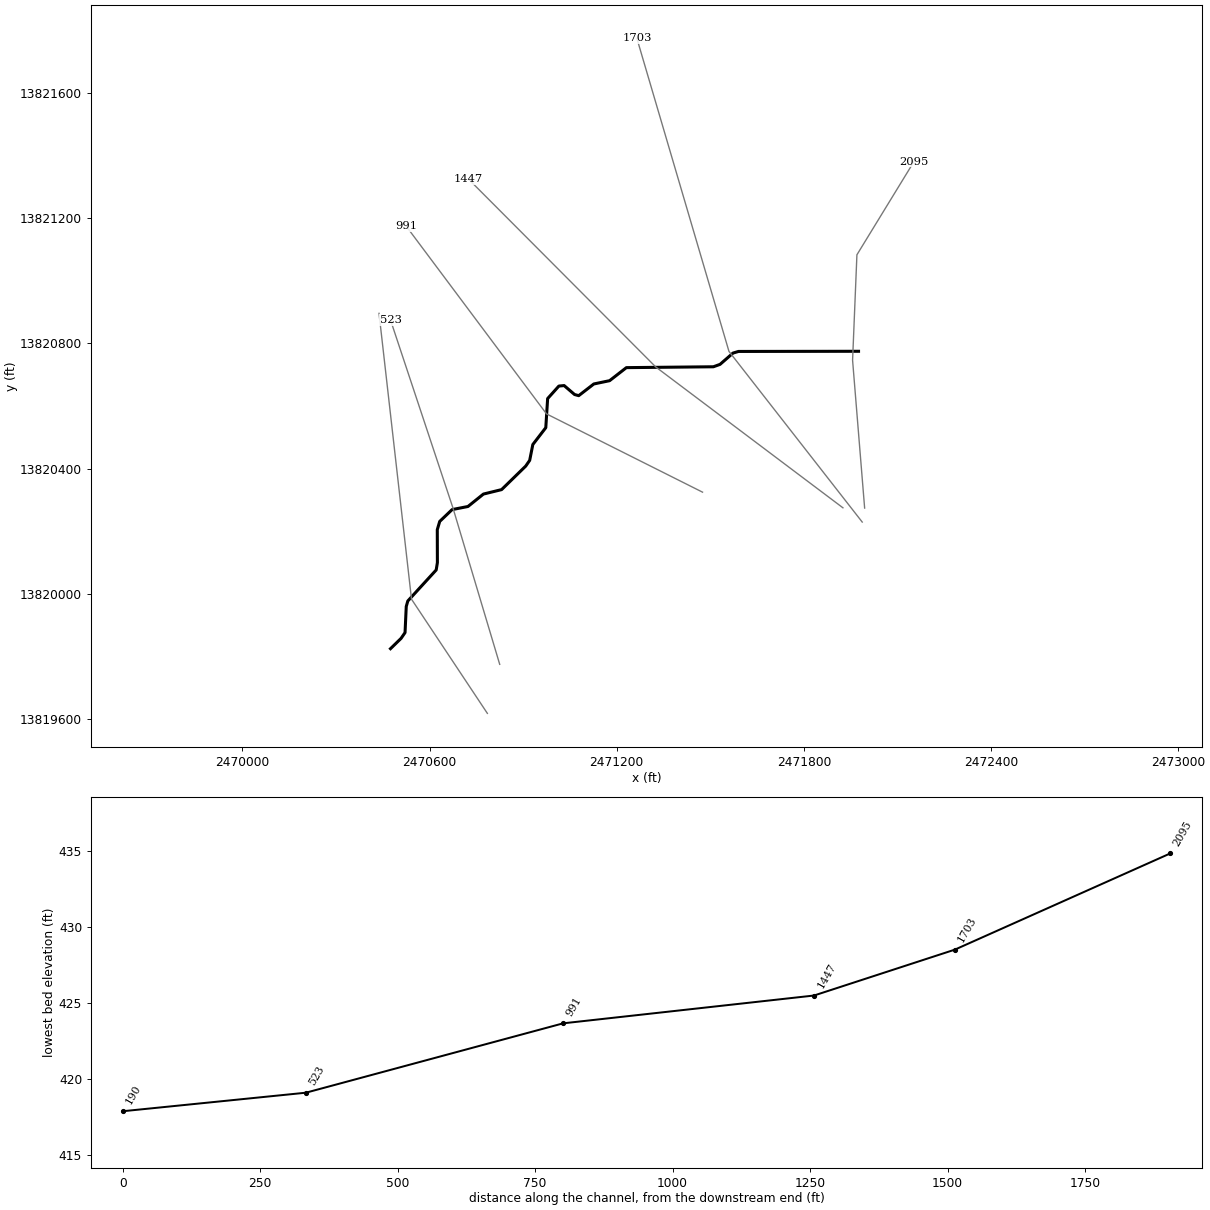
--- Stream0434.prj (project) ---

Proj Title=Stream0434 Base Level Engineering
Current Plan=p01
Default Exp/Contr=0.3,0.1
English Units
Geom File=g01
Flow File=f01
Plan File=p01
BEGIN DESCRIPTION:
Stream0434
END DESCRIPTION:

--- Stream0434.p01 (plan) ---

Plan Title=Multiple Run
Short Identifier=Multiple
Geom File=g01
Flow File=f01
Subcritical Flow
K Sum by GR= 0
Std Step Tol= 0.01
Critical Tol= 0.01
Num of Std Step Trials= 20
Max Error Tol= 0.3
Flow Tol Ratio= 0.001
Split Flow NTrial= 30
Split Flow Tol= 0.02
Split Flow Ratio= 0.02
Log Output Level= 0
Friction Slope Method= 1
Unsteady Friction Slope Method= 2
Unsteady Bridges Friction Slope Method= 1
Parabolic Critical Depth
Global Vel Dist=  1 , 1 , 1
Global Log Level= 0
CheckData=True
Encroach Param= -1, 0, 0, 0
BEGIN DESCRIPTION:
Multiple Run
END DESCRIPTION:

--- Stream0434.f01 (steady flow) ---

Flow Title=Multiple
Number of Profiles=7
Profile Names=10-year,25-year,50-year,1pct_min,100-year,1pct_plu,500-year
River Rch & RM= Stream0434,Reach-1,2095
     219     326     416     258     515    1027     777
Boundary for River Rch & Prof#=Stream0434,Reach-1,1
Up Type=0
Dn Type=3
Dn Slope=0.005
Boundary for River Rch & Prof#=Stream0434,Reach-1,2
Up Type=0
Dn Type=3
Dn Slope=0.005
Boundary for River Rch & Prof#=Stream0434,Reach-1,3
Up Type=0
Dn Type=3
Dn Slope=0.005
Boundary for River Rch & Prof#=Stream0434,Reach-1,4
Up Type=0
Dn Type=3
Dn Slope=0.005
Boundary for River Rch & Prof#=Stream0434,Reach-1,5
Up Type=0
Dn Type=3
Dn Slope=0.005
Boundary for River Rch & Prof#=Stream0434,Reach-1,6
Up Type=0
Dn Type=3
Dn Slope=0.005
Boundary for River Rch & Prof#=Stream0434,Reach-1,7
Up Type=0
Dn Type=3
Dn Slope=0.005

--- Stream0434.g01 (geometry) ---

Geom Title=Existing Conditions

River Reach=Stream0434,Reach-1
Reach XY= 30
      2471975.00     13820775.00      2471590.22     13820774.48
      2471572.67     13820769.25      2471531.06     13820733.14
      2471509.78     13820725.52      2471230.93     13820722.76
      2471177.17     13820681.09      2471126.63     13820670.59
      2471078.22     13820633.26      2471064.92     13820636.85
      2471031.49     13820665.47      2471014.63     13820663.92
      2470978.61     13820623.97      2470972.67     13820530.97
      2470931.14     13820477.17      2470921.06     13820426.62
      2470908.37     13820408.29      2470831.07     13820333.13
      2470772.81     13820318.90      2470723.23     13820279.20
      2470672.42     13820269.29      2470632.70     13820231.48
      2470624.94     13820205.11      2470625.27     13820099.89
      2470621.44     13820076.47      2470530.52     13819977.43
      2470525.48     13819959.80      2470521.61     13819876.41
      2470508.87     13819857.95      2470475.00     13819825.00

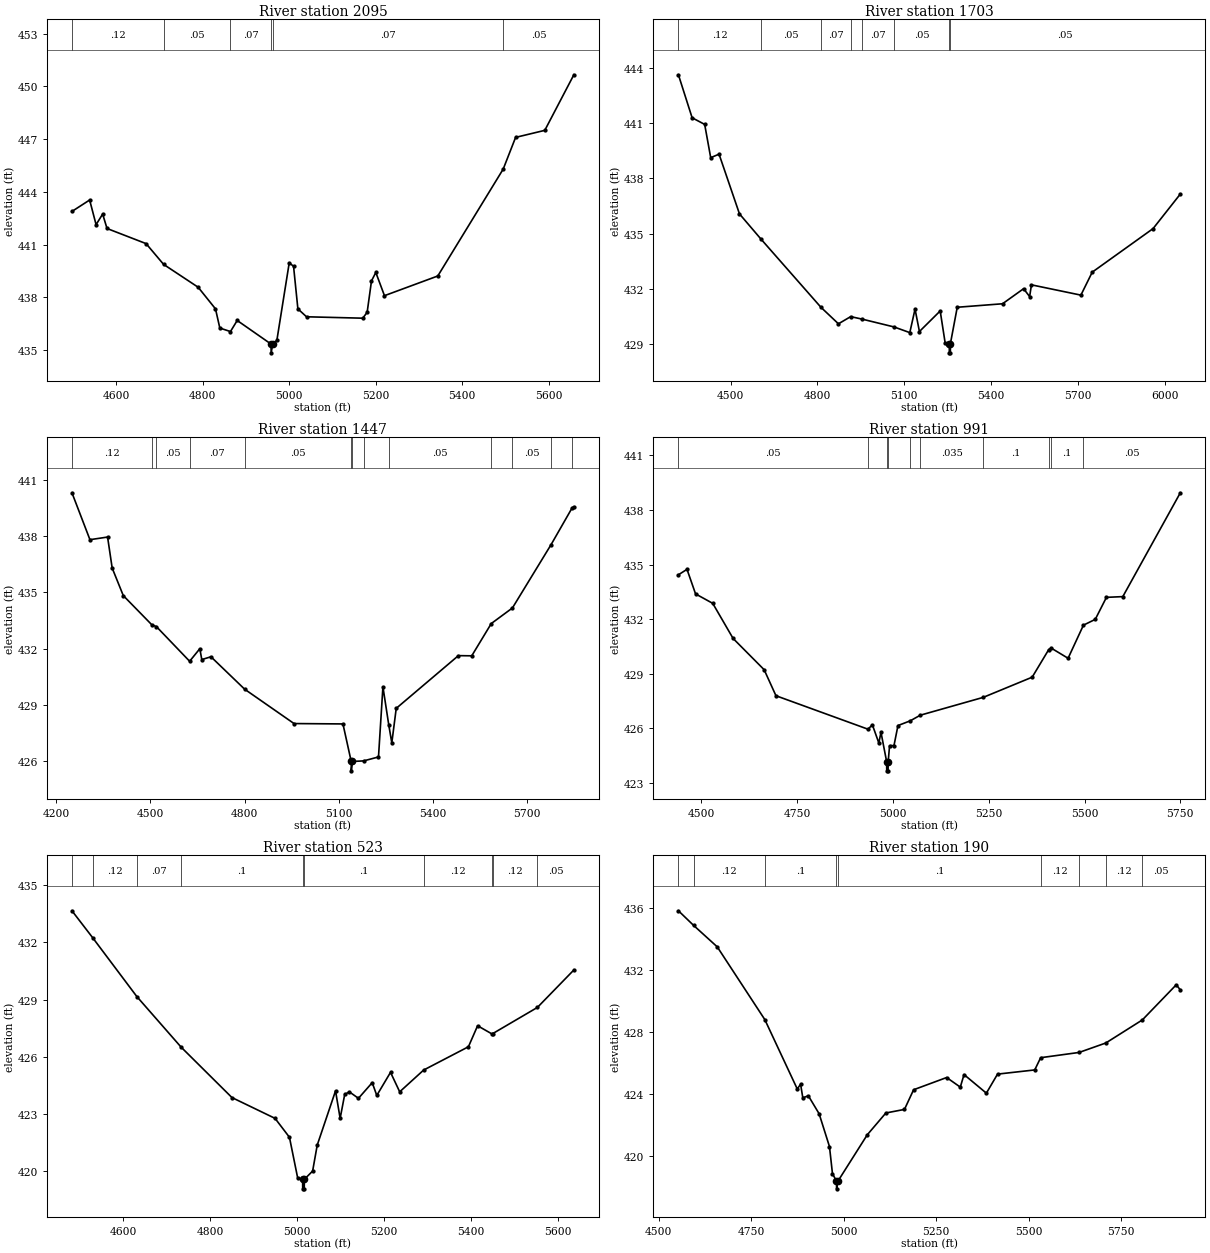
Type RM Length L Ch R = 1,2095,392,392,392
BEGIN DESCRIPTION:
XS6784
END DESCRIPTION:
XS GIS Cut Line= 4
      2471994.53     13820274.20      2471955.90     13820746.41
      2471969.79     13821083.21      2472152.76     13821381.14
#Sta/Elev= 30
  4497.6  442.89  4538.5  443.54  4553.4  442.14  4568.6  442.74  4578.7  441.92
  4669.0  441.06  4709.5  439.88  4789.4  438.58  4829.5  437.35  4839.5  436.26
  4864.1  436.06  4879.7  436.69  4957.9  435.35  4958.2  434.85  4961.9  435.35
  4971.4  435.56  5000.0  439.97  5010.0  439.77  5020.0  437.35  5040.0  436.90
  5170.1  436.82  5180.2  437.16  5190.2  438.94  5200.2  439.42  5220.2  438.10
  5343.5  439.22  5494.8  445.30  5523.4  447.10  5590.9  447.50  5658.1  450.66
#Mann=6,-1,0
  4497.6    0.12       0  4709.5    0.05       0  4864.1    0.07       0
  4957.9    0.05       0  4961.9    0.07       0  5494.8    0.05       0
Bank Sta=4957.9,4961.9
Exp/Cntr=0.3,0.1

Type RM Length L Ch R = 1,1703,256,256,256
BEGIN DESCRIPTION:
Stream0434 4.0
END DESCRIPTION:
XS GIS Cut Line= 3
      2471986.78     13820229.54      2471559.72     13820774.65
      2471264.59     13821774.63
#Sta/Elev= 30
  4319.3  443.64  4366.7  441.30  4410.1  440.94  4430.9  439.13  4459.8  439.32
  4530.4  436.07  4603.6  434.72  4811.9  430.99  4872.5  430.09  4914.8  430.48
  4952.8  430.35  5064.5  429.92  5119.2  429.61  5137.3  430.89  5152.5  429.67
  5224.3  430.79  5241.5  429.04  5255.6  429.01  5255.9  428.51  5259.4  428.51
  5259.6  429.01  5283.2  430.99  5439.8  431.18  5512.6  432.00  5533.5  431.57
  5539.7  432.21  5710.7  431.65  5749.9  432.90  5960.2  435.27  6054.4  437.15
#Mann=8,-1,0
  4319.3    0.12       0  4603.6    0.05       0  4811.9    0.07       0
  4914.8    0.05       0  4952.8    0.07       0  5064.5    0.05       0
  5255.6    0.05       0  5259.6    0.05       0
Bank Sta=5255.6,5259.6
Exp/Cntr=0.3,0.1

Type RM Length L Ch R = 1,1447,456,456,456
BEGIN DESCRIPTION:
Stream0434 3.0
END DESCRIPTION:
XS GIS Cut Line= 3
      2471924.99     13820275.00      2471325.00     13820725.00
      2470725.01     13821324.99
#Sta/Elev= 30
  4249.9  440.31  4307.2  437.81  4363.4  437.95  4378.0  436.30  4413.4  434.83
  4504.5  433.27  4518.7  433.18  4624.7  431.33  4657.2  432.00  4663.4  431.42
  4692.6  431.57  4800.0  429.84  4957.2  428.01  5113.0  427.99  5139.3  425.99
  5139.6  425.49  5143.3  425.99  5178.8  426.02  5226.2  426.23  5240.3  429.97
  5259.0  427.93  5268.6  426.98  5282.7  428.82  5480.7  431.63  5523.2  431.62
  5585.4  433.34  5652.7  434.17  5776.0  437.55  5842.7  439.50  5848.4  439.56
#Mann=13,-1,0
  4249.9    0.12       0  4504.5    0.07       0  4518.7    0.05       0
  4624.7    0.07       0  4800.0    0.05       0  5139.3    0.05       0
  5143.3    0.05       0  5178.8    0.07       0  5259.0    0.05       0
  5585.4    0.07       0  5652.7    0.05       0  5776.0    0.07       0
  5842.7    0.05       0
Bank Sta=5139.3,5143.3
Exp/Cntr=0.3,0.1

Type RM Length L Ch R = 1,991,468,468,468
BEGIN DESCRIPTION:
Stream0434 2.0
END DESCRIPTION:
XS GIS Cut Line= 3
      2471475.02     13820324.99      2470975.00     13820575.00
      2470525.03     13821174.97
#Sta/Elev= 30
  4440.9  434.44  4463.3  434.74  4485.6  433.39  4530.4  432.87  4583.5  430.94
  4664.5  429.22  4695.3  427.79  4935.3  425.95  4946.8  426.19  4963.6  425.19
  4969.2  425.78  4984.0  424.16  4984.2  423.66  4987.7  423.66  4988.0  424.16
  4991.6  425.04  5003.1  425.05  5013.5  426.15  5045.5  426.41  5071.8  426.72
  5235.9  427.70  5363.5  428.81  5406.8  430.33  5413.1  430.41  5457.2  429.85
  5497.2  431.67  5528.1  431.99  5557.2  433.20  5599.9  433.24  5749.9  438.95
#Mann=10,-1,0
  4440.9    0.05       0  4935.3   0.035       0  4984.0   0.035       0
  4988.0   0.035       0  5045.5    0.05       0  5071.8   0.035       0
  5235.9     0.1       0  5406.8   0.035       0  5413.1     0.1       0
  5497.2    0.05       0
Bank Sta=4984,4988
Exp/Cntr=0.3,0.1

Type RM Length L Ch R = 1,523,333,333,333
BEGIN DESCRIPTION:
Stream0434 1.0
END DESCRIPTION:
XS GIS Cut Line= 3
      2470825.00     13819775.00      2470675.00     13820275.00
      2470474.99     13820875.03
#Sta/Elev= 30
  4482.1  433.65  4529.4  432.25  4631.3  429.16  4733.2  426.51  4850.1  423.87
  4949.3  422.78  4982.4  421.79  5001.5  419.64  5012.7  419.59  5012.9  419.09
  5016.4  419.09  5016.7  419.59  5035.7  420.02  5046.3  421.38  5088.4  424.22
  5099.0  422.78  5109.5  424.03  5120.1  424.17  5141.1  423.83  5172.8  424.65
  5183.3  423.98  5214.9  425.19  5236.0  424.17  5291.1  425.31  5394.1  426.53
  5415.2  427.63  5448.3  427.20  5450.1  427.22  5552.8  428.59  5636.6  430.55
#Mann=10,-1,0
  4482.1    0.07       0  4529.4    0.12       0  4631.3    0.07       0
  4733.2     0.1       0  5012.7    0.05       0  5016.7     0.1       0
  5291.1    0.12       0  5448.3     0.1       0  5450.1    0.12       0
  5552.8    0.05       0
Bank Sta=5012.7,5016.7
Exp/Cntr=0.3,0.1

Type RM Length L Ch R = 1,190,0,0,0
BEGIN DESCRIPTION:
XS6785
END DESCRIPTION:
XS GIS Cut Line= 3
      2470785.44     13819618.37      2470542.36     13819982.99
      2470438.20     13820896.15
#Sta/Elev= 30
  4553.1  435.83  4594.0  434.89  4658.1  433.50  4786.8  428.80  4874.5  424.32
  4883.5  424.63  4889.5  423.75  4904.5  423.88  4933.6  422.72  4961.6  420.60
  4969.7  418.85  4980.6  418.37  4980.9  417.87  4984.6  418.37  5063.8  421.36
  5114.1  422.77  5164.4  423.00  5189.1  424.27  5278.5  425.06  5315.4  424.44
  5325.5  425.25  5385.9  424.05  5416.1  425.28  5516.7  425.55  5532.7  426.34
  5636.7  426.68  5708.9  427.29  5807.7  428.78  5899.4  431.05  5910.4  430.72
#Mann=9,-1,0
  4553.1    0.07       0  4594.0    0.12       0  4786.8     0.1       0
  4980.6    0.05       0  4984.6     0.1       0  5532.7    0.12       0
  5636.7     0.1       0  5708.9    0.12       0  5807.7    0.05       0
Bank Sta=4980.6,4984.6
Exp/Cntr=0.3,0.1

Chan Stop Cuts=-1