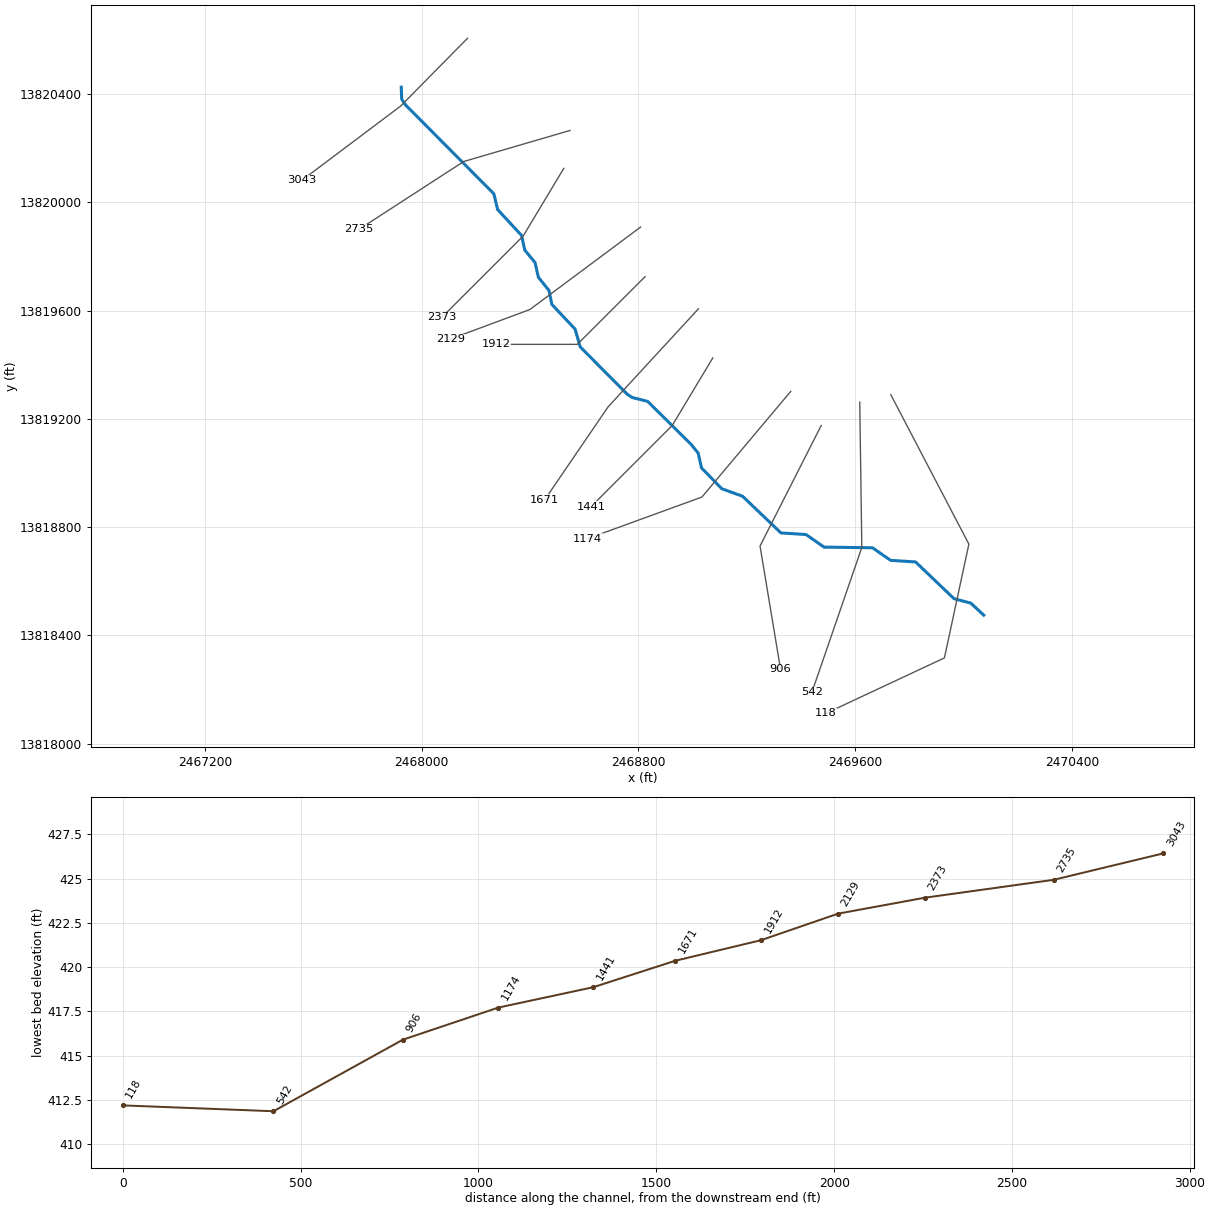
--- Stream0435.prj (project) ---

Proj Title=Stream0435 Base Level Engineering
Current Plan=p01
Default Exp/Contr=0.3,0.1
English Units
Geom File=g01
Flow File=f01
Plan File=p01
BEGIN DESCRIPTION:
Stream0435
END DESCRIPTION:

--- Stream0435.p01 (plan) ---

Plan Title=Multiple Run
Short Identifier=Multiple
Geom File=g01
Flow File=f01
Subcritical Flow
K Sum by GR= 0
Std Step Tol= 0.01
Critical Tol= 0.01
Num of Std Step Trials= 20
Max Error Tol= 0.3
Flow Tol Ratio= 0.001
Split Flow NTrial= 30
Split Flow Tol= 0.02
Split Flow Ratio= 0.02
Log Output Level= 0
Friction Slope Method= 1
Unsteady Friction Slope Method= 2
Unsteady Bridges Friction Slope Method= 1
Parabolic Critical Depth
Global Vel Dist=  1 , 1 , 1
Global Log Level= 0
CheckData=True
Encroach Param= -1, 0, 0, 0
BEGIN DESCRIPTION:
Multiple Run
END DESCRIPTION:

--- Stream0435.f01 (steady flow) ---

Flow Title=Multiple
Number of Profiles=7
Profile Names=10-year,25-year,50-year,1pct_min,100-year,1pct_plu,500-year
River Rch & RM= Stream0435,Reach-1,3043
     531     843    1120     722    1441    2876    2359
Boundary for River Rch & Prof#=Stream0435,Reach-1,1
Up Type=0
Dn Type=3
Dn Slope=0.005
Boundary for River Rch & Prof#=Stream0435,Reach-1,2
Up Type=0
Dn Type=3
Dn Slope=0.005
Boundary for River Rch & Prof#=Stream0435,Reach-1,3
Up Type=0
Dn Type=3
Dn Slope=0.005
Boundary for River Rch & Prof#=Stream0435,Reach-1,4
Up Type=0
Dn Type=3
Dn Slope=0.005
Boundary for River Rch & Prof#=Stream0435,Reach-1,5
Up Type=0
Dn Type=3
Dn Slope=0.005
Boundary for River Rch & Prof#=Stream0435,Reach-1,6
Up Type=0
Dn Type=3
Dn Slope=0.005
Boundary for River Rch & Prof#=Stream0435,Reach-1,7
Up Type=0
Dn Type=3
Dn Slope=0.005

--- Stream0435.g01 (geometry) ---

Geom Title=Existing Conditions

River Reach=Stream0435,Reach-1
Reach XY= 30
      2467925.00     13820425.00      2467926.68     13820381.14
      2467938.47     13820361.73      2468266.84     13820031.05
      2468280.87     13819972.72      2468369.15     13819877.29
      2468381.10     13819822.81      2468418.92     13819777.20
      2468431.08     13819722.80      2468470.81     13819673.26
      2468480.85     13819622.71      2468566.82     13819531.04
      2468585.78     13819465.32      2468758.33     13819291.65
      2468776.65     13819278.98      2468834.68     13819264.22
      2468995.38     13819105.16      2469021.02     13819073.35
      2469033.15     13819018.93      2469108.29     13818941.64
      2469184.68     13818914.22      2469326.50     13818778.61
      2469419.02     13818772.64      2469485.50     13818726.22
      2469664.50     13818723.78      2469730.98     13818677.36
      2469823.50     13818671.39      2469965.29     13818535.70
      2470027.35     13818519.29      2470075.00     13818475.00

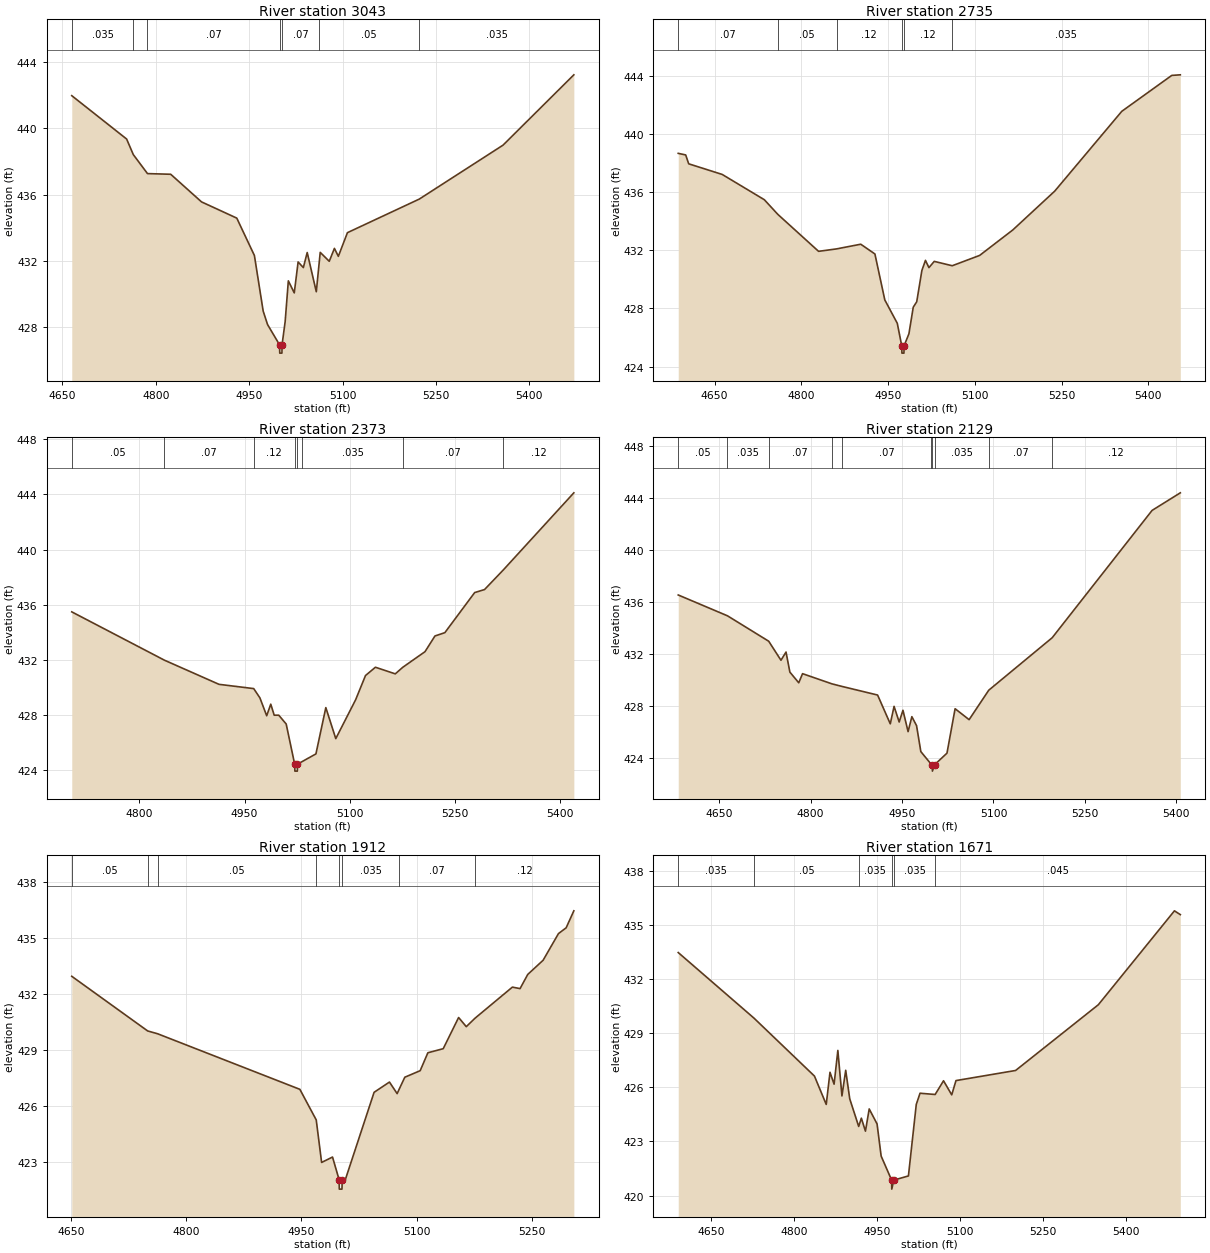
Type RM Length L Ch R = 1,3043,308,308,308
BEGIN DESCRIPTION:
XS6787
END DESCRIPTION:
XS GIS Cut Line= 3
      2468169.47     13820605.23      2467922.92     13820355.21
      2467559.20     13820081.56
#Sta/Elev= 30
  4665.1  441.98  4753.2  439.36  4763.9  438.42  4786.7  437.27  4824.0  437.23
  4873.5  435.56  4930.1  434.58  4958.4  432.32  4972.5  428.96  4979.5  428.15
  4998.8  426.92  4999.1  426.42  5002.6  426.42  5002.8  426.92  5007.8  428.33
  5012.9  430.79  5022.4  430.06  5028.6  431.93  5037.0  431.59  5043.2  432.50
  5057.8  430.13  5061.9  431.68  5064.1  432.51  5078.6  431.97  5086.9  432.75
  5093.2  432.27  5107.8  433.70  5223.2  435.73  5357.7  438.99  5471.4  443.24
#Mann=7,-1,0
  4665.1   0.035       0  4763.9    0.05       0  4786.7    0.07       0
  4998.8    0.05       0  5002.8    0.07       0  5061.9    0.05       0
  5223.2   0.035       0
Bank Sta=4998.8,5002.8
Exp/Cntr=0.3,0.1

Type RM Length L Ch R = 1,2735,362,362,362
BEGIN DESCRIPTION:
Stream0435 6.0
END DESCRIPTION:
XS GIS Cut Line= 3
      2468547.92     13820264.93      2468155.56     13820150.35
      2467770.10     13819900.32
#Sta/Elev= 30
  4587.0  438.67  4599.9  438.56  4605.1  437.95  4663.0  437.22  4735.9  435.48
  4759.3  434.47  4829.7  431.93  4861.0  432.10  4902.6  432.42  4927.1  431.75
  4944.2  428.59  4965.8  426.98  4973.5  425.43  4973.8  424.93  4977.3  424.93
  4977.5  425.43  4985.9  426.26  4993.4  428.09  4999.4  428.46  5008.3  430.61
  5014.5  431.31  5020.5  430.81  5029.7  431.24  5060.8  430.94  5108.2  431.65
  5165.5  433.40  5238.0  436.07  5354.0  441.56  5440.4  444.03  5455.2  444.07
#Mann=6,-1,0
  4587.0    0.07       0  4759.3    0.05       0  4861.0    0.12       0
  4973.5    0.05       0  4977.5    0.12       0  5060.8   0.035       0
Bank Sta=4973.5,4977.5
Exp/Cntr=0.3,0.1

Type RM Length L Ch R = 1,2373,244,244,244
BEGIN DESCRIPTION:
Stream0435 5.0
END DESCRIPTION:
XS GIS Cut Line= 3
      2468524.98     13820124.97      2468375.00     13819875.00
      2468074.99     13819574.99
#Sta/Elev= 30
  4703.7  435.48  4835.9  431.97  4913.6  430.22  4963.1  429.91  4971.9  429.24
  4981.6  427.94  4987.4  428.78  4992.3  427.98  4998.8  427.98  5009.4  427.34
  5021.5  424.42  5021.8  423.92  5025.3  423.92  5025.5  424.42  5032.4  424.62
  5051.8  425.17  5065.9  428.53  5080.1  426.28  5108.4  429.10  5122.5  430.86
  5136.6  431.46  5164.9  430.98  5175.7  431.46  5207.3  432.59  5221.5  433.73
  5235.6  433.97  5278.1  436.88  5292.2  437.10  5318.9  438.52  5419.5  444.12
#Mann=8,-1,0
  4703.7    0.05       0  4835.9    0.07       0  4963.1    0.12       0
  5021.5    0.05       0  5025.5    0.12       0  5032.4   0.035       0
  5175.7    0.07       0  5318.9    0.12       0
Bank Sta=5021.5,5025.5
Exp/Cntr=0.3,0.1

Type RM Length L Ch R = 1,2129,217,217,217
BEGIN DESCRIPTION:
E21034
END DESCRIPTION:
XS GIS Cut Line= 3
      2468808.43     13819908.17      2468399.72     13819603.59
      2468105.60     13819494.27
#Sta/Elev= 30
  4583.0  436.54  4663.8  434.94  4731.4  432.99  4751.5  431.53  4759.8  432.16
  4766.1  430.62  4780.7  429.80  4786.9  430.50  4835.0  429.72  4851.7  429.52
  4910.0  428.86  4930.8  426.65  4937.0  427.99  4945.4  426.79  4951.6  427.69
  4960.0  426.05  4966.2  427.20  4973.9  426.51  4980.9  424.52  4997.5  423.57
  4999.7  423.52  4999.9  423.02  5003.7  423.52  5023.8  424.40  5037.1  427.81
  5060.1  426.97  5092.3  429.23  5196.4  433.26  5360.2  443.03  5406.5  444.38
#Mann=10,-1,0
  4583.0    0.05       0  4663.8   0.035       0  4731.4    0.07       0
  4835.0    0.05       0  4851.7    0.07       0  4997.5   0.035       0
  4999.7   0.035       0  5003.7   0.035       0  5092.3    0.07       0
  5196.4    0.12       0
Bank Sta=4999.7,5003.7
Exp/Cntr=0.3,0.1

Type RM Length L Ch R = 1,1912,241,241,241
BEGIN DESCRIPTION:
Stream0435 4.0
END DESCRIPTION:
XS GIS Cut Line= 3
      2468824.97     13819724.97      2468575.00     13819475.00
      2468275.01     13819475.00
#Sta/Elev= 30
  4651.3  432.93  4750.1  430.00  4763.0  429.85  4948.2  426.87  4969.5  425.23
  4976.5  422.95  4990.7  423.24  4999.3  422.02  4999.5  421.52  5003.0  421.52
  5003.3  422.02  5007.3  422.02  5044.8  426.71  5064.8  427.26  5074.8  426.64
  5077.6  426.89  5084.8  427.52  5104.8  427.87  5114.8  428.83  5134.8  429.05
  5154.8  430.72  5164.8  430.23  5176.1  430.68  5224.8  432.35  5234.8  432.27
  5244.8  433.03  5264.8  433.79  5284.8  435.22  5294.8  435.53  5304.8  436.44
#Mann=8,-1,0
  4651.3    0.05       0  4750.1   0.035       0  4763.0    0.05       0
  4969.5   0.035       0  4999.3   0.035       0  5003.3   0.035       0
  5077.6    0.07       0  5176.1    0.12       0
Bank Sta=4999.3,5003.3
Exp/Cntr=0.3,0.1

Type RM Length L Ch R = 1,1671,230,230,230
BEGIN DESCRIPTION:
E21033
END DESCRIPTION:
XS GIS Cut Line= 3
      2469021.89     13819606.20      2468688.67     13819244.35
      2468454.38     13818900.72
#Sta/Elev= 30
  4590.5  433.46  4727.4  429.83  4836.8  426.62  4858.1  425.05  4864.9  426.83
  4872.3  426.17  4879.1  428.04  4886.5  425.52  4893.3  426.94  4900.6  425.36
  4916.8  423.83  4921.6  424.29  4929.0  423.57  4935.8  424.80  4950.0  423.97
  4957.4  422.19  4976.3  420.86  4976.6  420.36  4980.3  420.86  5006.7  421.09
  5020.9  425.05  5027.7  425.67  5055.0  425.60  5070.2  426.36  5085.0  425.58
  5092.7  426.37  5200.5  426.93  5350.1  430.57  5487.7  435.77  5498.3  435.56
#Mann=6,-1,0
  4590.5   0.035       0  4727.4    0.05       0  4916.8   0.035       0
  4976.3   0.035       0  4980.3   0.035       0  5055.0   0.045       0
Bank Sta=4976.3,4980.3
Exp/Cntr=0.3,0.1

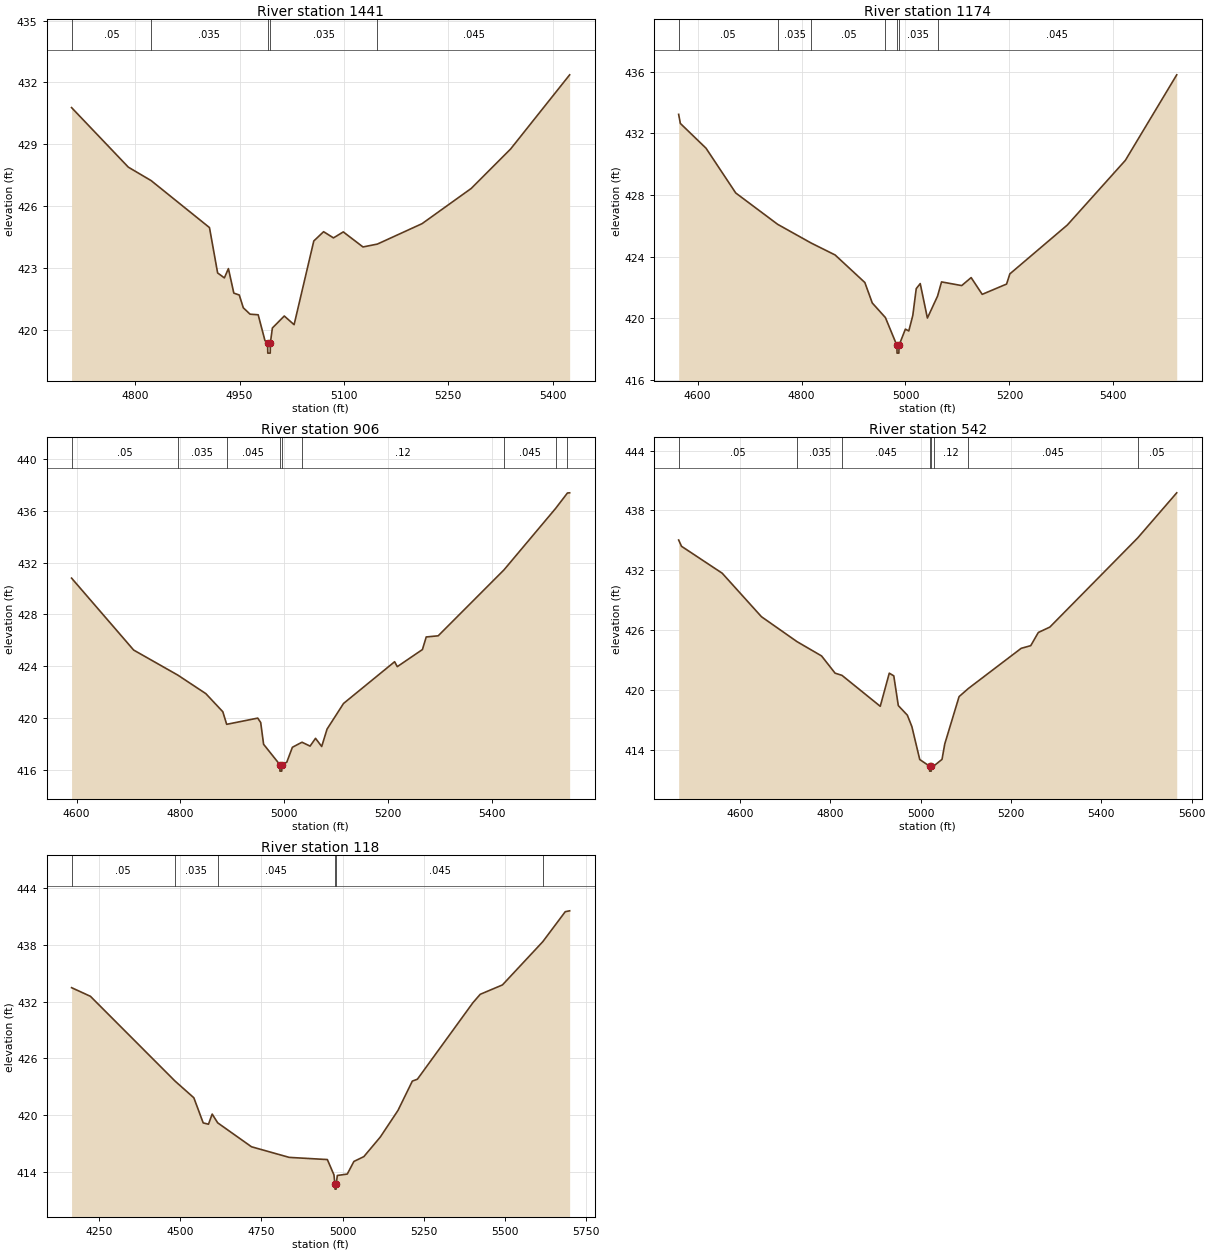
Type RM Length L Ch R = 1,1441,267,267,267
BEGIN DESCRIPTION:
Stream0435 3.0
END DESCRIPTION:
XS GIS Cut Line= 3
      2469074.99     13819424.98      2468925.00     13819175.00
      2468624.99     13818874.99
#Sta/Elev= 30
  4708.5  430.78  4790.1  427.89  4822.8  427.24  4906.7  424.96  4918.4  422.76
  4928.1  422.52  4933.9  422.97  4941.7  421.78  4949.5  421.69  4955.3  421.07
  4965.0  420.76  4976.7  420.73  4986.4  419.48  4990.2  419.37  4990.5  418.87
  4994.0  418.87  4994.2  419.37  4997.1  420.09  5014.2  420.67  5028.3  420.25
  5056.6  424.31  5070.7  424.76  5084.9  424.46  5099.0  424.75  5127.3  424.02
  5148.0  424.16  5212.2  425.15  5282.9  426.86  5339.4  428.77  5424.3  432.37
#Mann=5,-1,0
  4708.5    0.05       0  4822.8   0.035       0  4990.2   0.035       0
  4994.2   0.035       0  5148.0   0.045       0
Bank Sta=4990.2,4994.2
Exp/Cntr=0.3,0.1

Type RM Length L Ch R = 1,1174,268,268,268
BEGIN DESCRIPTION:
E21032
END DESCRIPTION:
XS GIS Cut Line= 3
      2469362.87     13819301.60      2469034.89     13818911.15
      2468613.22     13818757.57
#Sta/Elev= 30
  4563.4  433.24  4566.7  432.65  4616.1  431.04  4673.3  428.13  4754.1  426.09
  4818.8  424.87  4864.6  424.10  4921.8  422.31  4936.1  420.98  4961.4  420.03
  4983.5  418.22  4983.8  417.72  4987.3  417.72  4987.5  418.22  4999.8  419.28
  5006.4  419.16  5014.1  420.17  5020.7  421.91  5028.4  422.24  5042.2  420.00
  5061.8  421.43  5069.4  422.35  5108.2  422.11  5126.4  422.63  5147.7  421.54
  5194.6  422.21  5200.9  422.87  5311.6  426.05  5423.2  430.25  5522.1  435.81
#Mann=7,-1,0
  4563.4    0.05       0  4754.1   0.035       0  4818.8    0.05       0
  4961.4   0.035       0  4983.5   0.035       0  4987.5   0.035       0
  5061.8   0.045       0
Bank Sta=4983.5,4987.5
Exp/Cntr=0.3,0.1

Type RM Length L Ch R = 1,906,364,364,364
BEGIN DESCRIPTION:
Stream0435 2.0
END DESCRIPTION:
XS GIS Cut Line= 3
      2469475.01     13819175.01      2469249.31     13818730.21
      2469324.99     13818275.05
#Sta/Elev= 30
  4590.4  430.80  4710.1  425.25  4795.1  423.32  4849.2  421.89  4882.0  420.49
  4889.4  419.52  4949.3  420.00  4955.0  419.66  4960.6  417.98  4991.9  416.41
  4992.1  415.91  4995.6  415.91  4995.9  416.41  5005.3  416.60  5016.1  417.75
  5034.6  418.14  5050.2  417.84  5060.7  418.44  5072.6  417.81  5082.9  419.15
  5114.7  421.13  5213.2  424.35  5218.3  423.97  5266.8  425.29  5274.1  426.26
  5297.2  426.35  5424.1  431.44  5523.4  436.17  5546.4  437.37  5550.6  437.38
#Mann=9,-1,0
  4590.4    0.05       0  4795.1   0.035       0  4889.4   0.045       0
  4991.9   0.045       0  4995.9   0.045       0  5034.6    0.12       0
  5424.1   0.045       0  5523.4    0.12       0  5546.4    0.05       0
Bank Sta=4991.9,4995.9
Exp/Cntr=0.3,0.1

Type RM Length L Ch R = 1,542,424,424,424
BEGIN DESCRIPTION:
Stream0435 1.0
END DESCRIPTION:
XS GIS Cut Line= 3
      2469617.36     13819261.44      2469625.00     13818725.00
      2469440.53     13818189.27
#Sta/Elev= 30
  4463.9  435.04  4470.3  434.41  4560.4  431.71  4647.3  427.35  4726.1  424.85
  4780.4  423.42  4810.4  421.69  4825.7  421.47  4910.4  418.37  4930.4  421.69
  4940.4  421.42  4950.4  418.44  4970.4  417.48  4980.4  416.34  4997.9  413.03
  5019.6  412.37  5019.8  411.87  5023.3  411.87  5023.6  412.37  5029.7  412.41
  5047.2  413.05  5053.3  414.60  5085.0  419.34  5105.7  420.16  5222.5  424.18
  5243.7  424.45  5260.5  425.77  5286.0  426.31  5480.6  435.25  5567.0  439.77
#Mann=8,-1,0
  4463.9    0.05       0  4726.1   0.035       0  4825.7   0.045       0
  5019.6   0.045       0  5023.6   0.045       0  5029.7    0.12       0
  5105.7   0.045       0  5480.6    0.05       0
Bank Sta=5019.6,5023.6
Exp/Cntr=0.3,0.1

Type RM Length L Ch R = 1,118,0,0,0
BEGIN DESCRIPTION:
XS6786
END DESCRIPTION:
XS GIS Cut Line= 4
      2469731.96     13819289.21      2470020.14     13818737.15
      2469929.86     13818317.01      2469492.33     13818112.14
#Sta/Elev= 30
  4164.7  433.46  4222.8  432.55  4483.5  423.61  4541.7  421.84  4570.5  419.19
  4586.8  419.05  4598.2  420.12  4615.1  419.20  4719.4  416.67  4835.7  415.55
  4953.3  415.32  4973.6  413.71  4976.7  412.70  4976.9  412.20  4980.4  412.20
  4980.7  412.70  4984.0  413.64  5014.7  413.79  5035.1  415.12  5065.8  415.63
  5116.6  417.70  5171.1  420.51  5215.3  423.60  5230.9  423.80  5401.8  431.86
  5424.6  432.76  5493.1  433.75  5617.4  438.31  5686.8  441.48  5700.3  441.57
#Mann=6,-1,0
  4164.7    0.05       0  4483.5   0.035       0  4615.1   0.045       0
  4976.7   0.045       0  4980.7   0.045       0  5617.4    0.05       0
Bank Sta=4976.7,4980.7
Exp/Cntr=0.3,0.1

Chan Stop Cuts=-1