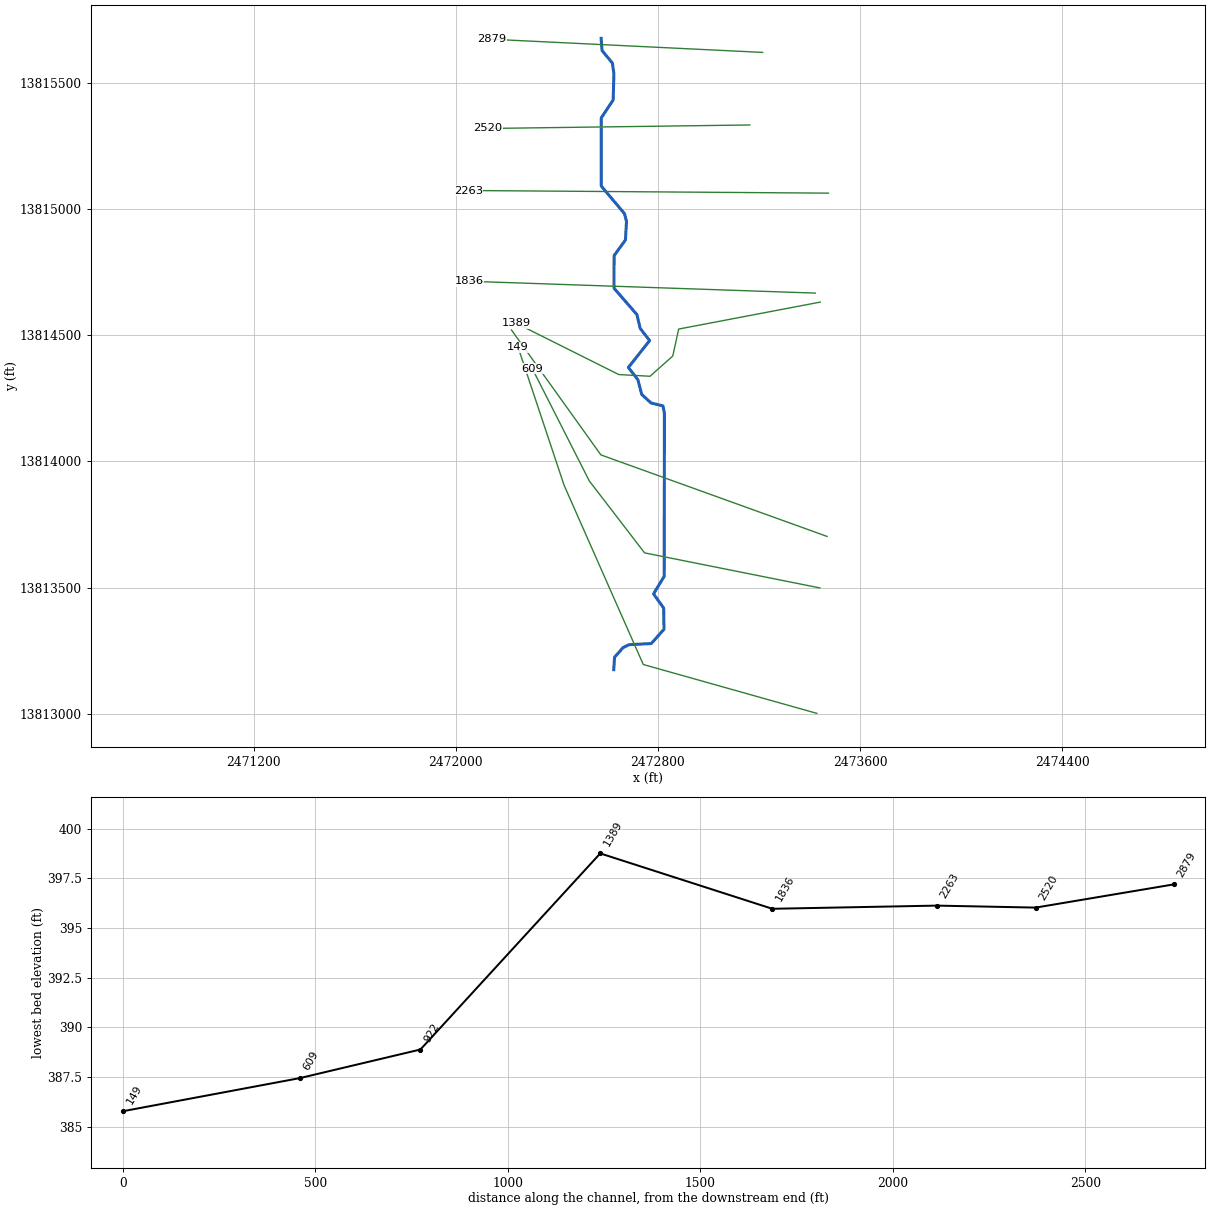
--- Stream0437.prj (project) ---

Proj Title=Stream0437 Base Level Engineering
Current Plan=p01
Default Exp/Contr=0.3,0.1
English Units
Geom File=g01
Flow File=f01
Plan File=p01
BEGIN DESCRIPTION:
Stream0437
END DESCRIPTION:

--- Stream0437.p01 (plan) ---

Plan Title=Multiple Run
Short Identifier=Multiple
Geom File=g01
Flow File=f01
Subcritical Flow
K Sum by GR= 0
Std Step Tol= 0.01
Critical Tol= 0.01
Num of Std Step Trials= 20
Max Error Tol= 0.3
Flow Tol Ratio= 0.001
Split Flow NTrial= 30
Split Flow Tol= 0.02
Split Flow Ratio= 0.02
Log Output Level= 0
Friction Slope Method= 1
Unsteady Friction Slope Method= 2
Unsteady Bridges Friction Slope Method= 1
Parabolic Critical Depth
Global Vel Dist=  1 , 1 , 1
Global Log Level= 0
CheckData=True
Encroach Param= -1, 0, 0, 0
BEGIN DESCRIPTION:
Multiple Run
END DESCRIPTION:

--- Stream0437.f01 (steady flow) ---

Flow Title=Multiple
Number of Profiles=7
Profile Names=10-year,25-year,50-year,1pct_min,100-year,1pct_plu,500-year
River Rch & RM= Stream0437,Reach-1,2879
     367     565     735     465     927    1849    1456
Boundary for River Rch & Prof#=Stream0437,Reach-1,1
Up Type=0
Dn Type=3
Dn Slope=0.005
Boundary for River Rch & Prof#=Stream0437,Reach-1,2
Up Type=0
Dn Type=3
Dn Slope=0.005
Boundary for River Rch & Prof#=Stream0437,Reach-1,3
Up Type=0
Dn Type=3
Dn Slope=0.005
Boundary for River Rch & Prof#=Stream0437,Reach-1,4
Up Type=0
Dn Type=3
Dn Slope=0.005
Boundary for River Rch & Prof#=Stream0437,Reach-1,5
Up Type=0
Dn Type=3
Dn Slope=0.005
Boundary for River Rch & Prof#=Stream0437,Reach-1,6
Up Type=0
Dn Type=3
Dn Slope=0.005
Boundary for River Rch & Prof#=Stream0437,Reach-1,7
Up Type=0
Dn Type=3
Dn Slope=0.005

--- Stream0437.g01 (geometry) ---

Geom Title=Existing Conditions

River Reach=Stream0437,Reach-1
Reach XY= 30
      2472575.00     13815675.00      2472578.65     13815626.51
      2472619.47     13815577.42      2472625.51     13815535.17
      2472622.75     13815430.94      2472575.52     13815359.78
      2472575.39     13815090.16      2472667.22     13814981.16
      2472675.49     13814950.04      2472671.30     13814876.60
      2472626.21     13814814.49      2472626.04     13814685.44
      2472716.86     13814581.04      2472729.46     13814526.65
      2472767.15     13814478.23      2472682.85     13814371.77
      2472720.53     13814323.33      2472735.67     13814265.03
      2472772.86     13814230.92      2472819.79     13814219.55
      2472825.63     13814190.55      2472824.82     13813544.98
      2472782.56     13813475.00      2472822.64     13813419.10
      2472824.13     13813335.31      2472773.75     13813278.51
      2472685.36     13813273.92      2472661.35     13813261.87
      2472628.12     13813224.01      2472625.00     13813175.00

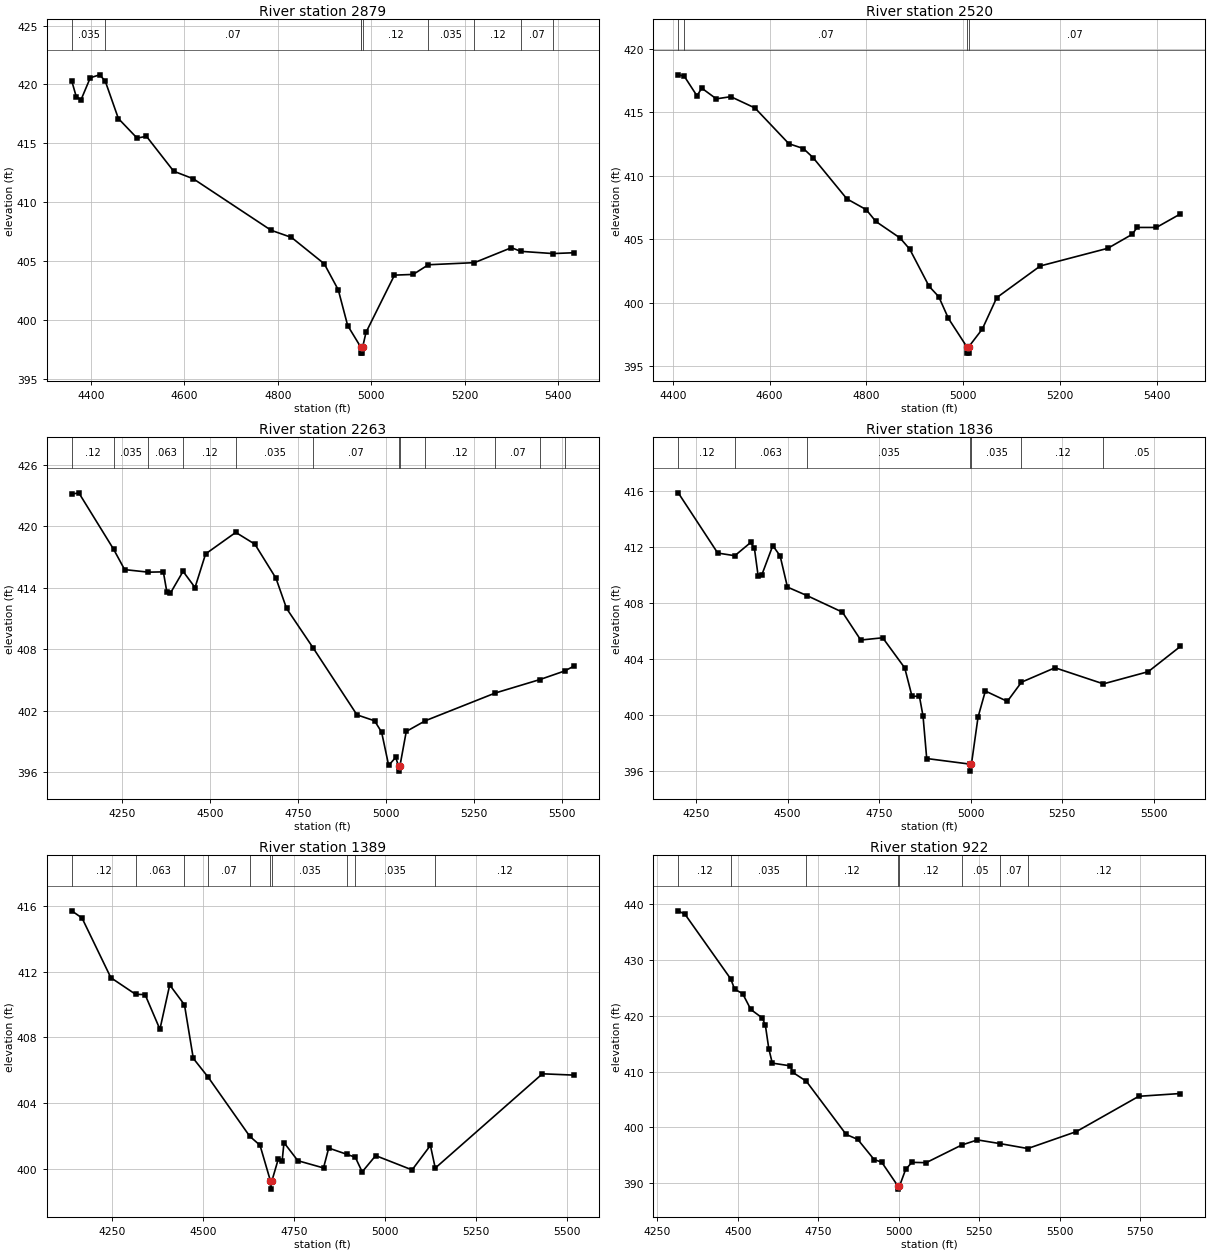
Type RM Length L Ch R = 1,2879,359,359,359
BEGIN DESCRIPTION:
XS6796
END DESCRIPTION:
XS GIS Cut Line= 2
      2473214.56     13815619.27      2472141.63     13815671.36
#Sta/Elev= 30
  4359.4  420.30  4369.0  418.96  4379.2  418.70  4399.0  420.57  4419.0  420.82
  4431.0  420.29  4459.1  417.11  4499.1  415.45  4519.2  415.60  4577.4  412.64
  4619.3  412.00  4785.7  407.63  4829.5  407.02  4899.6  404.78  4929.6  402.57
  4949.7  399.54  4977.4  397.73  4977.7  397.70  4977.9  397.20  4981.4  397.20
  4981.7  397.70  4988.9  398.96  5049.8  403.82  5089.8  403.88  5122.3  404.70
  5221.0  404.88  5300.1  406.15  5319.8  405.84  5389.0  405.65  5433.6  405.72
#Mann=9,-1,0
  4359.4   0.035       0  4431.0    0.07       0  4977.4    0.12       0
  4977.7    0.05       0  4981.7    0.12       0  5122.3   0.035       0
  5221.0    0.12       0  5319.8    0.07       0  5389.0   0.035       0
Bank Sta=4977.7,4981.7
Exp/Cntr=0.3,0.1

Type RM Length L Ch R = 1,2520,257,257,257
BEGIN DESCRIPTION:
E21044
END DESCRIPTION:
XS GIS Cut Line= 2
      2473163.67     13815331.94      2472125.56     13815318.06
#Sta/Elev= 30
  4410.9  417.93  4423.2  417.83  4449.6  416.28  4459.6  416.88  4489.6  416.04
  4519.6  416.21  4569.6  415.32  4639.6  412.51  4669.6  412.13  4689.6  411.42
  4759.6  408.17  4799.6  407.32  4819.6  406.39  4869.6  405.09  4889.6  404.21
  4929.6  401.29  4949.6  400.47  4969.6  398.76  5007.6  396.53  5007.9  396.03
  5011.4  396.03  5011.6  396.53  5039.6  397.92  5069.6  400.40  5159.6  402.89
  5299.2  404.28  5349.7  405.38  5359.7  405.92  5399.7  405.92  5449.1  406.98
#Mann=4,-1,0
  4410.9   0.035       0  4423.2    0.07       0  5007.6    0.05       0
  5011.6    0.07       0
Bank Sta=5007.6,5011.6
Exp/Cntr=0.3,0.1

Type RM Length L Ch R = 1,2263,427,427,427
BEGIN DESCRIPTION:
XS6795
END DESCRIPTION:
XS GIS Cut Line= 2
      2473475.05     13815061.98      2472048.98     13815072.39
#Sta/Elev= 30
  4108.0  423.15  4128.0  423.28  4227.1  417.76  4258.1  415.79  4325.6  415.54
  4368.1  415.57  4378.1  413.61  4388.1  413.49  4424.1  415.62  4458.1  414.04
  4488.1  417.32  4573.8  419.42  4628.1  418.27  4688.1  414.94  4718.1  412.00
  4793.8  408.14  4918.1  401.62  4968.1  401.04  4988.1  399.93  5008.1  396.69
  5028.1  397.47  5036.1  396.63  5036.3  396.13  5040.1  396.63  5058.1  400.00
  5112.6  401.05  5310.8  403.75  5437.4  405.06  5507.9  405.90  5534.1  406.37
#Mann=12,-1,0
  4108.0    0.12       0  4227.1   0.035       0  4325.6   0.063       0
  4424.1    0.12       0  4573.8   0.035       0  4793.8    0.07       0
  5036.1    0.05       0  5040.1    0.07       0  5112.6    0.12       0
  5310.8    0.07       0  5437.4    0.12       0  5507.9   0.035       0
Bank Sta=5036.1,5040.1
Exp/Cntr=0.3,0.1

Type RM Length L Ch R = 1,1836,447,447,447
BEGIN DESCRIPTION:
XS6794
END DESCRIPTION:
XS GIS Cut Line= 2
      2473422.91     13814666.15      2472053.11     13814713.02
#Sta/Elev= 30
  4201.7  415.84  4309.5  411.54  4356.1  411.35  4399.7  412.30  4409.7  411.87
  4419.7  409.93  4429.7  409.97  4459.8  412.07  4479.8  411.34  4499.8  409.11
  4553.4  408.50  4649.9  407.32  4699.9  405.33  4759.9  405.49  4820.0  403.34
  4840.0  401.30  4860.0  401.33  4870.0  399.89  4880.0  396.87  4998.1  396.47
  4998.3  395.97  5002.1  396.47  5020.1  399.82  5040.1  401.69  5100.1  400.95
  5138.7  402.32  5230.2  403.35  5362.3  402.20  5484.7  403.07  5572.3  404.87
#Mann=7,-1,0
  4201.7    0.12       0  4356.1   0.063       0  4553.4   0.035       0
  4998.1   0.035       0  5002.1   0.035       0  5138.7    0.12       0
  5362.3    0.05       0
Bank Sta=4998.1,5002.1
Exp/Cntr=0.3,0.1

Type RM Length L Ch R = 1,1389,467,467,467
BEGIN DESCRIPTION:
XS6793
END DESCRIPTION:
XS GIS Cut Line= 6
      2473442.72     13814630.58      2472882.06     13814523.79
      2472858.70     13814416.99      2472768.59     13814336.89
      2472645.11     13814343.57      2472238.93     13814546.66
#Sta/Elev= 30
  4139.5  415.70  4167.7  415.26  4246.8  411.63  4314.6  410.62  4340.8  410.60
  4381.5  408.49  4408.4  411.19  4448.9  409.98  4473.1  406.72  4514.1  405.57
  4628.0  401.98  4656.3  401.43  4684.9  399.26  4685.1  398.76  4688.9  399.26
  4706.2  400.57  4717.0  400.46  4722.1  401.59  4760.2  400.49  4830.6  400.05
  4844.9  401.26  4895.9  400.87  4917.9  400.70  4936.8  399.81  4973.8  400.80
  5073.8  399.93  5124.1  401.42  5137.4  400.04  5431.6  405.78  5517.9  405.70
#Mann=10,-1,0
  4139.5    0.12       0  4314.6   0.063       0  4448.9   0.035       0
  4514.1    0.07       0  4628.0   0.035       0  4684.9   0.035       0
  4688.9   0.035       0  4895.9    0.12       0  4917.9   0.035       0
  5137.4    0.12       0
Bank Sta=4684.9,4688.9
Exp/Cntr=0.3,0.1

Type RM Length L Ch R = 1,922,313,313,313
BEGIN DESCRIPTION:
XS6792
END DESCRIPTION:
XS GIS Cut Line= 3
      2473469.80     13813702.60      2472573.96     13814025.52
      2472220.00     13814520.03
#Sta/Elev= 30
  4314.6  438.86  4336.0  438.21  4477.9  426.62  4489.8  424.79  4514.9  423.98
  4540.2  421.14  4576.2  419.60  4585.5  418.27  4596.1  414.09  4606.9  411.51
  4663.0  411.02  4670.5  409.85  4712.6  408.26  4836.5  398.70  4872.5  397.81
  4923.2  394.20  4946.9  393.72  4998.0  389.38  4998.3  388.88  5002.0  389.38
  5021.3  392.41  5040.7  393.69  5085.1  393.63  5195.2  396.79  5244.5  397.72
  5314.0  397.06  5401.0  396.17  5551.9  399.21  5745.8  405.55  5875.0  406.05
#Mann=8,-1,0
  4314.6    0.12       0  4477.9   0.035       0  4712.6    0.12       0
  4998.0    0.05       0  5002.0    0.12       0  5195.2    0.05       0
  5314.0    0.07       0  5401.0    0.12       0
Bank Sta=4998,5002
Exp/Cntr=0.3,0.1

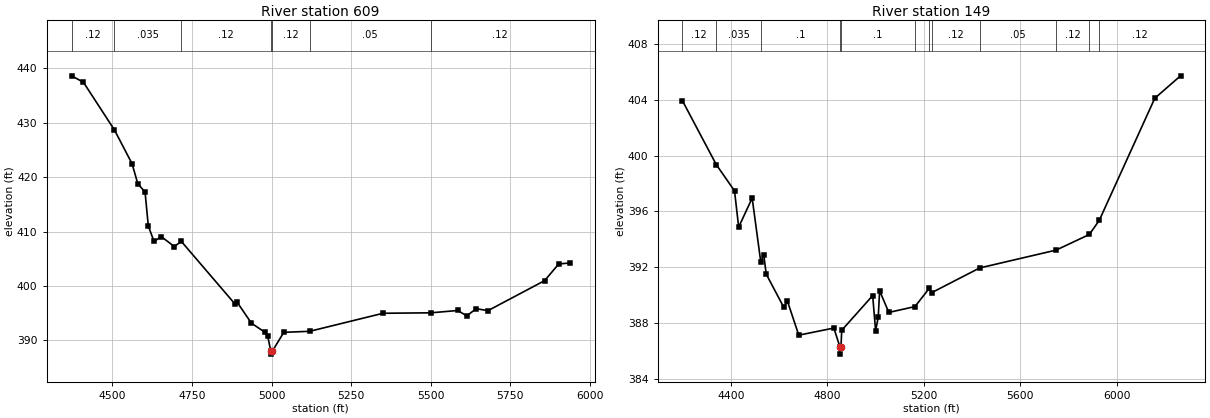
Type RM Length L Ch R = 1,609,460,460,460
BEGIN DESCRIPTION:
E21043
END DESCRIPTION:
XS GIS Cut Line= 4
      2473441.49     13813498.61      2472747.05     13813637.50
      2472528.30     13813922.22      2472302.61     13814366.66
#Sta/Elev= 30
  4371.4  438.65  4408.6  437.47  4506.3  428.68  4561.6  422.47  4579.7  418.78
  4602.4  417.28  4612.6  411.04  4630.6  408.17  4653.4  409.07  4694.2  407.24
  4716.5  408.18  4885.6  396.63  4890.7  397.10  4936.6  393.15  4979.7  391.44
  4987.6  390.83  4998.1  387.94  4998.3  387.44  5002.1  387.94  5038.6  391.45
  5120.0  391.64  5350.7  394.96  5500.3  395.04  5585.7  395.47  5613.6  394.48
  5643.6  395.80  5680.4  395.44  5858.4  400.96  5902.9  404.03  5937.1  404.21
#Mann=7,-1,0
  4371.4    0.12       0  4506.3   0.035       0  4716.5    0.12       0
  4998.1    0.05       0  5002.1    0.12       0  5120.0    0.05       0
  5500.3    0.12       0
Bank Sta=4998.1,5002.1
Exp/Cntr=0.3,0.1

Type RM Length L Ch R = 1,149,0,0,0
BEGIN DESCRIPTION:
XS6791
END DESCRIPTION:
XS GIS Cut Line= 4
      2473429.37     13813001.95      2472741.89     13813195.51
      2472428.13     13813905.73      2472246.28     13814451.27
#Sta/Elev= 30
  4198.7  403.94  4338.7  399.37  4414.6  397.48  4431.8  394.88  4487.8  396.96
  4523.6  392.37  4535.7  392.91  4546.1  391.51  4618.8  389.13  4634.3  389.56
  4681.1  387.13  4826.6  387.64  4852.1  386.27  4852.4  385.77  4856.1  386.27
  4859.3  387.48  4987.6  389.97  4999.8  387.45  5010.7  388.42  5016.4  390.32
  5054.5  388.76  5163.0  389.18  5221.9  390.48  5232.4  390.18  5431.4  391.95
  5748.2  393.23  5886.2  394.35  5927.3  395.36  6157.7  404.12  6264.4  405.73
#Mann=12,-1,0
  4198.7    0.12       0  4338.7   0.035       0  4523.6     0.1       0
  4852.1    0.05       0  4856.1     0.1       0  5163.0    0.12       0
  5221.9    0.05       0  5232.4    0.12       0  5431.4    0.05       0
  5748.2    0.12       0  5886.2    0.05       0  5927.3    0.12       0
Bank Sta=4852.1,4856.1
Exp/Cntr=0.3,0.1

Chan Stop Cuts=-1