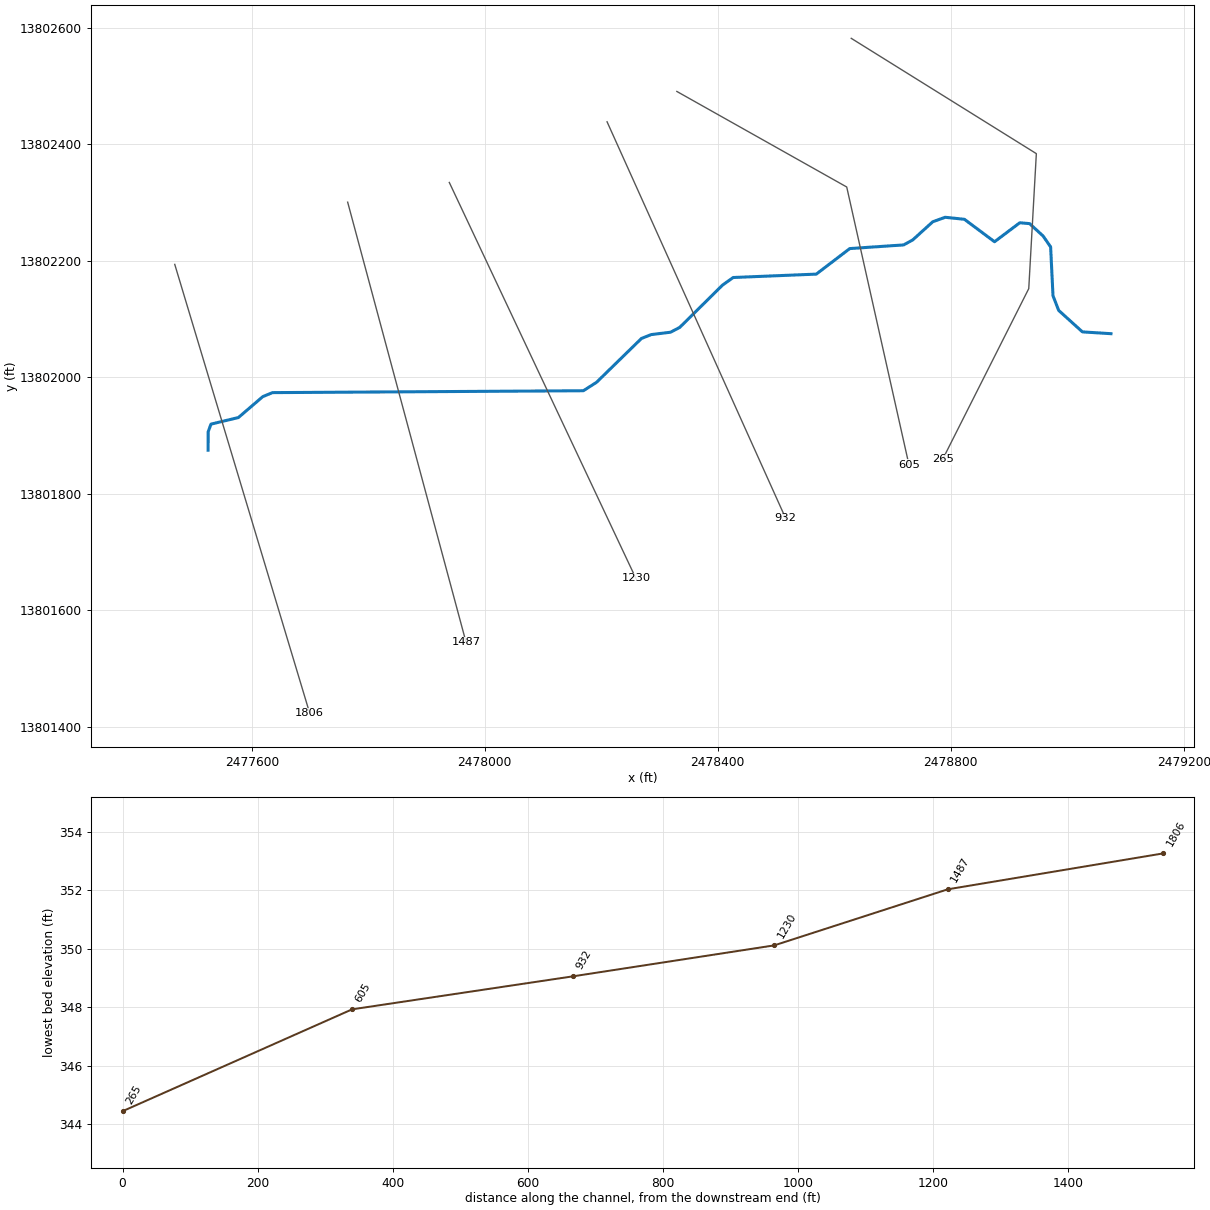
--- Stream0439.prj (project) ---

Proj Title=Stream0439 Base Level Engineering
Current Plan=p01
Default Exp/Contr=0.3,0.1
English Units
Geom File=g01
Flow File=f01
Plan File=p01
BEGIN DESCRIPTION:
Stream0439
END DESCRIPTION:

--- Stream0439.p01 (plan) ---

Plan Title=Multiple Run
Short Identifier=Multiple
Geom File=g01
Flow File=f01
Subcritical Flow
K Sum by GR= 0
Std Step Tol= 0.01
Critical Tol= 0.01
Num of Std Step Trials= 20
Max Error Tol= 0.3
Flow Tol Ratio= 0.001
Split Flow NTrial= 30
Split Flow Tol= 0.02
Split Flow Ratio= 0.02
Log Output Level= 0
Friction Slope Method= 1
Unsteady Friction Slope Method= 2
Unsteady Bridges Friction Slope Method= 1
Parabolic Critical Depth
Global Vel Dist=  1 , 1 , 1
Global Log Level= 0
CheckData=True
Encroach Param= -1, 0, 0, 0
BEGIN DESCRIPTION:
Multiple Run
END DESCRIPTION:

--- Stream0439.f01 (steady flow) ---

Flow Title=Multiple
Number of Profiles=7
Profile Names=10-year,25-year,50-year,1pct_min,100-year,1pct_plu,500-year
River Rch & RM= Stream0439,Reach-1,1806
     432     679     897     575    1148    2291    1859
Boundary for River Rch & Prof#=Stream0439,Reach-1,1
Up Type=0
Dn Type=3
Dn Slope=0.005
Boundary for River Rch & Prof#=Stream0439,Reach-1,2
Up Type=0
Dn Type=3
Dn Slope=0.005
Boundary for River Rch & Prof#=Stream0439,Reach-1,3
Up Type=0
Dn Type=3
Dn Slope=0.005
Boundary for River Rch & Prof#=Stream0439,Reach-1,4
Up Type=0
Dn Type=3
Dn Slope=0.005
Boundary for River Rch & Prof#=Stream0439,Reach-1,5
Up Type=0
Dn Type=3
Dn Slope=0.005
Boundary for River Rch & Prof#=Stream0439,Reach-1,6
Up Type=0
Dn Type=3
Dn Slope=0.005
Boundary for River Rch & Prof#=Stream0439,Reach-1,7
Up Type=0
Dn Type=3
Dn Slope=0.005

--- Stream0439.g01 (geometry) ---

Geom Title=Existing Conditions

River Reach=Stream0439,Reach-1
Reach XY= 30
      2477525.00     13801875.00      2477525.06     13801906.56
      2477529.90     13801919.72      2477577.00     13801931.04
      2477618.88     13801966.95      2477635.48     13801973.82
      2478169.14     13801977.06      2478191.75     13801991.46
      2478268.96     13802066.82      2478285.64     13802073.45
      2478318.95     13802077.54      2478334.67     13802085.80
      2478408.25     13802158.54      2478426.47     13802171.45
      2478569.06     13802177.27      2478626.60     13802221.14
      2478719.03     13802227.38      2478734.65     13802235.95
      2478769.09     13802267.17      2478790.42     13802274.85
      2478823.37     13802271.41      2478875.10     13802232.84
      2478918.51     13802265.48      2478935.37     13802263.92
      2478958.54     13802242.61      2478971.39     13802223.97
      2478975.47     13802140.13      2478985.26     13802114.91
      2479025.99     13802078.12      2479075.00     13802075.00

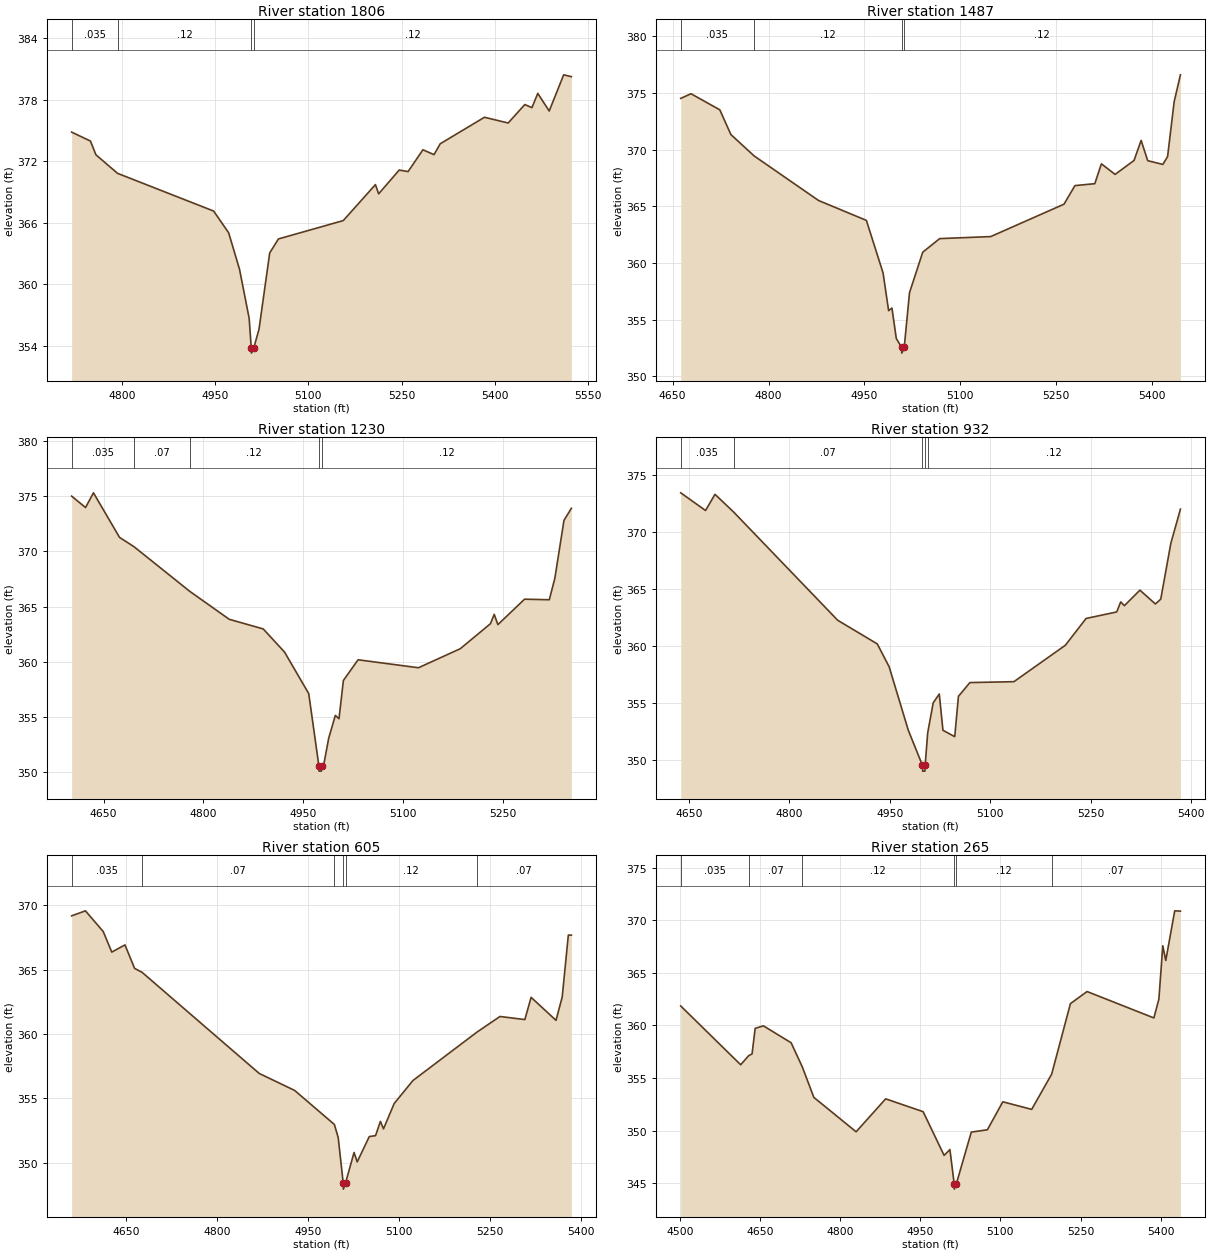
Type RM Length L Ch R = 1,1806,319,319,319
BEGIN DESCRIPTION:
XS6803
END DESCRIPTION:
XS GIS Cut Line= 2
      2477467.72     13802193.98      2477699.48     13801423.16
#Sta/Elev= 30
  4718.7  374.83  4749.0  373.96  4757.8  372.62  4792.6  370.81  4947.4  367.13
  4971.6  365.01  4989.1  361.45  5004.6  356.67  5008.0  353.77  5008.3  353.27
  5012.0  353.77  5020.5  355.61  5037.7  363.04  5051.8  364.41  5156.2  366.20
  5208.0  369.71  5213.2  368.81  5246.3  371.13  5260.6  370.98  5284.5  373.11
  5302.4  372.63  5312.3  373.69  5383.6  376.28  5421.8  375.72  5448.6  377.52
  5460.1  377.22  5469.5  378.61  5487.9  376.89  5511.2  380.42  5523.6  380.24
#Mann=4,-1,0
  4718.7   0.035       0  4792.6    0.12       0  5008.0    0.05       0
  5012.0    0.12       0
Bank Sta=5008,5012
Exp/Cntr=0.3,0.1

Type RM Length L Ch R = 1,1487,257,257,257
BEGIN DESCRIPTION:
XS6802
END DESCRIPTION:
XS GIS Cut Line= 2
      2477764.57     13802300.82      2477967.71     13801545.57
#Sta/Elev= 30
  4662.6  374.53  4678.7  374.94  4723.8  373.52  4741.1  371.34  4777.5  369.45
  4878.5  365.51  4953.2  363.76  4979.3  359.12  4988.0  355.79  4993.2  356.02
  5000.0  353.34  5008.4  352.54  5008.6  352.04  5012.4  352.54  5020.7  357.38
  5041.4  360.95  5067.9  362.15  5147.8  362.33  5262.5  365.19  5279.6  366.83
  5310.7  367.00  5321.0  368.75  5342.5  367.82  5372.1  369.05  5383.2  370.82
  5393.5  369.03  5417.2  368.70  5424.6  369.39  5434.9  374.24  5444.7  376.61
#Mann=4,-1,0
  4662.6   0.035       0  4777.5    0.12       0  5008.4    0.05       0
  5012.4    0.12       0
Bank Sta=5008.4,5012.4
Exp/Cntr=0.3,0.1

Type RM Length L Ch R = 1,1230,298,298,298
BEGIN DESCRIPTION:
XS6801
END DESCRIPTION:
XS GIS Cut Line= 2
      2477939.06     13802334.63      2478259.38     13801654.93
#Sta/Elev= 30
  4602.1  374.99  4623.0  373.96  4634.9  375.29  4674.1  371.26  4695.8  370.42
  4779.5  366.39  4839.1  363.85  4890.2  362.98  4922.3  360.88  4958.6  357.13
  4973.8  350.62  4974.1  350.12  4977.6  350.12  4977.8  350.62  4981.4  350.78
  4988.6  353.09  4998.6  355.16  5004.1  354.86  5010.7  358.32  5032.8  360.19
  5123.6  359.47  5186.4  361.19  5231.8  363.45  5237.5  364.30  5243.0  363.37
  5283.1  365.67  5320.3  365.62  5328.6  367.54  5342.4  372.80  5353.5  373.89
#Mann=5,-1,0
  4602.1   0.035       0  4695.8    0.07       0  4779.5    0.12       0
  4973.8    0.05       0  4977.8    0.12       0
Bank Sta=4973.8,4977.8
Exp/Cntr=0.3,0.1

Type RM Length L Ch R = 1,932,327,327,327
BEGIN DESCRIPTION:
XS6800
END DESCRIPTION:
XS GIS Cut Line= 2
      2478209.90     13802438.80      2478516.41     13801758.24
#Sta/Elev= 30
  4637.6  373.45  4674.7  371.90  4688.8  373.32  4717.1  371.74  4872.1  362.28
  4931.2  360.21  4948.9  358.21  4977.5  352.65  4998.7  349.56  4998.9  349.06
  5002.4  349.06  5002.7  349.56  5006.5  352.41  5014.7  355.04  5023.8  355.82
  5029.3  352.64  5046.9  352.08  5052.4  355.61  5069.5  356.82  5135.3  356.90
  5212.1  360.09  5243.1  362.44  5288.8  363.01  5294.8  363.89  5300.3  363.56
  5323.5  364.92  5346.6  363.71  5354.6  364.13  5369.7  369.03  5384.0  372.02
#Mann=5,-1,0
  4637.6   0.035       0  4717.1    0.07       0  4998.7    0.05       0
  5002.7    0.07       0  5006.5    0.12       0
Bank Sta=4998.7,5002.7
Exp/Cntr=0.3,0.1

Type RM Length L Ch R = 1,605,340,340,340
BEGIN DESCRIPTION:
XS6799
END DESCRIPTION:
XS GIS Cut Line= 3
      2478329.70     13802490.88      2478621.35     13802326.82
      2478728.12     13801850.27
#Sta/Elev= 30
  4560.7  369.19  4583.4  369.58  4612.7  367.97  4626.8  366.37  4648.5  366.93
  4664.4  365.10  4676.6  364.80  4869.6  356.93  4927.9  355.61  4993.4  352.96
  4999.7  351.94  5007.9  348.43  5008.2  347.93  5011.9  348.43  5025.8  350.78
  5031.0  350.05  5050.9  352.02  5061.2  352.09  5069.2  353.20  5074.3  352.62
  5091.9  354.59  5122.8  356.38  5228.1  360.14  5266.1  361.36  5307.1  361.12
  5317.4  362.85  5358.4  361.06  5368.6  362.87  5378.7  367.69  5383.7  367.69
#Mann=6,-1,0
  4560.7   0.035       0  4676.6    0.07       0  4993.4    0.12       0
  5007.9    0.05       0  5011.9    0.12       0  5228.1    0.07       0
Bank Sta=5007.9,5011.9
Exp/Cntr=0.3,0.1

Type RM Length L Ch R = 1,265,0,0,0
BEGIN DESCRIPTION:
XS6798
END DESCRIPTION:
XS GIS Cut Line= 4
      2478629.12     13802582.06      2478946.88     13802384.11
      2478933.85     13802152.34      2478785.91     13801859.04
#Sta/Elev= 30
  4501.9  361.85  4614.1  356.26  4629.0  357.12  4635.4  357.29  4641.2  359.72
  4656.6  359.96  4708.5  358.35  4729.3  356.07  4751.0  353.16  4830.1  349.89
  4885.4  353.02  4955.5  351.80  4994.7  347.65  5005.6  348.20  5013.6  344.94
  5013.8  344.44  5017.6  344.94  5045.6  349.86  5075.7  350.08  5104.6  352.74
  5158.6  352.02  5196.0  355.37  5231.1  362.07  5262.2  363.22  5387.2  360.71
  5396.6  362.50  5403.9  367.57  5409.5  366.17  5426.2  370.89  5436.9  370.86
#Mann=6,-1,0
  4501.9   0.035       0  4629.0    0.07       0  4729.3    0.12       0
  5013.6    0.05       0  5017.6    0.12       0  5196.0    0.07       0
Bank Sta=5013.6,5017.6
Exp/Cntr=0.3,0.1

Chan Stop Cuts=-1