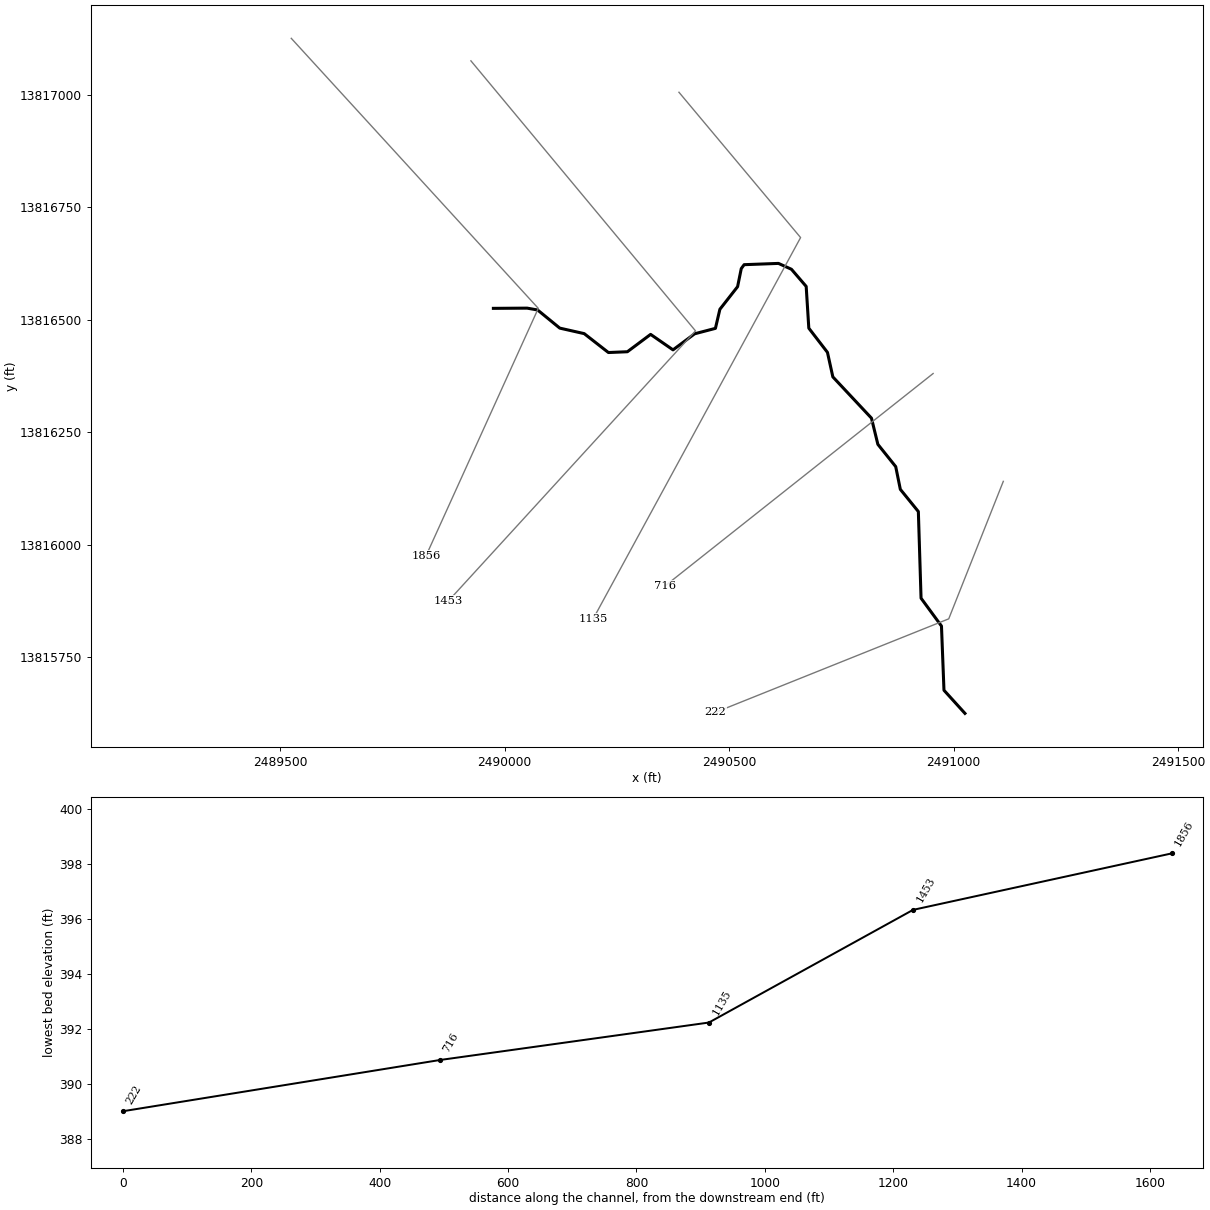
--- Stream0442.prj (project) ---

Proj Title=Stream0442 Base Level Engineering
Current Plan=p01
Default Exp/Contr=0.3,0.1
English Units
Geom File=g01
Flow File=f01
Plan File=p01
BEGIN DESCRIPTION:
Stream0442
END DESCRIPTION:

--- Stream0442.p01 (plan) ---

Plan Title=Multiple Run
Short Identifier=Multiple
Geom File=g01
Flow File=f01
Subcritical Flow
K Sum by GR= 0
Std Step Tol= 0.01
Critical Tol= 0.01
Num of Std Step Trials= 20
Max Error Tol= 0.3
Flow Tol Ratio= 0.001
Split Flow NTrial= 30
Split Flow Tol= 0.02
Split Flow Ratio= 0.02
Log Output Level= 0
Friction Slope Method= 1
Unsteady Friction Slope Method= 2
Unsteady Bridges Friction Slope Method= 1
Parabolic Critical Depth
Global Vel Dist=  1 , 1 , 1
Global Log Level= 0
CheckData=True
Encroach Param= -1, 0, 0, 0
BEGIN DESCRIPTION:
Multiple Run
END DESCRIPTION:

--- Stream0442.f01 (steady flow) ---

Flow Title=Multiple
Number of Profiles=7
Profile Names=10-year,25-year,50-year,1pct_min,100-year,1pct_plu,500-year
River Rch & RM= Stream0442,Reach-1,1856
     472     743     982     630    1256    2506    2033
Boundary for River Rch & Prof#=Stream0442,Reach-1,1
Up Type=0
Dn Type=3
Dn Slope=0.005
Boundary for River Rch & Prof#=Stream0442,Reach-1,2
Up Type=0
Dn Type=3
Dn Slope=0.005
Boundary for River Rch & Prof#=Stream0442,Reach-1,3
Up Type=0
Dn Type=3
Dn Slope=0.005
Boundary for River Rch & Prof#=Stream0442,Reach-1,4
Up Type=0
Dn Type=3
Dn Slope=0.005
Boundary for River Rch & Prof#=Stream0442,Reach-1,5
Up Type=0
Dn Type=3
Dn Slope=0.005
Boundary for River Rch & Prof#=Stream0442,Reach-1,6
Up Type=0
Dn Type=3
Dn Slope=0.005
Boundary for River Rch & Prof#=Stream0442,Reach-1,7
Up Type=0
Dn Type=3
Dn Slope=0.005

--- Stream0442.g01 (geometry) ---

Geom Title=Existing Conditions

River Reach=Stream0442,Reach-1
Reach XY= 30
      2489975.00     13816525.00      2490050.20     13816525.48
      2490073.50     13816521.37      2490122.81     13816481.08
      2490177.20     13816468.85      2490231.13     13816426.84
      2490273.37     13816428.59      2490325.09     13816467.17
      2490374.95     13816432.75      2490423.05     13816468.46
      2490469.41     13816480.55      2490479.33     13816522.93
      2490518.75     13816573.18      2490526.96     13816613.38
      2490533.32     13816622.04      2490609.79     13816624.88
      2490638.69     13816611.85      2490671.49     13816573.75
      2490677.34     13816480.97      2490718.86     13816427.17
      2490730.84     13816372.71      2490816.84     13816281.05
      2490831.10     13816222.81      2490870.84     13816173.28
      2490881.12     13816122.82      2490921.25     13816073.45
      2490927.26     13815880.94      2490972.73     13815819.06
      2490978.30     13815676.37      2491025.00     13815625.00

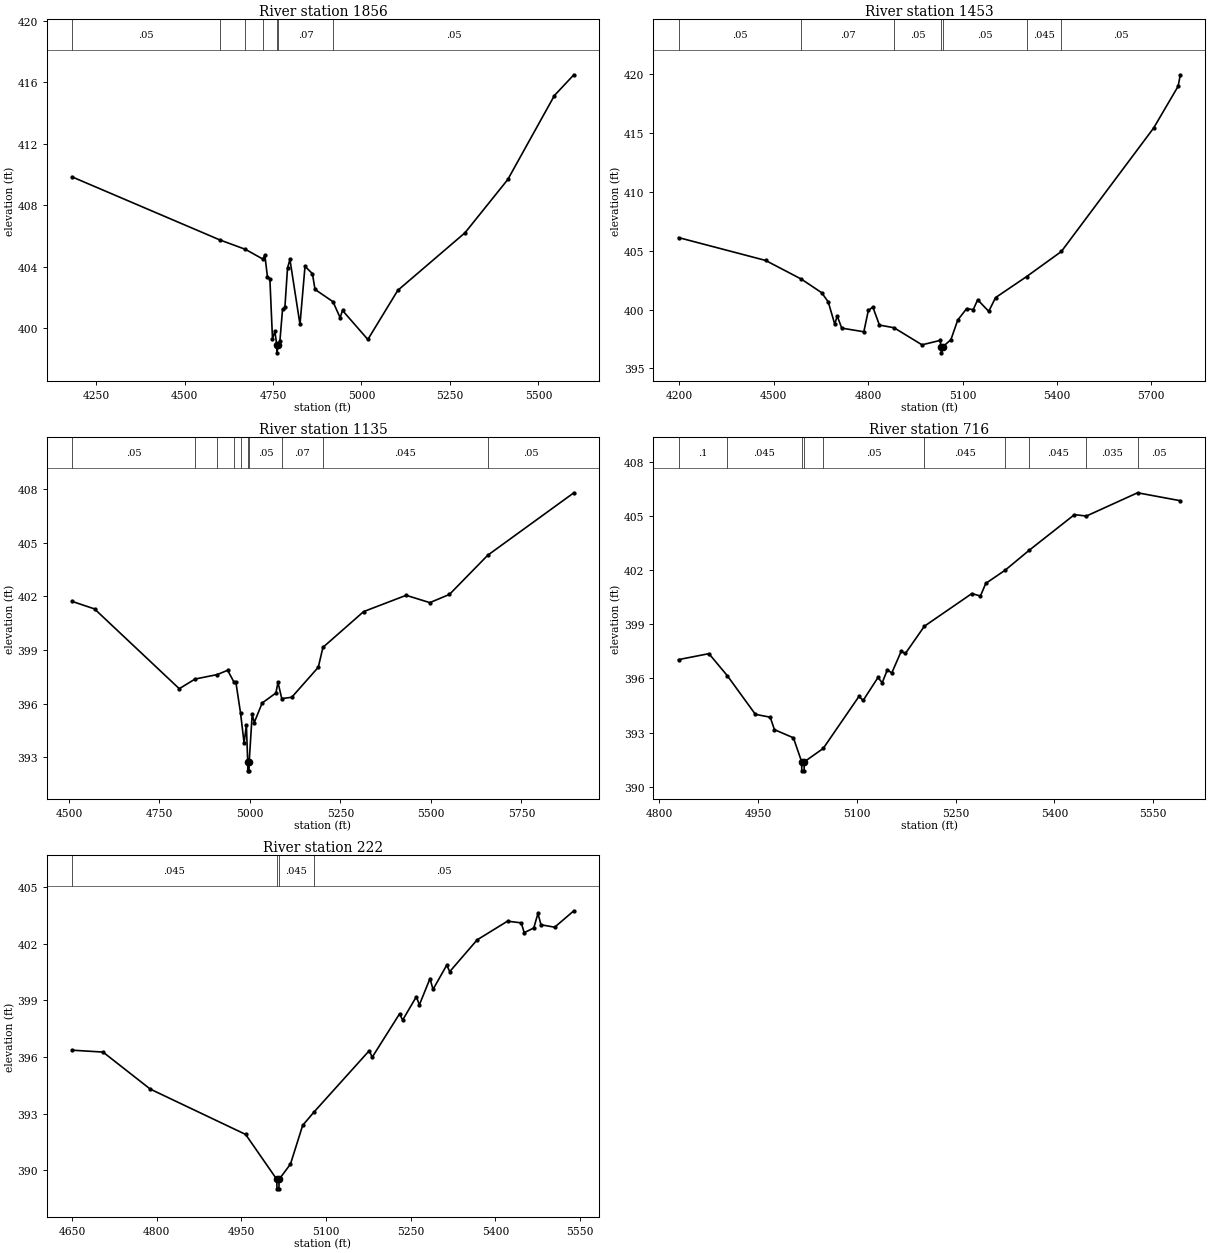
Type RM Length L Ch R = 1,1856,403,403,403
BEGIN DESCRIPTION:
Stream0442 2.0
END DESCRIPTION:
XS GIS Cut Line= 3
      2489524.99     13817125.01      2490075.00     13816525.00
      2489825.01     13815975.01
#Sta/Elev= 30
  4182.1  409.84  4600.1  405.73  4672.1  405.12  4721.0  404.49  4726.9  404.74
  4734.3  403.32  4741.1  403.21  4748.5  399.30  4755.3  399.77  4760.7  398.88
  4760.9  398.38  4764.7  398.88  4769.5  399.16  4776.9  401.21  4783.6  401.35
  4791.0  403.91  4797.8  404.46  4826.2  400.23  4840.4  404.01  4861.3  403.54
  4868.7  402.51  4919.5  401.71  4939.6  400.67  4946.4  401.14  5018.0  399.25
  5102.6  402.45  5292.6  406.20  5413.5  409.67  5545.3  415.14  5600.2  416.49
#Mann=7,-1,0
  4182.1    0.05       0  4600.1    0.07       0  4672.1    0.05       0
  4721.0    0.07       0  4760.7    0.05       0  4764.7    0.07       0
  4919.5    0.05       0
Bank Sta=4760.7,4764.7
Exp/Cntr=0.3,0.1

Type RM Length L Ch R = 1,1453,318,318,318
BEGIN DESCRIPTION:
Stream0442 1.0
END DESCRIPTION:
XS GIS Cut Line= 3
      2489925.00     13817075.00      2490425.00     13816475.00
      2489874.97     13815874.97
#Sta/Elev= 30
  4197.3  406.12  4473.9  404.18  4587.8  402.59  4652.2  401.44  4673.1  400.66
  4693.9  398.76  4701.7  399.46  4716.0  398.43  4786.3  398.12  4800.6  399.93
  4815.0  400.22  4835.8  398.69  4882.4  398.46  4971.2  397.01  5028.0  397.38
  5032.7  396.83  5033.0  396.33  5036.7  396.83  5063.1  397.45  5084.7  399.11
  5113.1  400.09  5134.0  400.00  5148.2  400.84  5183.3  399.85  5204.9  401.02
  5303.8  402.81  5414.2  404.94  5707.5  415.43  5785.2  418.97  5792.3  419.95
#Mann=7,-1,0
  4197.3    0.05       0  4587.8    0.07       0  4882.4    0.05       0
  5032.7    0.05       0  5036.7    0.05       0  5303.8   0.045       0
  5414.2    0.05       0
Bank Sta=5032.7,5036.7
Exp/Cntr=0.3,0.1

Type RM Length L Ch R = 1,1135,419,419,419
BEGIN DESCRIPTION:
XS6811
END DESCRIPTION:
XS GIS Cut Line= 3
      2490388.20     13817005.20      2490659.03     13816682.29
      2490197.20     13815835.04
#Sta/Elev= 30
  4508.5  401.71  4570.5  401.29  4804.7  396.83  4848.3  397.37  4909.7  397.62
  4938.3  397.86  4955.0  397.23  4961.0  397.20  4974.0  395.47  4983.8  393.79
  4990.1  394.80  4993.8  392.74  4994.0  392.24  4997.5  392.24  4997.8  392.74
  5006.2  395.40  5011.9  394.94  5033.7  396.03  5071.7  396.59  5077.4  397.19
  5087.8  396.28  5115.4  396.35  5188.8  398.03  5201.6  399.14  5314.1  401.14
  5431.5  402.05  5497.0  401.64  5551.2  402.10  5657.0  404.29  5894.9  407.78
#Mann=10,-1,0
  4508.5    0.05       0  4848.3    0.07       0  4909.7   0.035       0
  4955.0    0.07       0  4974.0    0.05       0  4993.8    0.05       0
  4997.8    0.05       0  5087.8    0.07       0  5201.6   0.045       0
  5657.0    0.05       0
Bank Sta=4993.8,4997.8
Exp/Cntr=0.3,0.1

Type RM Length L Ch R = 1,716,494,494,494
BEGIN DESCRIPTION:
XS6810
END DESCRIPTION:
XS GIS Cut Line= 2
      2490954.15     13816380.20      2490356.98     13815908.01
#Sta/Elev= 30
  4829.6  397.04  4875.7  397.37  4903.6  396.15  4946.2  394.01  4968.7  393.85
  4975.1  393.16  5003.9  392.71  5016.4  391.38  5016.6  390.88  5020.1  390.88
  5020.4  391.38  5049.1  392.12  5103.3  395.00  5109.7  394.78  5132.2  396.05
  5138.6  395.76  5146.6  396.49  5153.0  396.29  5167.4  397.50  5173.8  397.38
  5202.6  398.89  5274.7  400.70  5287.6  400.56  5295.7  401.26  5325.4  402.00
  5361.4  403.09  5430.3  405.07  5448.3  404.99  5526.0  406.28  5590.9  405.84
#Mann=10,-1,0
  4829.6     0.1       0  4903.6   0.045       0  5016.4   0.045       0
  5020.4   0.045       0  5049.1    0.05       0  5202.6   0.045       0
  5325.4   0.035       0  5361.4   0.045       0  5448.3   0.035       0
  5526.0    0.05       0
Bank Sta=5016.4,5020.4
Exp/Cntr=0.3,0.1

Type RM Length L Ch R = 1,222,0,0,0
BEGIN DESCRIPTION:
XS6809
END DESCRIPTION:
XS GIS Cut Line= 3
      2491110.40     13816140.59      2490988.89     13815835.07
      2490469.04     13815627.13
#Sta/Elev= 30
  4650.1  396.36  4704.9  396.26  4788.6  394.30  4957.5  391.90  5012.7  389.52
  5013.0  389.02  5016.5  389.02  5016.7  389.52  5036.9  390.33  5058.5  392.38
  5078.1  393.07  5176.3  396.33  5181.7  395.99  5230.2  398.29  5235.5  397.95
  5259.8  399.19  5265.2  398.76  5284.0  400.15  5289.4  399.58  5313.6  400.86
  5319.0  400.52  5367.5  402.20  5421.3  403.19  5445.6  403.10  5450.9  402.58
  5467.8  402.83  5475.2  403.60  5480.6  403.00  5504.8  402.87  5538.8  403.74
#Mann=4,-1,0
  4650.1   0.045       0  5012.7   0.045       0  5016.7   0.045       0
  5078.1    0.05       0
Bank Sta=5012.7,5016.7
Exp/Cntr=0.3,0.1

Chan Stop Cuts=-1