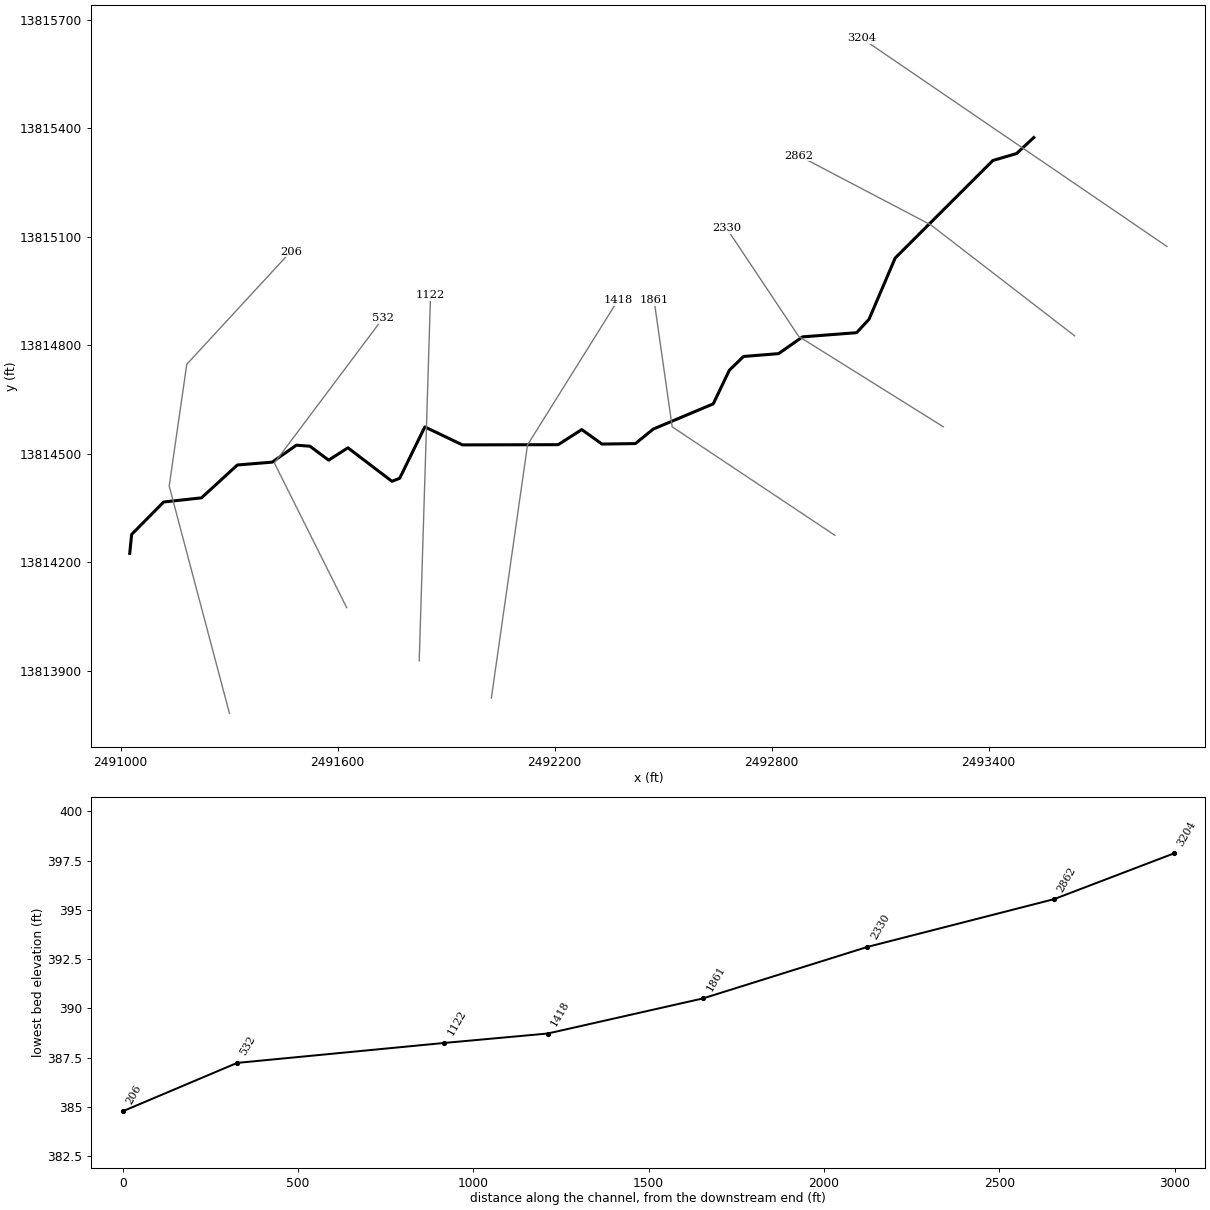
--- Stream0443.prj (project) ---

Proj Title=Stream0443 Base Level Engineering
Current Plan=p01
Default Exp/Contr=0.3,0.1
English Units
Geom File=g01
Flow File=f01
Plan File=p01
BEGIN DESCRIPTION:
Stream0443
END DESCRIPTION:

--- Stream0443.p01 (plan) ---

Plan Title=Multiple Run
Short Identifier=Multiple
Geom File=g01
Flow File=f01
Subcritical Flow
K Sum by GR= 0
Std Step Tol= 0.01
Critical Tol= 0.01
Num of Std Step Trials= 20
Max Error Tol= 0.3
Flow Tol Ratio= 0.001
Split Flow NTrial= 30
Split Flow Tol= 0.02
Split Flow Ratio= 0.02
Log Output Level= 0
Friction Slope Method= 1
Unsteady Friction Slope Method= 2
Unsteady Bridges Friction Slope Method= 1
Parabolic Critical Depth
Global Vel Dist=  1 , 1 , 1
Global Log Level= 0
CheckData=True
Encroach Param= -1, 0, 0, 0
BEGIN DESCRIPTION:
Multiple Run
END DESCRIPTION:

--- Stream0443.f01 (steady flow) ---

Flow Title=Multiple
Number of Profiles=7
Profile Names=10-year,25-year,50-year,1pct_min,100-year,1pct_plu,500-year
River Rch & RM= Stream0443,Reach-1,3204
     901    1468    1985    1299    2593    5173    4378
Boundary for River Rch & Prof#=Stream0443,Reach-1,1
Up Type=0
Dn Type=3
Dn Slope=0.005
Boundary for River Rch & Prof#=Stream0443,Reach-1,2
Up Type=0
Dn Type=3
Dn Slope=0.005
Boundary for River Rch & Prof#=Stream0443,Reach-1,3
Up Type=0
Dn Type=3
Dn Slope=0.005
Boundary for River Rch & Prof#=Stream0443,Reach-1,4
Up Type=0
Dn Type=3
Dn Slope=0.005
Boundary for River Rch & Prof#=Stream0443,Reach-1,5
Up Type=0
Dn Type=3
Dn Slope=0.005
Boundary for River Rch & Prof#=Stream0443,Reach-1,6
Up Type=0
Dn Type=3
Dn Slope=0.005
Boundary for River Rch & Prof#=Stream0443,Reach-1,7
Up Type=0
Dn Type=3
Dn Slope=0.005

--- Stream0443.g01 (geometry) ---

Geom Title=Existing Conditions

River Reach=Stream0443,Reach-1
Reach XY= 30
      2493525.00     13815375.00      2493477.35     13815330.71
      2493411.77     13815311.43      2493141.64     13815041.68
      2493069.29     13814872.42      2493035.12     13814835.35
      2492885.51     13814823.77      2492819.02     13814777.36
      2492722.33     13814769.58      2492683.03     13814731.36
      2492638.56     13814638.48      2492472.82     13814568.88
      2492423.41     13814528.68      2492330.89     13814527.36
      2492275.00     13814567.44      2492209.84     13814525.66
      2491945.01     13814525.09      2491841.00     13814574.77
      2491771.49     13814432.70      2491750.09     13814424.38
      2491628.33     13814516.99      2491575.09     13814482.84
      2491523.37     13814521.41      2491485.71     13814524.19
      2491419.03     13814477.38      2491322.58     13814469.46
      2491223.50     13814378.63      2491118.81     13814367.16
      2491030.30     13814277.54      2491025.00     13814225.00

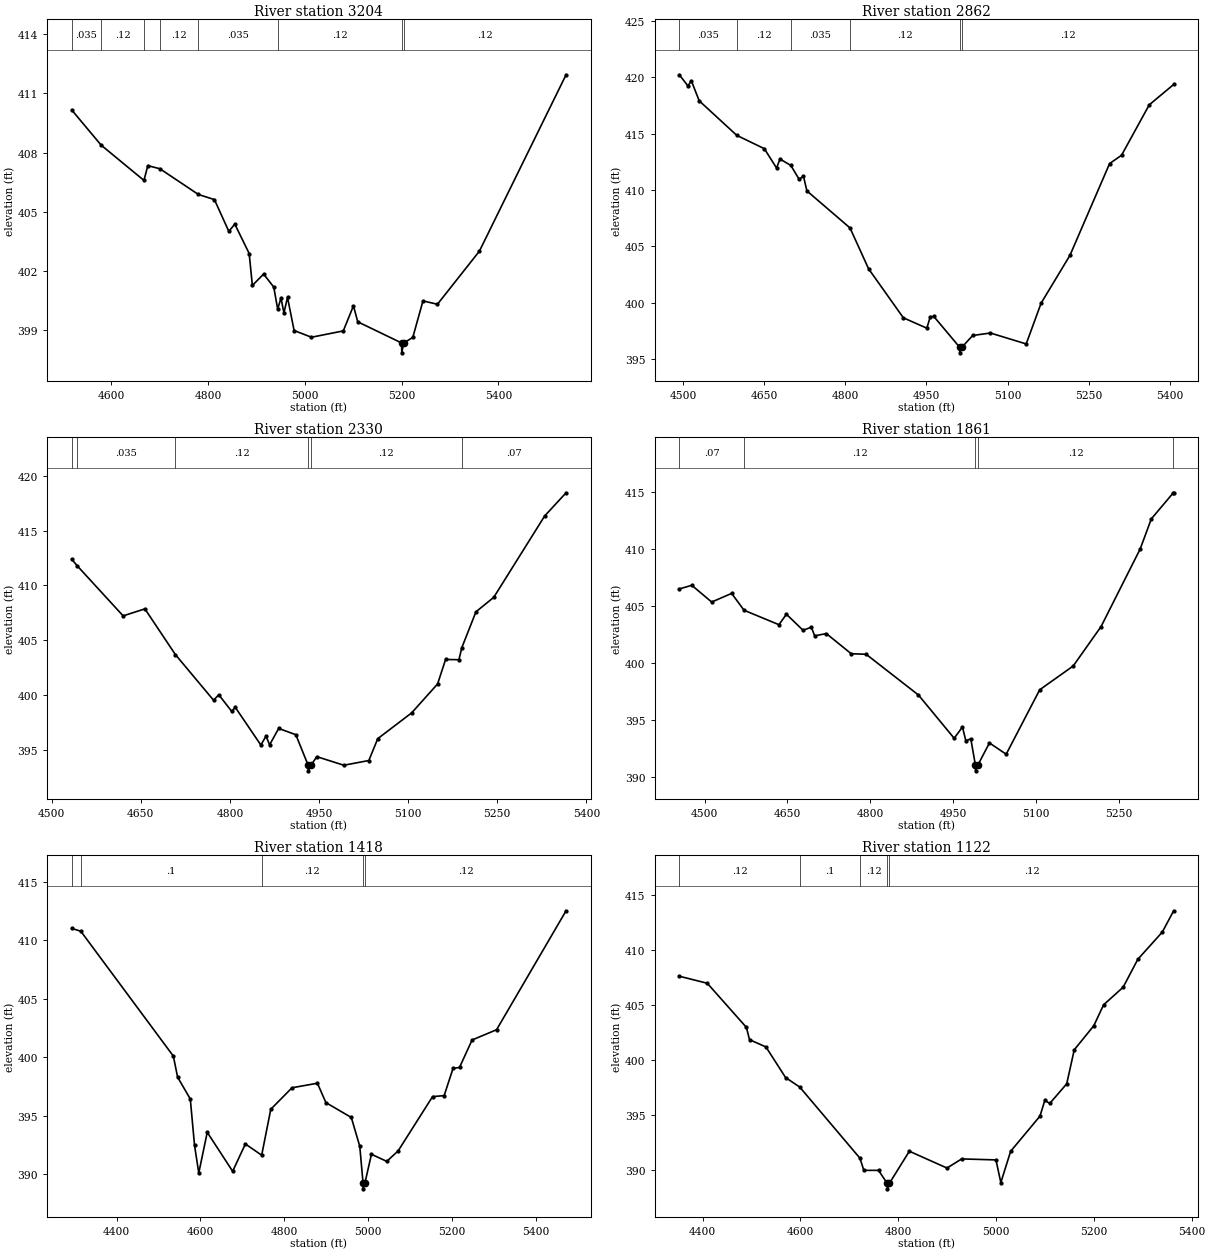
Type RM Length L Ch R = 1,3204,342,342,342
BEGIN DESCRIPTION:
XS6814
END DESCRIPTION:
XS GIS Cut Line= 2
      2493893.27     13815073.67      2493049.76     13815649.29
#Sta/Elev= 30
  4518.7  410.16  4579.4  408.38  4668.0  406.59  4675.9  407.34  4701.0  407.18
  4780.3  405.88  4813.5  405.62  4843.3  404.01  4855.6  404.38  4885.3  402.89
  4891.9  401.27  4915.1  401.85  4936.1  401.19  4944.2  400.07  4951.0  400.64
  4957.1  399.88  4964.5  400.67  4978.1  398.99  5014.0  398.65  5079.7  398.97
  5100.7  400.24  5109.6  399.43  5200.2  398.36  5200.5  397.86  5204.5  398.36
  5223.3  398.64  5244.3  400.49  5274.2  400.32  5360.9  403.01  5539.9  411.94
#Mann=8,-1,0
  4518.7   0.035       0  4579.4    0.12       0  4668.0   0.035       0
  4701.0    0.12       0  4780.3   0.035       0  4944.2    0.12       0
  5200.2    0.05       0  5204.5    0.12       0
Bank Sta=5200.2,5204.5
Exp/Cntr=0.3,0.1

Type RM Length L Ch R = 1,2862,532,532,532
BEGIN DESCRIPTION:
Stream0443 5.0
END DESCRIPTION:
XS GIS Cut Line= 3
      2493637.99     13814826.59      2493239.58     13815133.85
      2492874.98     13815325.01
#Sta/Elev= 30
  4492.6  420.23  4508.6  419.24  4514.9  419.70  4529.4  417.92  4599.0  414.85
  4649.9  413.67  4672.6  411.95  4678.9  412.75  4699.0  412.18  4714.2  410.96
  4722.4  411.22  4728.7  409.92  4808.5  406.63  4842.9  403.00  4907.2  398.65
  4950.7  397.73  4957.0  398.75  4963.6  398.77  5011.3  396.04  5011.6  395.54
  5015.6  396.04  5035.5  397.08  5068.3  397.30  5134.5  396.33  5162.2  399.96
  5215.4  404.19  5288.9  412.35  5310.9  413.08  5362.2  417.56  5407.4  419.37
#Mann=6,-1,0
  4492.6   0.035       0  4599.0    0.12       0  4699.0   0.035       0
  4808.5    0.12       0  5011.3    0.05       0  5015.6    0.12       0
Bank Sta=5011.3,5015.6
Exp/Cntr=0.3,0.1

Type RM Length L Ch R = 1,2330,469,469,469
BEGIN DESCRIPTION:
Stream0443 4.0
END DESCRIPTION:
XS GIS Cut Line= 3
      2493274.96     13814575.02      2492875.00     13814825.00
      2492675.01     13815124.99
#Sta/Elev= 30
  4533.6  412.39  4542.9  411.79  4620.2  407.23  4656.8  407.87  4708.1  403.71
  4772.4  399.55  4781.2  400.05  4803.0  398.53  4808.9  398.91  4852.0  395.47
  4860.8  396.29  4866.7  395.48  4882.0  396.98  4910.9  396.41  4931.7  393.62
  4932.0  393.12  4936.1  393.62  4946.3  394.41  4991.7  393.63  5033.8  394.06
  5048.8  396.05  5105.9  398.40  5149.5  401.03  5163.0  403.26  5185.5  403.24
  5190.2  404.32  5214.1  407.60  5244.1  408.92  5329.8  416.33  5365.8  418.44
#Mann=6,-1,0
  4533.6    0.12       0  4542.9   0.035       0  4708.1    0.12       0
  4931.7    0.05       0  4936.1    0.12       0  5190.2    0.07       0
Bank Sta=4931.7,4936.1
Exp/Cntr=0.3,0.1

Type RM Length L Ch R = 1,1861,443,443,443
BEGIN DESCRIPTION:
Stream0443 3.0
END DESCRIPTION:
XS GIS Cut Line= 3
      2492975.04     13814274.97      2492525.00     13814575.00
      2492475.00     13814924.97
#Sta/Elev= 30
  4454.4  406.49  4477.0  406.81  4513.0  405.34  4549.1  406.10  4571.5  404.62
  4634.7  403.35  4648.2  404.27  4678.3  402.86  4693.3  403.13  4699.3  402.37
  4720.4  402.57  4765.4  400.80  4792.5  400.75  4887.1  397.17  4951.7  393.37
  4966.7  394.37  4972.7  393.16  4981.8  393.32  4990.1  391.01  4990.4  390.51
  4994.5  391.01  5015.5  392.96  5045.8  391.97  5106.4  397.63  5167.0  399.72
  5217.5  403.19  5288.2  410.00  5308.4  412.65  5348.2  414.94  5348.8  414.94
#Mann=5,-1,0
  4454.4    0.07       0  4571.5    0.12       0  4990.1    0.05       0
  4994.5    0.12       0  5348.2    0.07       0
Bank Sta=4990.1,4994.5
Exp/Cntr=0.3,0.1

Type RM Length L Ch R = 1,1418,296,296,296
BEGIN DESCRIPTION:
Stream0443 2.0
END DESCRIPTION:
XS GIS Cut Line= 3
      2492025.00     13813825.02      2492125.00     13814525.00
      2492375.01     13814925.01
#Sta/Elev= 30
  4293.0  411.02  4314.7  410.78  4535.4  400.09  4545.5  398.29  4575.8  396.42
  4585.9  392.45  4596.0  390.09  4616.2  393.57  4676.8  390.23  4707.1  392.57
  4746.0  391.61  4767.7  395.54  4818.3  397.38  4878.9  397.77  4899.1  396.11
  4959.7  394.84  4979.9  392.37  4987.7  389.23  4988.0  388.73  4992.2  389.23
  5007.7  391.69  5044.3  391.08  5071.4  391.98  5153.4  396.62  5181.1  396.71
  5202.3  399.04  5217.7  399.12  5247.7  401.47  5306.1  402.35  5471.8  412.53
#Mann=5,-1,0
  4293.0    0.12       0  4314.7     0.1       0  4746.0    0.12       0
  4987.7    0.05       0  4992.2    0.12       0
Bank Sta=4987.7,4992.2
Exp/Cntr=0.3,0.1

Type RM Length L Ch R = 1,1122,590,590,590
BEGIN DESCRIPTION:
XS6813
END DESCRIPTION:
XS GIS Cut Line= 2
      2491825.52     13813927.84      2491856.77     13814938.25
#Sta/Elev= 30
  4352.2  407.58  4409.4  406.94  4489.4  402.93  4495.8  401.81  4529.4  401.15
  4569.5  398.37  4598.5  397.50  4721.7  391.03  4729.5  389.93  4759.6  389.93
  4777.3  388.75  4777.6  388.25  4781.8  388.75  4822.6  391.67  4899.6  390.14
  4929.6  390.97  4999.7  390.88  5009.7  388.82  5029.7  391.66  5089.7  394.86
  5099.7  396.30  5109.7  396.01  5144.4  397.80  5159.8  400.89  5199.8  403.08
  5219.8  404.98  5259.8  406.58  5289.8  409.12  5339.8  411.59  5363.1  413.53
#Mann=5,-1,0
  4352.2    0.12       0  4598.5     0.1       0  4721.7    0.12       0
  4777.3    0.05       0  4781.8    0.12       0
Bank Sta=4777.3,4781.8
Exp/Cntr=0.3,0.1

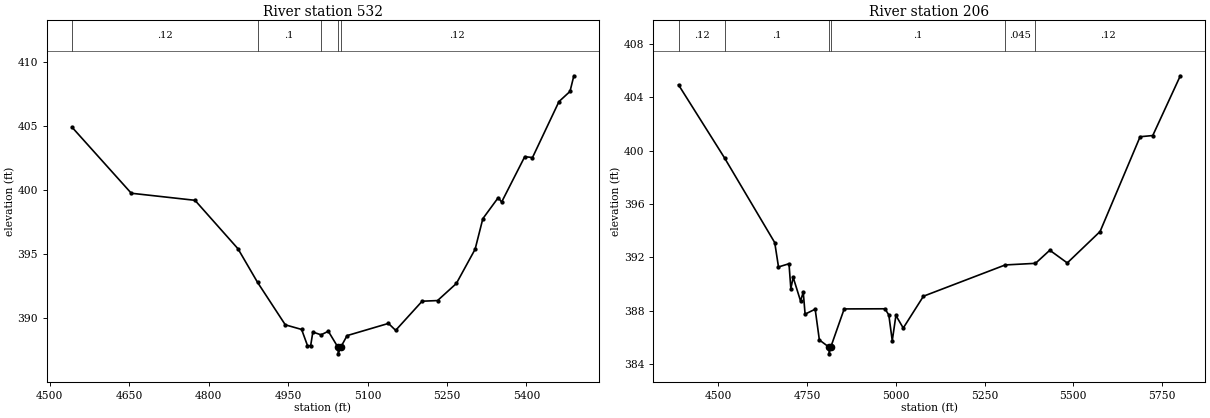
Type RM Length L Ch R = 1,532,326,326,326
BEGIN DESCRIPTION:
Stream0443 1.0
END DESCRIPTION:
XS GIS Cut Line= 3
      2491625.01     13814074.99      2491425.00     13814475.00
      2491724.98     13814874.98
#Sta/Elev= 30
  4542.2  404.89  4654.0  399.75  4774.2  399.20  4855.3  395.43  4892.3  392.81
  4944.7  389.50  4975.5  389.14  4986.6  387.88  4992.6  387.88  4996.7  388.94
  5012.2  388.72  5025.9  389.00  5044.3  387.74  5044.6  387.24  5049.2  387.74
  5061.3  388.66  5139.4  389.61  5153.0  389.07  5203.0  391.34  5232.1  391.39
  5267.6  392.72  5303.0  395.39  5317.6  397.77  5346.7  399.41  5353.0  399.06
  5396.7  402.60  5411.3  402.53  5461.3  406.89  5482.1  407.68  5489.4  408.90
#Mann=5,-1,0
  4542.2    0.12       0  4892.3     0.1       0  5012.2    0.12       0
  5044.3    0.05       0  5049.2    0.12       0
Bank Sta=5044.3,5049.2
Exp/Cntr=0.3,0.1

Type RM Length L Ch R = 1,206,0,0,0
BEGIN DESCRIPTION:
XS6812
END DESCRIPTION:
XS GIS Cut Line= 4
      2491300.79     13813782.63      2491134.12     13814411.11
      2491182.74     13814747.92      2491470.35     13815059.59
#Sta/Elev= 30
  4387.4  404.91  4517.2  399.44  4658.6  393.11  4669.2  391.29  4698.8  391.53
  4704.0  389.67  4710.6  390.51  4731.3  388.75  4739.0  389.40  4744.2  387.76
  4772.6  388.13  4784.4  385.83  4811.6  385.29  4811.9  384.79  4816.5  385.29
  4854.4  388.15  4969.2  388.16  4980.2  387.70  4989.9  385.77  5000.2  387.66
  5020.9  386.72  5077.8  389.10  5308.4  391.44  5393.7  391.56  5434.0  392.54
  5483.3  391.59  5575.8  393.94  5688.6  401.03  5724.3  401.12  5802.0  405.59
#Mann=6,-1,0
  4387.4    0.12       0  4517.2     0.1       0  4811.6    0.05       0
  4816.5     0.1       0  5308.4   0.045       0  5393.7    0.12       0
Bank Sta=4811.6,4816.5
Exp/Cntr=0.3,0.1

Chan Stop Cuts=-1