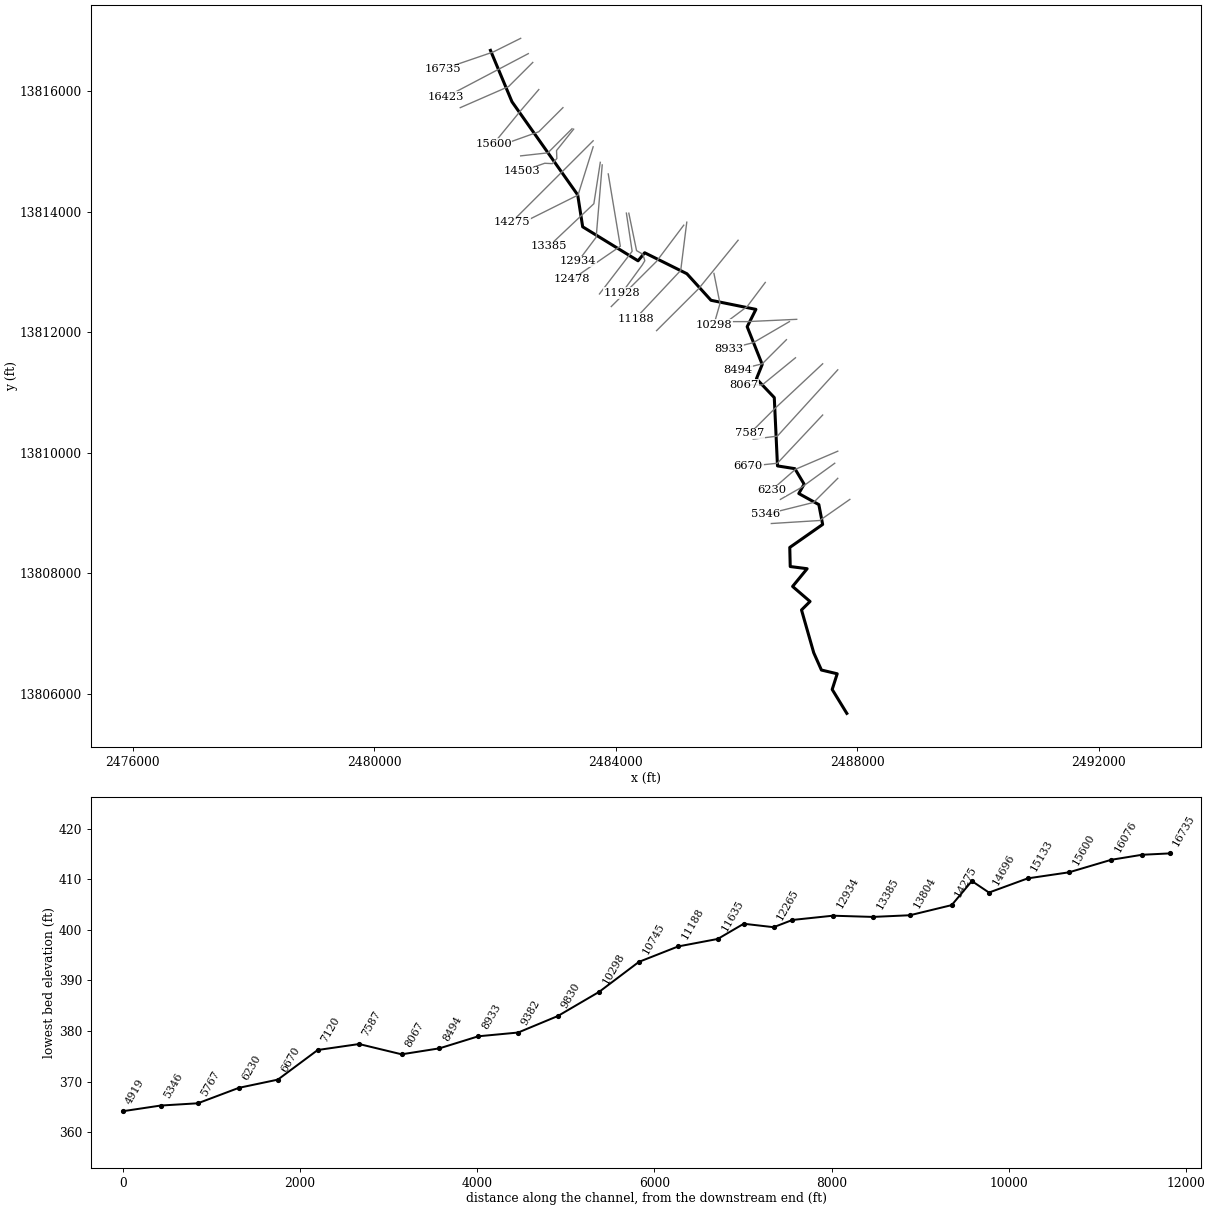
--- Stream0444.prj (project) ---

Proj Title=Stream0444 Base Level Engineering
Current Plan=p01
Default Exp/Contr=0.3,0.1
English Units
Geom File=g01
Flow File=f01
Plan File=p01
BEGIN DESCRIPTION:
Stream0444
END DESCRIPTION:

--- Stream0444.p01 (plan) ---

Plan Title=Multiple Run
Short Identifier=Multiple
Geom File=g01
Flow File=f01
Subcritical Flow
K Sum by GR= 0
Std Step Tol= 0.01
Critical Tol= 0.01
Num of Std Step Trials= 20
Max Error Tol= 0.3
Flow Tol Ratio= 0.001
Split Flow NTrial= 30
Split Flow Tol= 0.02
Split Flow Ratio= 0.02
Log Output Level= 0
Friction Slope Method= 1
Unsteady Friction Slope Method= 2
Unsteady Bridges Friction Slope Method= 1
Parabolic Critical Depth
Global Vel Dist=  1 , 1 , 1
Global Log Level= 0
CheckData=True
Encroach Param= -1, 0, 0, 0
BEGIN DESCRIPTION:
Multiple Run
END DESCRIPTION:

--- Stream0444.f01 (steady flow) ---

Flow Title=Multiple
Number of Profiles=7
Profile Names=10-year,25-year,50-year,1pct_min,100-year,1pct_plu,500-year
River Rch & RM= Stream0444,Reach-1,16735
     608     960    1272     815    1626    3245    2633
River Rch & RM= Stream0444,Reach-1,15600
     876    1406    1881    1217    2428    4844    4004
River Rch & RM= Stream0444,Reach-1,9382
    1218    1992    2699    1766    3524    7031    5950
River Rch & RM= Stream0444,Reach-1,4919
    1318    2165    2942    1930    3851    7684    6535
Boundary for River Rch & Prof#=Stream0444,Reach-1,1
Up Type=0
Dn Type=3
Dn Slope=0.005
Boundary for River Rch & Prof#=Stream0444,Reach-1,2
Up Type=0
Dn Type=3
Dn Slope=0.005
Boundary for River Rch & Prof#=Stream0444,Reach-1,3
Up Type=0
Dn Type=3
Dn Slope=0.005
Boundary for River Rch & Prof#=Stream0444,Reach-1,4
Up Type=0
Dn Type=3
Dn Slope=0.005
Boundary for River Rch & Prof#=Stream0444,Reach-1,5
Up Type=0
Dn Type=3
Dn Slope=0.005
Boundary for River Rch & Prof#=Stream0444,Reach-1,6
Up Type=0
Dn Type=3
Dn Slope=0.005
Boundary for River Rch & Prof#=Stream0444,Reach-1,7
Up Type=0
Dn Type=3
Dn Slope=0.005

--- Stream0444.g01 (geometry) ---

Geom Title=Existing Conditions

River Reach=Stream0444,Reach-1
Reach XY= 30
      2481925.00     13816675.00      2482280.83     13815822.70
      2483369.19     13814277.29      2483451.48     13813747.99
      2484368.22     13813183.82      2484478.15     13813317.47
      2485177.30     13812969.17      2485576.50     13812528.61
      2486319.87     13812377.95      2486175.24     13812090.21
      2486424.28     13811464.29      2486328.46     13811226.50
      2486623.95     13810914.57      2486677.06     13809780.83
      2486964.94     13809735.12      2487117.52     13809478.62
      2487029.96     13809322.46      2487361.73     13809138.69
      2487424.76     13808809.77      2486880.39     13808427.98
      2486887.98     13808111.29      2487168.03     13808075.25
      2486926.96     13807780.90      2487216.06     13807531.68
      2487074.75     13807390.71      2487277.10     13806680.72
      2487404.48     13806394.09      2487665.82     13806331.95
      2487582.79     13806071.94      2487825.00     13805675.00

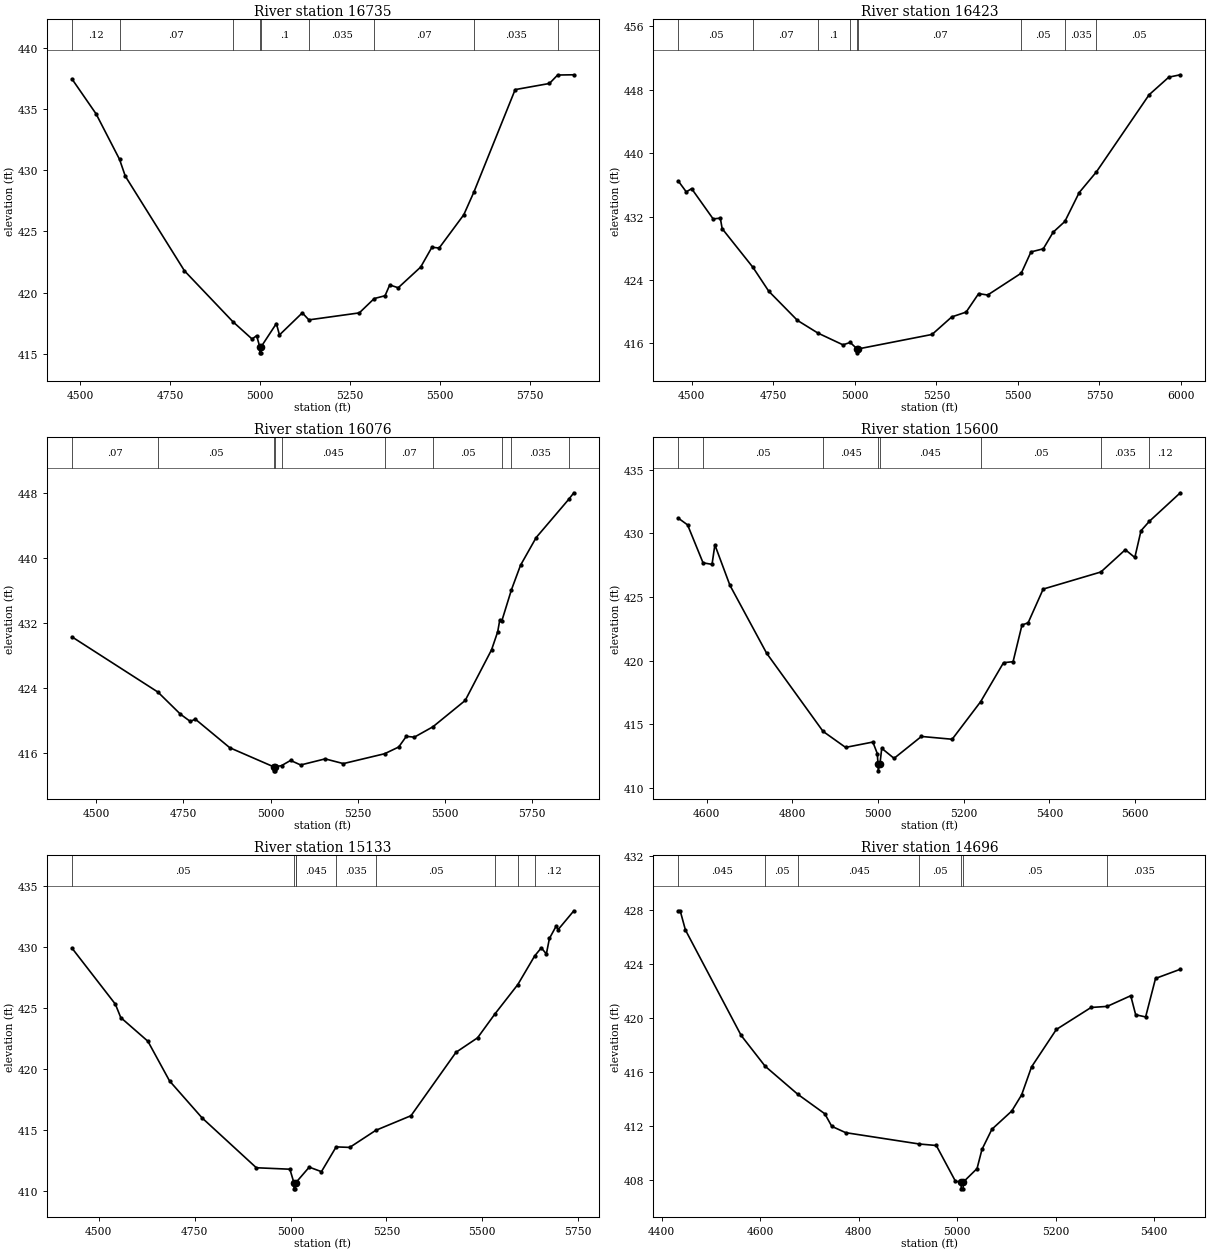
Type RM Length L Ch R = 1,16735,312,312,312
BEGIN DESCRIPTION:
Stream0444 33.0
END DESCRIPTION:
XS GIS Cut Line= 3
      2482425.01     13816875.01      2481971.25     13816648.81
      2481130.66     13816360.72
#Sta/Elev= 30
  4477.7  437.44  4544.8  434.59  4610.0  430.88  4626.0  429.51  4790.6  421.78
  4924.9  417.64  4978.5  416.22  4991.3  416.49  4999.8  415.59  5000.1  415.09
  5003.7  415.09  5003.9  415.59  5046.1  417.48  5054.7  416.55  5118.2  418.35
  5136.5  417.78  5276.7  418.35  5318.2  419.52  5348.3  419.75  5361.3  420.63
  5384.9  420.40  5447.4  422.09  5478.7  423.71  5498.7  423.64  5567.3  426.36
  5595.2  428.20  5710.1  436.57  5805.3  437.07  5828.2  437.76  5873.3  437.78
#Mann=9,-1,0
  4477.7    0.12       0  4610.0    0.07       0  4924.9     0.1       0
  4999.8    0.05       0  5003.9     0.1       0  5136.5   0.035       0
  5318.2    0.07       0  5595.2   0.035       0  5828.2    0.05       0
Bank Sta=4999.8,5003.9
Exp/Cntr=0.3,0.1

Type RM Length L Ch R = 1,16423,347,347,347
BEGIN DESCRIPTION:
XS6821
END DESCRIPTION:
XS GIS Cut Line= 2
      2482551.40     13816621.19      2481189.93     13815902.97
#Sta/Elev= 30
  4458.8  436.47  4482.9  435.12  4499.3  435.53  4565.3  431.71  4587.3  431.81
  4593.0  430.48  4687.6  425.59  4735.9  422.59  4823.9  418.91  4886.8  417.31
  4963.5  415.83  4985.7  416.13  5006.7  415.32  5006.9  414.82  5010.8  415.32
  5236.7  417.14  5297.1  419.35  5341.2  419.96  5379.6  422.29  5407.2  422.11
  5510.3  424.87  5540.1  427.55  5577.8  427.94  5608.0  430.03  5644.0  431.39
  5687.9  435.03  5740.9  437.65  5902.4  447.37  5962.8  449.59  5998.1  449.89
#Mann=9,-1,0
  4458.8    0.05       0  4687.6    0.07       0  4886.8     0.1       0
  4985.7    0.07       0  5006.7    0.05       0  5010.8    0.07       0
  5510.3    0.05       0  5644.0   0.035       0  5740.9    0.05       0
Bank Sta=5006.7,5010.8
Exp/Cntr=0.3,0.1

Type RM Length L Ch R = 1,16076,476,476,476
BEGIN DESCRIPTION:
Stream0444 32.0
END DESCRIPTION:
XS GIS Cut Line= 3
      2482624.97     13816474.97      2482225.00     13816075.00
      2481424.96     13815724.98
#Sta/Elev= 30
  4430.5  430.30  4677.0  423.51  4741.6  420.79  4769.9  419.90  4784.0  420.19
  4883.0  416.67  5008.5  414.33  5008.8  413.83  5012.4  413.83  5012.6  414.33
  5031.3  414.47  5057.3  415.11  5086.2  414.55  5156.4  415.30  5208.6  414.72
  5326.7  415.93  5367.3  416.76  5389.1  418.07  5412.1  417.97  5465.5  419.25
  5557.9  422.48  5633.5  428.71  5651.1  430.93  5656.9  432.35  5662.9  432.26
  5690.4  436.08  5716.5  439.10  5761.4  442.51  5854.4  447.19  5869.4  448.01
#Mann=10,-1,0
  4430.5    0.07       0  4677.0    0.05       0  5008.5    0.05       0
  5012.6    0.05       0  5031.3   0.045       0  5326.7    0.07       0
  5465.5    0.05       0  5662.9    0.07       0  5690.4   0.035       0
  5854.4    0.05       0
Bank Sta=5008.5,5012.6
Exp/Cntr=0.3,0.1

Type RM Length L Ch R = 1,15600,467,467,467
BEGIN DESCRIPTION:
Stream0444 31.0
END DESCRIPTION:
XS GIS Cut Line= 3
      2482725.02     13816025.02      2482425.00     13815675.00
      2481975.03     13815125.03
#Sta/Elev= 30
  4533.9  431.19  4555.3  430.67  4591.4  427.69  4612.4  427.57  4619.0  429.10
  4654.1  425.93  4739.7  420.60  4871.5  414.46  4924.1  413.20  4987.8  413.62
  4998.1  412.72  4999.9  411.86  5000.2  411.36  5004.2  411.86  5008.5  413.13
  5037.3  412.34  5101.1  414.06  5172.9  413.84  5239.4  416.79  5292.8  419.85
  5315.1  419.93  5335.9  422.81  5350.2  422.98  5385.4  425.63  5520.0  426.97
  5577.1  428.72  5599.3  428.11  5613.7  430.21  5633.2  430.95  5705.5  433.19
#Mann=8,-1,0
  4533.9   0.035       0  4591.4    0.05       0  4871.5   0.045       0
  4999.9   0.045       0  5004.2   0.045       0  5239.4    0.05       0
  5520.0   0.035       0  5633.2    0.12       0
Bank Sta=4999.9,5004.2
Exp/Cntr=0.3,0.1

Type RM Length L Ch R = 1,15133,437,437,437
BEGIN DESCRIPTION:
Stream0444 30.0
END DESCRIPTION:
XS GIS Cut Line= 3
      2483125.02     13815725.02      2482725.00     13815325.00
      2482025.02     13815075.01
#Sta/Elev= 30
  4430.0  429.91  4543.2  425.31  4557.3  424.21  4628.0  422.27  4684.6  419.01
  4769.4  415.98  4910.9  411.89  4998.4  411.77  5008.9  410.66  5009.2  410.16
  5013.0  410.16  5013.3  410.66  5015.4  410.72  5048.8  411.94  5080.7  411.57
  5119.0  413.60  5154.5  413.56  5222.5  414.96  5314.3  416.16  5431.6  421.36
  5487.9  422.55  5533.2  424.51  5592.9  426.92  5636.7  429.26  5654.1  429.93
  5667.3  429.43  5675.3  430.70  5692.8  431.71  5698.1  431.43  5739.0  432.97
#Mann=9,-1,0
  4430.0    0.05       0  5008.9    0.05       0  5013.3    0.05       0
  5015.4   0.045       0  5119.0   0.035       0  5222.5    0.05       0
  5533.2    0.12       0  5592.9   0.035       0  5636.7    0.12       0
Bank Sta=5008.9,5013.3
Exp/Cntr=0.3,0.1

Type RM Length L Ch R = 1,14696,193,193,193
BEGIN DESCRIPTION:
Stream0444 29.0
END DESCRIPTION:
XS GIS Cut Line= 3
      2483275.02     13815375.02      2482875.00     13814975.00
      2482424.99     13814925.00
#Sta/Elev= 30
  4434.3  427.95  4437.9  427.95  4448.5  426.53  4561.6  418.72  4610.3  416.44
  4676.6  414.36  4731.3  412.92  4745.5  411.99  4773.7  411.52  4923.1  410.68
  4957.6  410.57  4996.5  407.92  5007.9  407.86  5008.2  407.36  5012.0  407.36
  5012.3  407.86  5040.3  408.86  5050.3  410.28  5070.4  411.77  5110.7  413.12
  5130.8  414.32  5150.9  416.39  5201.2  419.16  5271.7  420.79  5304.4  420.87
  5352.2  421.66  5362.2  420.25  5382.4  420.09  5402.5  422.94  5452.8  423.62
#Mann=7,-1,0
  4434.3   0.045       0  4610.3    0.05       0  4676.6   0.045       0
  4923.1    0.05       0  5007.9    0.05       0  5012.3    0.05       0
  5304.4   0.035       0
Bank Sta=5007.9,5012.3
Exp/Cntr=0.3,0.1

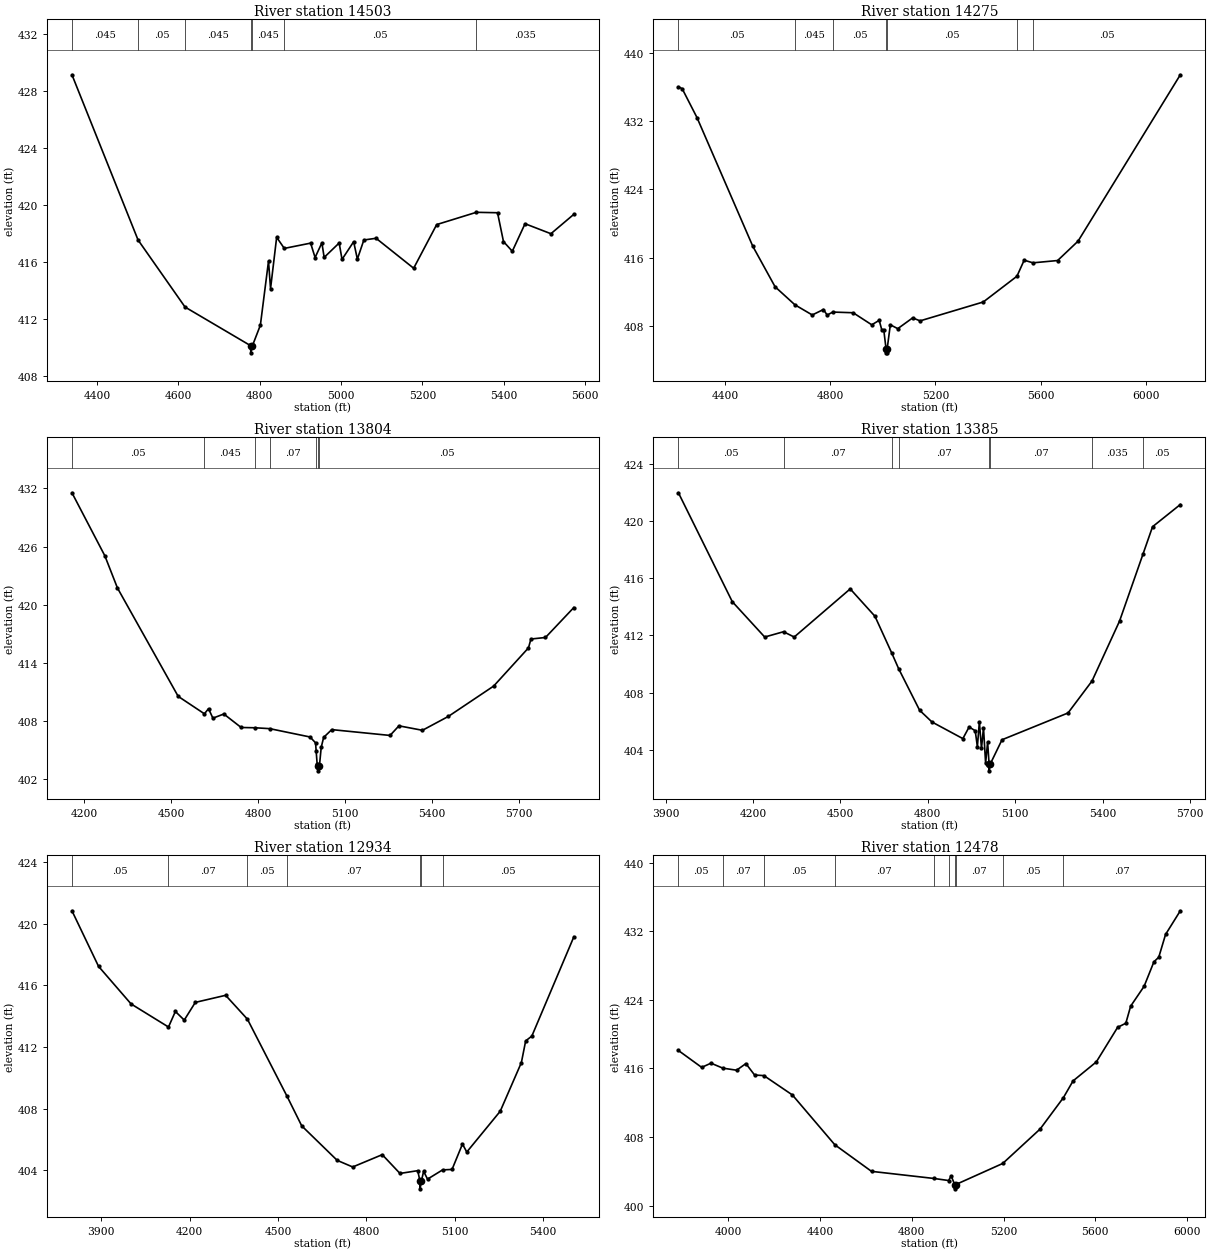
Type RM Length L Ch R = 1,14503,228,228,228
BEGIN DESCRIPTION:
Stream0444 29.0a
END DESCRIPTION:
XS GIS Cut Line= 6
      2483302.49     13815368.77      2483018.62     13815013.28
      2483024.10     13814881.61      2482950.91     13814795.83
      2482823.31     13814802.34      2482441.80     13814668.23
#Sta/Elev= 30
  4338.7  429.12  4501.2  417.54  4616.7  412.84  4778.0  410.13  4778.3  409.63
  4782.4  410.13  4801.9  411.57  4821.9  416.06  4826.9  414.13  4841.9  417.73
  4860.7  416.95  4925.4  417.32  4936.4  416.31  4953.1  417.34  4958.7  416.32
  4995.6  417.33  5002.6  416.18  5031.2  417.42  5040.3  416.20  5056.3  417.54
  5086.3  417.66  5178.7  415.56  5235.3  418.62  5332.8  419.48  5384.9  419.45
  5399.5  417.43  5421.2  416.75  5452.5  418.68  5516.1  417.98  5572.5  419.34
#Mann=7,-1,0
  4338.7   0.045       0  4501.2    0.05       0  4616.7   0.045       0
  4778.0    0.05       0  4782.4   0.045       0  4860.7    0.05       0
  5332.8   0.035       0
Bank Sta=4778,4782.4
Exp/Cntr=0.3,0.1

Type RM Length L Ch R = 1,14275,471,471,471
BEGIN DESCRIPTION:
Stream0444 28.0
END DESCRIPTION:
XS GIS Cut Line= 3
      2483625.01     13815175.01      2483075.00     13814625.00
      2482275.00     13813825.00
#Sta/Elev= 30
  4222.1  436.00  4236.3  435.79  4292.8  432.40  4505.0  417.35  4589.8  412.61
  4665.2  410.50  4731.2  409.31  4773.7  409.95  4787.8  409.30  4809.5  409.65
  4886.8  409.57  4957.5  408.16  4985.8  408.68  4996.4  407.50  5003.5  407.50
  5011.8  405.38  5012.1  404.88  5016.0  404.88  5016.3  405.38  5028.2  408.16
  5056.5  407.71  5113.1  408.97  5141.4  408.62  5381.8  410.83  5509.8  413.84
  5537.3  415.72  5570.7  415.41  5664.6  415.68  5742.4  417.95  6131.3  437.41
#Mann=7,-1,0
  4222.1    0.05       0  4665.2   0.045       0  4809.5    0.05       0
  5011.8    0.05       0  5016.3    0.05       0  5509.8   0.035       0
  5570.7    0.05       0
Bank Sta=5011.8,5016.3
Exp/Cntr=0.3,0.1

Type RM Length L Ch R = 1,13804,419,419,419
BEGIN DESCRIPTION:
Stream0444 27.0
END DESCRIPTION:
XS GIS Cut Line= 3
      2483624.99     13815074.97      2483375.00     13814275.00
      2482574.96     13813874.98
#Sta/Elev= 30
  4157.6  431.55  4271.2  425.05  4314.7  421.73  4524.3  410.56  4614.9  408.76
  4629.0  409.29  4644.2  408.31  4681.9  408.74  4741.7  407.35  4789.9  407.32
  4840.3  407.23  4979.5  406.37  4998.5  405.77  5000.7  404.90  5004.1  403.55
  5007.4  403.38  5007.7  402.88  5011.9  403.38  5018.1  405.31  5026.5  406.33
  5054.4  407.13  5255.7  406.53  5286.4  407.52  5367.5  407.06  5456.9  408.49
  5613.4  411.62  5733.6  415.56  5742.0  416.47  5792.3  416.63  5890.2  419.72
#Mann=7,-1,0
  4157.6    0.05       0  4614.9   0.045       0  4789.9    0.05       0
  4840.3    0.07       0  5000.7    0.05       0  5007.4    0.05       0
  5011.9    0.05       0
Bank Sta=5007.4,5011.9
Exp/Cntr=0.3,0.1

Type RM Length L Ch R = 1,13385,451,451,451
BEGIN DESCRIPTION:
XS6820
END DESCRIPTION:
XS GIS Cut Line= 3
      2483743.24     13814817.58      2483636.69     13814130.92
      2482890.79     13813424.49
#Sta/Elev= 30
  3944.2  421.96  4129.0  414.36  4240.3  411.89  4304.8  412.26  4341.5  411.89
  4533.7  415.25  4618.6  413.34  4676.5  410.76  4699.9  409.68  4771.8  406.78
  4814.2  405.96  4920.2  404.80  4941.7  405.61  4962.7  405.35  4970.0  404.23
  4976.9  405.97  4984.1  404.11  4991.0  405.56  4998.3  403.08  5005.2  404.56
  5010.1  403.05  5010.4  402.55  5014.8  403.05  5054.6  404.72  5281.1  406.59
  5363.4  408.82  5457.8  413.00  5538.0  417.66  5571.1  419.59  5666.4  421.14
#Mann=8,-1,0
  3944.2    0.05       0  4304.8    0.07       0  4676.5    0.05       0
  4699.9    0.07       0  5010.1    0.05       0  5014.8    0.07       0
  5363.4   0.035       0  5538.0    0.05       0
Bank Sta=5010.1,5014.8
Exp/Cntr=0.3,0.1

Type RM Length L Ch R = 1,12934,456,456,456
BEGIN DESCRIPTION:
Stream0444 26.0
END DESCRIPTION:
XS GIS Cut Line= 3
      2483775.00     13814775.00      2483675.00     13813575.00
      2483374.98     13813174.97
#Sta/Elev= 30
  3800.4  420.85  3890.7  417.24  4001.1  414.80  4128.2  413.30  4151.6  414.31
  4181.7  413.75  4219.3  414.90  4322.2  415.36  4396.2  413.81  4530.5  408.81
  4580.6  406.88  4701.0  404.64  4753.7  404.21  4854.0  405.01  4914.2  403.79
  4974.5  403.97  4982.1  403.29  4982.4  402.79  4986.9  403.29  4994.5  403.93
  5007.7  403.42  5058.8  404.02  5091.0  404.05  5126.4  405.70  5141.0  405.18
  5254.6  407.83  5326.4  410.99  5341.0  412.40  5361.9  412.71  5504.6  419.16
#Mann=7,-1,0
  3800.4    0.05       0  4128.2    0.07       0  4396.2    0.05       0
  4530.5    0.07       0  4982.1    0.05       0  4986.9    0.07       0
  5058.8    0.05       0
Bank Sta=4982.1,4986.9
Exp/Cntr=0.3,0.1

Type RM Length L Ch R = 1,12478,213,213,213
BEGIN DESCRIPTION:
Stream0444 25.0
END DESCRIPTION:
XS GIS Cut Line= 3
      2483874.99     13814625.03      2484075.00     13813425.00
      2483275.01     13812875.00
#Sta/Elev= 30
  3783.2  418.09  3884.6  416.12  3925.2  416.61  3976.8  416.03  4036.7  415.79
  4077.2  416.56  4115.2  415.23  4155.7  415.16  4280.0  412.90  4464.9  407.09
  4624.7  403.99  4896.9  403.16  4960.7  402.92  4971.9  403.46  4987.2  402.45
  4987.6  401.95  4992.0  402.45  5196.6  404.91  5359.7  408.93  5461.1  412.59
  5503.1  414.54  5604.6  416.76  5697.3  420.79  5733.1  421.27  5754.1  423.26
  5812.8  425.58  5855.6  428.44  5876.6  428.97  5906.3  431.63  5970.6  434.39
#Mann=10,-1,0
  3783.2    0.05       0  3976.8    0.07       0  4155.7    0.05       0
  4464.9    0.07       0  4896.9     0.1       0  4960.7    0.07       0
  4987.2    0.05       0  4992.0    0.07       0  5196.6    0.05       0
  5461.1    0.07       0
Bank Sta=4987.2,4992
Exp/Cntr=0.3,0.1

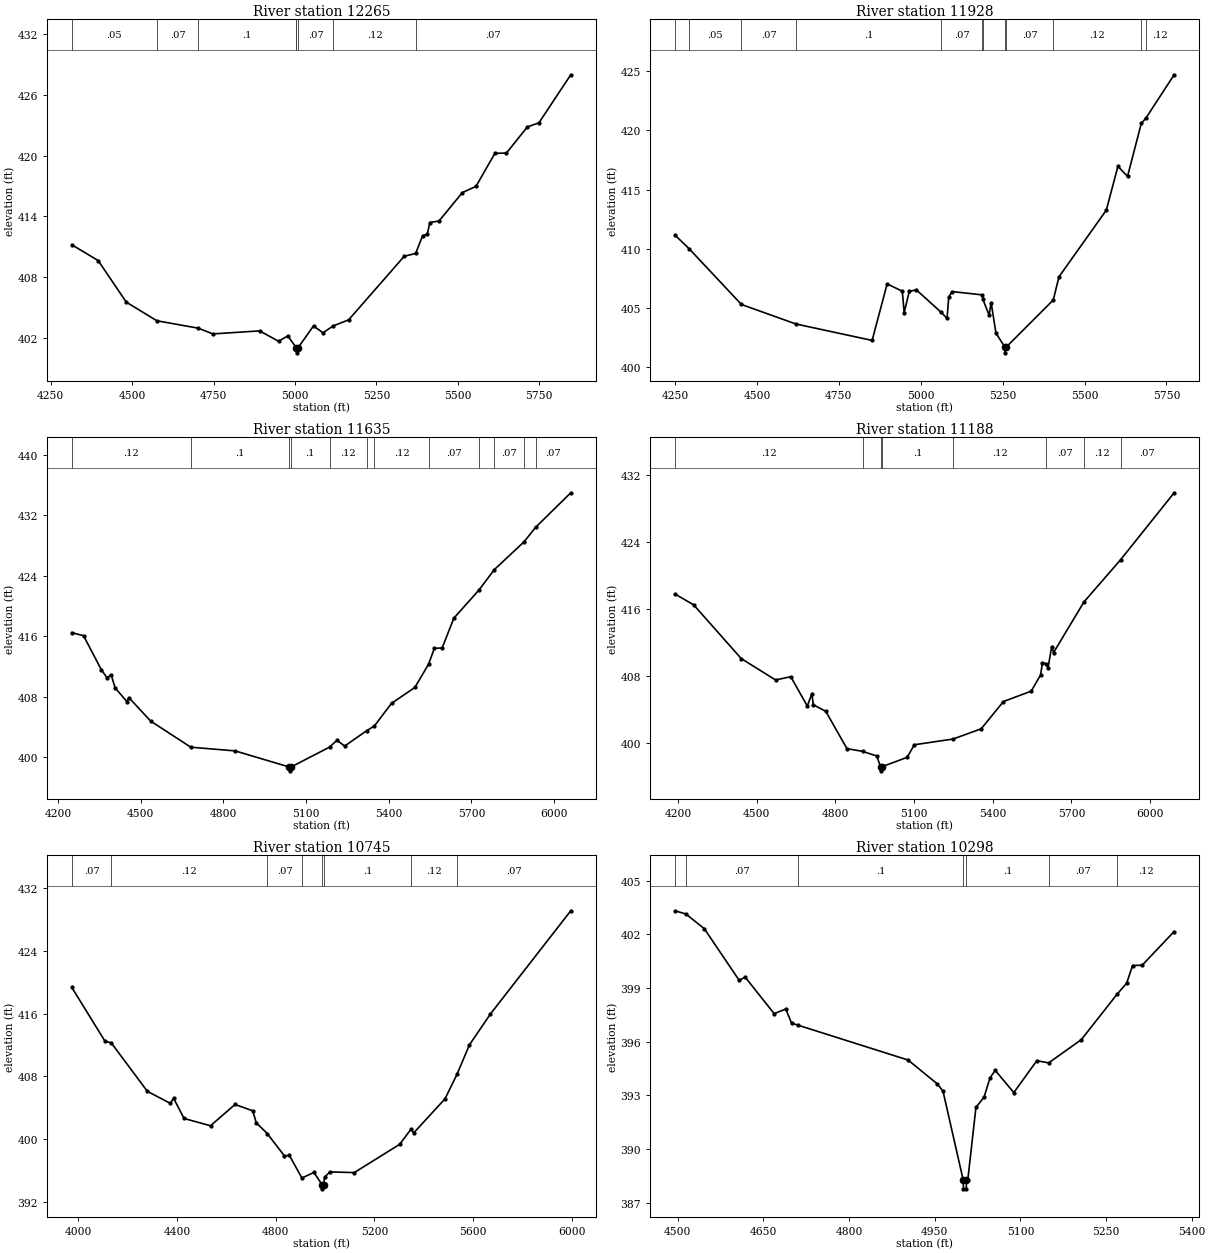
Type RM Length L Ch R = 1,12265,337,337,337
BEGIN DESCRIPTION:
Stream0444 24.0
END DESCRIPTION:
XS GIS Cut Line= 3
      2484175.00     13813975.02      2484270.57     13813341.41
      2483729.44     13812633.77
#Sta/Elev= 30
  4314.8  411.20  4395.7  409.64  4482.1  405.53  4575.8  403.69  4702.6  402.96
  4747.6  402.39  4891.3  402.69  4949.3  401.67  4977.8  402.19  5004.0  401.02
  5004.4  401.02  5004.7  400.52  5009.3  401.02  5056.7  403.18  5085.7  402.50
  5117.2  403.18  5164.6  403.78  5335.1  410.06  5370.4  410.35  5391.7  412.10
  5405.8  412.23  5414.0  413.40  5442.0  413.55  5513.7  416.36  5555.4  416.97
  5613.5  420.24  5648.8  420.26  5713.2  422.85  5748.6  423.25  5846.4  428.00
#Mann=8,-1,0
  4314.8    0.05       0  4575.8    0.07       0  4702.6     0.1       0
  5004.0    0.07       0  5004.4    0.05       0  5009.3    0.07       0
  5117.2    0.12       0  5370.4    0.07       0
Bank Sta=5004.4,5009.3
Exp/Cntr=0.3,0.1

Type RM Length L Ch R = 1,11928,293,293,293
BEGIN DESCRIPTION:
Stream0444 24.0a
END DESCRIPTION:
XS GIS Cut Line= 6
      2484215.54     13813973.74      2484343.77     13813352.78
      2484447.50     13813292.28      2484480.63     13813185.67
      2484437.41     13813113.63      2484099.83     13812650.25
#Sta/Elev= 30
  4250.5  411.14  4293.2  410.00  4452.7  405.29  4619.0  403.64  4851.7  402.25
  4897.6  407.03  4943.8  406.41  4949.6  404.61  4965.3  406.41  4986.8  406.52
  5062.4  404.63  5080.4  404.11  5085.6  405.92  5096.0  406.38  5188.3  406.10
  5189.9  405.72  5208.8  404.39  5215.0  405.44  5229.7  402.87  5256.6  401.70
  5256.9  401.20  5261.5  401.70  5404.7  405.67  5422.1  407.63  5566.5  413.26
  5602.1  416.97  5631.4  416.12  5673.3  420.60  5686.8  421.02  5773.6  424.71
#Mann=12,-1,0
  4250.5    0.07       0  4293.2    0.05       0  4452.7    0.07       0
  4619.0     0.1       0  5062.4    0.07       0  5188.3     0.1       0
  5189.9    0.07       0  5256.6    0.05       0  5261.5    0.07       0
  5404.7    0.12       0  5673.3    0.07       0  5686.8    0.12       0
Bank Sta=5256.6,5261.5
Exp/Cntr=0.3,0.1

Type RM Length L Ch R = 1,11635,447,447,447
BEGIN DESCRIPTION:
Stream0444 23.0
END DESCRIPTION:
XS GIS Cut Line= 3
      2485124.99     13813774.98      2484675.00     13813175.00
      2483925.03     13812425.03
#Sta/Elev= 30
  4250.0  416.49  4292.7  416.08  4357.3  411.57  4378.1  410.50  4392.7  410.93
  4407.3  409.17  4450.0  407.36  4457.3  407.88  4536.4  404.78  4681.8  401.33
  4842.7  400.84  5039.7  398.70  5040.1  398.20  5045.2  398.70  5185.2  401.34
  5212.1  402.24  5240.4  401.48  5320.7  403.53  5347.8  404.13  5410.1  407.13
  5495.0  409.24  5544.6  412.32  5565.7  414.42  5593.9  414.46  5636.4  418.41
  5727.0  422.11  5783.2  424.83  5891.1  428.51  5932.7  430.42  6060.6  435.00
#Mann=12,-1,0
  4250.0    0.12       0  4681.8     0.1       0  5039.7    0.05       0
  5045.2     0.1       0  5185.2    0.12       0  5320.7    0.07       0
  5347.8    0.12       0  5544.6    0.07       0  5727.0    0.12       0
  5783.2    0.07       0  5891.1    0.12       0  5932.7    0.07       0
Bank Sta=5039.7,5045.2
Exp/Cntr=0.3,0.1

Type RM Length L Ch R = 1,11188,443,443,443
BEGIN DESCRIPTION:
Stream0444 22.0
END DESCRIPTION:
XS GIS Cut Line= 3
      2485175.01     13813825.04      2485075.00     13813025.00
      2484324.97     13812224.96
#Sta/Elev= 30
  4188.8  417.78  4259.4  416.50  4440.8  410.10  4571.8  407.55  4629.7  407.94
  4692.7  404.44  4710.4  405.93  4715.4  404.60  4763.3  403.81  4843.9  399.37
  4903.8  399.04  4957.3  398.49  4972.1  397.22  4972.6  396.72  4977.8  397.22
  5073.0  398.32  5101.3  399.83  5248.5  400.51  5355.8  401.73  5440.8  404.98
  5546.8  406.22  5582.4  408.15  5589.3  409.56  5602.5  409.51  5610.8  408.99
  5624.9  411.53  5631.8  410.81  5747.8  416.85  5887.6  421.88  6091.7  429.86
#Mann=8,-1,0
  4188.8    0.12       0  4903.8     0.1       0  4972.1    0.05       0
  4977.8     0.1       0  5248.5    0.12       0  5602.5    0.07       0
  5747.8    0.12       0  5887.6    0.07       0
Bank Sta=4972.1,4977.8
Exp/Cntr=0.3,0.1

Type RM Length L Ch R = 1,10745,447,447,447
BEGIN DESCRIPTION:
Stream0444 21.0
END DESCRIPTION:
XS GIS Cut Line= 3
      2486025.02     13813525.02      2485375.00     13812725.00
      2484674.97     13812024.97
#Sta/Elev= 30
  3974.3  419.34  4109.4  412.45  4133.5  412.30  4280.3  406.10  4373.0  404.57
  4386.6  405.21  4429.0  402.64  4536.1  401.71  4635.2  404.42  4707.0  403.62
  4721.4  402.09  4765.8  400.72  4834.9  397.89  4855.7  397.92  4906.2  395.05
  4954.8  395.76  4988.6  394.17  4989.1  393.67  4994.4  394.17  4997.9  395.13
  5019.2  395.83  5118.2  395.74  5302.1  399.34  5348.4  401.30  5358.7  400.79
  5485.9  405.15  5534.2  408.26  5584.9  412.03  5669.8  415.96  5995.1  429.11
#Mann=8,-1,0
  3974.3    0.07       0  4133.5    0.12       0  4765.8    0.07       0
  4906.2     0.1       0  4988.6    0.05       0  4994.4     0.1       0
  5348.4    0.12       0  5534.2    0.07       0
Bank Sta=4988.6,4994.4
Exp/Cntr=0.3,0.1

Type RM Length L Ch R = 1,10298,468,468,468
BEGIN DESCRIPTION:
Stream0444 20.0
END DESCRIPTION:
XS GIS Cut Line= 3
      2485625.00     13812974.99      2485725.00     13812475.00
      2485625.00     13812124.99
#Sta/Elev= 30
  4495.3  403.31  4514.1  403.13  4546.3  402.31  4607.5  399.42  4617.7  399.61
  4668.7  397.56  4689.0  397.82  4699.2  397.03  4711.1  396.91  4903.2  394.97
  4954.2  393.64  4964.4  393.23  4999.7  388.27  5000.2  387.77  5005.1  387.77
  5005.5  388.27  5007.8  388.27  5022.1  392.32  5036.4  392.90  5046.8  393.98
  5055.9  394.39  5088.4  393.15  5128.7  394.93  5149.5  394.81  5206.7  396.11
  5269.1  398.64  5286.0  399.26  5296.4  400.25  5313.3  400.27  5369.2  402.15
#Mann=7,-1,0
  4495.3    0.12       0  4514.1    0.07       0  4711.1     0.1       0
  4999.7    0.05       0  5005.5     0.1       0  5149.5    0.07       0
  5269.1    0.12       0
Bank Sta=4999.7,5005.5
Exp/Cntr=0.3,0.1

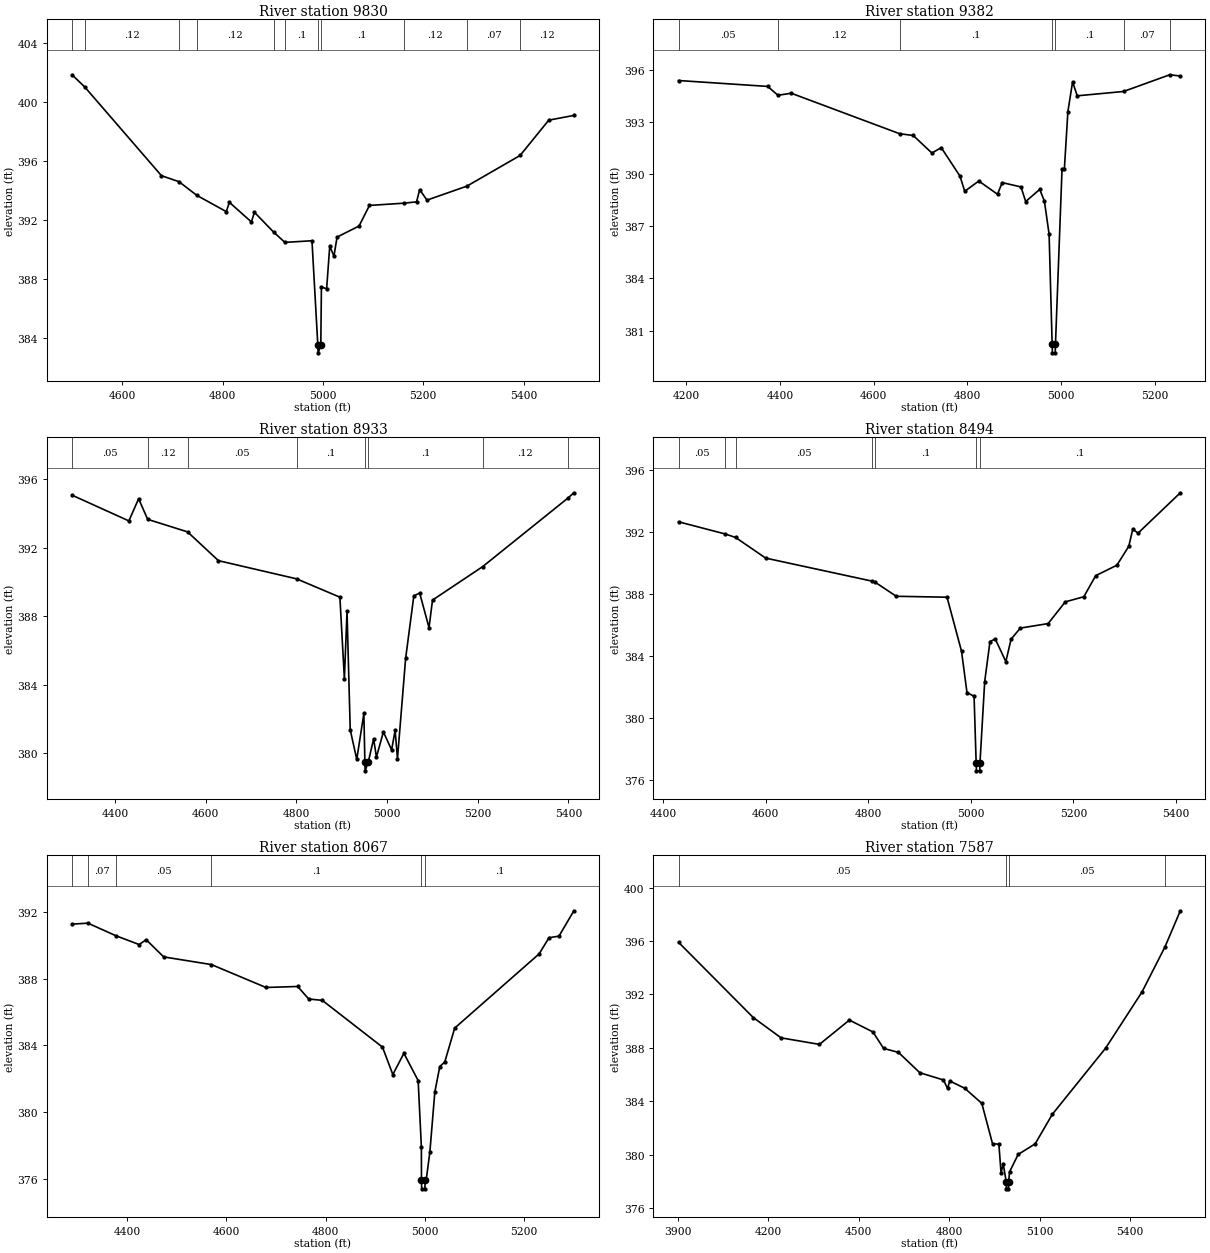
Type RM Length L Ch R = 1,9830,448,448,448
BEGIN DESCRIPTION:
Stream0444 19.0
END DESCRIPTION:
XS GIS Cut Line= 3
      2486475.00     13812825.00      2486175.00     13812425.00
      2485775.00     13812125.00
#Sta/Elev= 30
  4500.1  401.86  4525.4  401.03  4678.2  395.01  4713.2  394.60  4748.8  393.67
  4807.4  392.57  4813.6  393.20  4857.4  391.87  4863.6  392.52  4902.0  391.17
  4924.3  390.48  4978.2  390.59  4989.9  383.48  4990.4  382.98  4995.8  383.48
  4997.0  387.45  5007.4  387.33  5013.6  390.22  5022.0  389.55  5028.2  390.84
  5072.0  391.59  5092.8  392.99  5161.0  393.14  5186.6  393.23  5192.8  394.06
  5207.4  393.35  5287.0  394.30  5392.9  396.38  5450.1  398.78  5500.1  399.10
#Mann=11,-1,0
  4500.1    0.07       0  4525.4    0.12       0  4713.2    0.07       0
  4748.8    0.12       0  4902.0    0.07       0  4924.3     0.1       0
  4989.9    0.05       0  4995.8     0.1       0  5161.0    0.12       0
  5287.0    0.07       0  5392.9    0.12       0
Bank Sta=4989.9,4995.8
Exp/Cntr=0.3,0.1

Type RM Length L Ch R = 1,9382,449,449,449
BEGIN DESCRIPTION:
Stream0444 18.0
END DESCRIPTION:
XS GIS Cut Line= 3
      2486995.20     13812212.90      2486175.00     13812175.00
      2485924.98     13812175.00
#Sta/Elev= 30
  4183.5  395.38  4373.9  395.04  4395.7  394.53  4424.0  394.65  4655.5  392.32
  4684.4  392.22  4724.3  391.21  4744.3  391.52  4784.3  389.88  4794.4  389.01
  4824.4  389.60  4864.4  388.84  4874.4  389.51  4914.5  389.26  4924.5  388.42
  4954.5  389.12  4964.5  388.44  4974.5  386.54  4981.0  380.22  4981.5  379.72
  4987.6  379.72  4988.1  380.22  5002.1  390.29  5007.1  390.29  5014.6  393.59
  5024.6  395.30  5034.6  394.50  5133.4  394.75  5231.9  395.71  5254.6  395.64
#Mann=7,-1,0
  4183.5    0.05       0  4395.7    0.12       0  4655.5     0.1       0
  4981.0    0.05       0  4988.1     0.1       0  5133.4    0.07       0
  5231.9    0.12       0
Bank Sta=4981,4988.1
Exp/Cntr=0.3,0.1

Type RM Length L Ch R = 1,8933,439,439,439
BEGIN DESCRIPTION:
Stream0444 17.0
END DESCRIPTION:
XS GIS Cut Line= 3
      2486874.98     13812174.99      2486275.00     13811825.00
      2485875.01     13811725.00
#Sta/Elev= 30
  4305.2  395.06  4430.5  393.56  4452.0  394.85  4472.0  393.65  4559.9  392.92
  4628.1  391.24  4800.4  390.18  4896.0  389.11  4905.9  384.35  4911.7  388.28
  4918.8  381.37  4933.2  379.65  4948.9  382.33  4951.1  379.48  4951.6  378.98
  4958.4  379.48  4970.4  380.84  4976.6  379.78  4991.9  381.25  5010.1  380.20
  5017.8  381.34  5023.0  379.69  5041.0  385.54  5059.1  389.19  5072.0  389.35
  5092.6  387.33  5100.3  388.94  5210.8  390.89  5398.5  394.88  5412.1  395.20
#Mann=8,-1,0
  4305.2    0.05       0  4472.0    0.12       0  4559.9    0.05       0
  4800.4     0.1       0  4951.1    0.05       0  4958.4     0.1       0
  5210.8    0.12       0  5398.5     0.1       0
Bank Sta=4951.1,4958.4
Exp/Cntr=0.3,0.1

Type RM Length L Ch R = 1,8494,427,427,427
BEGIN DESCRIPTION:
Stream0444 16.0
END DESCRIPTION:
XS GIS Cut Line= 3
      2486825.03     13811875.03      2486425.00     13811475.00
      2486025.04     13811375.01
#Sta/Elev= 30
  4430.4  392.65  4521.9  391.86  4541.6  391.64  4600.2  390.31  4808.4  388.82
  4812.5  388.78  4854.7  387.85  4953.7  387.79  4982.0  384.30  4992.6  381.64
  5006.4  381.41  5010.5  377.10  5011.0  376.60  5017.4  376.60  5017.9  377.10
  5027.1  382.35  5037.4  384.93  5047.7  385.10  5068.3  383.64  5078.6  385.09
  5096.6  385.80  5150.7  386.09  5184.2  387.49  5220.3  387.82  5243.5  389.18
  5284.7  389.85  5307.9  391.07  5315.7  392.17  5326.0  391.92  5408.4  394.52
#Mann=7,-1,0
  4430.4    0.05       0  4521.9    0.07       0  4541.6    0.05       0
  4808.4    0.07       0  4812.5     0.1       0  5010.5    0.05       0
  5017.9     0.1       0
Bank Sta=5010.5,5017.9
Exp/Cntr=0.3,0.1

Type RM Length L Ch R = 1,8067,480,480,480
BEGIN DESCRIPTION:
Stream0444 15.0
END DESCRIPTION:
XS GIS Cut Line= 3
      2486975.01     13811575.01      2486425.00     13811125.00
      2486125.04     13811125.00
#Sta/Elev= 30
  4289.3  391.26  4321.2  391.32  4377.3  390.57  4424.3  390.04  4438.6  390.33
  4473.8  389.30  4570.0  388.84  4679.8  387.47  4743.7  387.53  4765.9  386.78
  4793.2  386.70  4914.5  383.90  4935.3  382.26  4957.6  383.53  4986.3  381.90
  4992.8  377.93  4993.0  375.92  4993.5  375.42  4999.9  375.42  5000.4  375.92
  5002.4  375.92  5009.9  377.62  5019.9  381.22  5029.9  382.74  5039.9  383.01
  5059.9  385.04  5229.9  389.48  5249.9  390.45  5269.9  390.54  5299.9  392.06
#Mann=6,-1,0
  4289.3    0.05       0  4321.2    0.07       0  4377.3    0.05       0
  4570.0     0.1       0  4993.0    0.05       0  5000.4     0.1       0
Bank Sta=4993,5000.4
Exp/Cntr=0.3,0.1

Type RM Length L Ch R = 1,7587,467,467,467
BEGIN DESCRIPTION:
Stream0444 14.0
END DESCRIPTION:
XS GIS Cut Line= 3
      2487425.03     13811475.02      2486625.00     13810725.00
      2486225.00     13810325.00
#Sta/Elev= 30
  3903.4  395.90  4150.9  390.27  4243.1  388.75  4370.2  388.26  4469.3  390.08
  4547.5  389.19  4582.6  387.96  4632.0  387.66  4702.8  386.14  4780.7  385.60
  4794.6  384.97  4801.9  385.52  4851.3  384.98  4908.0  383.85  4943.6  380.83
  4964.6  380.79  4971.9  378.62  4978.8  379.34  4989.1  377.95  4989.6  377.45
  4996.3  377.45  4996.8  377.95  5000.0  378.72  5028.3  380.02  5084.9  380.82
  5141.4  383.02  5318.2  387.98  5438.4  392.17  5514.5  395.54  5565.7  398.26
#Mann=4,-1,0
  3903.4    0.05       0  4989.1    0.05       0  4996.8    0.05       0
  5514.5    0.07       0
Bank Sta=4989.1,4996.8
Exp/Cntr=0.3,0.1

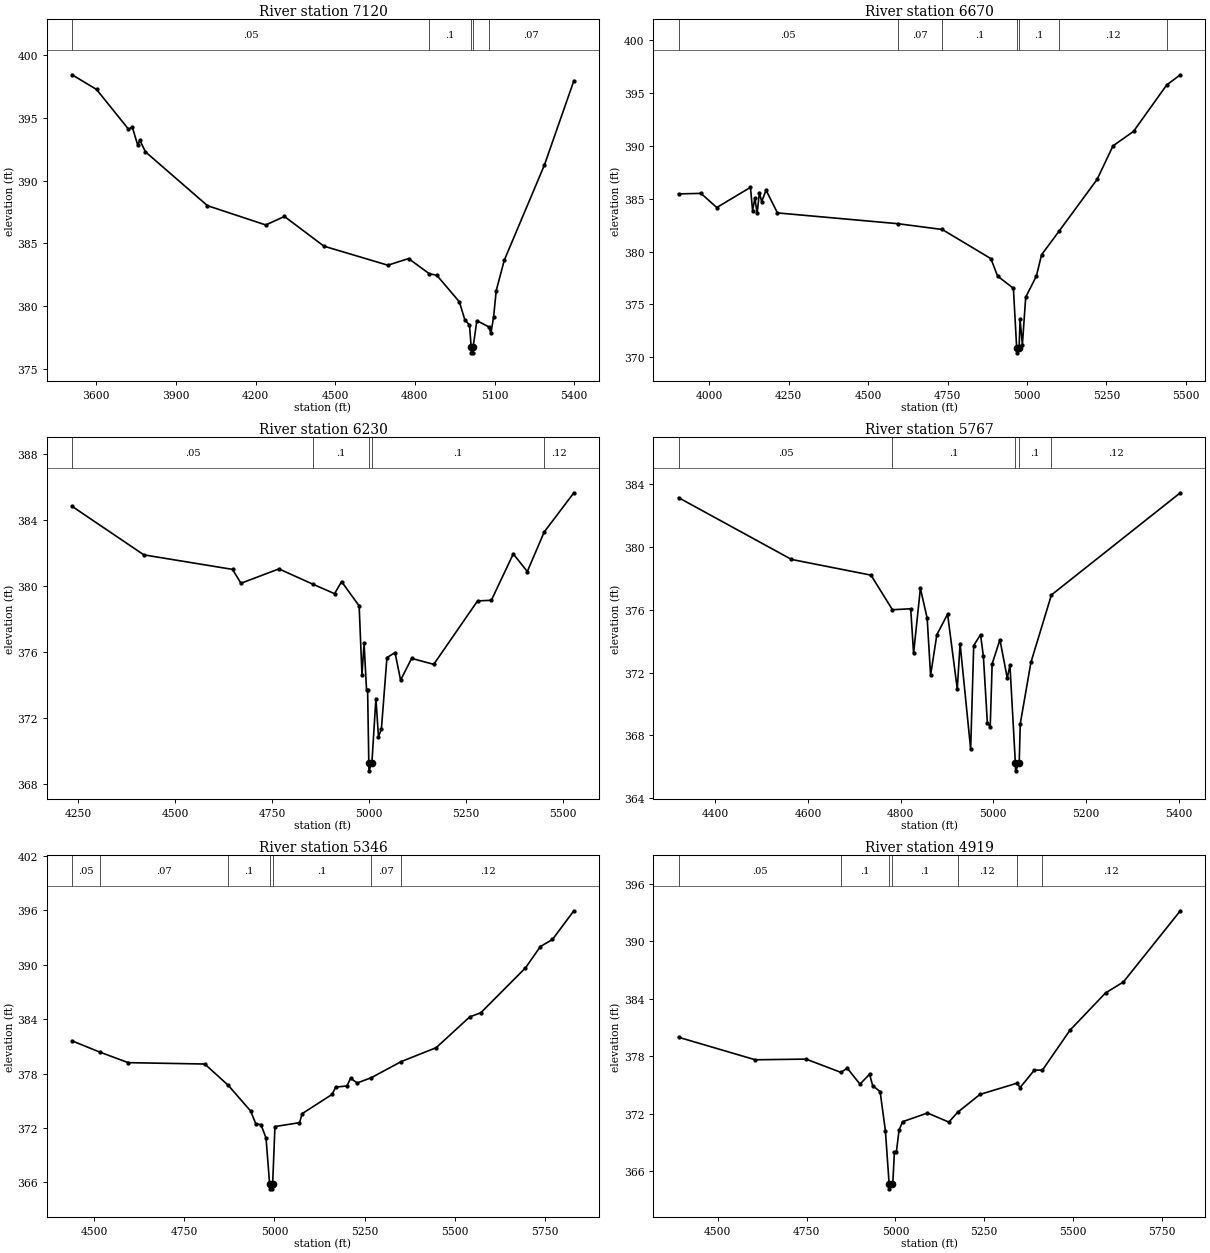
Type RM Length L Ch R = 1,7120,450,450,450
BEGIN DESCRIPTION:
Stream0444 13.0
END DESCRIPTION:
XS GIS Cut Line= 3
      2487674.97     13811374.97      2486675.00     13810275.00
      2486274.98     13810225.00
#Sta/Elev= 30
  3509.1  398.45  3601.3  397.28  3721.6  394.11  3735.8  394.28  3756.7  392.82
  3764.1  393.25  3785.1  392.31  4018.9  388.01  4238.5  386.47  4308.8  387.15
  4457.4  384.78  4698.3  383.26  4776.4  383.79  4854.3  382.58  4882.5  382.46
  4967.6  380.34  4988.6  378.88  5005.7  378.50  5012.0  376.77  5012.5  376.27
  5019.2  376.27  5019.7  376.77  5033.5  378.84  5078.4  378.34  5086.4  377.83
  5096.4  379.11  5106.5  381.24  5136.8  383.66  5287.9  391.25  5398.8  397.97
#Mann=5,-1,0
  3509.1    0.05       0  4854.3     0.1       0  5012.0    0.05       0
  5019.7     0.1       0  5078.4    0.07       0
Bank Sta=5012,5019.7
Exp/Cntr=0.3,0.1

Type RM Length L Ch R = 1,6670,440,440,440
BEGIN DESCRIPTION:
Stream0444 12.0
END DESCRIPTION:
XS GIS Cut Line= 3
      2487424.98     13810624.98      2486675.00     13809825.00
      2486194.30     13809774.54
#Sta/Elev= 30
  3903.0  385.47  3973.6  385.52  4023.4  384.18  4129.4  386.09  4136.2  383.89
  4143.5  385.07  4150.4  383.63  4157.7  385.59  4164.6  384.74  4178.7  385.82
  4214.4  383.67  4593.0  382.65  4733.3  382.10  4886.5  379.34  4907.5  377.69
  4957.3  376.53  4967.6  370.92  4968.1  370.42  4975.4  370.92  4978.3  373.58
  4985.6  371.20  4996.1  375.69  5029.7  377.69  5046.1  379.71  5100.8  381.93
  5220.8  386.84  5271.0  390.02  5335.6  391.39  5440.1  395.79  5482.9  396.75
#Mann=7,-1,0
  3903.0    0.05       0  4593.0    0.07       0  4733.3     0.1       0
  4967.6    0.05       0  4975.4     0.1       0  5100.8    0.12       0
  5440.1    0.07       0
Bank Sta=4967.6,4975.4
Exp/Cntr=0.3,0.1

Type RM Length L Ch R = 1,6230,463,463,463
BEGIN DESCRIPTION:
Stream0444 11.0
END DESCRIPTION:
XS GIS Cut Line= 3
      2487675.03     13810025.01      2486975.00     13809725.00
      2486575.01     13809375.01
#Sta/Elev= 30
  4234.8  384.82  4419.8  381.88  4648.3  381.00  4670.0  380.16  4767.9  381.03
  4855.7  380.10  4911.2  379.53  4929.3  380.26  4974.6  378.79  4981.9  374.62
  4987.3  376.52  4993.7  373.68  4996.4  373.68  4999.5  369.30  5000.0  368.80
  5007.5  369.30  5017.8  373.18  5024.4  370.86  5032.0  371.34  5046.2  375.66
  5067.1  375.96  5081.4  374.29  5109.8  375.61  5166.8  375.25  5279.7  379.09
  5315.3  379.13  5371.8  381.94  5407.9  380.87  5451.6  383.27  5527.9  385.64
#Mann=5,-1,0
  4234.8    0.05       0  4855.7     0.1       0  4999.5    0.05       0
  5007.5     0.1       0  5451.6    0.12       0
Bank Sta=4999.5,5007.5
Exp/Cntr=0.3,0.1

Type RM Length L Ch R = 1,5767,421,421,421
BEGIN DESCRIPTION:
Stream0444 10.0
END DESCRIPTION:
XS GIS Cut Line= 3
      2487625.02     13809825.02      2487075.00     13809425.00
      2486725.01     13809225.01
#Sta/Elev= 30
  4320.4  383.13  4564.2  379.20  4735.8  378.20  4782.1  376.00  4821.6  376.06
  4827.8  373.23  4842.5  377.36  4857.1  375.46  4864.5  371.83  4878.0  374.41
  4901.2  375.72  4922.1  370.95  4928.2  373.84  4951.0  367.13  4957.6  373.72
  4972.3  374.42  4978.5  373.03  4987.0  368.82  4993.2  368.54  4997.4  372.56
  5014.2  374.09  5030.0  371.65  5035.8  372.47  5047.5  366.25  5048.0  365.75
  5055.8  366.25  5058.1  368.75  5081.1  372.65  5125.3  376.94  5403.6  383.44
#Mann=5,-1,0
  4320.4    0.05       0  4782.1     0.1       0  5047.5    0.05       0
  5055.8     0.1       0  5125.3    0.12       0
Bank Sta=5047.5,5055.8
Exp/Cntr=0.3,0.1

Type RM Length L Ch R = 1,5346,427,427,427
BEGIN DESCRIPTION:
Stream0444 9.0
END DESCRIPTION:
XS GIS Cut Line= 3
      2487674.99     13809574.99      2487275.00     13809175.00
      2486475.00     13808975.00
#Sta/Elev= 30
  4439.4  381.60  4516.4  380.36  4595.0  379.20  4807.1  379.05  4872.2  376.70
  4934.4  373.86  4948.5  372.45  4962.7  372.38  4976.8  370.90  4986.8  365.80
  4987.3  365.30  4994.6  365.30  4995.1  365.80  5001.5  372.16  5069.5  372.59
  5077.2  373.59  5159.7  375.70  5170.0  376.51  5200.9  376.63  5211.2  377.49
  5229.3  376.96  5268.3  377.54  5351.5  379.32  5448.3  380.85  5541.1  384.24
  5572.0  384.70  5695.7  389.64  5736.9  391.99  5770.4  392.77  5829.7  395.93
#Mann=7,-1,0
  4439.4    0.05       0  4516.4    0.07       0  4872.2     0.1       0
  4986.8    0.05       0  4995.1     0.1       0  5268.3    0.07       0
  5351.5    0.12       0
Bank Sta=4986.8,4995.1
Exp/Cntr=0.3,0.1

Type RM Length L Ch R = 1,4919,643,643,643
BEGIN DESCRIPTION:
Stream0444 8.0
END DESCRIPTION:
XS GIS Cut Line= 3
      2487875.01     13809225.01      2487375.00     13808875.00
      2486575.00     13808825.00
#Sta/Elev= 30
  4389.7  379.99  4605.5  377.64  4748.5  377.71  4846.4  376.33  4864.5  376.76
  4900.2  375.10  4927.2  376.13  4936.0  374.94  4956.9  374.32  4971.7  370.26
  4982.3  364.68  4982.8  364.18  4990.7  364.68  4992.6  364.76  4997.0  367.97
  5002.5  367.97  5010.1  370.29  5020.1  371.18  5090.2  372.09  5150.3  371.14
  5175.2  372.17  5238.0  374.03  5342.3  375.20  5350.7  374.74  5390.8  376.56
  5413.6  376.56  5491.0  380.72  5591.2  384.61  5641.3  385.75  5801.6  393.18
#Mann=7,-1,0
  4389.7    0.05       0  4846.4     0.1       0  4982.3    0.05       0
  4990.7     0.1       0  5175.2    0.12       0  5342.3    0.07       0
  5413.6    0.12       0
Bank Sta=4982.3,4990.7
Exp/Cntr=0.3,0.1