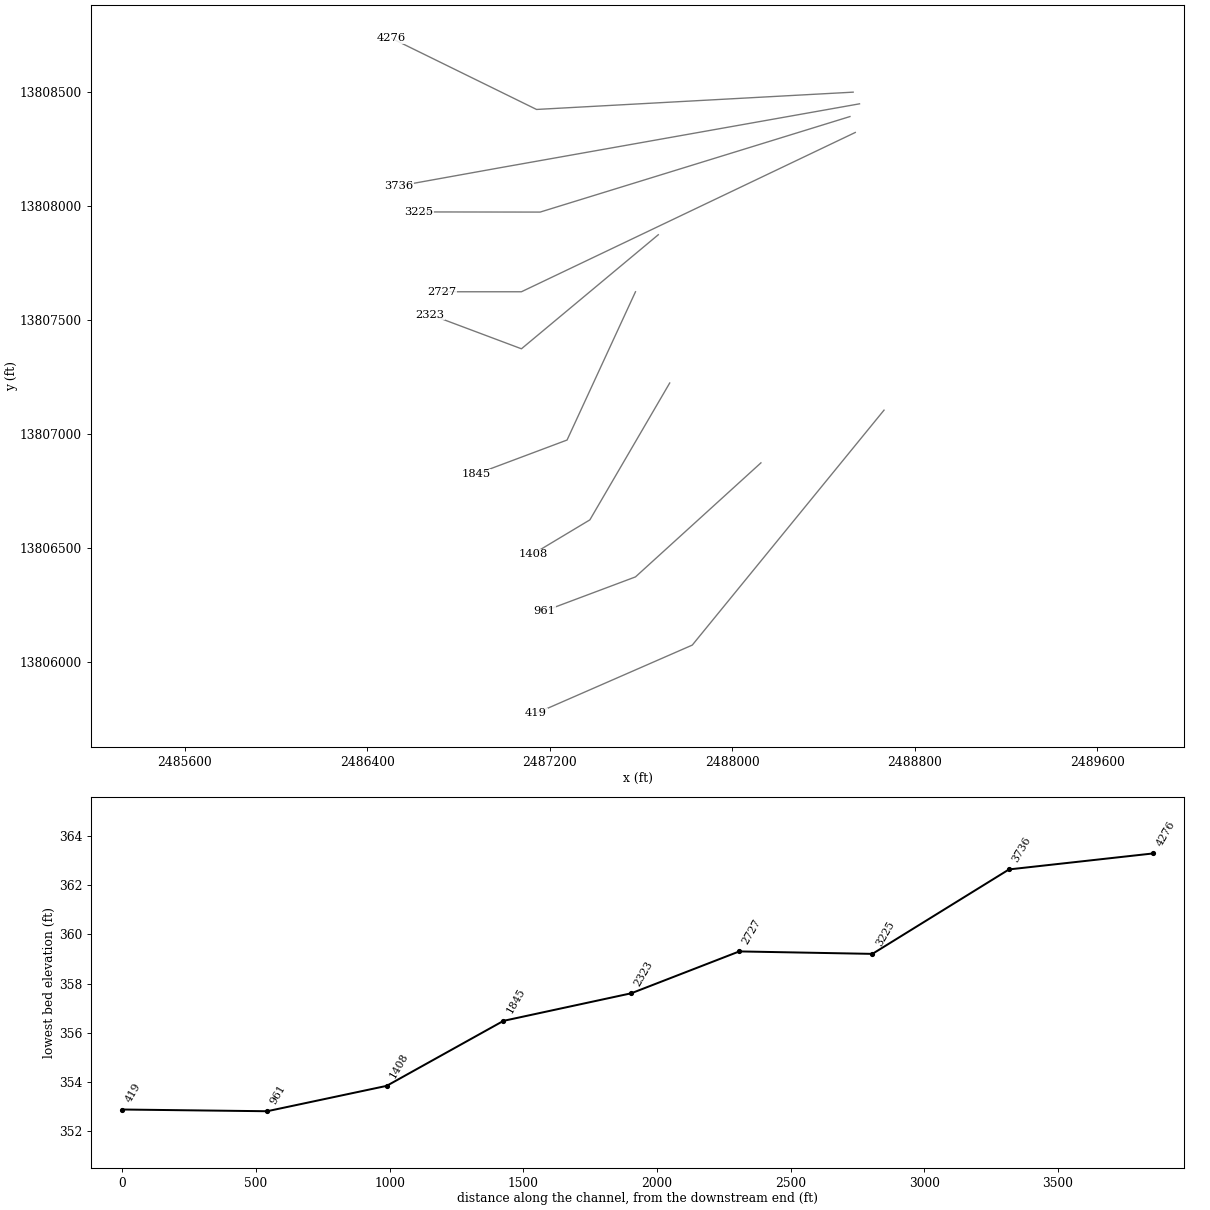
HEC-RAS study Stream0444.prj: Stream0444 Base Level Engineering

--- Stream0444.g01 (geometry) --- (continued)

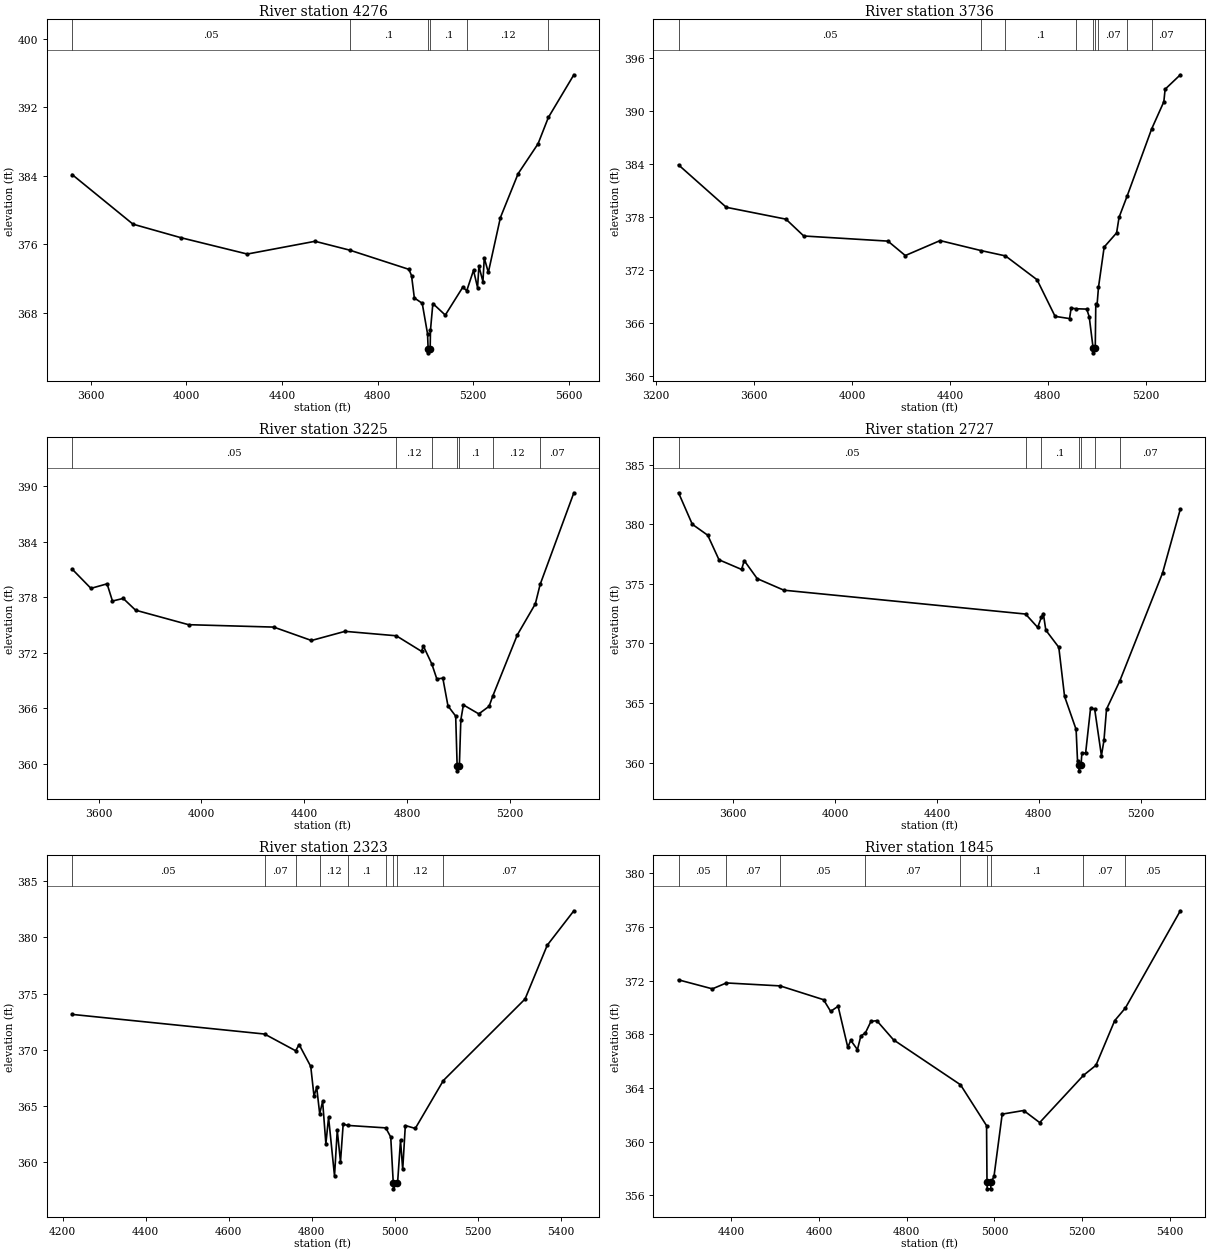
Type RM Length L Ch R = 1,4276,540,540,540
BEGIN DESCRIPTION:
XS6816
END DESCRIPTION:
XS GIS Cut Line= 3
      2488529.27     13808500.09      2487141.21     13808424.23
      2486505.81     13808736.01
#Sta/Elev= 30
  3522.8  384.12  3777.5  378.32  3977.8  376.74  4255.3  374.83  4538.6  376.32
  4684.3  375.28  4931.3  373.04  4942.1  372.30  4953.8  369.70  4986.7  369.08
  5009.0  365.51  5011.4  363.79  5011.9  363.29  5019.9  363.79  5021.3  365.96
  5031.2  369.05  5083.2  367.70  5156.2  370.95  5172.9  370.55  5201.2  372.93
  5218.1  370.91  5223.7  373.40  5240.6  371.61  5246.1  374.38  5263.1  372.68
  5313.6  379.09  5387.7  384.22  5471.0  387.71  5514.0  390.78  5620.7  395.77
#Mann=6,-1,0
  3522.8    0.05       0  4684.3     0.1       0  5011.4    0.05       0
  5019.9     0.1       0  5172.9    0.12       0  5514.0    0.07       0
Bank Sta=5011.4,5019.9
Exp/Cntr=0.3,0.1

Type RM Length L Ch R = 1,3736,511,511,511
BEGIN DESCRIPTION:
Stream0444 7.0
END DESCRIPTION:
XS GIS Cut Line= 3
      2488557.15     13808448.93      2486975.46     13808167.70
      2486538.69     13808089.01
#Sta/Elev= 30
  3290.9  383.87  3486.1  379.08  3729.8  377.74  3802.5  375.84  4146.5  375.26
  4217.4  373.63  4359.6  375.32  4527.1  374.19  4626.7  373.59  4755.7  370.90
  4829.5  366.76  4888.5  366.51  4895.1  367.69  4916.2  367.62  4958.8  367.58
  4969.0  366.71  4985.0  363.14  4985.5  362.64  4993.6  363.14  4995.8  368.18
  5000.9  368.02  5006.8  370.05  5030.0  374.59  5080.8  376.19  5090.9  377.95
  5124.4  380.39  5224.0  387.93  5273.8  391.00  5279.1  392.42  5341.2  394.05
#Mann=9,-1,0
  3290.9    0.05       0  4527.1    0.12       0  4626.7     0.1       0
  4916.2    0.12       0  4985.0    0.05       0  4993.6    0.12       0
  5006.8    0.07       0  5124.4    0.12       0  5224.0    0.07       0
Bank Sta=4985,4993.6
Exp/Cntr=0.3,0.1

Type RM Length L Ch R = 1,3225,498,498,498
BEGIN DESCRIPTION:
Stream0444 6.0
END DESCRIPTION:
XS GIS Cut Line= 3
      2488515.25     13808393.11      2487157.00     13807974.32
      2486625.05     13807975.00
#Sta/Elev= 30
  3496.4  381.04  3569.8  378.95  3632.7  379.44  3653.6  377.58  3695.5  377.86
  3743.6  376.59  3950.0  375.02  4281.5  374.76  4428.3  373.31  4559.0  374.30
  4758.6  373.82  4857.1  372.13  4863.4  372.74  4896.8  370.77  4916.2  369.16
  4939.7  369.23  4959.7  366.23  4989.7  365.13  4995.4  359.71  4995.9  359.21
  5004.0  359.71  5009.7  364.72  5019.7  366.34  5079.7  365.37  5119.7  366.19
  5134.8  367.35  5229.7  373.92  5299.7  377.27  5318.4  379.37  5449.7  389.29
#Mann=7,-1,0
  3496.4    0.05       0  4758.6    0.12       0  4896.8     0.1       0
  4995.4    0.05       0  5004.0     0.1       0  5134.8    0.12       0
  5318.4    0.07       0
Bank Sta=4995.4,5004
Exp/Cntr=0.3,0.1

Type RM Length L Ch R = 1,2727,404,404,404
BEGIN DESCRIPTION:
Stream0444 5.0
END DESCRIPTION:
XS GIS Cut Line= 3
      2488538.54     13808323.35      2487075.00     13807625.00
      2486725.02     13807625.00
#Sta/Elev= 30
  3384.6  382.63  3438.6  379.99  3499.3  379.07  3543.6  377.01  3632.3  376.20
  3642.8  376.94  3693.7  375.43  3798.5  374.46  4748.1  372.46  4795.7  371.34
  4810.3  372.19  4817.9  372.50  4827.7  371.11  4878.7  369.67  4901.3  365.56
  4946.7  362.78  4952.3  360.12  4957.6  359.81  4958.1  359.31  4966.2  359.81
  4969.4  360.82  4984.1  360.80  5003.4  364.54  5019.5  364.51  5046.2  360.58
  5056.2  361.87  5066.2  364.48  5118.0  366.83  5286.2  375.89  5356.2  381.26
#Mann=7,-1,0
  3384.6    0.05       0  4748.1    0.12       0  4810.3     0.1       0
  4957.6    0.05       0  4966.2     0.1       0  5019.5    0.12       0
  5118.0    0.07       0
Bank Sta=4957.6,4966.2
Exp/Cntr=0.3,0.1

Type RM Length L Ch R = 1,2323,478,478,478
BEGIN DESCRIPTION:
Stream0444 4.0
END DESCRIPTION:
XS GIS Cut Line= 3
      2487674.98     13807874.98      2487075.00     13807375.00
      2486674.99     13807525.00
#Sta/Elev= 30
  4222.7  373.15  4686.2  371.40  4761.0  369.91  4769.4  370.46  4797.4  368.51
  4805.2  365.88  4811.7  366.64  4818.9  364.31  4826.0  365.40  4833.8  361.62
  4840.3  363.98  4854.6  358.76  4861.2  362.82  4869.0  360.02  4875.5  363.38
  4886.3  363.26  4978.0  363.04  4990.0  362.22  4996.1  358.11  4996.6  357.61
  5004.7  358.11  5006.4  358.11  5013.5  361.93  5018.8  359.34  5025.1  363.25
  5049.1  362.99  5116.7  367.26  5313.4  374.52  5366.8  379.31  5430.9  382.38
#Mann=9,-1,0
  4222.7    0.05       0  4686.2    0.07       0  4761.0     0.1       0
  4818.9    0.12       0  4886.3     0.1       0  4978.0    0.12       0
  4996.1    0.05       0  5004.7    0.12       0  5116.7    0.07       0
Bank Sta=4996.1,5004.7
Exp/Cntr=0.3,0.1

Type RM Length L Ch R = 1,1845,437,437,437
BEGIN DESCRIPTION:
Stream0444 3.0
END DESCRIPTION:
XS GIS Cut Line= 3
      2487575.00     13807625.01      2487275.00     13806975.00
      2486875.00     13806825.00
#Sta/Elev= 30
  4280.3  372.07  4357.4  371.40  4389.3  371.84  4511.7  371.62  4610.7  370.59
  4626.8  369.72  4643.8  370.10  4665.8  367.05  4672.7  367.56  4687.8  366.87
  4695.6  367.88  4706.0  368.12  4718.6  368.97  4731.9  369.03  4770.0  367.60
  4922.6  364.25  4982.0  361.20  4983.0  356.99  4983.5  356.49  4991.5  356.49
  4992.0  356.99  4998.9  357.41  5017.6  362.06  5066.5  362.33  5103.0  361.43
  5202.7  364.95  5231.2  365.70  5273.9  369.03  5298.4  369.98  5423.4  377.22
#Mann=9,-1,0
  4280.3    0.05       0  4389.3    0.07       0  4511.7    0.05       0
  4706.0    0.07       0  4922.6     0.1       0  4983.0    0.05       0
  4992.0     0.1       0  5202.7    0.07       0  5298.4    0.05       0
Bank Sta=4983,4992
Exp/Cntr=0.3,0.1

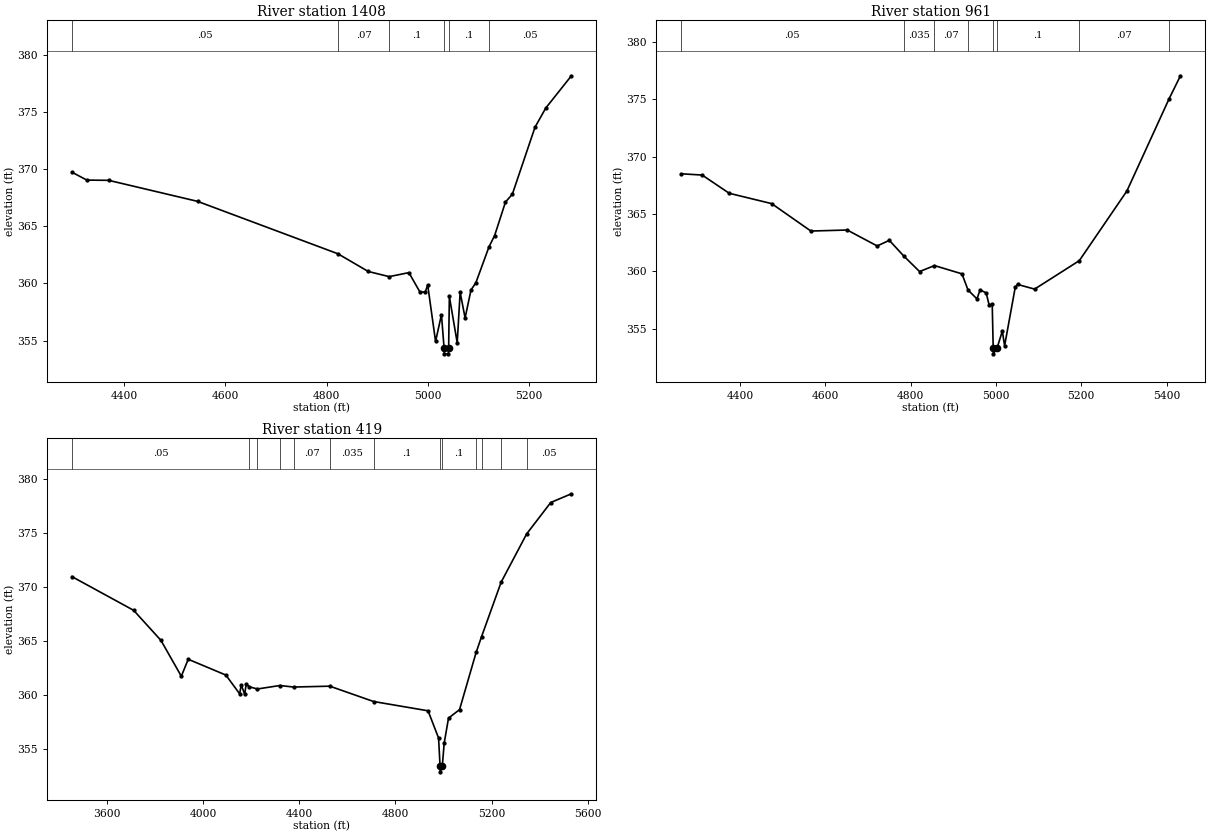
Type RM Length L Ch R = 1,1408,447,447,447
BEGIN DESCRIPTION:
Stream0444 2.0
END DESCRIPTION:
XS GIS Cut Line= 3
      2487725.01     13807225.01      2487375.00     13806625.00
      2487124.98     13806474.99
#Sta/Elev= 30
  4297.2  369.73  4326.6  369.04  4369.6  369.02  4545.3  367.18  4822.3  362.60
  4882.3  361.05  4923.6  360.60  4962.5  360.95  4984.0  359.28  4994.7  359.24
  4999.6  359.88  5015.2  354.93  5026.8  357.28  5032.0  354.35  5032.5  353.85
  5040.5  353.85  5041.0  354.35  5042.4  358.87  5057.9  354.82  5063.7  359.23
  5073.5  356.99  5085.1  359.43  5094.8  360.07  5120.7  363.21  5131.8  364.19
  5153.2  367.12  5166.8  367.81  5211.5  373.66  5232.8  375.34  5283.4  378.16
#Mann=6,-1,0
  4297.2    0.05       0  4822.3    0.07       0  4923.6     0.1       0
  5032.0    0.05       0  5041.0     0.1       0  5120.7    0.05       0
Bank Sta=5032,5041
Exp/Cntr=0.3,0.1

Type RM Length L Ch R = 1,961,542,542,542
BEGIN DESCRIPTION:
Stream0444 1.0
END DESCRIPTION:
XS GIS Cut Line= 3
      2488124.97     13806874.97      2487575.00     13806375.00
      2487174.97     13806224.99
#Sta/Elev= 30
  4262.0  368.51  4311.6  368.40  4375.1  366.81  4474.5  365.91  4566.4  363.52
  4651.5  363.61  4721.8  362.22  4750.2  362.71  4783.7  361.36  4821.1  359.99
  4856.1  360.51  4920.5  359.79  4934.7  358.38  4955.6  357.61  4963.0  358.39
  4977.2  358.13  4984.0  357.10  4991.4  357.12  4993.7  353.32  4994.2  352.82
  5002.7  353.32  5015.1  354.80  5020.4  353.52  5045.3  358.61  5050.7  358.87
  5090.7  358.46  5195.5  360.94  5307.0  367.01  5406.1  375.06  5432.5  377.05
#Mann=8,-1,0
  4262.0    0.05       0  4783.7   0.035       0  4856.1    0.07       0
  4934.7     0.1       0  4993.7    0.05       0  5002.7     0.1       0
  5195.5    0.07       0  5406.1    0.05       0
Bank Sta=4993.7,5002.7
Exp/Cntr=0.3,0.1

Type RM Length L Ch R = 1,419,0,0,0
BEGIN DESCRIPTION:
XS6815
END DESCRIPTION:
XS GIS Cut Line= 3
      2488664.58     13807106.09      2487823.96     13806076.04
      2487138.61     13805776.69
#Sta/Elev= 30
  3454.6  370.96  3711.3  367.84  3824.7  365.06  3909.5  361.74  3938.2  363.31
  4094.7  361.85  4152.2  360.11  4158.6  360.95  4173.0  360.07  4179.4  361.03
  4192.7  360.76  4225.9  360.56  4319.1  360.88  4376.5  360.74  4527.0  360.82
  4709.2  359.40  4935.8  358.54  4979.5  356.02  4985.8  353.39  4986.3  352.89
  4994.9  353.39  5002.9  355.55  5020.8  357.86  5066.7  358.65  5135.9  363.96
  5158.4  365.41  5239.8  370.45  5346.0  374.92  5446.0  377.82  5532.0  378.63
#Mann=13,-1,0
  3454.6    0.05       0  4192.7     0.1       0  4225.9    0.07       0
  4319.1     0.1       0  4376.5    0.07       0  4527.0   0.035       0
  4709.2     0.1       0  4985.8    0.05       0  4994.9     0.1       0
  5135.9    0.07       0  5158.4   0.035       0  5239.8    0.07       0
  5346.0    0.05       0
Bank Sta=4985.8,4994.9
Exp/Cntr=0.3,0.1

Chan Stop Cuts=-1