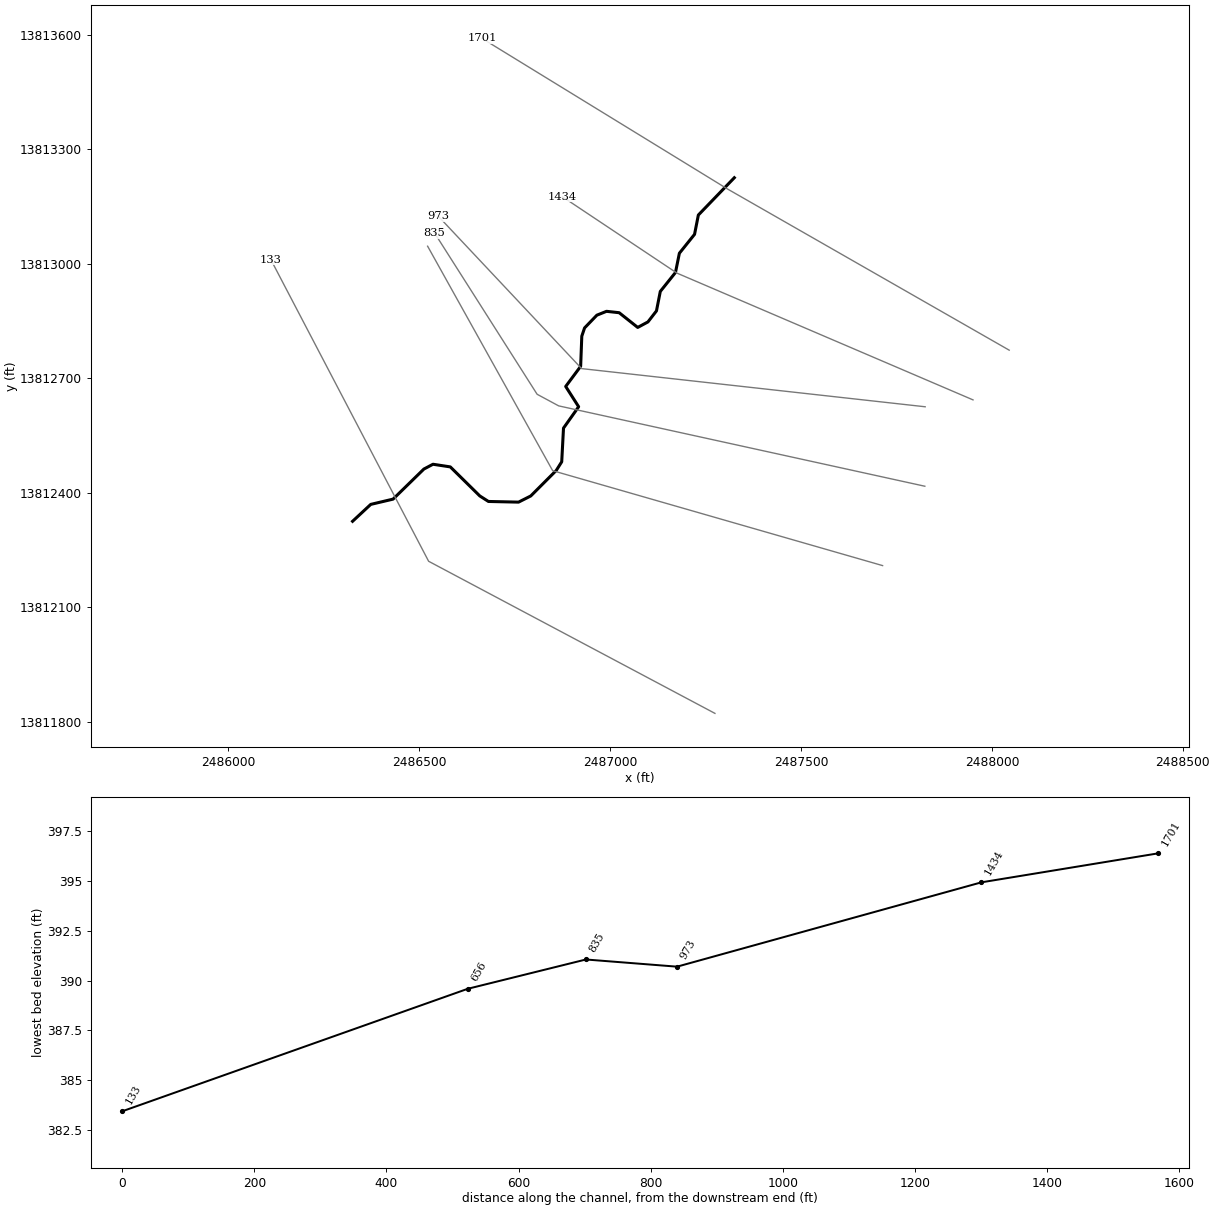
--- Stream0445.prj (project) ---

Proj Title=Stream0445 Base Level Engineering
Current Plan=p01
Default Exp/Contr=0.3,0.1
English Units
Geom File=g01
Flow File=f01
Plan File=p01
BEGIN DESCRIPTION:
Stream0445
END DESCRIPTION:

--- Stream0445.p01 (plan) ---

Plan Title=Multiple Run
Short Identifier=Multiple
Geom File=g01
Flow File=f01
Subcritical Flow
K Sum by GR= 0
Std Step Tol= 0.01
Critical Tol= 0.01
Num of Std Step Trials= 20
Max Error Tol= 0.3
Flow Tol Ratio= 0.001
Split Flow NTrial= 30
Split Flow Tol= 0.02
Split Flow Ratio= 0.02
Log Output Level= 0
Friction Slope Method= 1
Unsteady Friction Slope Method= 2
Unsteady Bridges Friction Slope Method= 1
Parabolic Critical Depth
Global Vel Dist=  1 , 1 , 1
Global Log Level= 0
CheckData=True
Encroach Param= -1, 0, 0, 0
BEGIN DESCRIPTION:
Multiple Run
END DESCRIPTION:

--- Stream0445.f01 (steady flow) ---

Flow Title=Multiple
Number of Profiles=7
Profile Names=10-year,25-year,50-year,1pct_min,100-year,1pct_plu,500-year
River Rch & RM= Stream0445,Reach-1,1701
     414     645     846     539    1076    2146    1717
Boundary for River Rch & Prof#=Stream0445,Reach-1,1
Up Type=0
Dn Type=3
Dn Slope=0.005
Boundary for River Rch & Prof#=Stream0445,Reach-1,2
Up Type=0
Dn Type=3
Dn Slope=0.005
Boundary for River Rch & Prof#=Stream0445,Reach-1,3
Up Type=0
Dn Type=3
Dn Slope=0.005
Boundary for River Rch & Prof#=Stream0445,Reach-1,4
Up Type=0
Dn Type=3
Dn Slope=0.005
Boundary for River Rch & Prof#=Stream0445,Reach-1,5
Up Type=0
Dn Type=3
Dn Slope=0.005
Boundary for River Rch & Prof#=Stream0445,Reach-1,6
Up Type=0
Dn Type=3
Dn Slope=0.005
Boundary for River Rch & Prof#=Stream0445,Reach-1,7
Up Type=0
Dn Type=3
Dn Slope=0.005

--- Stream0445.g01 (geometry) ---

Geom Title=Existing Conditions

River Reach=Stream0445,Reach-1
Reach XY= 30
      2487325.00     13813225.00      2487230.79     13813127.32
      2487220.82     13813076.73      2487181.08     13813027.20
      2487170.84     13812976.72      2487131.10     13812927.14
      2487121.06     13812876.16      2487098.73     13812847.30
      2487071.95     13812832.84      2487023.33     13812871.42
      2486990.22     13812875.04      2486964.95     13812864.95
      2486932.74     13812831.55      2486925.46     13812809.94
      2486922.45     13812730.90      2486883.28     13812678.22
      2486917.21     13812625.10      2486877.55     13812569.11
      2486872.86     13812480.88      2486858.56     13812458.21
      2486791.79     13812391.39      2486759.79     13812375.23
      2486680.90     13812376.97      2486658.26     13812391.44
      2486581.04     13812467.52      2486535.64     13812474.44
      2486511.80     13812461.87      2486431.08     13812383.08
      2486372.65     13812369.30      2486325.00     13812325.00

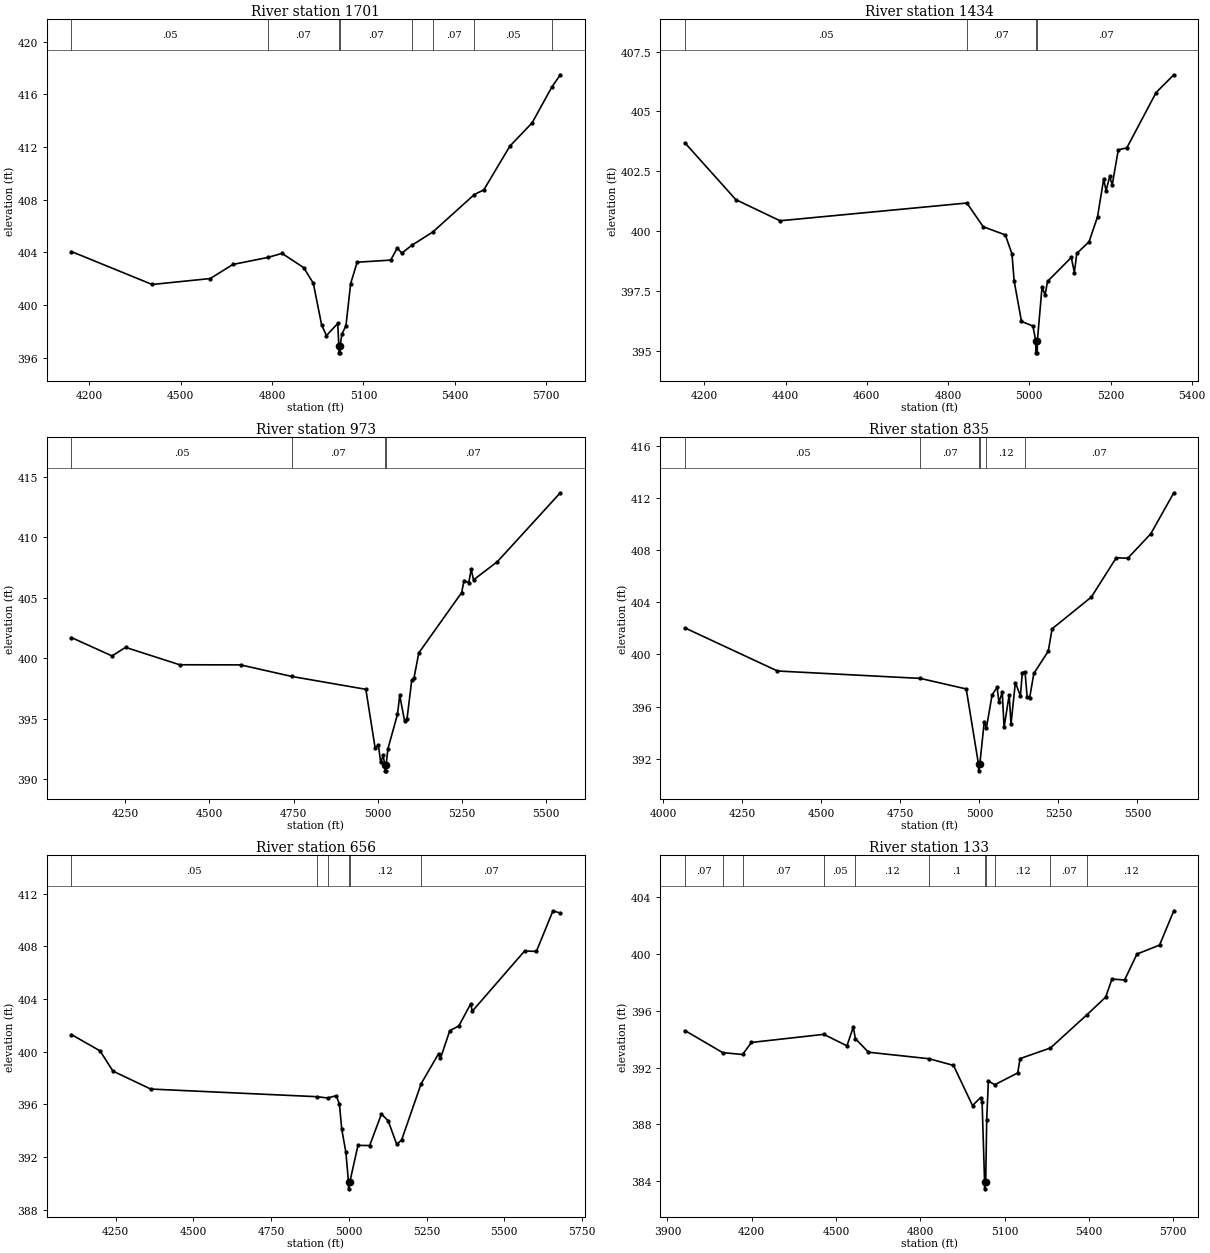
Type RM Length L Ch R = 1,1701,267,267,267
BEGIN DESCRIPTION:
XS6817
END DESCRIPTION:
XS GIS Cut Line= 3
      2488045.01     13812773.29      2487306.97     13813195.59
      2486663.87     13813590.13
#Sta/Elev= 30
  4141.3  404.07  4406.3  401.57  4597.1  402.02  4671.3  403.09  4785.5  403.62
  4832.6  403.93  4903.7  402.85  4935.3  401.66  4962.7  398.49  4978.5  397.69
  5015.4  398.61  5019.2  396.88  5019.5  396.38  5023.0  396.38  5023.2  396.88
  5029.1  397.80  5042.5  398.44  5057.9  401.64  5079.2  403.26  5189.4  403.42
  5210.7  404.33  5226.1  403.95  5257.7  404.53  5327.4  405.55  5463.9  408.40
  5494.9  408.75  5580.5  412.07  5653.5  413.84  5718.4  416.56  5746.1  417.49
#Mann=8,-1,0
  4141.3    0.05       0  4785.5    0.07       0  5019.2    0.05       0
  5023.2    0.07       0  5257.7    0.05       0  5327.4    0.07       0
  5463.9    0.05       0  5718.4    0.07       0
Bank Sta=5019.2,5023.2
Exp/Cntr=0.3,0.1

Type RM Length L Ch R = 1,1434,461,461,461
BEGIN DESCRIPTION:
Stream0445 2.0
END DESCRIPTION:
XS GIS Cut Line= 3
      2487950.28     13812643.06      2487175.00     13812975.00
      2486875.00     13813175.00
#Sta/Elev= 30
  4152.0  403.69  4277.4  401.32  4386.2  400.44  4846.3  401.18  4886.6  400.19
  4941.0  399.85  4957.3  399.06  4962.7  397.93  4980.8  396.24  5008.9  396.05
  5015.9  395.43  5016.1  394.93  5019.6  394.93  5019.9  395.43  5031.4  397.68
  5038.9  397.34  5044.9  397.91  5103.5  398.91  5111.0  398.28  5117.0  399.08
  5147.1  399.56  5168.1  400.61  5183.1  402.17  5189.1  401.70  5198.2  402.29
  5204.2  401.93  5219.2  403.40  5240.2  403.48  5312.3  405.79  5355.9  406.53
#Mann=4,-1,0
  4152.0    0.05       0  4846.3    0.07       0  5015.9    0.05       0
  5019.9    0.07       0
Bank Sta=5015.9,5019.9
Exp/Cntr=0.3,0.1

Type RM Length L Ch R = 1,973,138,138,138
BEGIN DESCRIPTION:
Stream0445 1.0
END DESCRIPTION:
XS GIS Cut Line= 3
      2487824.96     13812625.00      2486925.00     13812725.00
      2486549.64     13813124.12
#Sta/Elev= 30
  4089.6  401.72  4210.3  400.20  4250.5  400.91  4411.5  399.47  4592.6  399.46
  4745.3  398.50  4964.9  397.44  4992.6  392.57  5002.2  392.82  5009.0  391.40
  5016.3  391.97  5021.2  391.20  5021.5  390.70  5025.0  390.70  5025.2  391.20
  5030.5  392.52  5058.8  395.36  5065.7  396.93  5079.9  394.84  5087.2  394.97
  5101.3  398.19  5108.2  398.40  5122.3  400.45  5249.8  405.44  5256.7  406.43
  5270.8  406.26  5278.1  407.36  5285.0  406.49  5355.8  407.99  5543.0  413.69
#Mann=4,-1,0
  4089.6    0.05       0  4745.3    0.07       0  5021.2    0.05       0
  5025.2    0.07       0
Bank Sta=5021.2,5025.2
Exp/Cntr=0.3,0.1

Type RM Length L Ch R = 1,835,179,179,179
BEGIN DESCRIPTION:
Stream0445 1.0a
END DESCRIPTION:
XS GIS Cut Line= 4
      2487824.07     13812416.87      2486864.85     13812627.38
      2486808.43     13812657.76      2486539.99     13813079.91
#Sta/Elev= 30
  4068.5  402.04  4361.2  398.73  4813.2  398.16  4958.3  397.35  4997.2  391.56
  4997.5  391.06  5001.2  391.56  5015.3  394.83  5022.1  394.35  5040.2  396.90
  5056.1  397.48  5061.7  396.32  5072.3  397.10  5078.0  394.39  5094.2  396.90
  5099.9  394.64  5113.7  397.84  5129.7  396.82  5135.7  398.60  5144.3  398.66
  5150.9  396.76  5158.8  396.65  5172.1  398.54  5217.8  400.25  5229.9  401.97
  5354.1  404.41  5432.9  407.43  5469.3  407.39  5542.1  409.27  5614.9  412.42
#Mann=6,-1,0
  4068.5    0.05       0  4813.2    0.07       0  4997.2    0.05       0
  5001.2    0.07       0  5022.1    0.12       0  5144.3    0.07       0
Bank Sta=4997.2,5001.2
Exp/Cntr=0.3,0.1

Type RM Length L Ch R = 1,656,523,523,523
BEGIN DESCRIPTION:
XS6818
END DESCRIPTION:
XS GIS Cut Line= 3
      2487713.42     13812208.97      2486849.17     13812457.59
      2486521.61     13813045.61
#Sta/Elev= 30
  4107.9  401.31  4199.9  400.07  4241.5  398.53  4363.0  397.17  4896.5  396.59
  4932.2  396.49  4959.5  396.67  4969.9  396.01  4977.4  394.11  4990.7  392.36
  4999.1  390.09  4999.4  389.59  5003.1  390.09  5029.5  392.89  5067.2  392.88
  5104.9  395.27  5126.6  394.76  5154.1  392.97  5170.1  393.31  5232.6  397.57
  5288.9  399.86  5294.7  399.49  5324.8  401.60  5354.1  401.97  5391.8  403.63
  5397.5  403.09  5565.6  407.66  5603.3  407.62  5656.7  410.71  5680.3  410.53
#Mann=6,-1,0
  4107.9    0.05       0  4896.5    0.07       0  4932.2    0.12       0
  4999.1    0.05       0  5003.1    0.12       0  5232.6    0.07       0
Bank Sta=4999.1,5003.1
Exp/Cntr=0.3,0.1

Type RM Length L Ch R = 1,133,0,0,0
BEGIN DESCRIPTION:
XS6819
END DESCRIPTION:
XS GIS Cut Line= 3
      2487274.24     13811821.87      2486524.22     13812220.31
      2486111.20     13813010.04
#Sta/Elev= 30
  3962.1  394.61  4096.6  393.05  4167.3  392.92  4199.0  393.77  4456.5  394.34
  4539.0  393.53  4561.4  394.85  4569.1  394.03  4615.6  393.08  4831.6  392.62
  4918.2  392.15  4986.0  389.32  5014.4  389.88  5020.1  389.56  5028.9  383.95
  5029.1  383.45  5032.9  383.95  5036.5  388.33  5042.4  391.05  5065.3  390.79
  5146.9  391.62  5155.2  392.63  5263.5  393.38  5393.8  395.73  5459.9  396.96
  5482.5  398.24  5527.3  398.17  5571.4  400.00  5651.8  400.63  5702.6  403.05
#Mann=11,-1,0
  3962.1    0.07       0  4096.6    0.05       0  4167.3    0.07       0
  4456.5    0.05       0  4569.1    0.12       0  4831.6     0.1       0
  5028.9    0.05       0  5032.9     0.1       0  5065.3    0.12       0
  5263.5    0.07       0  5393.8    0.12       0
Bank Sta=5028.9,5032.9
Exp/Cntr=0.3,0.1

Chan Stop Cuts=-1