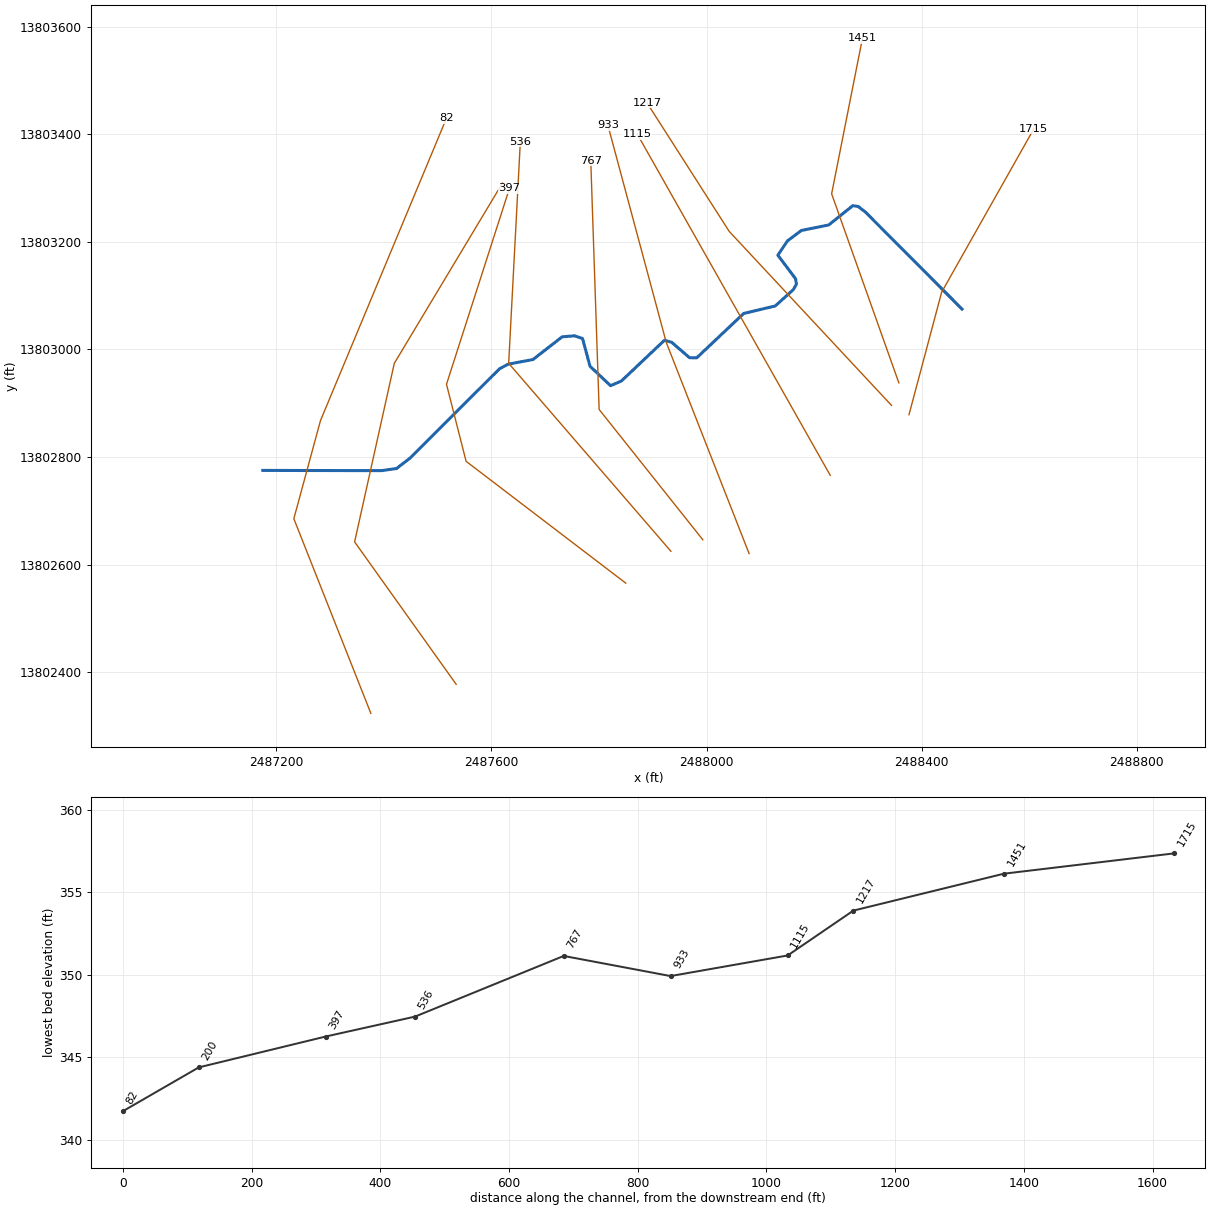
--- Stream0446.prj (project) ---

Proj Title=Stream0446 Base Level Engineering
Current Plan=p01
Default Exp/Contr=0.3,0.1
English Units
Geom File=g01
Flow File=f01
Plan File=p01
BEGIN DESCRIPTION:
Stream0446
END DESCRIPTION:

--- Stream0446.p01 (plan) ---

Plan Title=Multiple Run
Short Identifier=Multiple
Geom File=g01
Flow File=f01
Subcritical Flow
K Sum by GR= 0
Std Step Tol= 0.01
Critical Tol= 0.01
Num of Std Step Trials= 20
Max Error Tol= 0.3
Flow Tol Ratio= 0.001
Split Flow NTrial= 30
Split Flow Tol= 0.02
Split Flow Ratio= 0.02
Log Output Level= 0
Friction Slope Method= 1
Unsteady Friction Slope Method= 2
Unsteady Bridges Friction Slope Method= 1
Parabolic Critical Depth
Global Vel Dist=  1 , 1 , 1
Global Log Level= 0
CheckData=True
Encroach Param= -1, 0, 0, 0
BEGIN DESCRIPTION:
Multiple Run
END DESCRIPTION:

--- Stream0446.f01 (steady flow) ---

Flow Title=Multiple
Number of Profiles=7
Profile Names=10-year,25-year,50-year,1pct_min,100-year,1pct_plu,500-year
River Rch & RM= Stream0446,Reach-1,1715
     259     391     504     315     629    1256     969
Boundary for River Rch & Prof#=Stream0446,Reach-1,1
Up Type=0
Dn Type=3
Dn Slope=0.005
Boundary for River Rch & Prof#=Stream0446,Reach-1,2
Up Type=0
Dn Type=3
Dn Slope=0.005
Boundary for River Rch & Prof#=Stream0446,Reach-1,3
Up Type=0
Dn Type=3
Dn Slope=0.005
Boundary for River Rch & Prof#=Stream0446,Reach-1,4
Up Type=0
Dn Type=3
Dn Slope=0.005
Boundary for River Rch & Prof#=Stream0446,Reach-1,5
Up Type=0
Dn Type=3
Dn Slope=0.005
Boundary for River Rch & Prof#=Stream0446,Reach-1,6
Up Type=0
Dn Type=3
Dn Slope=0.005
Boundary for River Rch & Prof#=Stream0446,Reach-1,7
Up Type=0
Dn Type=3
Dn Slope=0.005

--- Stream0446.g01 (geometry) ---

Geom Title=Existing Conditions

River Reach=Stream0446,Reach-1
Reach XY= 30
      2488475.00     13803075.00      2488295.03     13803255.72
      2488281.73     13803265.89      2488271.77     13803267.17
      2488227.24     13803231.43      2488176.18     13803221.09
      2488150.64     13803202.00      2488132.48     13803175.20
      2488165.44     13803131.53      2488167.10     13803121.43
      2488161.49     13803111.32      2488127.83     13803080.85
      2488068.99     13803066.80      2487981.66     13802984.32
      2487968.33     13802984.62      2487935.00     13803013.28
      2487921.67     13803016.97      2487841.58     13802941.24
      2487821.43     13802932.55      2487783.28     13802968.69
      2487769.39     13803020.17      2487754.66     13803025.29
      2487731.51     13803023.39      2487677.22     13802981.20
      2487631.04     13802972.51      2487615.32     13802964.24
      2487448.53     13802797.86      2487423.54     13802778.53
      2487395.18     13802774.57      2487175.00     13802775.00

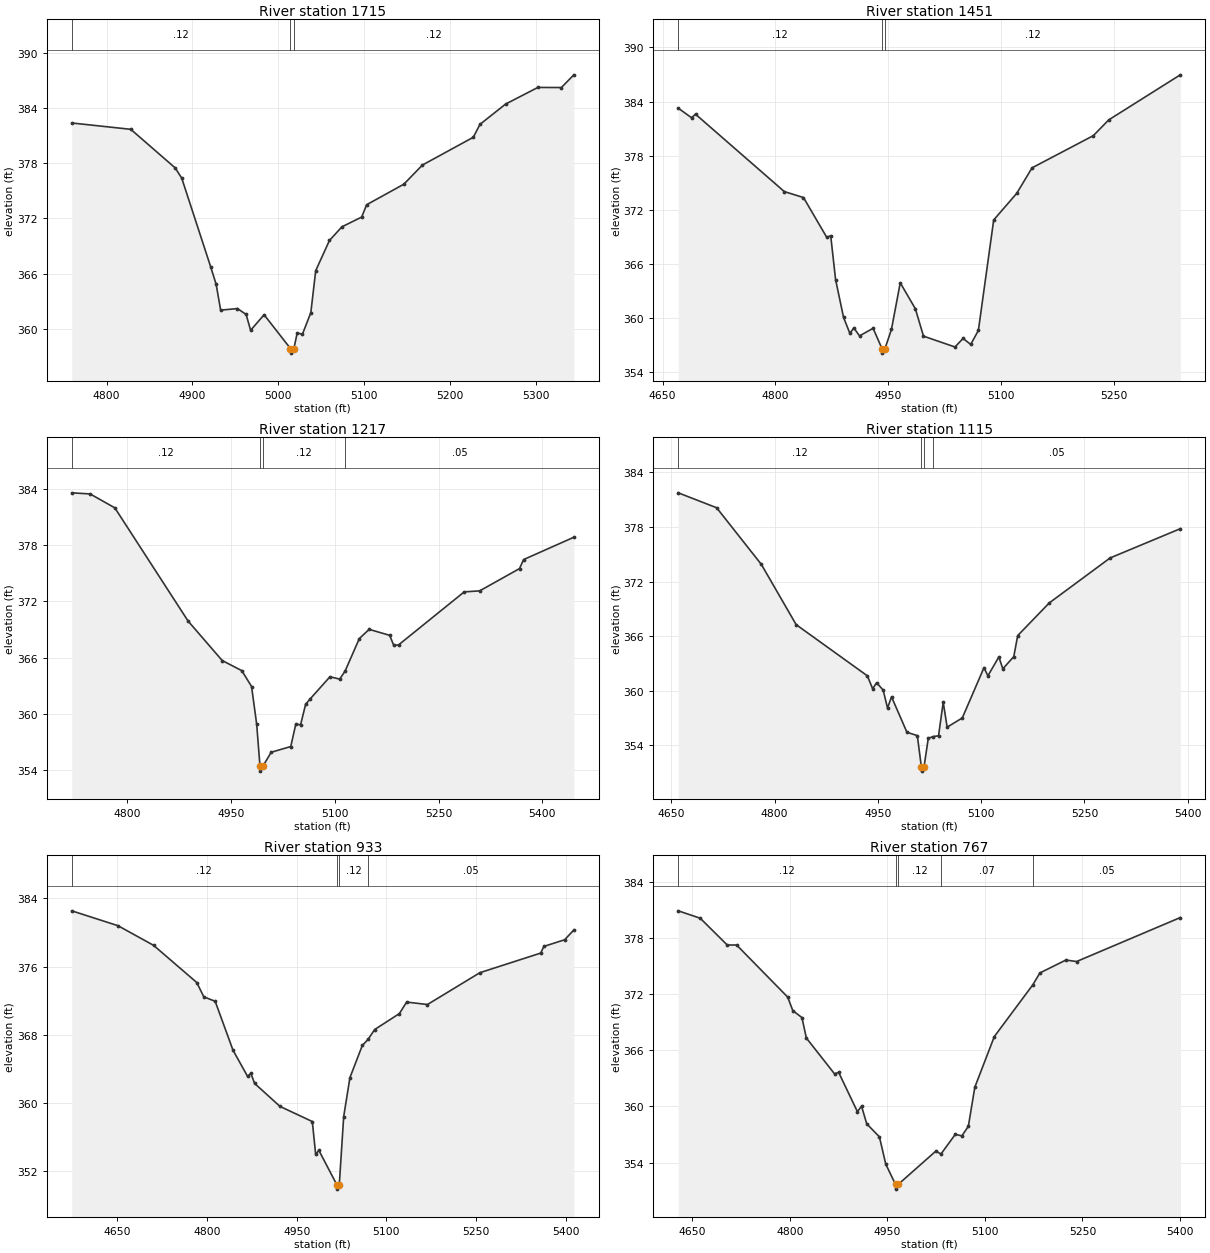
Type RM Length L Ch R = 1,1715,264,264,264
BEGIN DESCRIPTION:
XS6826
END DESCRIPTION:
XS GIS Cut Line= 3
      2488376.40     13802878.63      2488437.15     13803106.47
      2488608.52     13803410.15
#Sta/Elev= 30
  4759.5  382.37  4828.2  381.68  4879.9  377.49  4887.5  376.38  4921.3  366.72
  4927.6  364.84  4932.8  362.04  4952.4  362.21  4962.5  361.57  4967.7  359.85
  4983.4  361.54  5014.1  357.87  5014.4  357.37  5018.1  357.87  5021.9  359.54
  5028.1  359.44  5037.8  361.77  5043.5  366.33  5059.5  369.61  5074.0  371.09
  5097.0  372.15  5102.8  373.49  5146.1  375.72  5167.7  377.80  5227.0  380.82
  5234.7  382.22  5264.5  384.42  5302.1  386.23  5329.5  386.22  5344.0  387.60
#Mann=3,-1,0
  4759.5    0.12       0  5014.1    0.05       0  5018.1    0.12       0
Bank Sta=5014.1,5018.1
Exp/Cntr=0.3,0.1

Type RM Length L Ch R = 1,1451,234,234,234
BEGIN DESCRIPTION:
E21049
END DESCRIPTION:
XS GIS Cut Line= 3
      2488357.54     13802937.81      2488232.55     13803289.35
      2488289.85     13803578.43
#Sta/Elev= 30
  4670.9  383.27  4688.6  382.21  4693.9  382.60  4812.0  374.03  4837.5  373.37
  4868.4  368.97  4873.7  369.14  4880.2  364.28  4890.8  360.09  4899.2  358.33
  4904.5  358.93  4912.0  358.05  4930.1  358.89  4941.9  356.64  4942.1  356.14
  4945.9  356.64  4954.5  358.77  4966.2  363.93  4986.3  361.05  4997.1  358.02
  5039.0  356.82  5049.8  357.77  5059.9  357.10  5070.1  358.65  5090.5  370.89
  5121.1  373.83  5141.5  376.66  5223.1  380.23  5243.5  381.97  5338.7  386.96
#Mann=3,-1,0
  4670.9    0.12       0  4941.9    0.05       0  4945.9    0.12       0
Bank Sta=4941.9,4945.9
Exp/Cntr=0.3,0.1

Type RM Length L Ch R = 1,1217,102,102,102
BEGIN DESCRIPTION:
XS6825
END DESCRIPTION:
XS GIS Cut Line= 3
      2488343.86     13802895.94      2488042.19     13803219.31
      2487889.13     13803458.60
#Sta/Elev= 30
  4719.4  383.54  4746.0  383.42  4781.7  381.94  4887.7  369.88  4937.0  365.68
  4965.4  364.60  4979.5  362.91  4986.9  358.89  4991.7  354.40  4992.0  353.90
  4995.7  354.40  5007.9  355.91  5036.2  356.52  5043.5  358.91  5050.4  358.84
  5057.7  361.02  5064.5  361.61  5092.9  363.95  5107.0  363.70  5114.8  364.56
  5135.4  368.02  5149.6  369.00  5179.3  368.36  5185.2  367.29  5192.1  367.34
  5287.1  372.99  5309.5  373.10  5367.1  375.47  5373.0  376.43  5445.7  378.81
#Mann=4,-1,0
  4719.4    0.12       0  4991.7    0.05       0  4995.7    0.12       0
  5114.8    0.05       0
Bank Sta=4991.7,4995.7
Exp/Cntr=0.3,0.1

Type RM Length L Ch R = 1,1115,182,182,182
BEGIN DESCRIPTION:
E21048
END DESCRIPTION:
XS GIS Cut Line= 2
      2488229.97     13802765.87      2487870.94     13803400.67
#Sta/Elev= 30
  4659.9  381.75  4715.7  380.11  4780.6  373.89  4831.2  367.27  4934.6  361.65
  4942.3  360.23  4948.0  360.89  4957.6  360.08  4963.9  358.11  4969.7  359.34
  4992.1  355.45  5007.2  355.08  5013.0  351.68  5013.3  351.18  5017.0  351.68
  5023.1  354.79  5030.4  354.98  5038.0  355.06  5044.8  358.75  5050.5  356.01
  5072.5  357.02  5104.0  362.54  5109.7  361.65  5125.6  363.72  5131.4  362.42
  5147.3  363.76  5153.0  366.07  5198.9  369.66  5287.3  374.60  5389.2  377.81
#Mann=4,-1,0
  4659.9    0.12       0  5013.0    0.05       0  5017.0    0.12       0
  5030.4    0.05       0
Bank Sta=5013,5017
Exp/Cntr=0.3,0.1

Type RM Length L Ch R = 1,933,166,166,166
BEGIN DESCRIPTION:
XS6824
END DESCRIPTION:
XS GIS Cut Line= 3
      2488079.08     13802620.35      2487925.00     13803013.15
      2487816.50     13803416.78
#Sta/Elev= 30
  4573.8  382.54  4651.0  380.80  4710.6  378.50  4782.9  374.14  4794.7  372.46
  4813.7  371.94  4843.5  366.21  4868.0  363.13  4873.4  363.51  4879.6  362.32
  4922.2  359.62  4976.2  357.85  4981.8  354.01  4987.2  354.47  5017.3  350.43
  5017.5  349.93  5021.3  350.43  5028.7  358.44  5039.1  362.99  5059.8  366.76
  5069.5  367.48  5080.5  368.63  5121.9  370.50  5134.0  371.85  5168.8  371.56
  5256.5  375.29  5358.3  377.59  5363.5  378.37  5398.3  379.15  5413.7  380.30
#Mann=4,-1,0
  4573.8    0.12       0  5017.3    0.05       0  5021.3    0.12       0
  5069.5    0.05       0
Bank Sta=5017.3,5021.3
Exp/Cntr=0.3,0.1

Type RM Length L Ch R = 1,767,231,231,231
BEGIN DESCRIPTION:
E21047
END DESCRIPTION:
XS GIS Cut Line= 3
      2487993.00     13802646.08      2487800.26     13802888.30
      2487784.67     13803350.89
#Sta/Elev= 30
  4628.1  380.95  4661.9  380.16  4703.5  377.29  4717.9  377.29  4796.4  371.72
  4804.4  370.26  4818.4  369.52  4825.2  367.33  4868.5  363.50  4874.9  363.65
  4903.7  359.45  4910.1  360.03  4918.1  358.14  4937.6  356.75  4947.4  353.82
  4962.4  351.65  4962.6  351.15  4966.4  351.65  5024.4  355.22  5032.3  354.91
  5054.4  357.02  5064.4  356.85  5074.4  357.87  5084.4  362.07  5114.4  367.49
  5173.6  373.03  5184.5  374.30  5224.5  375.68  5240.9  375.52  5400.5  380.23
#Mann=5,-1,0
  4628.1    0.12       0  4962.4    0.05       0  4966.4    0.12       0
  5032.3    0.07       0  5173.6    0.05       0
Bank Sta=4962.4,4966.4
Exp/Cntr=0.3,0.1

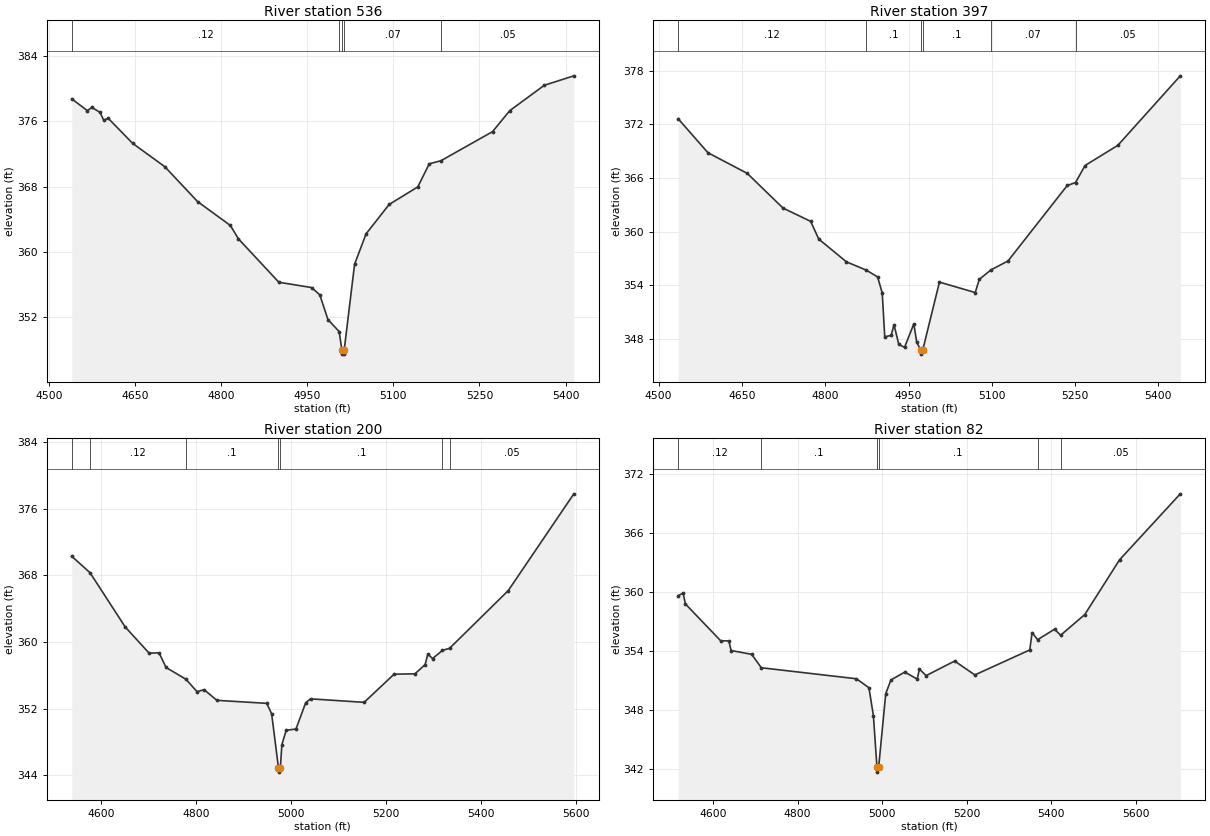
Type RM Length L Ch R = 1,536,139,139,139
BEGIN DESCRIPTION:
XS6823
END DESCRIPTION:
XS GIS Cut Line= 3
      2487933.70     13802624.68      2487632.03     13802974.09
      2487653.73     13803386.40
#Sta/Elev= 30
  4539.9  378.76  4567.1  377.31  4574.8  377.71  4589.0  377.11  4595.6  376.14
  4603.3  376.38  4646.0  373.30  4702.0  370.44  4759.0  366.17  4816.1  363.24
  4830.3  361.59  4900.6  356.28  4957.6  355.63  4971.9  354.74  4986.1  351.70
  5005.6  350.24  5010.4  347.97  5010.7  347.47  5014.2  347.47  5014.4  347.97
  5032.5  358.49  5052.5  362.21  5092.6  365.81  5142.6  367.97  5162.6  370.80
  5182.8  371.17  5272.8  374.74  5302.8  377.31  5362.9  380.42  5414.4  381.58
#Mann=5,-1,0
  4539.9    0.12       0  5005.6    0.07       0  5010.4    0.05       0
  5014.4    0.07       0  5182.8    0.05       0
Bank Sta=5010.4,5014.4
Exp/Cntr=0.3,0.1

Type RM Length L Ch R = 1,397,197,197,197
BEGIN DESCRIPTION:
E21050
END DESCRIPTION:
XS GIS Cut Line= 4
      2487849.75     13802565.38      2487552.86     13802791.95
      2487516.41     13802935.18      2487633.59     13803299.75
#Sta/Elev= 30
  4535.3  372.63  4588.8  368.83  4659.5  366.52  4724.0  362.63  4773.8  361.14
  4788.4  359.15  4838.3  356.60  4874.1  355.67  4894.4  354.91  4902.7  353.11
  4907.2  348.21  4918.7  348.35  4923.9  349.56  4932.5  347.35  4942.9  347.02
  4959.6  349.66  4964.8  347.58  4971.8  346.76  4972.1  346.26  4975.8  346.76
  5005.7  354.33  5070.2  353.16  5077.4  354.64  5098.7  355.71  5129.2  356.70
  5235.9  365.16  5250.8  365.49  5268.0  367.40  5327.0  369.66  5439.5  377.45
#Mann=6,-1,0
  4535.3    0.12       0  4874.1     0.1       0  4971.8    0.05       0
  4975.8     0.1       0  5098.7    0.07       0  5250.8    0.05       0
Bank Sta=4971.8,4975.8
Exp/Cntr=0.3,0.1

Type RM Length L Ch R = 1,200,118,118,118
BEGIN DESCRIPTION:
XS6822
END DESCRIPTION:
XS GIS Cut Line= 4
      2487534.36     13802377.32      2487345.57     13802642.06
      2487419.36     13802974.09      2487620.43     13803309.20
#Sta/Elev= 30
  4539.1  370.28  4577.5  368.31  4651.4  361.81  4701.8  358.66  4722.7  358.70
  4737.5  356.94  4779.3  355.53  4802.6  354.04  4817.4  354.28  4844.4  353.00
  4949.2  352.64  4959.5  351.40  4973.9  344.89  4974.1  344.39  4977.9  344.89
  4981.0  347.68  4990.2  349.41  5010.7  349.56  5031.2  352.72  5041.4  353.18
  5154.1  352.76  5217.1  356.14  5260.9  356.18  5282.3  357.28  5288.2  358.56
  5297.9  358.01  5318.9  358.99  5334.0  359.25  5457.3  366.17  5595.2  377.77
#Mann=7,-1,0
  4539.1    0.07       0  4577.5    0.12       0  4779.3     0.1       0
  4973.9    0.05       0  4977.9     0.1       0  5318.9    0.07       0
  5334.0    0.05       0
Bank Sta=4973.9,4977.9
Exp/Cntr=0.3,0.1

Type RM Length L Ch R = 1,82,0,0,0
BEGIN DESCRIPTION:
E21046
END DESCRIPTION:
XS GIS Cut Line= 4
      2487375.77     13802323.23      2487232.55     13802685.18
      2487282.03     13802867.47      2487516.40     13803429.95
#Sta/Elev= 30
  4517.7  359.65  4529.2  359.91  4534.6  358.81  4618.3  355.06  4637.3  355.06
  4642.7  354.08  4691.4  353.69  4714.2  352.33  4939.2  351.21  4968.7  350.30
  4979.3  347.48  4987.7  342.23  4987.9  341.73  4991.7  342.23  5008.5  349.70
  5020.8  351.09  5053.5  351.89  5082.9  351.18  5088.1  352.20  5104.0  351.53
  5171.5  353.01  5219.2  351.60  5349.2  354.14  5354.6  355.90  5367.7  355.18
  5407.7  356.24  5422.1  355.63  5479.2  357.73  5561.5  363.29  5705.2  369.99
#Mann=6,-1,0
  4517.7    0.12       0  4714.2     0.1       0  4987.7    0.05       0
  4991.7     0.1       0  5367.7    0.07       0  5422.1    0.05       0
Bank Sta=4987.7,4991.7
Exp/Cntr=0.3,0.1

Chan Stop Cuts=-1