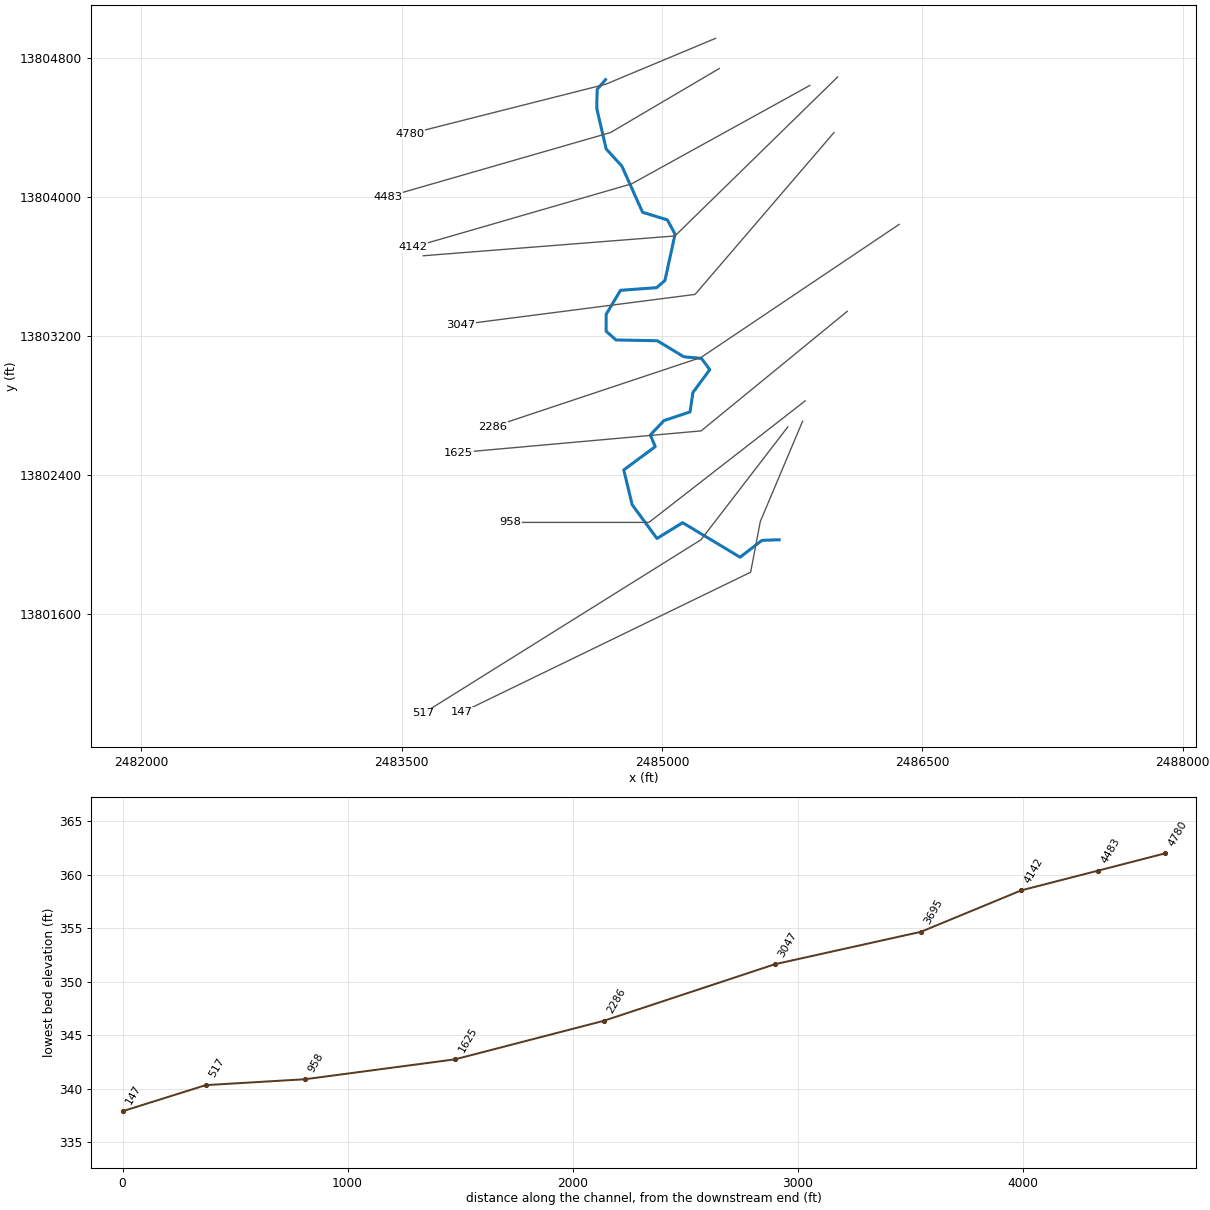
--- Stream0447.prj (project) ---

Proj Title=Stream0447 Base Level Engineering
Current Plan=p01
Default Exp/Contr=0.3,0.1
English Units
Geom File=g01
Flow File=f01
Plan File=p01
BEGIN DESCRIPTION:
Stream0447
END DESCRIPTION:

--- Stream0447.p01 (plan) ---

Plan Title=Multiple Run
Short Identifier=Multiple
Geom File=g01
Flow File=f01
Subcritical Flow
K Sum by GR= 0
Std Step Tol= 0.01
Critical Tol= 0.01
Num of Std Step Trials= 20
Max Error Tol= 0.3
Flow Tol Ratio= 0.001
Split Flow NTrial= 30
Split Flow Tol= 0.02
Split Flow Ratio= 0.02
Log Output Level= 0
Friction Slope Method= 1
Unsteady Friction Slope Method= 2
Unsteady Bridges Friction Slope Method= 1
Parabolic Critical Depth
Global Vel Dist=  1 , 1 , 1
Global Log Level= 0
CheckData=True
Encroach Param= -1, 0, 0, 0
BEGIN DESCRIPTION:
Multiple Run
END DESCRIPTION:

--- Stream0447.f01 (steady flow) ---

Flow Title=Multiple
Number of Profiles=7
Profile Names=10-year,25-year,50-year,1pct_min,100-year,1pct_plu,500-year
River Rch & RM= Stream0447,Reach-1,4780
    1013    1658    2250    1477    2947    5880    5005
Boundary for River Rch & Prof#=Stream0447,Reach-1,1
Up Type=0
Dn Type=3
Dn Slope=0.005
Boundary for River Rch & Prof#=Stream0447,Reach-1,2
Up Type=0
Dn Type=3
Dn Slope=0.005
Boundary for River Rch & Prof#=Stream0447,Reach-1,3
Up Type=0
Dn Type=3
Dn Slope=0.005
Boundary for River Rch & Prof#=Stream0447,Reach-1,4
Up Type=0
Dn Type=3
Dn Slope=0.005
Boundary for River Rch & Prof#=Stream0447,Reach-1,5
Up Type=0
Dn Type=3
Dn Slope=0.005
Boundary for River Rch & Prof#=Stream0447,Reach-1,6
Up Type=0
Dn Type=3
Dn Slope=0.005
Boundary for River Rch & Prof#=Stream0447,Reach-1,7
Up Type=0
Dn Type=3
Dn Slope=0.005

--- Stream0447.g01 (geometry) ---

Geom Title=Existing Conditions

River Reach=Stream0447,Reach-1
Reach XY= 30
      2484675.00     13804675.00      2484626.88     13804619.21
      2484624.53     13804509.83      2484678.55     13804276.47
      2484769.15     13804177.29      2484888.45     13803911.37
      2485031.50     13803867.27      2485075.57     13803785.24
      2485017.28     13803518.50      2484969.35     13803476.97
      2484761.33     13803461.78      2484678.67     13803323.41
      2484678.36     13803226.25      2484735.26     13803175.98
      2484973.45     13803171.25      2485126.59     13803078.83
      2485227.75     13803069.58      2485275.52     13803004.95
      2485178.63     13802873.50      2485161.77     13802761.28
      2485011.64     13802711.59      2484933.00     13802628.34
      2484961.50     13802561.32      2484780.08     13802427.31
      2484828.62     13802226.50      2484971.42     13802032.49
      2485118.95     13802123.41      2485450.03     13801924.50
      2485576.41     13802021.60      2485675.00     13802025.00

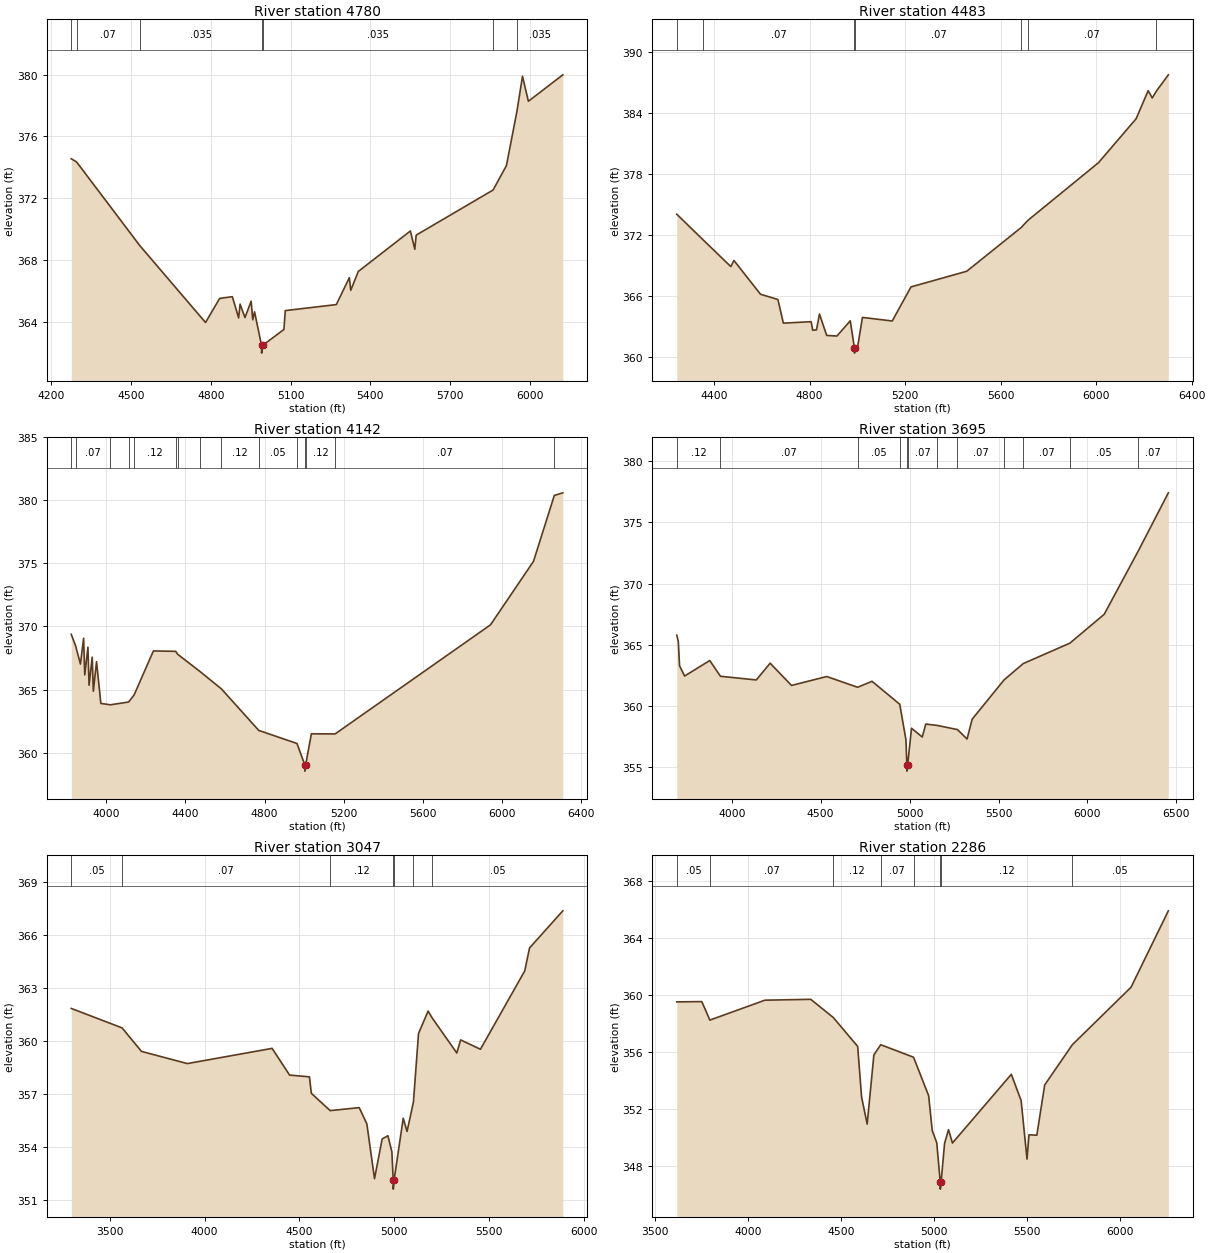
Type RM Length L Ch R = 1,4780,297,297,297
BEGIN DESCRIPTION:
XS6830
END DESCRIPTION:
XS GIS Cut Line= 3
      2485309.15     13804913.22      2484676.07     13804648.85
      2483549.45     13804363.72
#Sta/Elev= 30
  4275.4  374.55  4295.3  374.35  4532.9  368.94  4780.3  363.96  4833.4  365.52
  4881.0  365.63  4904.8  364.26  4910.2  365.15  4928.6  364.28  4951.8  365.34
  4957.8  364.14  4964.6  364.65  4990.9  362.48  4991.2  361.98  4994.9  362.48
  5075.0  363.51  5080.1  364.73  5272.0  365.12  5321.0  366.86  5326.2  366.04
  5354.5  367.26  5550.5  369.88  5567.1  368.70  5572.2  369.61  5861.4  372.53
  5911.6  374.11  5951.1  377.62  5972.0  379.89  5994.1  378.27  6123.6  379.98
#Mann=7,-1,0
  4275.4   0.035       0  4295.3    0.07       0  4532.9   0.035       0
  4990.9   0.035       0  4994.9   0.035       0  5861.4   0.063       0
  5951.1   0.035       0
Bank Sta=4990.9,4994.9
Exp/Cntr=0.3,0.1

Type RM Length L Ch R = 1,4483,341,341,341
BEGIN DESCRIPTION:
Stream0447 6.0
END DESCRIPTION:
XS GIS Cut Line= 3
      2485330.08     13804739.31      2484703.89     13804370.56
      2483423.74     13804001.82
#Sta/Elev= 30
  4243.4  374.03  4351.4  371.56  4469.8  368.88  4482.9  369.48  4594.2  366.16
  4667.1  365.64  4689.9  363.32  4806.3  363.46  4812.8  362.63  4828.5  362.65
  4841.2  364.21  4871.4  362.11  4914.3  362.05  4970.1  363.55  4987.6  360.87
  4987.9  360.37  4992.0  360.87  5000.2  360.87  5021.0  363.88  5145.9  363.53
  5224.5  366.88  5458.1  368.42  5686.6  372.73  5714.5  373.43  6009.6  379.09
  6167.6  383.42  6217.7  386.17  6235.0  385.46  6252.3  386.13  6302.3  387.73
#Mann=7,-1,0
  4243.4   0.035       0  4351.4    0.07       0  4987.6    0.05       0
  4992.0    0.07       0  5686.6   0.063       0  5714.5    0.07       0
  6252.3   0.035       0
Bank Sta=4987.6,4992
Exp/Cntr=0.3,0.1

Type RM Length L Ch R = 1,4142,447,447,447
BEGIN DESCRIPTION:
Stream0447 5.0
END DESCRIPTION:
XS GIS Cut Line= 3
      2485851.85     13804641.89      2484825.00     13804075.00
      2483563.54     13803709.79
#Sta/Elev= 30
  3822.5  369.38  3844.1  368.49  3869.0  367.02  3885.1  369.07  3890.8  366.16
  3906.9  368.36  3912.6  365.34  3928.6  367.57  3934.3  364.87  3950.4  367.21
  3972.2  363.90  4020.8  363.79  4112.5  364.01  4140.4  364.57  4238.0  368.06
  4350.9  368.03  4360.5  367.80  4471.3  366.46  4582.1  365.05  4770.8  361.76
  4964.3  360.72  5003.6  359.03  5003.9  358.53  5008.0  359.03  5037.1  361.49
  5157.1  361.48  5942.8  370.13  6160.2  375.16  6265.6  380.39  6308.7  380.60
#Mann=15,-1,0
  3822.5    0.12       0  3844.1    0.07       0  4020.8    0.12       0
  4112.5    0.07       0  4140.4    0.12       0  4350.9    0.07       0
  4360.5    0.12       0  4471.3    0.07       0  4582.1    0.12       0
  4770.8    0.05       0  4964.3    0.12       0  5003.6    0.05       0
  5008.0    0.12       0  5157.1    0.07       0  6265.6   0.035       0
Bank Sta=5003.6,5008
Exp/Cntr=0.3,0.1

Type RM Length L Ch R = 1,3695,648,648,648
BEGIN DESCRIPTION:
Stream0447 4.0
END DESCRIPTION:
XS GIS Cut Line= 3
      2486011.85     13804690.56      2485075.00     13803775.00
      2483625.52     13803660.90
#Sta/Elev= 30
  3690.8  365.77  3699.6  365.24  3706.6  363.27  3734.9  362.43  3876.4  363.70
  3936.6  362.41  4138.0  362.11  4215.9  363.48  4336.0  361.66  4534.0  362.39
  4707.8  361.51  4788.6  362.00  4944.6  360.12  4979.5  357.21  4984.5  355.15
  4984.8  354.65  4988.9  355.15  5010.8  358.16  5071.0  357.44  5091.0  358.50
  5154.8  358.39  5268.9  358.05  5323.0  357.28  5351.8  358.90  5530.9  362.11
  5638.9  363.45  5901.1  365.12  6094.1  367.48  6285.6  372.66  6454.7  377.42
#Mann=12,-1,0
  3690.8    0.12       0  3936.6    0.07       0  4707.8    0.05       0
  4944.6    0.07       0  4984.5    0.05       0  4988.9    0.07       0
  5154.8    0.12       0  5268.9    0.07       0  5530.9    0.05       0
  5638.9    0.07       0  5901.1    0.05       0  6285.6    0.07       0
Bank Sta=4984.5,4988.9
Exp/Cntr=0.3,0.1

Type RM Length L Ch R = 1,3047,761,761,761
BEGIN DESCRIPTION:
XS6829
END DESCRIPTION:
XS GIS Cut Line= 3
      2485991.04     13804370.58      2485190.91     13803438.27
      2483841.16     13803264.33
#Sta/Elev= 30
  3297.7  361.85  3565.5  360.75  3667.6  359.42  3909.1  358.73  4355.7  359.59
  4447.9  358.08  4552.4  357.98  4562.5  357.05  4661.6  356.07  4814.6  356.24
  4854.9  355.32  4895.2  352.22  4935.6  354.47  4965.8  354.65  4986.6  353.75
  4993.8  352.13  4994.1  351.63  4998.2  352.13  5046.5  355.64  5066.6  354.89
  5100.2  356.55  5127.1  360.43  5177.5  361.70  5199.1  361.31  5328.8  359.33
  5348.9  360.07  5453.2  359.54  5686.5  363.97  5711.9  365.27  5887.2  367.37
#Mann=7,-1,0
  3297.7    0.05       0  3565.5    0.07       0  4661.6    0.12       0
  4993.8    0.05       0  4998.2    0.12       0  5100.2    0.07       0
  5199.1    0.05       0
Bank Sta=4993.8,4998.2
Exp/Cntr=0.3,0.1

Type RM Length L Ch R = 1,2286,661,661,661
BEGIN DESCRIPTION:
Stream0447 3.0
END DESCRIPTION:
XS GIS Cut Line= 3
      2486366.68     13803841.77      2485225.00     13803075.00
      2484024.98     13802674.99
#Sta/Elev= 30
  3618.4  359.50  3753.0  359.52  3796.3  358.22  4092.1  359.62  4338.1  359.68
  4459.3  358.40  4590.1  356.37  4611.1  352.81  4641.1  350.91  4677.1  355.77
  4713.8  356.49  4890.2  355.61  4971.2  352.91  4990.7  350.45  5014.8  349.60
  5033.6  346.84  5033.9  346.34  5038.1  346.84  5056.9  349.56  5078.0  350.52
  5099.1  349.58  5415.3  354.41  5468.0  352.56  5499.6  348.45  5510.2  350.16
  5552.3  350.13  5594.5  353.66  5742.4  356.48  6058.3  360.53  6258.6  365.90
#Mann=8,-1,0
  3618.4    0.05       0  3796.3    0.07       0  4459.3    0.12       0
  4713.8    0.07       0  4890.2    0.12       0  5033.6    0.05       0
  5038.1    0.12       0  5742.4    0.05       0
Bank Sta=5033.6,5038.1
Exp/Cntr=0.3,0.1

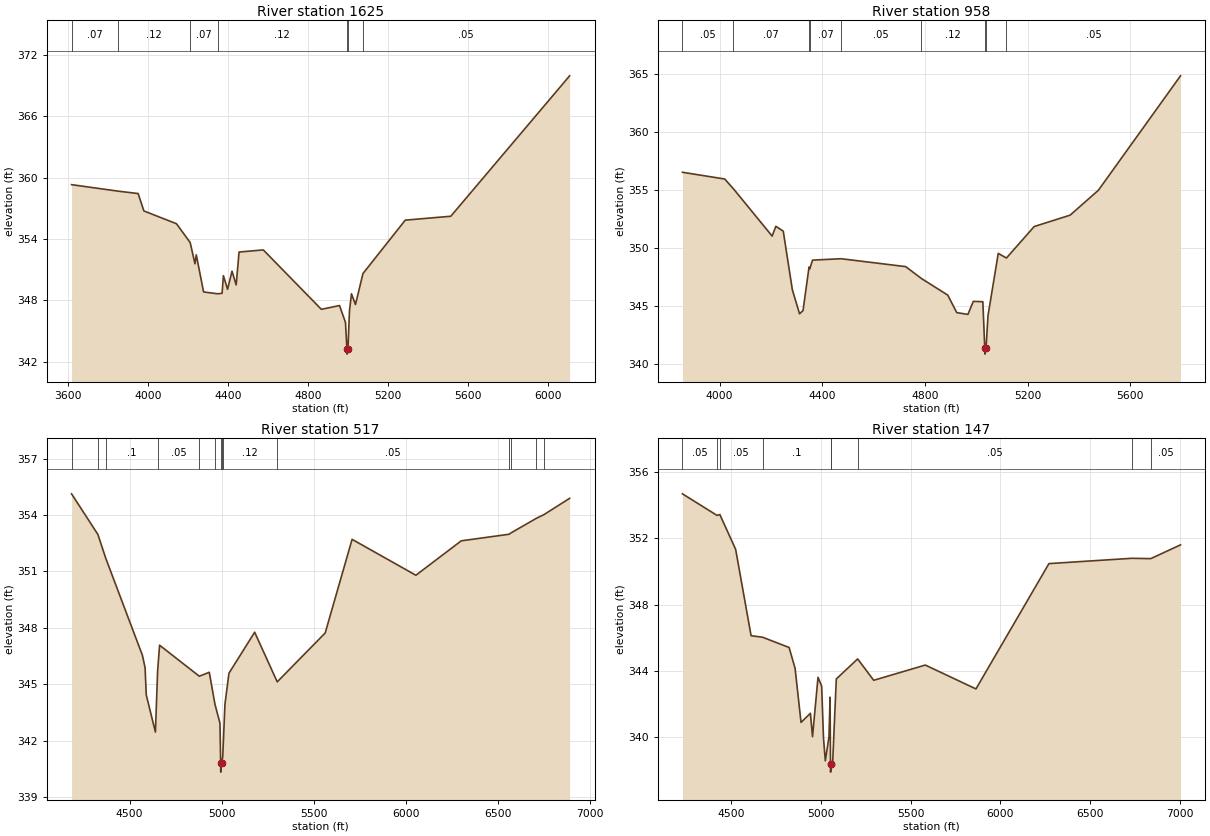
Type RM Length L Ch R = 1,1625,667,667,667
BEGIN DESCRIPTION:
XS6828
END DESCRIPTION:
XS GIS Cut Line= 3
      2486067.53     13803340.85      2485225.70     13802652.08
      2483828.59     13802526.97
#Sta/Elev= 30
  3618.1  359.31  3848.9  358.68  3951.0  358.44  3979.7  356.74  4142.6  355.49
  4211.2  353.65  4235.2  351.57  4241.7  352.45  4278.3  348.82  4349.0  348.64
  4370.8  348.69  4377.3  350.41  4398.2  349.08  4420.4  350.85  4441.2  349.51
  4455.6  352.72  4576.9  352.93  4867.1  347.12  4957.9  347.49  4987.6  345.85
  4995.2  343.24  4995.6  342.74  5000.1  343.24  5007.7  346.97  5017.7  348.64
  5037.8  347.59  5075.2  350.62  5286.7  355.84  5514.3  356.22  6108.5  369.95
#Mann=7,-1,0
  3618.1    0.07       0  3848.9    0.12       0  4211.2    0.07       0
  4349.0    0.12       0  4995.2    0.05       0  5000.1    0.12       0
  5075.2    0.05       0
Bank Sta=4995.2,5000.1
Exp/Cntr=0.3,0.1

Type RM Length L Ch R = 1,958,441,441,441
BEGIN DESCRIPTION:
Stream0447 2.0
END DESCRIPTION:
XS GIS Cut Line= 3
      2485825.01     13802825.01      2484925.00     13802125.00
      2484124.99     13802125.00
#Sta/Elev= 30
  3855.0  356.53  4019.7  355.95  4053.5  355.11  4204.3  351.04  4218.8  351.88
  4247.7  351.46  4283.0  346.43  4311.1  344.35  4324.7  344.63  4348.1  348.37
  4350.8  348.22  4361.8  348.97  4472.9  349.09  4724.6  348.41  4785.7  347.39
  4888.4  345.96  4923.7  344.45  4967.1  344.30  4988.0  345.42  5025.2  345.39
  5032.7  341.38  5033.1  340.88  5037.6  341.38  5045.2  344.18  5085.2  349.55
  5117.0  349.15  5225.2  351.86  5365.2  352.84  5475.2  354.98  5795.2  364.83
#Mann=9,-1,0
  3855.0    0.05       0  4053.5    0.07       0  4348.1     0.1       0
  4350.8    0.07       0  4472.9    0.05       0  4785.7    0.12       0
  5032.7    0.05       0  5037.6    0.12       0  5117.0    0.05       0
Bank Sta=5032.7,5037.6
Exp/Cntr=0.3,0.1

Type RM Length L Ch R = 1,517,370,370,370
BEGIN DESCRIPTION:
Stream0447 1.0
END DESCRIPTION:
XS GIS Cut Line= 3
      2485724.98     13802674.97      2485225.00     13802025.00
      2483625.02     13801025.01
#Sta/Elev= 30
  4184.5  355.13  4327.6  352.97  4370.8  351.69  4569.6  346.54  4584.1  345.88
  4590.4  344.44  4640.2  342.46  4652.2  345.71  4662.9  347.08  4878.6  345.43
  4932.9  345.64  4963.8  343.94  4991.0  342.93  4994.8  340.83  4995.2  340.33
  4999.7  340.83  5006.0  341.14  5018.1  343.94  5039.9  345.59  5179.6  347.77
  5302.2  345.13  5562.9  347.73  5709.1  352.71  6055.8  350.80  6302.3  352.63
  6562.1  352.98  6572.4  353.05  6711.1  353.83  6752.8  354.03  6891.3  354.89
#Mann=14,-1,0
  4184.5    0.05       0  4327.6    0.07       0  4370.8     0.1       0
  4652.2    0.05       0  4878.6    0.12       0  4963.8     0.1       0
  4994.8    0.05       0  4999.7     0.1       0  5006.0    0.12       0
  5302.2    0.05       0  6562.1   0.035       0  6572.4    0.05       0
  6711.1   0.035       0  6752.8    0.05       0
Bank Sta=4994.8,4999.7
Exp/Cntr=0.3,0.1

Type RM Length L Ch R = 1,147,0,0,0
BEGIN DESCRIPTION:
XS6827
END DESCRIPTION:
XS GIS Cut Line= 4
      2485810.14     13802707.78      2485566.61     13802130.28
      2485510.95     13801838.07      2483849.07     13801031.46
#Sta/Elev= 30
  4230.8  354.68  4422.9  353.38  4438.9  353.43  4526.8  351.33  4612.7  346.12
  4676.4  346.03  4824.2  345.41  4857.6  344.15  4890.6  340.89  4942.8  341.44
  4954.5  340.03  4985.1  343.61  5005.4  343.08  5015.6  339.95  5025.8  338.57
  5046.2  340.03  5052.2  342.41  5054.6  338.39  5055.0  337.89  5060.1  338.39
  5066.5  338.45  5086.9  343.51  5205.7  344.72  5295.0  343.43  5582.1  344.35
  5864.0  342.91  6270.2  350.47  6730.5  350.79  6836.7  350.77  7002.3  351.60
#Mann=9,-1,0
  4230.8    0.05       0  4422.9    0.07       0  4438.9    0.05       0
  4676.4     0.1       0  5054.6    0.05       0  5060.1     0.1       0
  5205.7    0.05       0  6730.5   0.035       0  6836.7    0.05       0
Bank Sta=5054.6,5060.1
Exp/Cntr=0.3,0.1

Chan Stop Cuts=-1