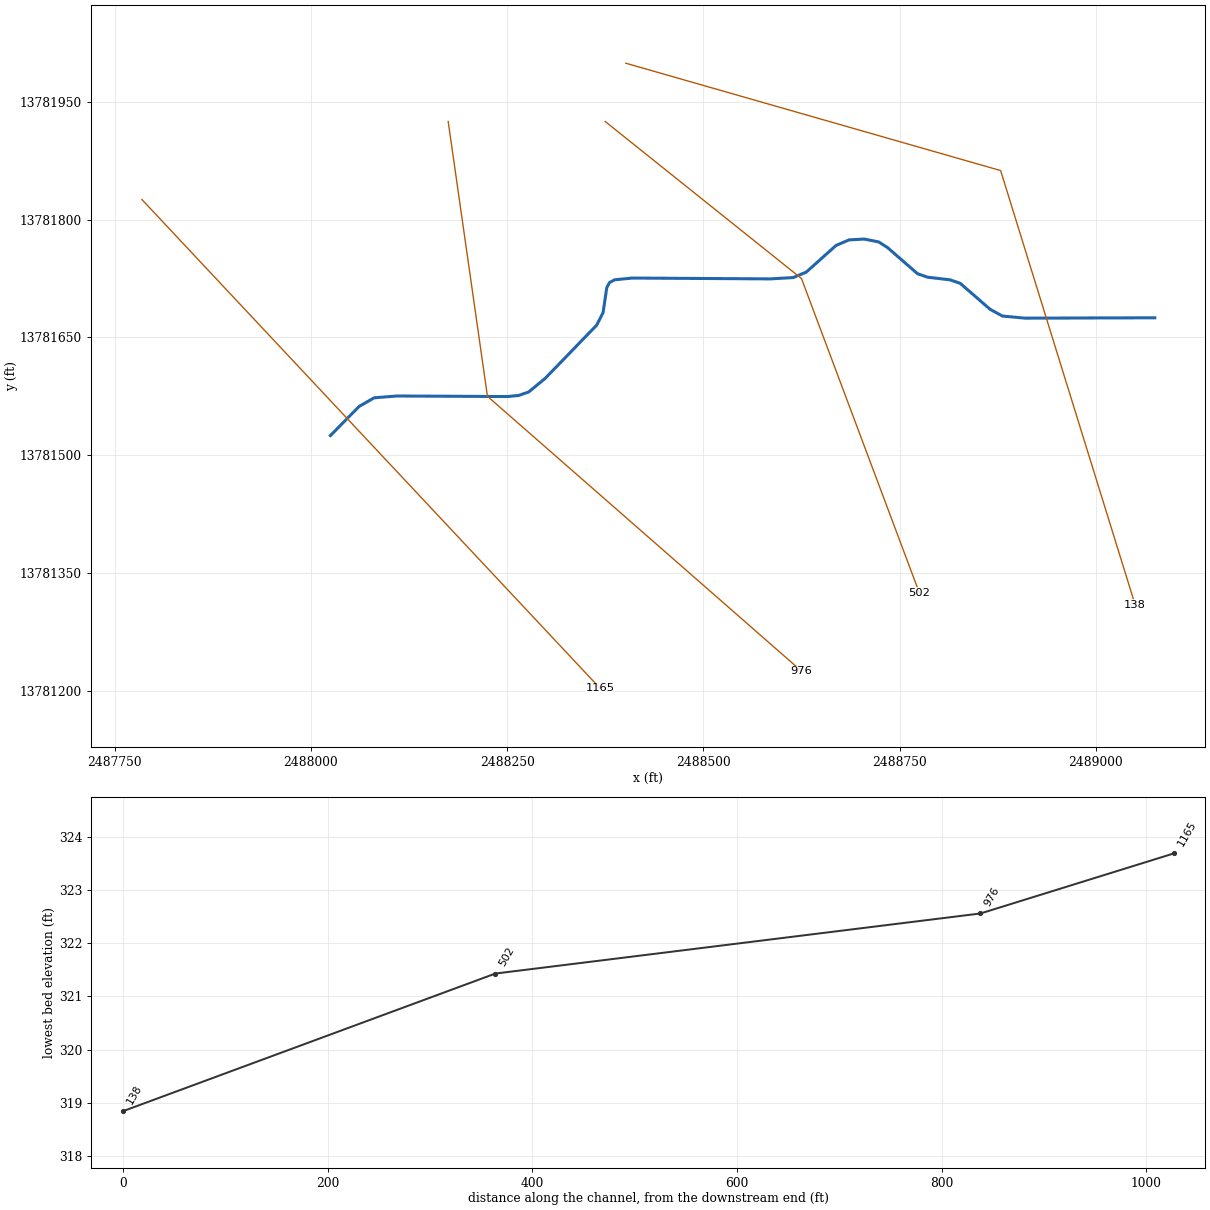
--- Stream0453.prj (project) ---

Proj Title=Stream0453 Base Level Engineering
Current Plan=p01
Default Exp/Contr=0.3,0.1
English Units
Geom File=g01
Flow File=f01
Plan File=p01
BEGIN DESCRIPTION:
Stream0453
END DESCRIPTION:

--- Stream0453.p01 (plan) ---

Plan Title=Multiple Run
Short Identifier=Multiple
Geom File=g01
Flow File=f01
Subcritical Flow
K Sum by GR= 0
Std Step Tol= 0.01
Critical Tol= 0.01
Num of Std Step Trials= 20
Max Error Tol= 0.3
Flow Tol Ratio= 0.001
Split Flow NTrial= 30
Split Flow Tol= 0.02
Split Flow Ratio= 0.02
Log Output Level= 0
Friction Slope Method= 1
Unsteady Friction Slope Method= 2
Unsteady Bridges Friction Slope Method= 1
Parabolic Critical Depth
Global Vel Dist=  1 , 1 , 1
Global Log Level= 0
CheckData=True
Encroach Param= -1, 0, 0, 0
BEGIN DESCRIPTION:
Multiple Run
END DESCRIPTION:

--- Stream0453.f01 (steady flow) ---

Flow Title=Multiple
Number of Profiles=7
Profile Names=10-year,25-year,50-year,1pct_min,100-year,1pct_plu,500-year
River Rch & RM= Stream0453,Reach-1,1165
     743    1202    1619    1055    2106    4202    3527
Boundary for River Rch & Prof#=Stream0453,Reach-1,1
Up Type=0
Dn Type=3
Dn Slope=0.005
Boundary for River Rch & Prof#=Stream0453,Reach-1,2
Up Type=0
Dn Type=3
Dn Slope=0.005
Boundary for River Rch & Prof#=Stream0453,Reach-1,3
Up Type=0
Dn Type=3
Dn Slope=0.005
Boundary for River Rch & Prof#=Stream0453,Reach-1,4
Up Type=0
Dn Type=3
Dn Slope=0.005
Boundary for River Rch & Prof#=Stream0453,Reach-1,5
Up Type=0
Dn Type=3
Dn Slope=0.005
Boundary for River Rch & Prof#=Stream0453,Reach-1,6
Up Type=0
Dn Type=3
Dn Slope=0.005
Boundary for River Rch & Prof#=Stream0453,Reach-1,7
Up Type=0
Dn Type=3
Dn Slope=0.005

--- Stream0453.g01 (geometry) ---

Geom Title=Existing Conditions

River Reach=Stream0453,Reach-1
Reach XY= 30
      2488025.00     13781525.00      2488061.50     13781562.08
      2488080.78     13781573.11      2488109.83     13781575.41
      2488250.13     13781574.70      2488264.57     13781576.05
      2488277.47     13781580.46      2488298.58     13781597.84
      2488364.10     13781665.60      2488372.27     13781681.52
      2488376.98     13781713.31      2488380.44     13781719.82
      2488386.83     13781723.38      2488409.45     13781725.63
      2488585.19     13781724.55      2488614.50     13781726.24
      2488631.08     13781733.19      2488669.08     13781767.19
      2488685.69     13781774.24      2488704.83     13781775.29
      2488723.28     13781771.66      2488734.55     13781764.49
      2488772.80     13781731.15      2488785.68     13781726.69
      2488814.31     13781723.34      2488827.18     13781718.89
      2488865.33     13781685.79      2488880.92     13781677.23
      2488909.81     13781674.55      2489075.00     13781675.00

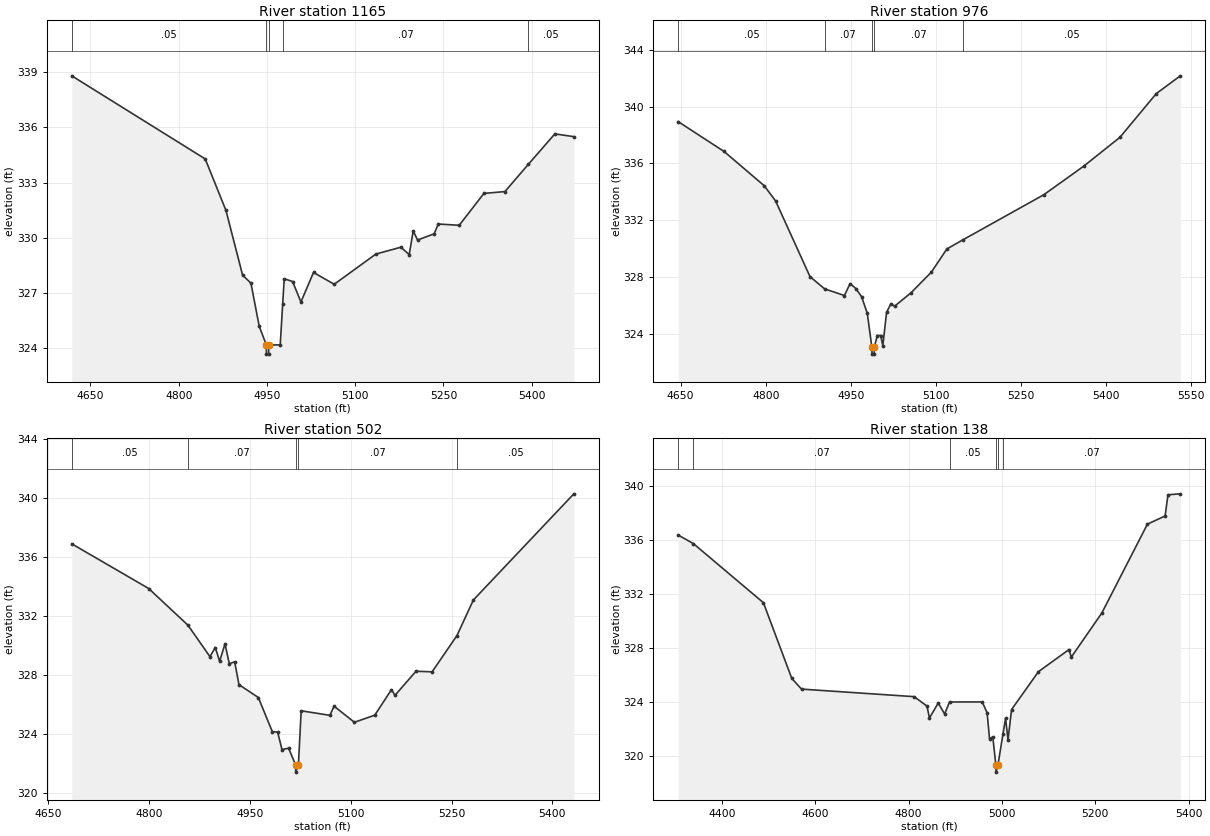
Type RM Length L Ch R = 1,1165,189,189,189
BEGIN DESCRIPTION:
XS6840
END DESCRIPTION:
XS GIS Cut Line= 2
      2487784.92     13781825.63      2488368.66     13781202.83
#Sta/Elev= 30
  4618.2  338.79  4845.1  334.28  4880.3  331.49  4908.6  327.98  4922.8  327.54
  4936.9  325.20  4949.0  324.19  4949.2  323.69  4952.9  323.69  4953.2  324.19
  4972.6  324.19  4976.8  326.41  4979.4  327.78  4993.6  327.63  5007.8  326.52
  5029.2  328.12  5064.4  327.48  5135.2  329.12  5177.7  329.49  5191.9  329.09
  5198.7  330.38  5206.1  329.88  5234.4  330.22  5241.2  330.75  5276.9  330.68
  5318.9  332.41  5354.6  332.51  5394.5  333.99  5439.5  335.64  5471.8  335.49
#Mann=5,-1,0
  4618.2    0.05       0  4949.0    0.05       0  4953.2    0.05       0
  4976.8    0.07       0  5394.5    0.05       0
Bank Sta=4949,4953.2
Exp/Cntr=0.3,0.1

Type RM Length L Ch R = 1,976,474,474,474
BEGIN DESCRIPTION:
Stream0453 2.0
END DESCRIPTION:
XS GIS Cut Line= 3
      2488175.00     13781924.99      2488225.00     13781575.00
      2488625.04     13781224.97
#Sta/Elev= 30
  4645.8  338.94  4726.6  336.84  4797.3  334.43  4817.5  333.35  4878.1  328.02
  4903.8  327.16  4938.7  326.69  4948.8  327.53  4958.9  327.18  4969.0  326.61
  4979.1  325.43  4987.1  323.06  4987.4  322.56  4991.1  322.56  4991.4  323.06
  4996.8  323.87  5002.7  323.87  5006.5  323.16  5013.1  325.51  5020.7  326.11
  5027.3  325.94  5055.8  326.87  5091.9  328.33  5119.4  329.97  5147.9  330.62
  5290.2  333.79  5360.5  335.80  5424.5  337.84  5488.6  340.92  5530.9  342.17
#Mann=5,-1,0
  4645.8    0.05       0  4903.8    0.07       0  4987.1    0.05       0
  4991.4    0.07       0  5147.9    0.05       0
Bank Sta=4987.1,4991.4
Exp/Cntr=0.3,0.1

Type RM Length L Ch R = 1,502,364,364,364
BEGIN DESCRIPTION:
Stream0453 1.0
END DESCRIPTION:
XS GIS Cut Line= 3
      2488375.00     13781925.00      2488625.00     13781725.00
      2488775.02     13781324.96
#Sta/Elev= 30
  4684.7  336.91  4799.2  333.88  4857.7  331.39  4890.4  329.26  4898.4  329.88
  4904.8  328.94  4912.8  330.13  4919.2  328.78  4927.2  328.91  4933.6  327.36
  4962.4  326.49  4983.2  324.18  4991.2  324.14  4997.6  322.96  5007.5  323.05
  5017.8  321.93  5018.1  321.43  5022.1  321.93  5026.2  325.59  5068.9  325.28
  5075.2  325.90  5105.4  324.81  5135.7  325.29  5160.6  327.02  5165.9  326.64
  5197.1  328.27  5221.1  328.23  5258.1  330.69  5282.5  333.10  5432.1  340.30
#Mann=5,-1,0
  4684.7    0.05       0  4857.7    0.07       0  5017.8    0.05       0
  5022.1    0.07       0  5258.1    0.05       0
Bank Sta=5017.8,5022.1
Exp/Cntr=0.3,0.1

Type RM Length L Ch R = 1,138,0,0,0
BEGIN DESCRIPTION:
XS6839
END DESCRIPTION:
XS GIS Cut Line= 3
      2488401.24     13781999.26      2488878.65     13781862.54
      2489049.90     13781309.76
#Sta/Elev= 30
  4306.7  336.37  4339.1  335.74  4489.1  331.37  4549.9  325.77  4570.7  324.98
  4812.1  324.42  4839.5  323.72  4844.7  322.84  4863.5  323.95  4877.3  323.14
  4887.8  324.03  4957.8  324.03  4968.2  323.23  4973.5  321.29  4980.4  321.45
  4987.0  319.34  4987.3  318.84  4991.3  319.34  5002.3  321.68  5007.7  322.82
  5013.0  321.23  5020.6  323.47  5078.2  326.27  5143.4  327.90  5148.6  327.35
  5213.8  330.60  5311.6  337.18  5349.4  337.78  5355.6  339.35  5382.0  339.42
#Mann=6,-1,0
  4306.7    0.05       0  4339.1    0.07       0  4887.8    0.05       0
  4987.0    0.05       0  4991.3    0.05       0  5002.3    0.07       0
Bank Sta=4987,4991.3
Exp/Cntr=0.3,0.1

Chan Stop Cuts=-1