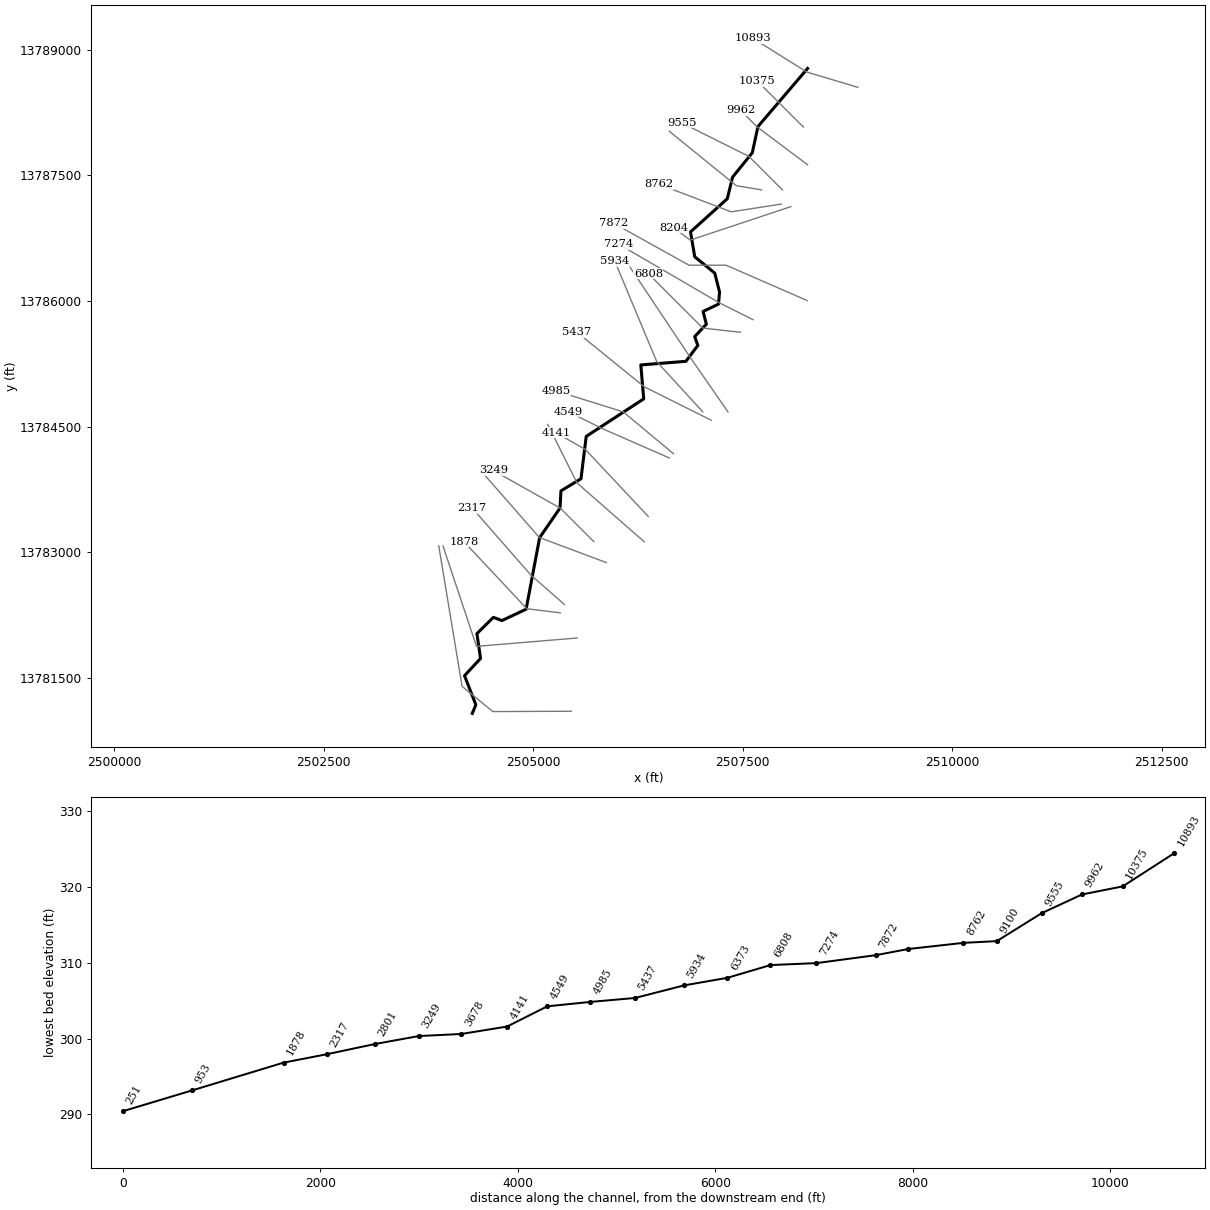
--- Stream0457.prj (project) ---

Proj Title=Stream0457 Base Level Engineering
Current Plan=p01
Default Exp/Contr=0.3,0.1
English Units
Geom File=g01
Flow File=f01
Plan File=p01
BEGIN DESCRIPTION:
Stream0457
END DESCRIPTION:

--- Stream0457.p01 (plan) ---

Plan Title=Multiple Run
Short Identifier=Multiple
Geom File=g01
Flow File=f01
Subcritical Flow
K Sum by GR= 0
Std Step Tol= 0.01
Critical Tol= 0.01
Num of Std Step Trials= 20
Max Error Tol= 0.3
Flow Tol Ratio= 0.001
Split Flow NTrial= 30
Split Flow Tol= 0.02
Split Flow Ratio= 0.02
Log Output Level= 0
Friction Slope Method= 1
Unsteady Friction Slope Method= 2
Unsteady Bridges Friction Slope Method= 1
Parabolic Critical Depth
Global Vel Dist=  1 , 1 , 1
Global Log Level= 0
CheckData=True
Encroach Param= -1, 0, 0, 0
BEGIN DESCRIPTION:
Multiple Run
END DESCRIPTION:

--- Stream0457.f01 (steady flow) ---

Flow Title=Multiple
Number of Profiles=7
Profile Names=10-year,25-year,50-year,1pct_min,100-year,1pct_plu,500-year
River Rch & RM= Stream0457,Reach-1,10893
     734    1182    1586    1030    2055    4100    3416
River Rch & RM= Stream0457,Reach-1,9555
     975    1578    2124    1382    2757    5501    4599
Boundary for River Rch & Prof#=Stream0457,Reach-1,1
Up Type=0
Dn Type=3
Dn Slope=0.005
Boundary for River Rch & Prof#=Stream0457,Reach-1,2
Up Type=0
Dn Type=3
Dn Slope=0.005
Boundary for River Rch & Prof#=Stream0457,Reach-1,3
Up Type=0
Dn Type=3
Dn Slope=0.005
Boundary for River Rch & Prof#=Stream0457,Reach-1,4
Up Type=0
Dn Type=3
Dn Slope=0.005
Boundary for River Rch & Prof#=Stream0457,Reach-1,5
Up Type=0
Dn Type=3
Dn Slope=0.005
Boundary for River Rch & Prof#=Stream0457,Reach-1,6
Up Type=0
Dn Type=3
Dn Slope=0.005
Boundary for River Rch & Prof#=Stream0457,Reach-1,7
Up Type=0
Dn Type=3
Dn Slope=0.005

--- Stream0457.g01 (geometry) ---

Geom Title=Existing Conditions

River Reach=Stream0457,Reach-1
Reach XY= 30
      2508275.00     13788775.00      2507683.07     13788081.32
      2507615.42     13787768.45      2507380.00     13787476.98
      2507316.84     13787218.95      2506878.37     13786823.72
      2506928.76     13786526.56      2507167.32     13786331.52
      2507224.95     13786104.96      2507211.80     13785961.27
      2507028.36     13785873.75      2507067.20     13785721.58
      2506928.16     13785573.35      2506965.83     13785468.28
      2506823.75     13785278.45      2506285.32     13785235.18
      2506319.97     13784830.08      2505634.16     13784382.00
      2505571.63     13783876.28      2505332.69     13783731.48
      2505321.45     13783526.47      2505078.54     13783173.54
      2504917.02     13782318.62      2504628.40     13782182.84
      2504526.65     13782221.84      2504330.11     13782027.29
      2504373.38     13781731.04      2504182.29     13781525.09
      2504317.10     13781178.26      2504275.00     13781075.00

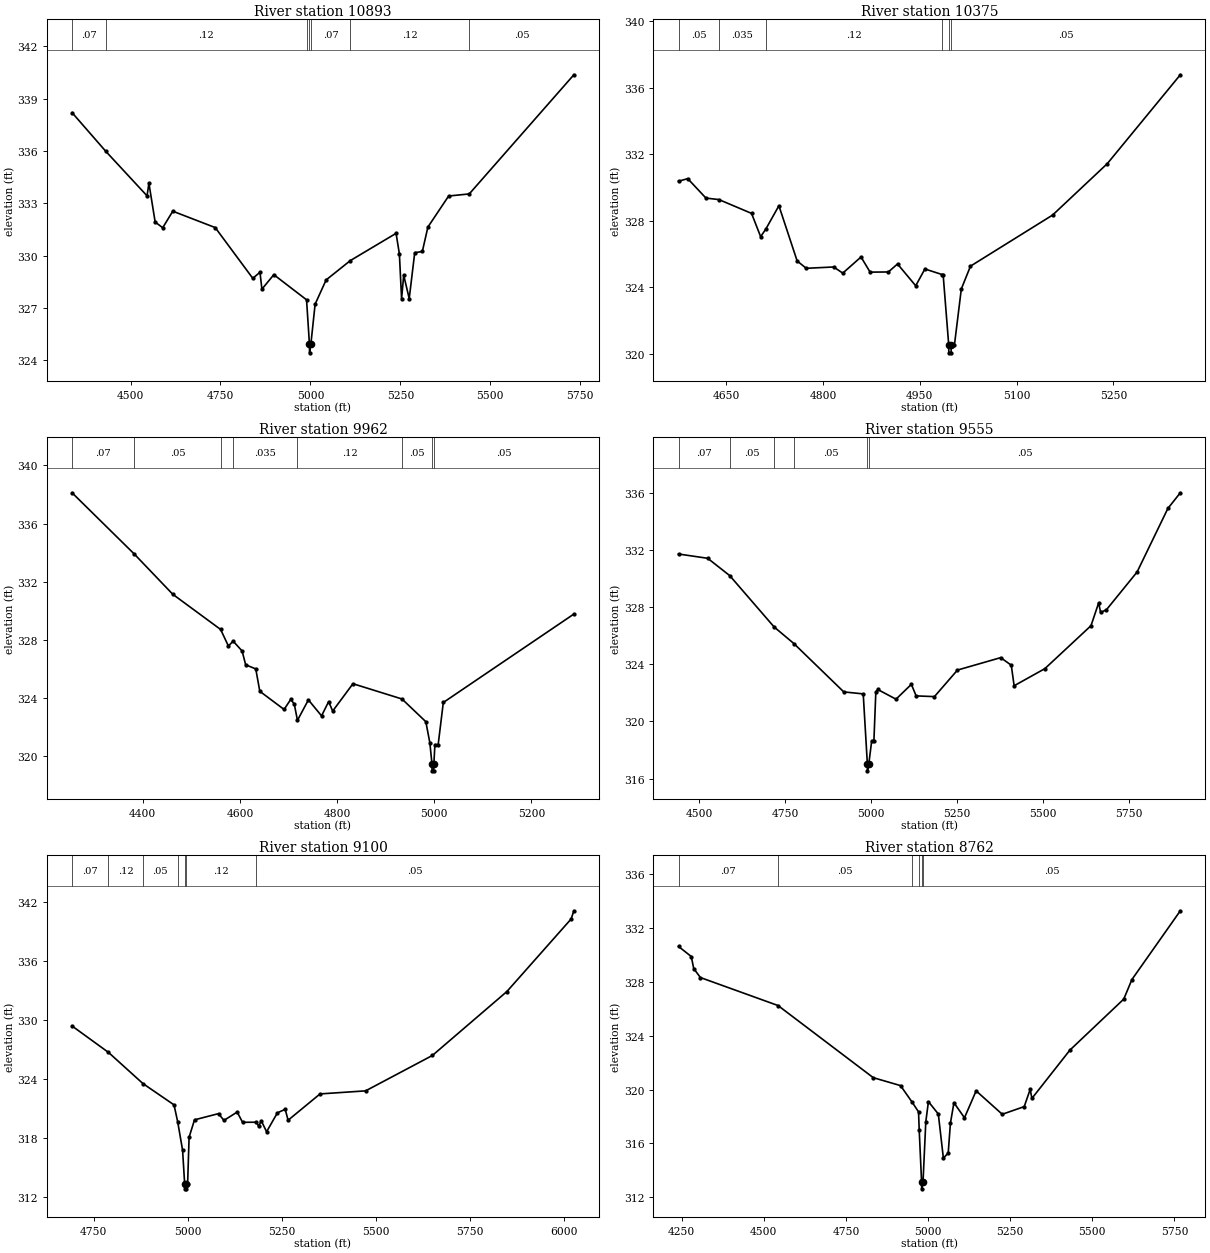
Type RM Length L Ch R = 1,10893,518,518,518
BEGIN DESCRIPTION:
Stream0457 20.0
END DESCRIPTION:
XS GIS Cut Line= 3
      2508876.30     13788549.44      2508266.34     13788731.36
      2507624.29     13789134.43
#Sta/Elev= 30
  4337.6  338.19  4431.4  335.97  4546.0  333.42  4551.2  334.14  4568.5  331.92
  4589.5  331.59  4617.5  332.54  4735.5  331.60  4839.9  328.69  4859.9  329.04
  4865.2  328.07  4898.3  328.90  4989.3  327.46  4997.3  324.92  4997.6  324.42
  5001.3  324.92  5013.1  327.21  5043.7  328.60  5111.1  329.71  5238.1  331.27
  5247.3  330.09  5253.4  327.52  5259.3  328.87  5274.6  327.53  5289.9  330.16
  5311.1  330.23  5326.5  331.63  5384.2  333.41  5441.5  333.53  5732.2  340.36
#Mann=7,-1,0
  4337.6    0.07       0  4431.4    0.12       0  4989.3    0.07       0
  4997.3    0.05       0  5001.3    0.07       0  5111.1    0.12       0
  5441.5    0.05       0
Bank Sta=4997.3,5001.3
Exp/Cntr=0.3,0.1

Type RM Length L Ch R = 1,10375,413,413,413
BEGIN DESCRIPTION:
Stream0457 19.0
END DESCRIPTION:
XS GIS Cut Line= 3
      2508225.03     13788074.97      2507925.00     13788375.00
      2507674.97     13788625.03
#Sta/Elev= 30
  4575.9  330.38  4590.1  330.54  4618.4  329.37  4638.5  329.28  4689.1  328.45
  4703.2  327.05  4711.4  327.52  4731.5  328.91  4759.8  325.59  4773.9  325.15
  4816.4  325.23  4830.5  324.86  4858.8  325.83  4872.9  324.92  4901.2  324.93
  4915.4  325.41  4943.6  324.10  4957.8  325.11  4984.9  324.77  4986.1  324.77
  4994.7  320.57  4994.9  320.07  4998.4  320.07  4998.7  320.57  5003.7  320.57
  5014.3  323.91  5028.5  325.28  5155.8  328.35  5240.6  331.44  5353.8  336.78
#Mann=6,-1,0
  4575.9    0.05       0  4638.5   0.035       0  4711.4    0.12       0
  4984.9    0.05       0  4994.7    0.05       0  4998.7    0.05       0
Bank Sta=4994.7,4998.7
Exp/Cntr=0.3,0.1

Type RM Length L Ch R = 1,9962,407,407,407
BEGIN DESCRIPTION:
Stream0457 18.0
END DESCRIPTION:
XS GIS Cut Line= 3
      2508274.98     13787625.02      2507675.00     13788075.00
      2507475.01     13788274.99
#Sta/Elev= 30
  4254.4  338.12  4382.4  333.91  4461.7  331.14  4560.2  328.72  4576.2  327.58
  4585.9  327.92  4604.4  327.24  4611.7  326.29  4632.5  326.01  4640.8  324.47
  4690.8  323.22  4704.4  323.91  4711.7  323.60  4718.3  322.47  4740.8  323.88
  4767.9  322.78  4782.5  323.76  4790.8  323.11  4832.5  324.99  4933.5  323.94
  4982.5  322.38  4990.8  320.93  4995.1  319.50  4995.3  319.00  4998.8  319.00
  4999.1  319.50  5001.2  320.80  5007.9  320.80  5018.5  323.70  5287.2  329.78
#Mann=8,-1,0
  4254.4    0.07       0  4382.4    0.05       0  4560.2    0.12       0
  4585.9   0.035       0  4718.3    0.12       0  4933.5    0.05       0
  4995.1    0.05       0  4999.1    0.05       0
Bank Sta=4995.1,4999.1
Exp/Cntr=0.3,0.1

Type RM Length L Ch R = 1,9555,455,455,455
BEGIN DESCRIPTION:
Stream0457 17.0
END DESCRIPTION:
XS GIS Cut Line= 3
      2507974.99     13787325.01      2507575.00     13787725.00
      2506775.00     13788125.00
#Sta/Elev= 30
  4439.6  331.73  4524.4  331.43  4588.4  330.22  4717.7  326.62  4775.1  325.46
  4920.4  322.07  4977.0  321.93  4989.0  317.04  4989.3  316.54  4993.3  317.04
  5001.7  318.65  5008.1  318.65  5013.7  322.07  5019.2  322.24  5072.4  321.56
  5117.1  322.60  5131.0  321.79  5184.2  321.74  5251.2  323.60  5377.0  324.47
  5407.8  323.94  5416.1  322.50  5505.6  323.70  5639.8  326.71  5662.1  328.31
  5667.7  327.64  5684.5  327.82  5773.9  330.47  5863.4  334.92  5899.7  336.02
#Mann=6,-1,0
  4439.6    0.07       0  4588.4    0.05       0  4717.7    0.07       0
  4775.1    0.05       0  4989.0    0.05       0  4993.3    0.05       0
Bank Sta=4989,4993.3
Exp/Cntr=0.3,0.1

Type RM Length L Ch R = 1,9100,338,338,338
BEGIN DESCRIPTION:
Stream0457 16.0
END DESCRIPTION:
XS GIS Cut Line= 3
      2507725.01     13787325.00      2507425.00     13787375.00
      2506625.02     13788024.99
#Sta/Elev= 30
  4692.1  329.37  4789.0  326.69  4880.6  323.53  4963.3  321.37  4973.1  319.65
  4986.1  316.77  4991.6  313.35  4991.9  312.85  4995.6  312.85  4995.9  313.35
  4999.5  313.35  5003.4  318.08  5017.8  319.85  5081.7  320.48  5096.1  319.79
  5131.3  320.64  5145.7  319.60  5182.4  319.61  5188.8  319.19  5195.2  319.77
  5209.6  318.64  5238.3  320.56  5259.1  320.92  5266.8  319.81  5351.8  322.48
  5473.0  322.79  5650.6  326.38  5848.9  332.87  6019.8  340.23  6027.0  341.06
#Mann=7,-1,0
  4692.1    0.07       0  4789.0    0.12       0  4880.6    0.05       0
  4973.1    0.12       0  4991.6    0.05       0  4995.9    0.12       0
  5182.4    0.05       0
Bank Sta=4991.6,4995.9
Exp/Cntr=0.3,0.1

Type RM Length L Ch R = 1,8762,558,558,558
BEGIN DESCRIPTION:
E21053
END DESCRIPTION:
XS GIS Cut Line= 3
      2507960.69     13787155.57      2507364.49     13787063.06
      2506501.06     13787391.98
#Sta/Elev= 30
  4240.6  330.63  4279.4  329.88  4286.8  328.99  4307.1  328.32  4543.4  326.24
  4833.3  320.88  4916.3  320.29  4951.0  319.08  4971.1  318.34  4973.1  317.01
  4980.4  313.12  4980.6  312.62  4984.7  313.12  4993.2  317.60  5001.2  319.10
  5031.3  318.18  5046.7  314.90  5061.4  315.28  5068.1  317.49  5078.8  319.02
  5110.9  317.90  5146.4  319.90  5225.9  318.16  5292.8  318.73  5310.9  320.01
  5316.2  319.34  5431.9  322.93  5595.8  326.72  5620.5  328.17  5767.9  333.28
#Mann=6,-1,0
  4240.6    0.07       0  4543.4    0.05       0  4951.0    0.12       0
  4973.1    0.05       0  4980.4    0.05       0  4984.7    0.05       0
Bank Sta=4980.4,4984.7
Exp/Cntr=0.3,0.1

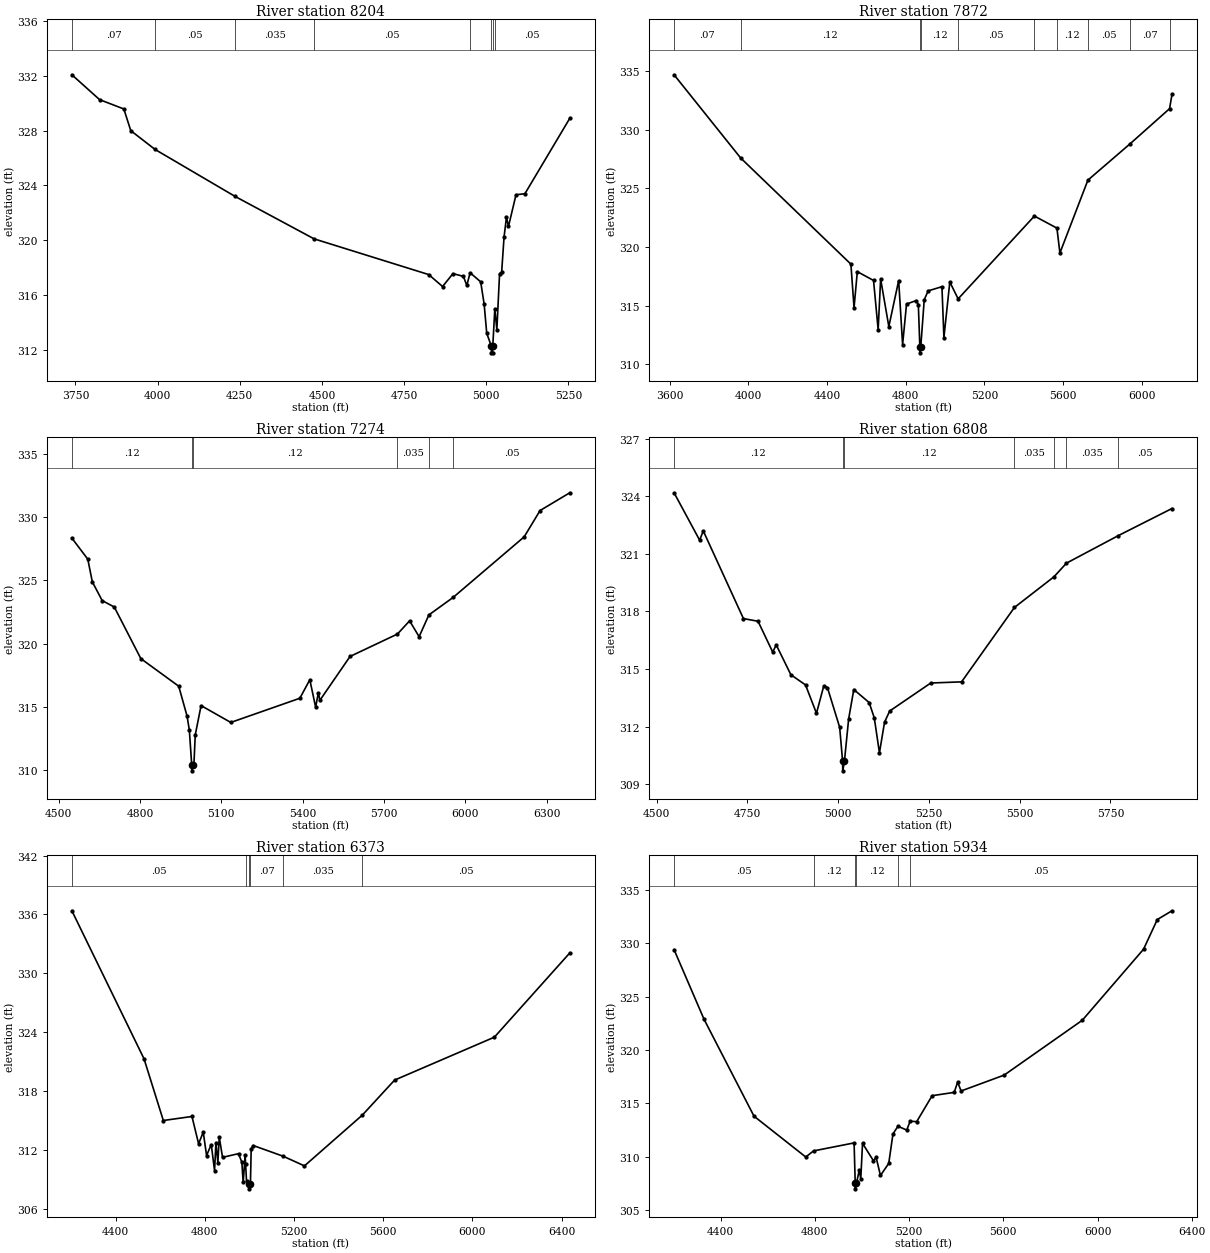
Type RM Length L Ch R = 1,8204,332,332,332
BEGIN DESCRIPTION:
Stream0457 15.0
END DESCRIPTION:
XS GIS Cut Line= 3
      2508074.96     13787124.99      2506875.00     13786725.00
      2506674.98     13786875.02
#Sta/Elev= 30
  3739.2  332.06  3823.5  330.25  3897.3  329.57  3918.4  327.99  3992.4  326.62
  4235.9  323.20  4476.2  320.11  4824.9  317.51  4867.0  316.64  4898.7  317.58
  4930.3  317.38  4940.8  316.72  4950.9  317.64  4983.0  316.98  4993.5  315.37
  5001.4  313.23  5015.4  312.31  5015.7  311.81  5019.5  311.81  5019.8  312.31
  5026.0  315.00  5032.2  313.50  5040.5  317.58  5046.8  317.68  5054.1  320.24
  5061.4  321.68  5067.6  321.02  5090.5  323.32  5117.6  323.40  5254.1  328.89
#Mann=8,-1,0
  3739.2    0.07       0  3992.4    0.05       0  4235.9   0.035       0
  4476.2    0.05       0  4950.9    0.12       0  5015.4    0.05       0
  5019.8    0.12       0  5026.0    0.05       0
Bank Sta=5015.4,5019.8
Exp/Cntr=0.3,0.1

Type RM Length L Ch R = 1,7872,598,598,598
BEGIN DESCRIPTION:
E21052
END DESCRIPTION:
XS GIS Cut Line= 4
      2508269.03     13786004.31      2507302.81     13786425.75
      2506860.81     13786425.75      2505956.22     13786929.44
#Sta/Elev= 30
  3622.2  334.69  3960.6  327.60  4521.2  318.55  4537.2  314.84  4553.9  317.91
  4636.3  317.16  4659.8  312.97  4672.4  317.28  4714.1  313.23  4764.1  317.15
  4784.1  311.70  4804.1  315.15  4854.1  315.45  4864.1  315.09  4871.8  311.49
  4872.1  310.99  4876.4  311.49  4894.1  315.52  4914.1  316.27  4984.1  316.63
  4994.1  312.29  5024.1  317.03  5066.4  315.59  5454.2  322.65  5568.7  321.62
  5583.9  319.50  5726.2  325.71  5939.6  328.79  6141.3  331.80  6153.7  333.01
#Mann=10,-1,0
  3622.2    0.07       0  3960.6    0.12       0  4871.8    0.05       0
  4876.4    0.12       0  5066.4    0.05       0  5454.2   0.035       0
  5568.7    0.12       0  5726.2    0.05       0  5939.6    0.07       0
  6141.3    0.05       0
Bank Sta=4871.8,4876.4
Exp/Cntr=0.3,0.1

Type RM Length L Ch R = 1,7274,466,466,466
BEGIN DESCRIPTION:
Stream0457 14.0
END DESCRIPTION:
XS GIS Cut Line= 3
      2507624.97     13785775.01      2507225.00     13785975.00
      2506025.02     13786674.99
#Sta/Elev= 30
  4549.1  328.32  4607.8  326.66  4624.5  324.87  4660.9  323.39  4705.6  322.88
  4803.4  318.81  4943.2  316.63  4973.9  314.27  4982.3  313.18  4991.0  310.45
  4991.4  309.95  4996.0  310.45  4999.2  310.45  5004.1  312.78  5025.6  315.10
  5135.2  313.77  5389.9  315.68  5426.7  317.14  5448.2  314.97  5458.1  316.11
  5463.9  315.52  5575.1  318.98  5750.0  320.75  5794.7  321.79  5829.8  320.54
  5865.9  322.26  5955.3  323.64  6217.2  328.42  6276.0  330.50  6385.5  331.90
#Mann=6,-1,0
  4549.1    0.12       0  4991.0    0.05       0  4996.0    0.12       0
  5750.0   0.035       0  5865.9    0.12       0  5955.3    0.05       0
Bank Sta=4991,4996
Exp/Cntr=0.3,0.1

Type RM Length L Ch R = 1,6808,435,435,435
BEGIN DESCRIPTION:
Stream0457 13.0
END DESCRIPTION:
XS GIS Cut Line= 3
      2507474.98     13785625.00      2507025.00     13785675.00
      2506374.99     13786325.01
#Sta/Elev= 30
  4547.7  324.19  4618.1  321.72  4628.2  322.20  4738.8  317.63  4779.1  317.49
  4819.3  315.89  4829.4  316.25  4869.6  314.70  4909.9  314.17  4940.1  312.69
  4960.2  314.12  4970.3  314.03  5004.0  311.96  5012.1  310.19  5012.5  309.69
  5017.1  310.19  5028.7  312.39  5042.9  313.93  5085.3  313.25  5099.4  312.45
  5113.6  310.63  5127.7  312.23  5141.9  312.81  5255.0  314.27  5339.9  314.33
  5485.6  318.21  5594.6  319.81  5628.9  320.52  5772.2  321.96  5919.7  323.37
#Mann=7,-1,0
  4547.7    0.12       0  5012.1    0.05       0  5017.1    0.12       0
  5485.6   0.035       0  5594.6    0.12       0  5628.9   0.035       0
  5772.2    0.05       0
Bank Sta=5012.1,5017.1
Exp/Cntr=0.3,0.1

Type RM Length L Ch R = 1,6373,439,439,439
BEGIN DESCRIPTION:
Stream0457 12.0
END DESCRIPTION:
XS GIS Cut Line= 3
      2507324.98     13784675.02      2506875.00     13785325.00
      2506074.98     13786525.03
#Sta/Elev= 30
  4204.2  336.37  4527.8  321.27  4614.3  314.98  4742.7  315.39  4772.4  312.61
  4793.4  313.79  4808.2  311.41  4829.2  312.53  4844.1  309.87  4850.1  312.73
  4858.9  310.68  4865.0  313.29  4879.9  311.22  4951.5  311.60  4966.4  310.72
  4972.4  308.66  4981.2  311.43  4983.3  310.53  4987.3  308.83  4999.6  308.51
  5000.0  308.01  5004.9  308.51  5008.3  312.08  5017.3  312.43  5152.4  311.33
  5247.1  310.35  5506.7  315.53  5651.3  319.10  6098.9  323.48  6437.0  332.07
#Mann=6,-1,0
  4204.2    0.05       0  4983.3    0.07       0  4999.6    0.05       0
  5004.9    0.07       0  5152.4   0.035       0  5506.7    0.05       0
Bank Sta=4999.6,5004.9
Exp/Cntr=0.3,0.1

Type RM Length L Ch R = 1,5934,497,497,497
BEGIN DESCRIPTION:
Stream0457 11.0
END DESCRIPTION:
XS GIS Cut Line= 3
      2507025.00     13784675.00      2506475.00     13785275.00
      2505975.02     13786474.96
#Sta/Elev= 30
  4202.3  329.40  4329.6  322.88  4541.7  313.81  4761.3  309.99  4794.4  310.56
  4966.6  311.31  4971.4  307.51  4971.8  307.01  4976.7  307.51  4988.2  308.74
  4995.0  307.97  5002.4  311.27  5048.7  309.64  5060.1  309.96  5078.5  308.26
  5113.7  309.39  5131.6  312.15  5152.8  312.87  5190.1  312.51  5204.5  313.34
  5232.4  313.30  5297.9  315.73  5391.6  316.04  5406.2  317.00  5420.9  316.17
  5603.9  317.66  5935.4  322.79  6195.4  329.44  6253.9  332.22  6316.2  333.04
#Mann=6,-1,0
  4202.3    0.05       0  4794.4    0.12       0  4971.4    0.05       0
  4976.7    0.12       0  5152.8   0.035       0  5204.5    0.05       0
Bank Sta=4971.4,4976.7
Exp/Cntr=0.3,0.1

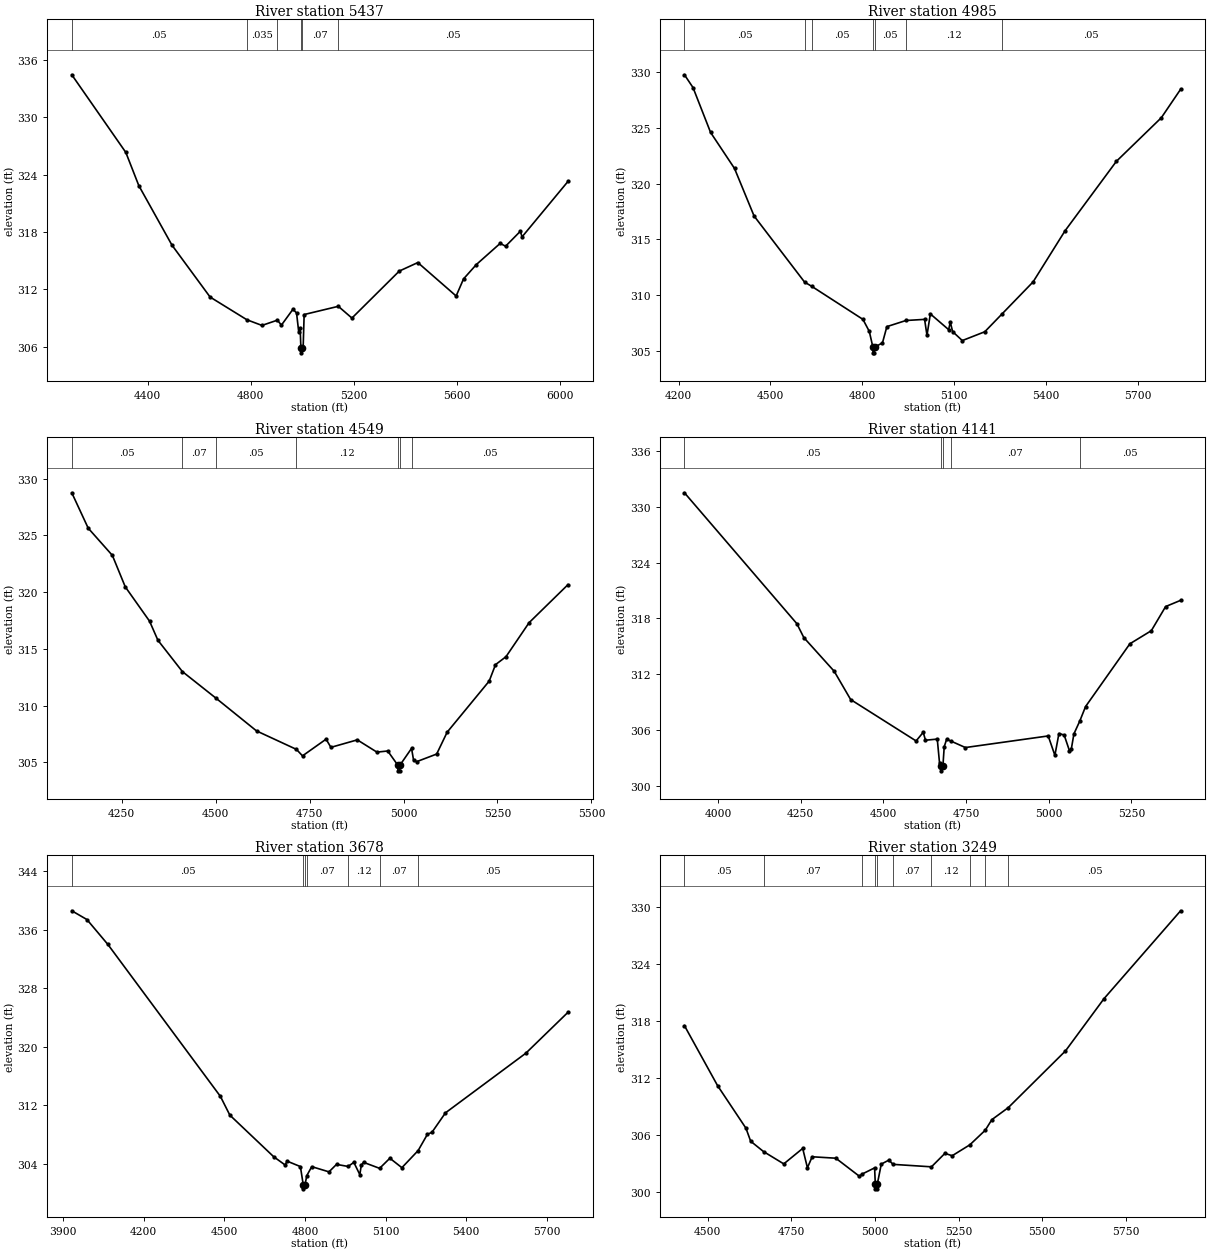
Type RM Length L Ch R = 1,5437,452,452,452
BEGIN DESCRIPTION:
Stream0457 10.0
END DESCRIPTION:
XS GIS Cut Line= 3
      2507125.03     13784574.98      2506325.00     13784975.00
      2505525.03     13785624.98
#Sta/Elev= 30
  4106.0  334.46  4315.7  326.33  4366.0  322.86  4494.6  316.63  4642.7  311.19
  4785.6  308.81  4843.9  308.22  4903.7  308.77  4919.4  308.25  4964.1  309.91
  4978.1  309.53  4986.5  307.55  4992.1  307.92  4995.0  305.85  4995.4  305.35
  5000.4  305.85  5003.7  305.85  5007.6  309.36  5140.2  310.22  5193.0  308.99
  5376.8  313.91  5448.7  314.80  5597.4  311.30  5626.1  313.09  5675.7  314.59
  5768.3  316.81  5789.2  316.51  5846.6  318.08  5853.1  317.49  6031.2  323.29
#Mann=6,-1,0
  4106.0    0.05       0  4785.6   0.035       0  4903.7    0.07       0
  4995.0    0.05       0  5000.4    0.07       0  5140.2    0.05       0
Bank Sta=4995,5000.4
Exp/Cntr=0.3,0.1

Type RM Length L Ch R = 1,4985,436,436,436
BEGIN DESCRIPTION:
Stream0457 9.0
END DESCRIPTION:
XS GIS Cut Line= 3
      2506675.00     13784175.00      2506075.00     13784675.00
      2505274.98     13784925.00
#Sta/Elev= 30
  4219.3  329.76  4247.3  328.61  4304.6  324.59  4382.7  321.36  4446.5  317.10
  4611.4  311.17  4634.3  310.80  4801.8  307.83  4822.6  306.75  4834.3  305.33
  4834.7  304.83  4839.3  304.83  4839.7  305.33  4865.6  305.73  4879.9  307.18
  4942.2  307.73  5003.0  307.83  5010.8  306.40  5021.8  308.32  5081.5  306.91
  5086.8  307.58  5094.6  306.73  5126.1  305.93  5199.4  306.72  5255.5  308.31
  5357.1  311.19  5461.3  315.77  5628.9  322.00  5775.6  325.91  5838.5  328.46
#Mann=7,-1,0
  4219.3    0.05       0  4611.4    0.07       0  4634.3    0.05       0
  4834.3    0.05       0  4839.7    0.05       0  4942.2    0.12       0
  5255.5    0.05       0
Bank Sta=4834.3,4839.7
Exp/Cntr=0.3,0.1

Type RM Length L Ch R = 1,4549,408,408,408
BEGIN DESCRIPTION:
Stream0457 8.0
END DESCRIPTION:
XS GIS Cut Line= 3
      2506624.99     13784125.00      2505825.00     13784475.00
      2505425.02     13784674.99
#Sta/Elev= 30
  4117.2  328.76  4160.9  325.64  4225.2  323.24  4259.5  320.47  4324.2  317.44
  4346.4  315.76  4411.5  313.00  4501.1  310.65  4608.8  307.77  4715.1  306.14
  4731.2  305.57  4793.9  307.04  4806.8  306.32  4877.0  306.98  4929.2  305.90
  4958.0  306.00  4984.8  304.75  4985.3  304.25  4990.1  304.25  4990.5  304.75
  5021.4  306.23  5026.7  305.20  5035.1  305.06  5088.2  305.73  5116.2  307.66
  5228.0  312.16  5244.8  313.61  5272.7  314.31  5334.2  317.31  5437.6  320.66
#Mann=7,-1,0
  4117.2    0.05       0  4411.5    0.07       0  4501.1    0.05       0
  4715.1    0.12       0  4984.8    0.05       0  4990.5    0.12       0
  5021.4    0.05       0
Bank Sta=4984.8,4990.5
Exp/Cntr=0.3,0.1

Type RM Length L Ch R = 1,4141,463,463,463
BEGIN DESCRIPTION:
Stream0457 7.0
END DESCRIPTION:
XS GIS Cut Line= 3
      2506375.02     13783424.98      2505625.00     13784225.00
      2505275.03     13784424.98
#Sta/Elev= 30
  3898.8  331.54  4238.5  317.44  4259.6  315.94  4351.4  312.31  4401.2  309.26
  4599.0  304.80  4620.5  305.73  4627.4  304.88  4663.0  305.00  4669.9  302.39
  4674.3  302.08  4674.8  301.58  4680.0  302.08  4684.0  304.18  4691.3  304.98
  4704.6  304.78  4748.0  304.09  4998.3  305.34  5018.5  303.25  5030.7  305.60
  5046.5  305.44  5062.4  303.76  5068.1  303.92  5076.0  305.56  5093.8  306.95
  5111.3  308.51  5245.2  315.27  5310.0  316.68  5353.2  319.28  5398.5  319.95
#Mann=5,-1,0
  3898.8    0.05       0  4674.3    0.05       0  4680.0    0.05       0
  4704.6    0.07       0  5093.8    0.05       0
Bank Sta=4674.3,4680
Exp/Cntr=0.3,0.1

Type RM Length L Ch R = 1,3678,429,429,429
BEGIN DESCRIPTION:
Stream0457 6.0
END DESCRIPTION:
XS GIS Cut Line= 3
      2506324.96     13783125.03      2505525.00     13783825.00
      2505175.00     13784525.01
#Sta/Elev= 30
  3932.9  338.58  3989.3  337.38  4067.2  333.98  4485.7  313.23  4520.8  310.67
  4684.1  304.98  4726.8  303.85  4733.4  304.39  4783.3  303.64  4794.1  301.10
  4794.6  300.60  4800.0  301.10  4807.2  302.41  4825.5  303.63  4889.6  302.92
  4917.6  303.94  4960.5  303.66  4982.1  304.21  5004.3  302.54  5009.8  303.82
  5018.2  304.22  5077.9  303.40  5116.1  304.78  5160.8  303.49  5221.3  305.83
  5255.8  308.05  5272.6  308.32  5322.9  310.98  5622.0  319.13  5778.5  324.71
#Mann=7,-1,0
  3932.9    0.05       0  4794.1    0.05       0  4800.0    0.05       0
  4807.2    0.07       0  4960.5    0.12       0  5077.9    0.07       0
  5221.3    0.05       0
Bank Sta=4794.1,4800
Exp/Cntr=0.3,0.1

Type RM Length L Ch R = 1,3249,448,448,448
BEGIN DESCRIPTION:
Stream0457 5.0
END DESCRIPTION:
XS GIS Cut Line= 3
      2505725.01     13783124.99      2505325.00     13783525.00
      2504524.98     13783975.01
#Sta/Elev= 30
  4430.4  317.53  4529.4  311.21  4614.3  306.72  4628.4  305.35  4666.8  304.26
  4727.4  302.96  4784.0  304.59  4798.1  302.55  4812.3  303.71  4883.0  303.56
  4953.7  301.65  4961.8  301.89  4999.0  302.54  5001.1  300.83  5001.6  300.33
  5006.6  300.33  5007.1  300.83  5019.0  302.94  5041.7  303.36  5054.2  302.91
  5169.0  302.65  5209.3  304.07  5231.0  303.82  5283.8  304.97  5329.9  306.51
  5349.5  307.62  5398.7  308.89  5569.8  314.87  5684.8  320.37  5914.0  329.64
#Mann=10,-1,0
  4430.4    0.05       0  4666.8    0.07       0  4961.8    0.12       0
  5001.1    0.05       0  5007.1    0.12       0  5054.2    0.07       0
  5169.0    0.12       0  5283.8    0.05       0  5329.9    0.07       0
  5398.7    0.05       0
Bank Sta=5001.1,5007.1
Exp/Cntr=0.3,0.1

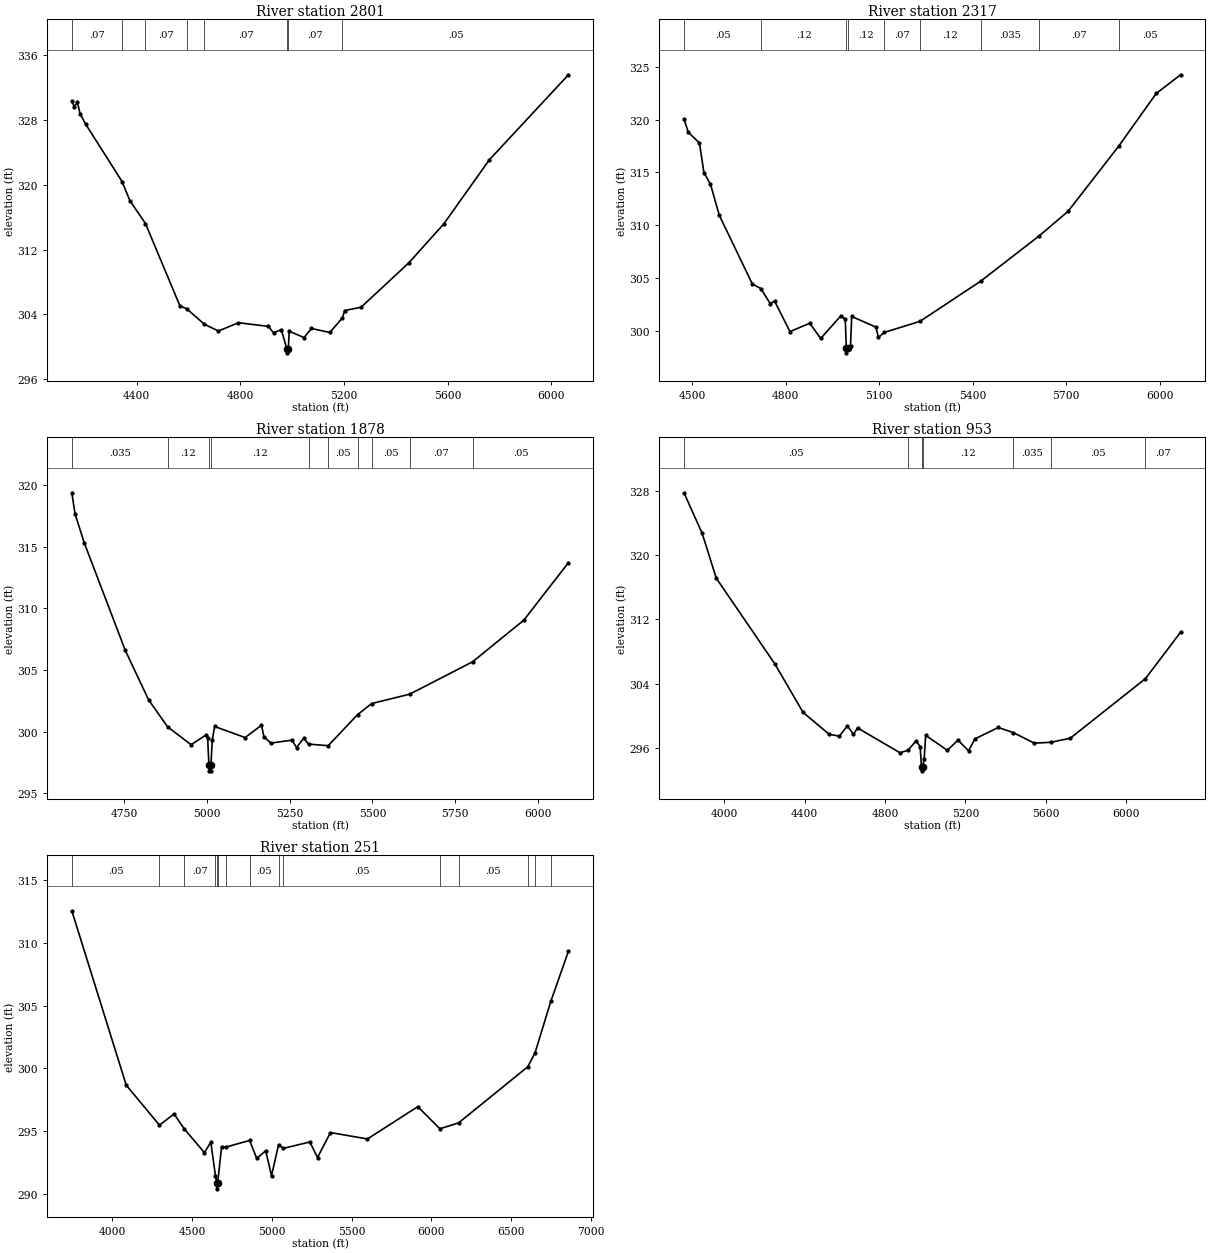
Type RM Length L Ch R = 1,2801,484,484,484
BEGIN DESCRIPTION:
Stream0457 4.0
END DESCRIPTION:
XS GIS Cut Line= 3
      2505875.04     13782874.99      2505075.00     13783175.00
      2504374.97     13783975.04
#Sta/Elev= 30
  4149.4  330.24  4159.2  329.61  4170.8  330.14  4181.5  328.73  4202.8  327.45
  4343.3  320.38  4373.7  318.02  4433.8  315.20  4566.8  305.06  4593.3  304.69
  4661.1  302.80  4715.5  301.96  4792.9  302.98  4908.6  302.53  4928.2  301.74
  4958.4  302.12  4979.5  299.77  4980.0  299.27  4985.5  299.77  4988.7  301.94
  5046.1  301.15  5074.5  302.27  5145.7  301.78  5194.5  303.59  5202.7  304.48
  5266.3  304.89  5450.4  310.35  5585.2  315.14  5761.7  323.06  6066.9  333.53
#Mann=8,-1,0
  4149.4    0.07       0  4343.3    0.05       0  4433.8    0.07       0
  4593.3    0.05       0  4661.1    0.07       0  4979.5    0.05       0
  4985.5    0.07       0  5194.5    0.05       0
Bank Sta=4979.5,4985.5
Exp/Cntr=0.3,0.1

Type RM Length L Ch R = 1,2317,439,439,439
BEGIN DESCRIPTION:
Stream0457 3.0
END DESCRIPTION:
XS GIS Cut Line= 3
      2505375.01     13782374.99      2504975.00     13782725.00
      2504275.02     13783524.98
#Sta/Elev= 30
  4472.9  320.06  4486.7  318.80  4522.7  317.77  4537.0  314.98  4557.9  313.89
  4586.3  310.94  4692.6  304.44  4719.8  304.01  4749.6  302.59  4763.8  302.83
  4813.2  299.94  4876.8  300.73  4911.9  299.29  4976.4  301.42  4990.7  301.12
  4994.2  298.43  4994.7  297.93  5000.3  298.43  5007.7  298.61  5011.5  301.37
  5089.4  300.36  5097.0  299.39  5116.1  299.86  5230.8  300.91  5425.2  304.70
  5613.7  309.00  5706.3  311.32  5869.0  317.49  5989.1  322.46  6067.4  324.23
#Mann=9,-1,0
  4472.9    0.05       0  4719.8    0.12       0  4994.2    0.05       0
  5000.3    0.12       0  5116.1    0.07       0  5230.8    0.12       0
  5425.2   0.035       0  5613.7    0.07       0  5869.0    0.05       0
Bank Sta=4994.2,5000.3
Exp/Cntr=0.3,0.1

Type RM Length L Ch R = 1,1878,925,925,925
BEGIN DESCRIPTION:
Stream0457 2.0
END DESCRIPTION:
XS GIS Cut Line= 3
      2505324.95     13782275.01      2504925.00     13782325.00
      2504174.97     13783125.04
#Sta/Elev= 30
  4592.3  319.38  4602.3  317.64  4630.0  315.31  4753.5  306.61  4824.0  302.59
  4881.3  300.40  4952.5  298.94  4998.8  299.75  5002.4  299.51  5006.3  297.32
  5006.8  296.82  5011.9  296.82  5012.4  297.32  5016.6  299.35  5023.5  300.42
  5115.8  299.52  5165.1  300.52  5172.4  299.59  5193.4  299.07  5256.9  299.31
  5271.1  298.71  5292.6  299.47  5307.2  298.99  5366.5  298.86  5455.6  301.39
  5497.9  302.28  5612.6  303.04  5802.8  305.67  5957.4  309.05  6092.0  313.71
#Mann=10,-1,0
  4592.3   0.035       0  4881.3    0.12       0  5006.3    0.05       0
  5012.4    0.12       0  5307.2   0.035       0  5366.5    0.05       0
  5455.6   0.035       0  5497.9    0.05       0  5612.6    0.07       0
  5802.8    0.05       0
Bank Sta=5006.3,5012.4
Exp/Cntr=0.3,0.1

Type RM Length L Ch R = 1,953,702,702,702
BEGIN DESCRIPTION:
Stream0457 1.0
END DESCRIPTION:
XS GIS Cut Line= 3
      2505525.02     13781975.00      2504325.00     13781875.00
      2503925.00     13783075.01
#Sta/Elev= 30
  3800.5  327.74  3890.8  322.71  3961.1  317.12  4252.1  306.47  4392.6  300.43
  4523.0  297.69  4573.2  297.48  4613.3  298.75  4643.4  297.70  4663.5  298.50
  4874.2  295.41  4914.5  295.71  4954.5  296.90  4974.6  296.18  4981.5  293.66
  4982.0  293.16  4987.7  293.66  4994.6  294.58  5002.2  297.57  5110.1  295.71
  5162.8  296.98  5215.5  295.65  5247.1  297.13  5363.1  298.55  5438.8  297.91
  5542.3  296.60  5624.8  296.71  5721.5  297.22  6095.0  304.63  6269.6  310.40
#Mann=7,-1,0
  3800.5    0.05       0  4914.5    0.12       0  4981.5    0.05       0
  4987.7    0.12       0  5438.8   0.035       0  5624.8    0.05       0
  6095.0    0.07       0
Bank Sta=4981.5,4987.7
Exp/Cntr=0.3,0.1

Type RM Length L Ch R = 1,251,0,0,0
BEGIN DESCRIPTION:
E21051
END DESCRIPTION:
XS GIS Cut Line= 4
      2505456.08     13781100.32      2504520.22     13781096.45
      2504152.85     13781398.09      2503874.41     13783076.44
#Sta/Elev= 30
  3746.8  312.54  4087.9  298.66  4296.3  295.48  4387.9  296.37  4450.0  295.21
  4577.9  293.29  4617.9  294.12  4647.0  291.46  4654.7  290.91  4655.2  290.41
  4661.0  290.91  4685.6  293.75  4711.2  293.73  4861.1  294.26  4905.9  292.83
  4961.9  293.44  4998.5  291.45  5042.6  293.93  5072.5  293.63  5238.8  294.14
  5286.7  292.90  5367.8  294.89  5599.5  294.38  5915.1  296.95  6053.7  295.19
  6170.9  295.66  6603.9  300.12  6649.5  301.21  6748.8  305.33  6859.3  309.32
#Mann=15,-1,0
  3746.8    0.05       0  4296.3    0.12       0  4450.0    0.07       0
  4647.0    0.05       0  4654.7    0.05       0  4661.0    0.05       0
  4711.2    0.07       0  4861.1    0.05       0  5042.6    0.07       0
  5072.5    0.05       0  6053.7   0.035       0  6170.9    0.05       0
  6603.9     0.1       0  6649.5    0.12       0  6748.8    0.07       0
Bank Sta=4654.7,4661
Exp/Cntr=0.3,0.1

Chan Stop Cuts=-1