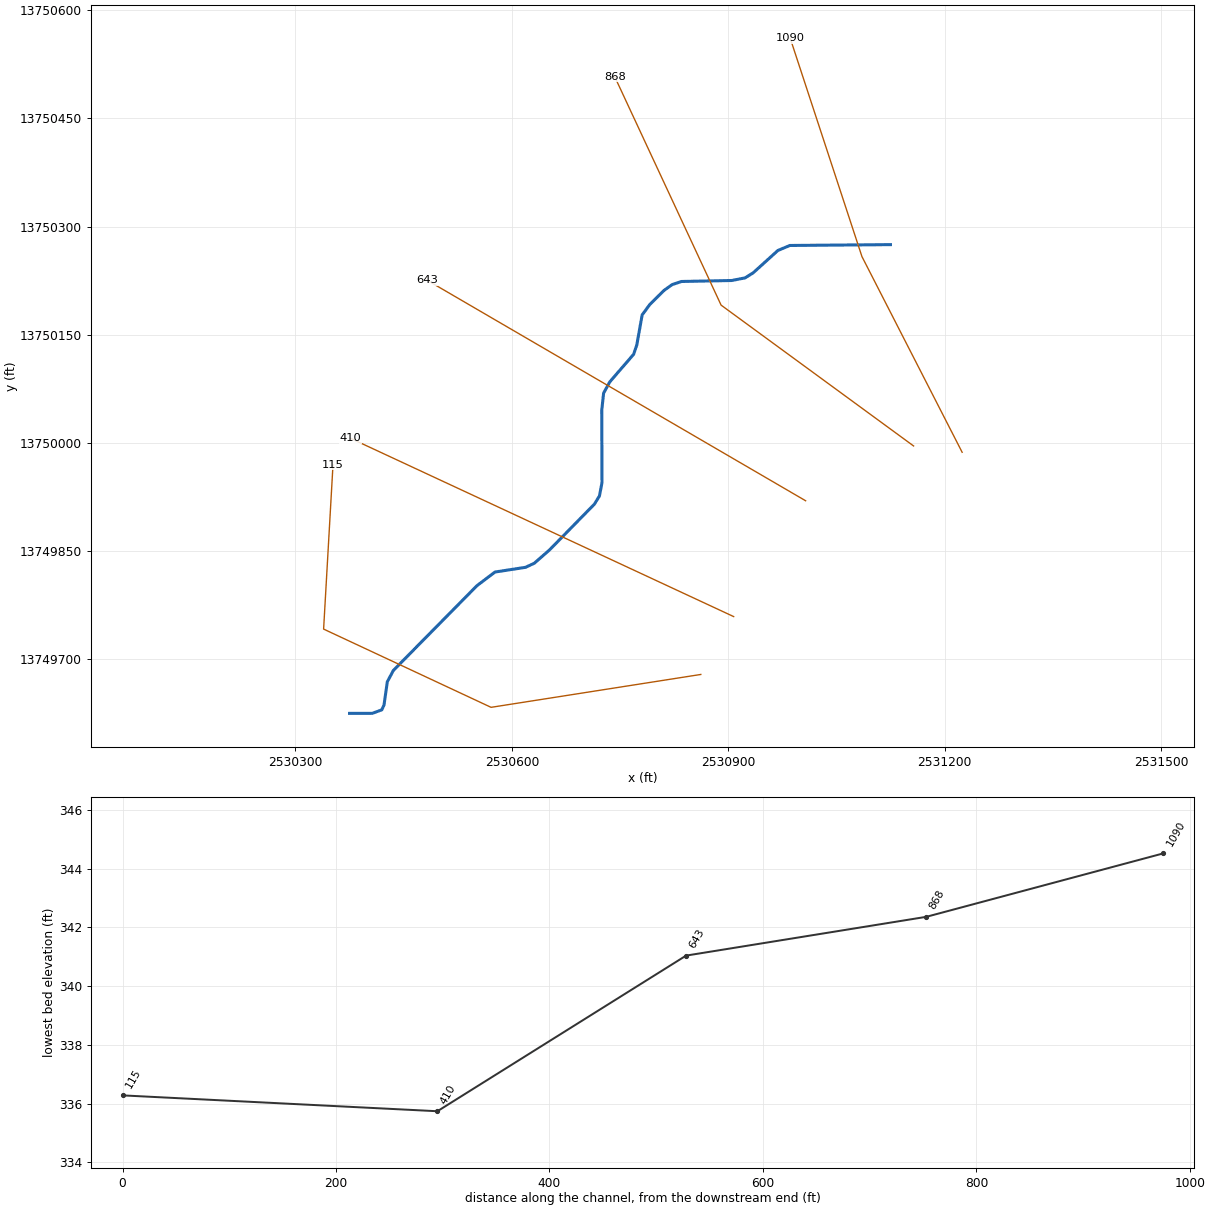
--- Stream0463.prj (project) ---

Proj Title=Stream0463 Base Level Engineering
Current Plan=p01
Default Exp/Contr=0.3,0.1
English Units
Geom File=g01
Flow File=f01
Plan File=p01
BEGIN DESCRIPTION:
Stream0463
END DESCRIPTION:

--- Stream0463.p01 (plan) ---

Plan Title=Multiple Run
Short Identifier=Multiple
Geom File=g01
Flow File=f01
Subcritical Flow
K Sum by GR= 0
Std Step Tol= 0.01
Critical Tol= 0.01
Num of Std Step Trials= 20
Max Error Tol= 0.3
Flow Tol Ratio= 0.001
Split Flow NTrial= 30
Split Flow Tol= 0.02
Split Flow Ratio= 0.02
Log Output Level= 0
Friction Slope Method= 1
Unsteady Friction Slope Method= 2
Unsteady Bridges Friction Slope Method= 1
Parabolic Critical Depth
Global Vel Dist=  1 , 1 , 1
Global Log Level= 0
CheckData=True
Encroach Param= -1, 0, 0, 0
BEGIN DESCRIPTION:
Multiple Run
END DESCRIPTION:

--- Stream0463.f01 (steady flow) ---

Flow Title=Multiple
Number of Profiles=7
Profile Names=10-year,25-year,50-year,1pct_min,100-year,1pct_plu,500-year
River Rch & RM= Stream0463,Reach-1,1090
     364     564     740     471     941    1877    1501
Boundary for River Rch & Prof#=Stream0463,Reach-1,1
Up Type=0
Dn Type=3
Dn Slope=0.005
Boundary for River Rch & Prof#=Stream0463,Reach-1,2
Up Type=0
Dn Type=3
Dn Slope=0.005
Boundary for River Rch & Prof#=Stream0463,Reach-1,3
Up Type=0
Dn Type=3
Dn Slope=0.005
Boundary for River Rch & Prof#=Stream0463,Reach-1,4
Up Type=0
Dn Type=3
Dn Slope=0.005
Boundary for River Rch & Prof#=Stream0463,Reach-1,5
Up Type=0
Dn Type=3
Dn Slope=0.005
Boundary for River Rch & Prof#=Stream0463,Reach-1,6
Up Type=0
Dn Type=3
Dn Slope=0.005
Boundary for River Rch & Prof#=Stream0463,Reach-1,7
Up Type=0
Dn Type=3
Dn Slope=0.005

--- Stream0463.g01 (geometry) ---

Geom Title=Existing Conditions

River Reach=Stream0463,Reach-1
Reach XY= 30
      2531125.00     13750275.00      2530985.48     13750273.83
      2530968.94     13750266.88      2530934.63     13750235.89
      2530923.40     13750228.86      2530904.89     13750225.25
      2530835.33     13750223.90      2530822.32     13750219.58
      2530811.34     13750211.74      2530791.45     13750192.13
      2530780.71     13750177.58      2530773.26     13750135.76
      2530768.85     13750122.86      2530735.80     13750084.67
      2530727.25     13750069.07      2530724.67     13750045.14
      2530725.02     13749944.99      2530721.46     13749926.46
      2530714.53     13749915.18      2530651.89     13749851.27
      2530631.07     13749833.15      2530618.96     13749827.53
      2530576.65     13749821.02      2530551.53     13749801.99
      2530435.72     13749684.54      2530427.30     13749668.79
      2530422.78     13749636.76      2530419.67     13749629.92
      2530406.54     13749625.07      2530375.00     13749625.00

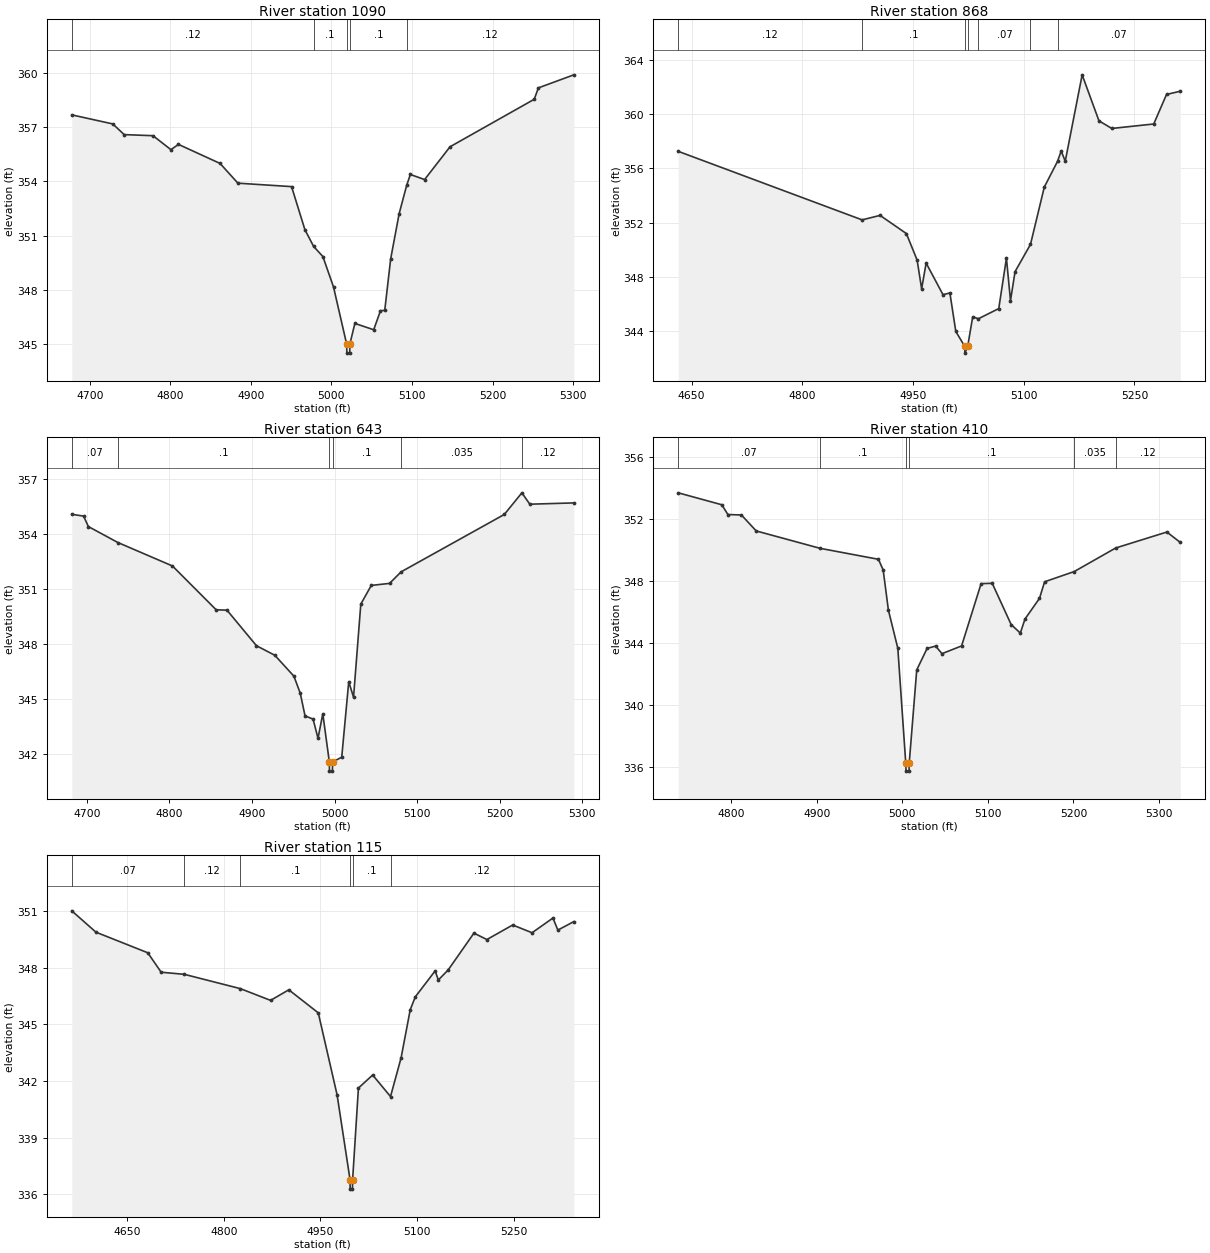
Type RM Length L Ch R = 1,1090,222,222,222
BEGIN DESCRIPTION:
XS6852
END DESCRIPTION:
XS GIS Cut Line= 3
      2531224.41     13749987.08      2531085.50     13750258.38
      2530986.05     13750561.06
#Sta/Elev= 30
  4677.6  357.67  4728.5  357.17  4742.7  356.58  4778.5  356.52  4800.7  355.75
  4810.1  356.04  4861.7  354.99  4883.9  353.90  4950.5  353.71  4967.1  351.33
  4977.9  350.41  4989.4  349.85  5002.6  348.17  5018.9  345.02  5019.2  344.52
  5022.7  344.52  5022.9  345.02  5029.1  346.16  5052.5  345.81  5060.9  346.86
  5066.2  346.88  5073.6  349.73  5084.1  352.22  5093.5  353.79  5098.0  354.38
  5115.7  354.10  5147.3  355.91  5251.8  358.53  5257.0  359.16  5301.0  359.88
#Mann=5,-1,0
  4677.6    0.12       0  4977.9     0.1       0  5018.9    0.05       0
  5022.9     0.1       0  5093.5    0.12       0
Bank Sta=5018.9,5022.9
Exp/Cntr=0.3,0.1

Type RM Length L Ch R = 1,868,225,225,225
BEGIN DESCRIPTION:
XS6851
END DESCRIPTION:
XS GIS Cut Line= 3
      2531157.11     13749995.80      2530890.19     13750191.10
      2530742.60     13750507.98
#Sta/Elev= 30
  4631.8  357.26  4880.9  352.20  4905.3  352.53  4940.9  351.19  4955.5  349.23
  4961.6  347.11  4967.7  349.01  4990.5  346.68  4999.9  346.80  5007.9  343.96
  5020.0  342.86  5020.2  342.36  5024.0  342.86  5030.8  345.04  5038.6  344.90
  5066.1  345.65  5076.5  349.37  5082.0  346.24  5088.2  348.38  5109.1  350.39
  5127.8  354.62  5145.8  356.53  5150.7  357.28  5156.2  356.53  5179.1  362.91
  5201.9  359.51  5219.3  358.95  5276.1  359.28  5293.4  361.46  5312.1  361.70
#Mann=7,-1,0
  4631.8    0.12       0  4880.9     0.1       0  5020.0    0.05       0
  5024.0     0.1       0  5038.6    0.07       0  5109.1    0.12       0
  5145.8    0.07       0
Bank Sta=5020,5024
Exp/Cntr=0.3,0.1

Type RM Length L Ch R = 1,643,233,233,233
BEGIN DESCRIPTION:
XS6850
END DESCRIPTION:
XS GIS Cut Line= 2
      2531007.37     13749919.84      2530482.20     13750225.82
#Sta/Elev= 30
  4681.8  355.05  4696.1  354.95  4701.9  354.38  4737.6  353.51  4803.7  352.23
  4856.6  349.84  4869.7  349.82  4905.4  347.88  4927.6  347.36  4950.7  346.22
  4958.4  345.29  4964.2  344.05  4973.9  343.88  4979.9  342.83  4985.7  344.17
  4993.6  341.54  4993.8  341.04  4997.3  341.04  4997.6  341.54  5008.6  341.80
  5017.1  345.92  5022.9  345.07  5031.7  350.15  5044.4  351.17  5066.5  351.28
  5080.5  351.91  5205.4  355.04  5226.7  356.22  5236.3  355.60  5289.6  355.67
#Mann=6,-1,0
  4681.8    0.07       0  4737.6     0.1       0  4993.6    0.05       0
  4997.6     0.1       0  5080.5   0.035       0  5226.7    0.12       0
Bank Sta=4993.6,4997.6
Exp/Cntr=0.3,0.1

Type RM Length L Ch R = 1,410,295,295,295
BEGIN DESCRIPTION:
XS6849
END DESCRIPTION:
XS GIS Cut Line= 2
      2530907.60     13749759.22      2530375.84     13750006.65
#Sta/Elev= 30
  4738.3  353.70  4789.2  352.93  4796.3  352.30  4812.1  352.27  4829.4  351.24
  4903.9  350.12  4972.2  349.41  4977.7  348.72  4983.8  346.13  4994.8  343.67
  5004.1  336.24  5004.4  335.74  5007.9  335.74  5008.1  336.24  5016.9  342.27
  5029.0  343.66  5039.0  343.81  5046.4  343.32  5069.3  343.82  5092.1  347.84
  5105.1  347.86  5127.2  345.20  5137.9  344.65  5143.4  345.56  5160.3  346.89
  5166.3  347.96  5200.9  348.62  5249.3  350.14  5309.1  351.17  5324.8  350.50
#Mann=6,-1,0
  4738.3    0.07       0  4903.9     0.1       0  5004.1    0.05       0
  5008.1     0.1       0  5200.9   0.035       0  5249.3    0.12       0
Bank Sta=5004.1,5008.1
Exp/Cntr=0.3,0.1

Type RM Length L Ch R = 1,115,0,0,0
BEGIN DESCRIPTION:
XS6848
END DESCRIPTION:
XS GIS Cut Line= 4
      2530862.01     13749678.96      2530571.18     13749633.38
      2530338.98     13749741.88      2530352.00     13749969.72
#Sta/Elev= 30
  4564.3  351.01  4601.8  349.88  4682.2  348.79  4703.0  347.76  4738.8  347.65
  4826.0  346.89  4872.7  346.27  4901.0  346.83  4946.7  345.61  4975.9  341.27
  4996.0  336.78  4996.2  336.28  4999.7  336.28  5000.0  336.78  5009.0  341.63
  5031.1  342.32  5058.8  341.18  5075.2  343.23  5089.4  345.78  5097.3  346.46
  5128.0  347.83  5133.0  347.35  5148.2  347.88  5188.2  349.83  5208.3  349.49
  5248.3  350.26  5278.4  349.85  5310.8  350.63  5318.4  349.99  5343.2  350.44
#Mann=6,-1,0
  4564.3    0.07       0  4738.8    0.12       0  4826.0     0.1       0
  4996.0    0.05       0  5000.0     0.1       0  5058.8    0.12       0
Bank Sta=4996,5000
Exp/Cntr=0.3,0.1

Chan Stop Cuts=-1