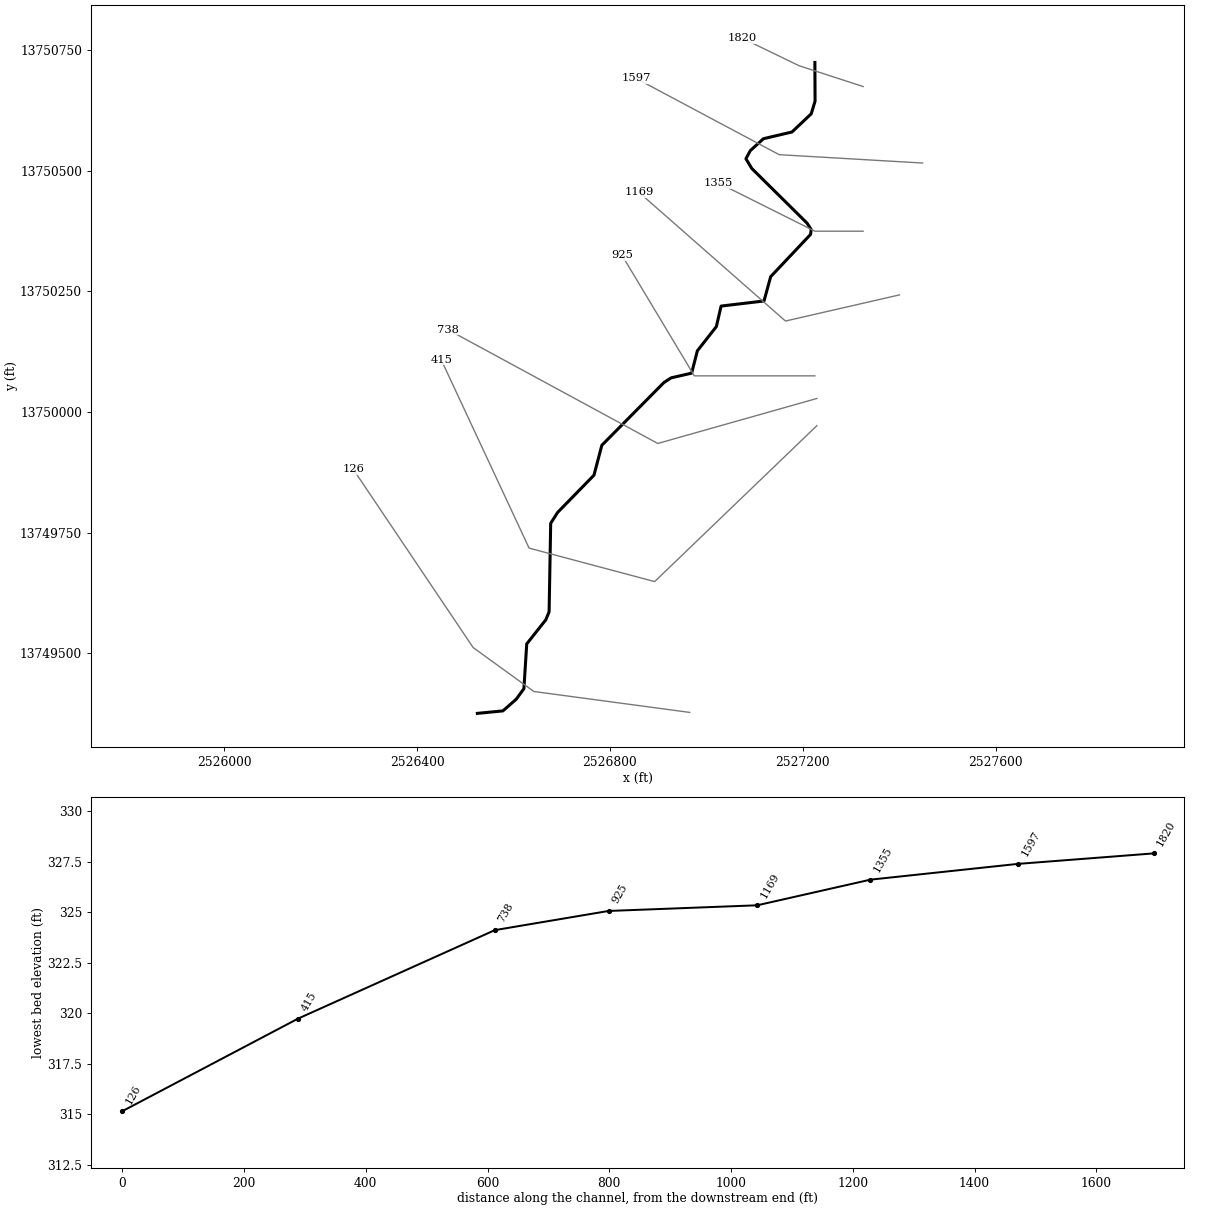
--- Stream0464.prj (project) ---

Proj Title=Stream0464 Base Level Engineering
Current Plan=p01
Default Exp/Contr=0.3,0.1
English Units
Geom File=g01
Flow File=f01
Plan File=p01
BEGIN DESCRIPTION:
Stream0464
END DESCRIPTION:

--- Stream0464.p01 (plan) ---

Plan Title=Multiple Run
Short Identifier=Multiple
Geom File=g01
Flow File=f01
Subcritical Flow
K Sum by GR= 0
Std Step Tol= 0.01
Critical Tol= 0.01
Num of Std Step Trials= 20
Max Error Tol= 0.3
Flow Tol Ratio= 0.001
Split Flow NTrial= 30
Split Flow Tol= 0.02
Split Flow Ratio= 0.02
Log Output Level= 0
Friction Slope Method= 1
Unsteady Friction Slope Method= 2
Unsteady Bridges Friction Slope Method= 1
Parabolic Critical Depth
Global Vel Dist=  1 , 1 , 1
Global Log Level= 0
CheckData=True
Encroach Param= -1, 0, 0, 0
BEGIN DESCRIPTION:
Multiple Run
END DESCRIPTION:

--- Stream0464.f01 (steady flow) ---

Flow Title=Multiple
Number of Profiles=7
Profile Names=10-year,25-year,50-year,1pct_min,100-year,1pct_plu,500-year
River Rch & RM= Stream0464,Reach-1,1820
     183     268     338     208     414     826     611
Boundary for River Rch & Prof#=Stream0464,Reach-1,1
Up Type=0
Dn Type=3
Dn Slope=0.005
Boundary for River Rch & Prof#=Stream0464,Reach-1,2
Up Type=0
Dn Type=3
Dn Slope=0.005
Boundary for River Rch & Prof#=Stream0464,Reach-1,3
Up Type=0
Dn Type=3
Dn Slope=0.005
Boundary for River Rch & Prof#=Stream0464,Reach-1,4
Up Type=0
Dn Type=3
Dn Slope=0.005
Boundary for River Rch & Prof#=Stream0464,Reach-1,5
Up Type=0
Dn Type=3
Dn Slope=0.005
Boundary for River Rch & Prof#=Stream0464,Reach-1,6
Up Type=0
Dn Type=3
Dn Slope=0.005
Boundary for River Rch & Prof#=Stream0464,Reach-1,7
Up Type=0
Dn Type=3
Dn Slope=0.005

--- Stream0464.g01 (geometry) ---

Geom Title=Existing Conditions

River Reach=Stream0464,Reach-1
Reach XY= 30
      2527225.00     13750725.00      2527225.38     13750644.73
      2527217.39     13750618.45      2527177.51     13750580.73
      2527118.31     13750566.83      2527091.04     13750542.04
      2527081.98     13750525.21      2527094.18     13750505.07
      2527208.80     13750391.67      2527217.40     13750378.34
      2527216.03     13750368.34      2527133.34     13750280.71
      2527119.46     13750230.29      2527030.52     13750219.72
      2527020.65     13750177.14      2526981.22     13750126.89
      2526969.41     13750080.61      2526927.01     13750070.87
      2526912.02     13750061.27      2526783.16     13749931.05
      2526766.82     13749868.96      2526691.46     13749791.75
      2526677.07     13749769.14      2526673.78     13749585.50
      2526666.86     13749568.94      2526627.36     13749519.02
      2526621.54     13749426.30      2526605.69     13749404.45
      2526577.94     13749380.13      2526525.00     13749375.00

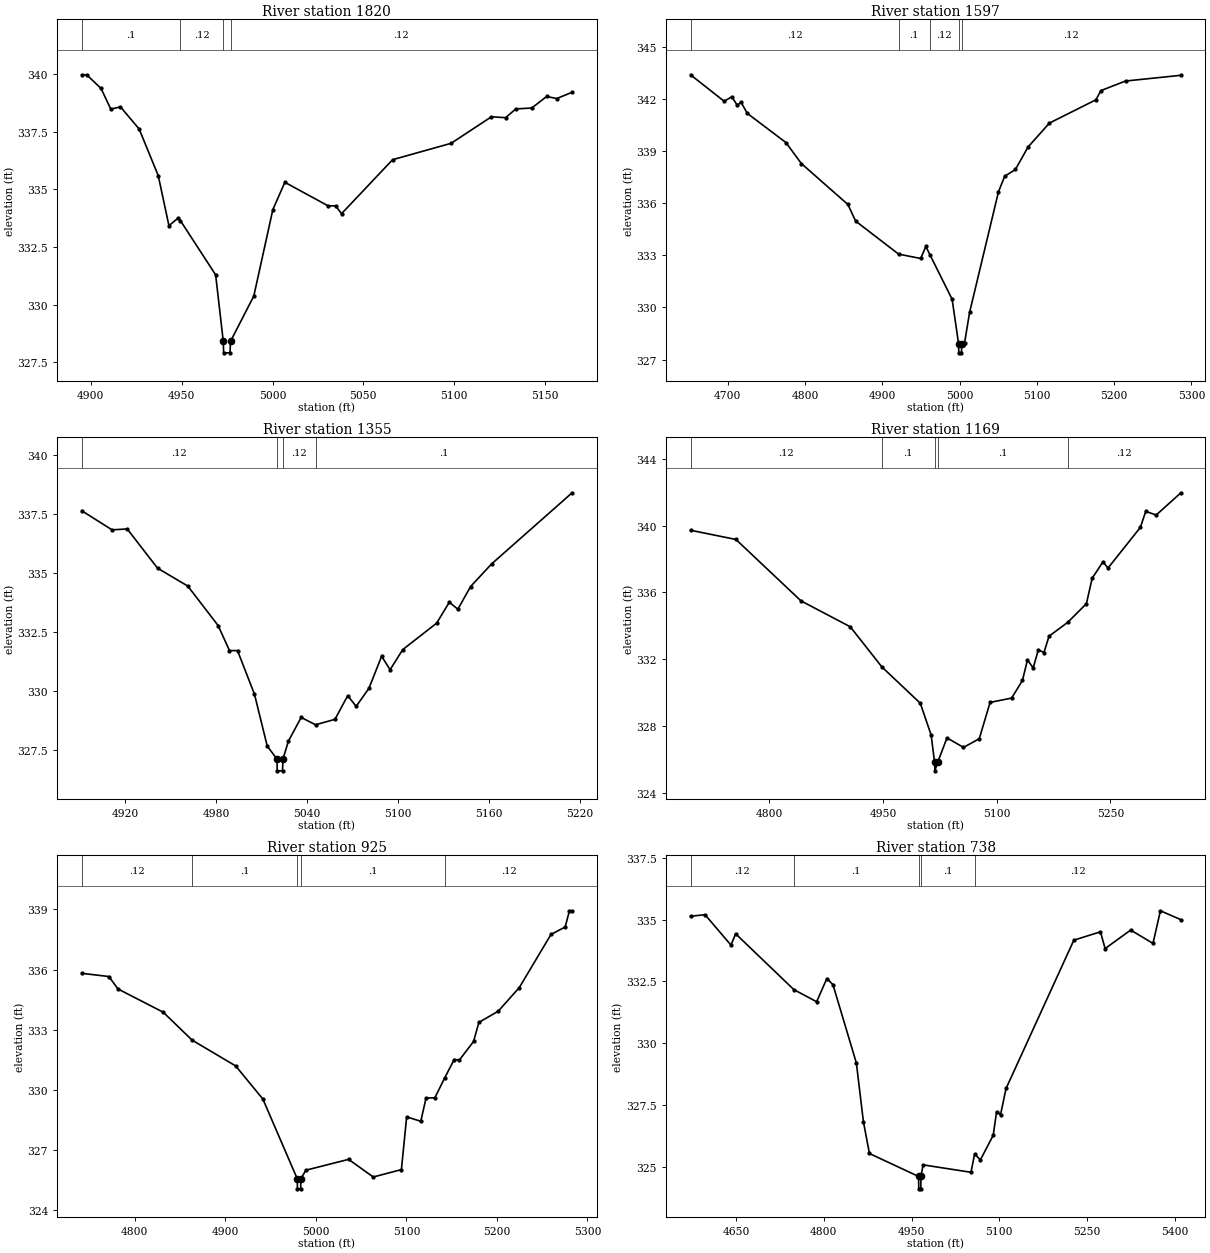
Type RM Length L Ch R = 1,1820,223,223,223
BEGIN DESCRIPTION:
Stream0464 3.0
END DESCRIPTION:
XS GIS Cut Line= 3
      2527325.04     13750674.99      2527192.19     13750718.19
      2527075.03     13750774.99
#Sta/Elev= 30
  4895.0  339.96  4897.7  339.96  4905.6  339.37  4911.0  338.47  4916.3  338.57
  4926.6  337.61  4937.1  335.59  4943.0  333.42  4948.2  333.76  4949.3  333.64
  4968.7  331.29  4972.9  328.41  4973.1  327.91  4976.6  327.91  4976.9  328.41
  4989.7  330.37  5000.2  334.12  5006.8  335.30  5030.6  334.28  5034.7  334.28
  5038.0  333.94  5066.1  336.28  5098.3  336.99  5120.5  338.14  5128.3  338.10
  5133.9  338.48  5142.7  338.52  5150.9  339.02  5156.4  338.93  5164.9  339.20
#Mann=4,-1,0
  4895.0     0.1       0  4949.3    0.12       0  4972.9    0.05       0
  4976.9    0.12       0
Bank Sta=4972.9,4976.9
Exp/Cntr=0.3,0.1

Type RM Length L Ch R = 1,1597,242,242,242
BEGIN DESCRIPTION:
XS6856
END DESCRIPTION:
XS GIS Cut Line= 3
      2527448.29     13750516.36      2527150.95     13750533.72
      2526853.66     13750692.13
#Sta/Elev= 30
  4651.7  343.39  4695.1  341.87  4705.1  342.12  4712.1  341.64  4717.1  341.81
  4725.1  341.17  4775.2  339.49  4795.2  338.28  4855.3  335.93  4865.4  334.97
  4921.0  333.07  4949.5  332.82  4956.3  333.51  4961.6  333.03  4990.3  330.47
  4998.7  327.89  4998.9  327.39  5002.4  327.39  5002.7  327.89  5006.3  327.94
  5012.9  329.72  5050.3  336.66  5058.3  337.55  5072.2  337.94  5088.5  339.23
  5116.2  340.61  5176.4  341.95  5182.9  342.48  5214.7  343.03  5286.4  343.36
#Mann=5,-1,0
  4651.7    0.12       0  4921.0     0.1       0  4961.6    0.12       0
  4998.7    0.05       0  5002.7    0.12       0
Bank Sta=4998.7,5002.7
Exp/Cntr=0.3,0.1

Type RM Length L Ch R = 1,1355,186,186,186
BEGIN DESCRIPTION:
Stream0464 2.0
END DESCRIPTION:
XS GIS Cut Line= 3
      2527325.04     13750375.00      2527225.00     13750375.00
      2527025.04     13750474.98
#Sta/Elev= 30
  4891.2  337.62  4911.2  336.81  4921.2  336.85  4941.2  335.19  4961.2  334.43
  4981.2  332.76  4988.7  331.70  4994.0  331.70  5005.2  329.85  5013.6  327.66
  5020.0  327.11  5020.2  326.61  5023.7  326.61  5024.0  327.11  5027.6  327.87
  5036.0  328.87  5045.5  328.56  5058.3  328.79  5066.7  329.79  5072.3  329.34
  5080.7  330.10  5089.1  331.46  5094.7  330.89  5103.0  331.74  5125.4  332.86
  5133.8  333.75  5139.4  333.45  5147.8  334.41  5161.7  335.37  5214.8  338.38
#Mann=4,-1,0
  4891.2    0.12       0  5020.0    0.05       0  5024.0    0.12       0
  5045.5     0.1       0
Bank Sta=5020,5024
Exp/Cntr=0.3,0.1

Type RM Length L Ch R = 1,1169,244,244,244
BEGIN DESCRIPTION:
XS6855
END DESCRIPTION:
XS GIS Cut Line= 3
      2527400.49     13750242.92      2527163.98     13750188.67
      2526860.14     13750455.61
#Sta/Elev= 30
  4696.0  339.72  4755.9  339.17  4841.7  335.50  4906.8  333.95  4948.5  331.55
  4999.2  329.38  5013.5  327.48  5018.1  325.84  5018.4  325.34  5022.1  325.84
  5034.4  327.31  5056.2  326.74  5077.0  327.26  5091.3  329.43  5119.7  329.69
  5134.0  330.74  5140.6  331.97  5148.2  331.49  5154.9  332.57  5162.4  332.41
  5169.1  333.39  5193.6  334.21  5218.4  335.33  5226.0  336.85  5240.2  337.83
  5246.9  337.46  5289.6  339.89  5296.7  340.85  5310.5  340.63  5343.1  341.96
#Mann=5,-1,0
  4696.0    0.12       0  4948.5     0.1       0  5018.1    0.05       0
  5022.1     0.1       0  5193.6    0.12       0
Bank Sta=5018.1,5022.1
Exp/Cntr=0.3,0.1

Type RM Length L Ch R = 1,925,187,187,187
BEGIN DESCRIPTION:
Stream0464 1.0
END DESCRIPTION:
XS GIS Cut Line= 3
      2527224.99     13750075.00      2526975.00     13750075.00
      2526825.02     13750324.97
#Sta/Elev= 30
  4741.5  335.81  4771.5  335.65  4781.5  335.03  4831.5  333.87  4863.3  332.48
  4911.5  331.19  4941.5  329.54  4979.5  325.56  4979.7  325.06  4983.2  325.06
  4983.5  325.56  4989.0  325.99  5036.2  326.53  5063.4  325.65  5094.5  326.02
  5100.3  328.65  5115.9  328.43  5121.7  329.59  5131.4  329.60  5142.4  330.60
  5152.8  331.51  5158.6  331.49  5174.2  332.41  5180.0  333.36  5201.4  333.92
  5224.7  335.10  5259.7  337.75  5275.3  338.12  5280.1  338.93  5283.0  338.93
#Mann=5,-1,0
  4741.5    0.12       0  4863.3     0.1       0  4979.5    0.05       0
  4983.5     0.1       0  5142.4    0.12       0
Bank Sta=4979.5,4983.5
Exp/Cntr=0.3,0.1

Type RM Length L Ch R = 1,738,323,323,323
BEGIN DESCRIPTION:
XS6854
END DESCRIPTION:
XS GIS Cut Line= 3
      2527229.10     13750028.09      2526899.22     13749934.77
      2526464.20     13750170.67
#Sta/Elev= 30
  4572.5  335.14  4597.3  335.20  4641.6  333.97  4649.5  334.43  4749.0  332.17
  4787.9  331.68  4805.4  332.62  4815.8  332.37  4855.8  329.20  4867.8  326.83
  4878.1  325.54  4962.1  324.61  4962.4  324.11  4965.9  324.11  4966.1  324.61
  4969.8  325.08  5051.6  324.78  5057.8  325.52  5067.7  325.28  5089.6  326.28
  5095.3  327.23  5102.1  327.11  5111.5  328.17  5227.3  334.17  5272.8  334.51
  5280.7  333.83  5324.4  334.58  5362.5  334.04  5375.2  335.36  5410.2  335.00
#Mann=5,-1,0
  4572.5    0.12       0  4749.0     0.1       0  4962.1    0.05       0
  4966.1     0.1       0  5057.8    0.12       0
Bank Sta=4962.1,4966.1
Exp/Cntr=0.3,0.1

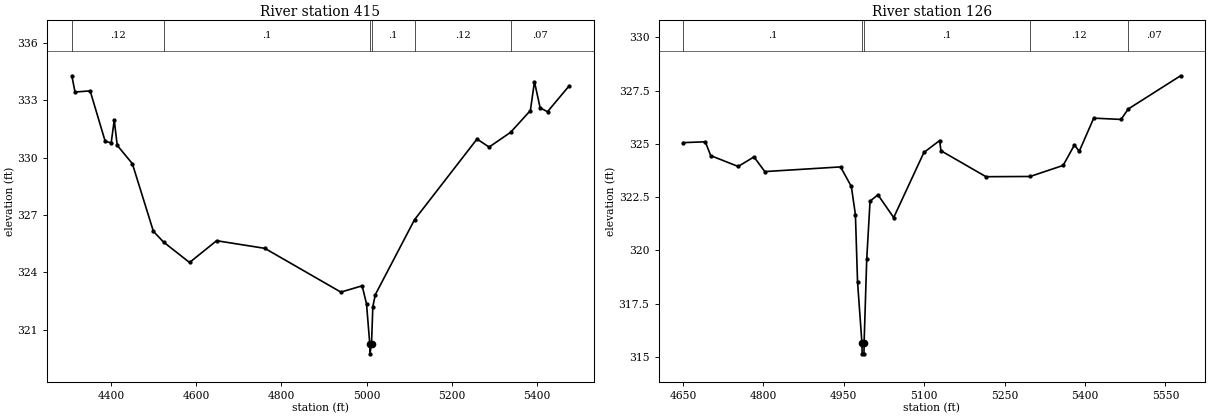
Type RM Length L Ch R = 1,415,289,289,289
BEGIN DESCRIPTION:
XS6853
END DESCRIPTION:
XS GIS Cut Line= 4
      2527229.09     13749971.67      2526892.71     13749648.31
      2526632.29     13749717.75      2526449.99     13750108.39
#Sta/Elev= 30
  4307.8  334.28  4315.3  333.43  4350.8  333.49  4386.1  330.85  4400.2  330.77
  4407.4  331.96  4414.4  330.64  4449.9  329.68  4499.3  326.14  4523.1  325.58
  4584.2  324.51  4647.7  325.65  4760.9  325.25  4939.5  322.96  4989.4  323.29
  4999.7  322.34  5007.4  320.23  5007.6  319.73  5011.4  320.23  5014.5  322.20
  5020.4  322.83  5112.4  326.75  5259.1  330.97  5287.5  330.55  5337.9  331.32
  5384.4  332.46  5394.0  333.97  5407.3  332.60  5424.6  332.40  5475.0  333.74
#Mann=6,-1,0
  4307.8    0.12       0  4523.1     0.1       0  5007.4    0.05       0
  5011.4     0.1       0  5112.4    0.12       0  5337.9    0.07       0
Bank Sta=5007.4,5011.4
Exp/Cntr=0.3,0.1

Type RM Length L Ch R = 1,126,0,0,0
BEGIN DESCRIPTION:
E21054
END DESCRIPTION:
XS GIS Cut Line= 4
      2526965.46     13749376.99      2526642.12     13749420.39
      2526516.25     13749511.54      2526267.55     13749881.35
#Sta/Elev= 30
  4650.9  325.06  4691.7  325.10  4701.8  324.45  4753.0  323.94  4782.5  324.39
  4802.7  323.70  4944.0  323.92  4964.1  323.00  4971.7  321.68  4975.7  318.51
  4983.9  315.64  4984.2  315.14  4987.7  315.14  4987.9  315.64  4992.8  319.58
  4999.0  322.31  5013.7  322.61  5043.1  321.54  5099.5  324.60  5128.9  325.16
  5131.2  324.68  5215.2  323.46  5297.6  323.47  5359.2  323.99  5380.2  324.95
  5389.2  324.65  5416.2  326.21  5467.2  326.15  5480.6  326.64  5578.2  328.20
#Mann=5,-1,0
  4650.9     0.1       0  4983.9    0.05       0  4987.9     0.1       0
  5297.6    0.12       0  5480.6    0.07       0
Bank Sta=4983.9,4987.9
Exp/Cntr=0.3,0.1

Chan Stop Cuts=-1