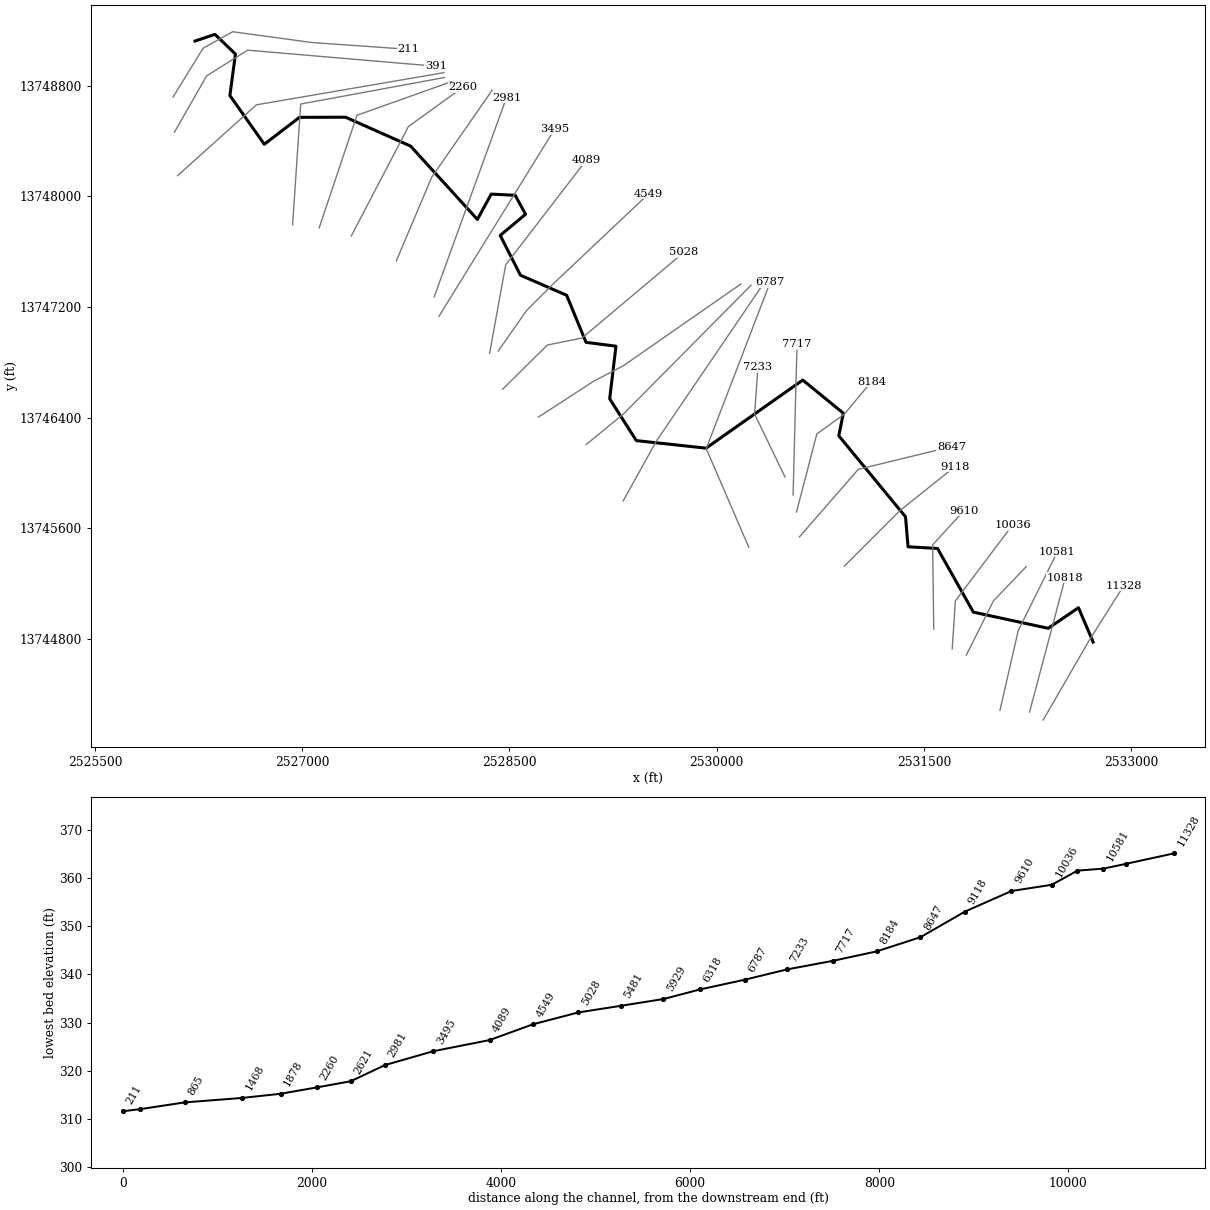
--- Stream0465.prj (project) ---

Proj Title=Stream0465 Base Level Engineering
Current Plan=p01
Default Exp/Contr=0.3,0.1
English Units
Geom File=g01
Flow File=f01
Plan File=p01
Y Axis Title=Elevation
X Axis Title(PF)=Main Channel Distance
X Axis Title(XS)=Station
BEGIN DESCRIPTION:
Stream0465
END DESCRIPTION:
DSS Export Rating Curves= 0
DSS Export Rating Curve Sorted= 0
DSS Export Volume Flow Curves= 0
DXF OffsetX= 0
DXF OffsetY= 0
DXF ScaleX= 1
DXF ScaleY= 10

--- Stream0465.p01 (plan) ---

Plan Title=Multiple Run
Short Identifier=Multiple
Geom File=g01
Flow File=f01
Subcritical Flow
K Sum by GR= 0
Std Step Tol= 0.01
Critical Tol= 0.01
Num of Std Step Trials= 20
Max Error Tol= 0.3
Flow Tol Ratio= 0.001
Split Flow NTrial= 30
Split Flow Tol= 0.02
Split Flow Ratio= 0.02
Log Output Level= 0
Friction Slope Method= 1
Unsteady Friction Slope Method= 2
Unsteady Bridges Friction Slope Method= 1
Parabolic Critical Depth
Global Vel Dist=  1 , 1 , 1
Global Log Level= 0
CheckData=True
Encroach Param= -1, 0, 0, 0
BEGIN DESCRIPTION:
Multiple Run
END DESCRIPTION:

--- Stream0465.f01 (steady flow) ---

Flow Title=Multiple
Number of Profiles=7
Profile Names=10-year,25-year,50-year,1pct_min,100-year,1pct_plu,500-year
River Rch & RM= Stream0465,Reach-1,11328
    1185    1990    2751    1841    3674    7331    6487
River Rch & RM= Stream0465,Reach-1,10818
    1168    1954    2691    1795    3582    7147    6281
River Rch & RM= Stream0465,Reach-1,8647
    1592    2701    3758    2528    5043   10062    8996
River Rch & RM= Stream0465,Reach-1,6318
    1680    2841    3940    2640    5267   10509    9326
Boundary for River Rch & Prof#=Stream0465,Reach-1,1
Up Type=0
Dn Type=3
Dn Slope=0.005
Boundary for River Rch & Prof#=Stream0465,Reach-1,2
Up Type=0
Dn Type=3
Dn Slope=0.005
Boundary for River Rch & Prof#=Stream0465,Reach-1,3
Up Type=0
Dn Type=3
Dn Slope=0.005
Boundary for River Rch & Prof#=Stream0465,Reach-1,4
Up Type=0
Dn Type=3
Dn Slope=0.005
Boundary for River Rch & Prof#=Stream0465,Reach-1,5
Up Type=0
Dn Type=3
Dn Slope=0.005
Boundary for River Rch & Prof#=Stream0465,Reach-1,6
Up Type=0
Dn Type=3
Dn Slope=0.005
Boundary for River Rch & Prof#=Stream0465,Reach-1,7
Up Type=0
Dn Type=3
Dn Slope=0.005

--- Stream0465.g01 (geometry) ---

Geom Title=Existing Conditions
Program Version=4.10

River Reach=Stream0465      ,Reach-1
Reach XY= 30
        2532725.       13744775.      2532619.16     13745023.51
      2532400.12      13744874.7      2531858.29     13744991.63
      2531598.84     13745452.44      2531385.34     13745464.76
      2531367.32     13745681.52      2530884.15     13746268.27
      2530917.35     13746431.45      2530623.41     13746671.33
       2529923.5     13746178.46      2529418.91     13746233.14
      2529226.04     13746535.44      2529271.49     13746916.57
      2529054.91     13746944.43      2528914.53     13747284.83
      2528580.17     13747430.41      2528433.77     13747718.21
      2528617.24     13747871.58      2528542.15     13748008.73
      2528368.48     13748017.33      2528268.51      13747833.9
      2527785.12     13748364.65       2527314.5     13748573.78
      2526980.85     13748572.94      2526726.43     13748378.01
      2526477.06     13748730.85      2526517.52     13749031.06
      2526368.98     13749173.41        2526225.       13749125.

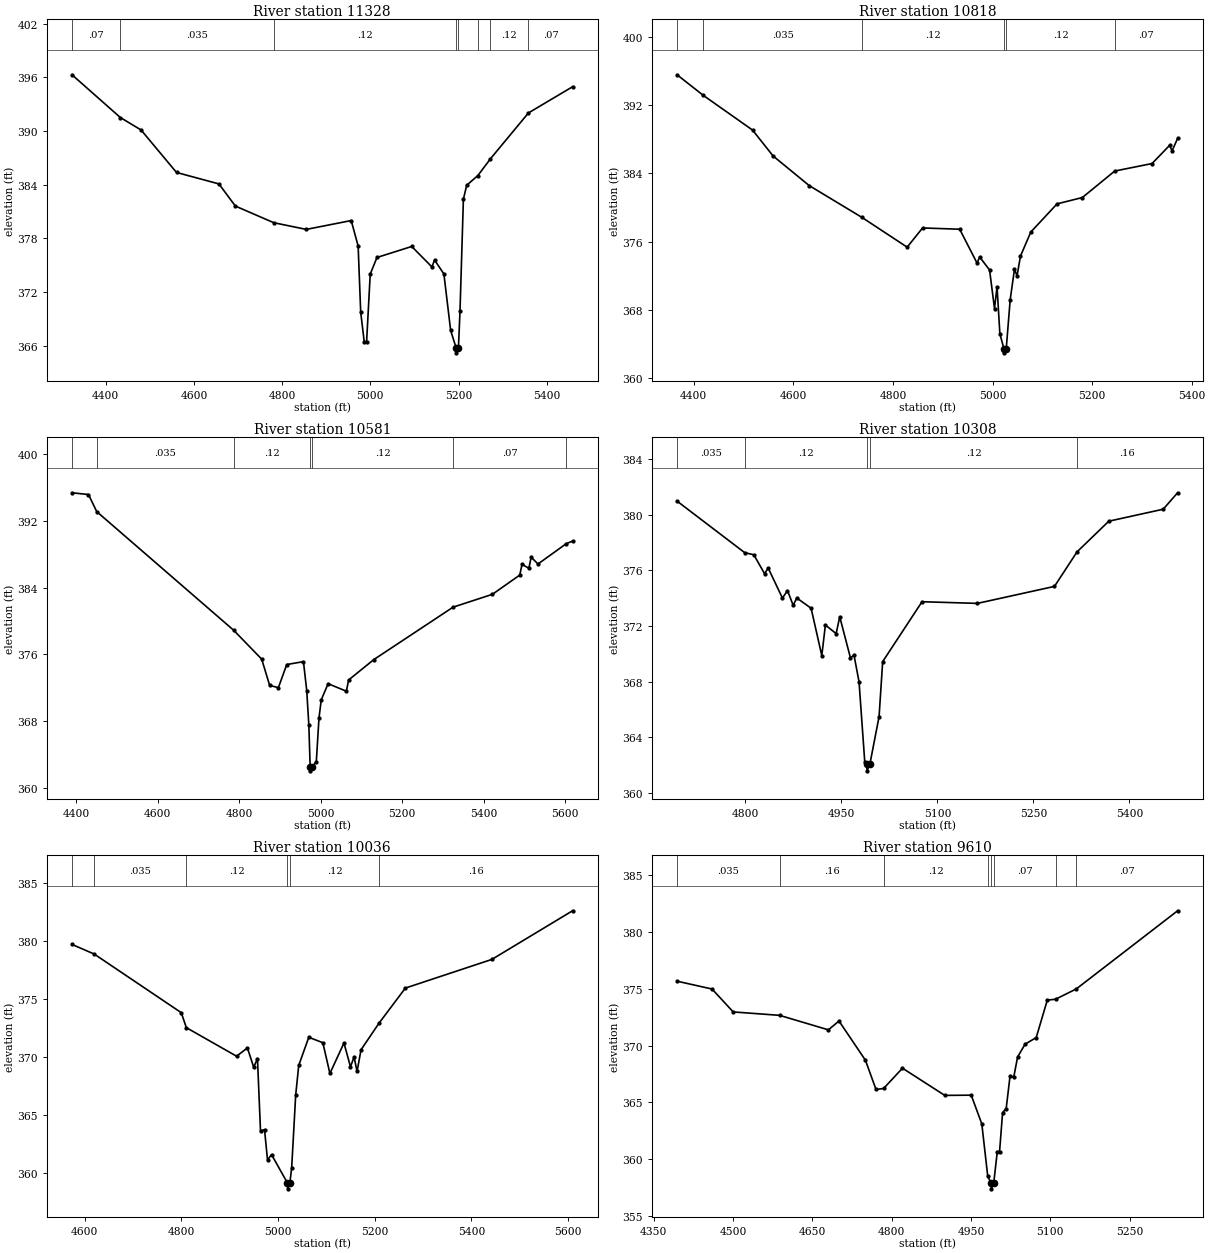
Type RM Length L Ch R = 1 ,11328   ,510,510,510
BEGIN DESCRIPTION:
XS6867
END DESCRIPTION:
XS GIS Cut Line= 3
      2532363.53     13744211.01      2532697.97     13744789.38
      2532947.15     13745184.35
#Sta/Elev= 30
  4323.5  396.29  4433.1  391.51  4480.2  390.11  4560.5  385.36  4656.7  384.08
    4694   381.6    4781  379.74  4854.8  378.99  4956.7  379.98  4972.4  377.13
  4978.2  369.72  4986.2  366.42  4991.6  366.42  4999.8  373.99  5015.1  375.85
  5093.9  377.08  5139.8  374.79  5145.7  375.57  5166.9     374  5182.2  367.68
    5195  365.68  5195.4  365.18  5199.8  365.68  5203.4  369.87  5211.1  382.37
  5218.6  383.93    5244  385.02  5272.4  386.89  5358.6  392.02  5458.6  394.95
#Mann= 8 ,-1 , 0
  4323.5     .07       0  4433.1    .035       0    4781     .12       0
    5195     .06       0  5199.8     .12       0    5244     .07       0
  5272.4     .12       0  5358.6     .07       0
Bank Sta=5195,5199.8
XS Rating Curve= 0 ,0
Exp/Cntr=0.3,0.1

Type RM Length L Ch R = 1 ,10818   ,237,237,237
BEGIN DESCRIPTION:
Stream0465 22.0
END DESCRIPTION:
XS GIS Cut Line= 3
       2532264.8     13744268.59      2532449.92     13744963.82
      2532523.03     13745239.96
#Sta/Elev= 30
  4366.6  395.55  4419.2  393.14  4518.1  389.08  4559.5  386.04  4631.9  382.58
  4737.4  378.87  4828.6  375.37  4859.6  377.62  4934.1  377.47    4969   373.5
  4974.2  374.22  4994.1   372.7    5004  368.19  5009.1  370.73  5014.8  365.23
  5022.8   363.5  5023.1     363  5027.6   363.5  5035.5  369.22  5044.1  372.78
  5049.3  372.02  5056.2  374.33  5076.9  377.14  5129.6  380.44  5180.4  381.18
  5245.4  384.28  5320.4  385.16  5355.5  387.28  5360.6  386.65  5371.7   388.1
#Mann= 6 ,-1 , 0
  4366.6     .07       0  4419.2    .035       0  4737.4     .12       0
  5022.8     .06       0  5027.6     .12       0  5245.4     .07       0
Bank Sta=5022.8,5027.6
XS Rating Curve= 0 ,0
Exp/Cntr=0.3,0.1

Type RM Length L Ch R = 1 ,10581   ,273,273,273
BEGIN DESCRIPTION:
Stream0465 21.0
END DESCRIPTION:
XS GIS Cut Line= 3
       2532050.9     13744280.94      2532182.54     13744856.86
      2532466.36     13745428.62
#Sta/Elev= 30
  4389.3  395.39  4429.8  395.18    4450  393.13  4786.2  378.89  4855.1  375.42
  4874.7  372.26  4896.1     372  4916.6  374.77  4957.6  375.12  4965.7  371.65
  4970.9  367.47  4974.1  362.51  4974.5  362.01    4979  362.51  4989.2  363.09
  4995.8  368.36  5001.4  370.54  5018.2  372.47    5063  371.57  5068.6  372.92
  5130.3  375.36  5325.1  381.66  5421.6   383.2  5488.8  385.51  5494.4   386.8
  5511.2  386.33  5516.8  387.66  5533.6  386.84    5603  389.28  5618.4  389.59
#Mann= 7 ,-1 , 0
  4389.3     .07       0    4450    .035       0  4786.2     .12       0
  4974.1     .06       0    4979     .12       0  5325.1     .07       0
    5603     .16       0
Bank Sta=4974.1,4979
XS Rating Curve= 0 ,0
Exp/Cntr=0.3,0.1

Type RM Length L Ch R = 1 ,10308   ,272,272,272
BEGIN DESCRIPTION:
XS6866
END DESCRIPTION:
XS GIS Cut Line= 3
      2531807.38     13744680.73      2532003.51       13745073.
      2532241.02     13745321.06
#Sta/Elev= 30
  4693.3  380.96    4799  377.26  4813.2  377.11    4830  375.75  4835.6  376.16
  4857.9     374  4865.8  374.54  4874.7  373.48  4880.3  374.01  4902.7  373.27
  4919.4  369.87    4925  372.07  4941.8  371.45  4947.4  372.66  4964.2   369.7
  4969.7  369.91  4977.6  367.98  4986.5  362.25  4989.7   362.1    4990   361.6
  4994.6   362.1  5008.9   365.5  5014.5  369.44    5076  373.74  5162.5  373.62
  5282.9  374.84  5318.2  377.32  5367.8  379.52  5452.8  380.38  5475.3  381.56
#Mann= 5 ,-1 , 0
  4693.3    .035       0    4799     .12       0  4989.7     .06       0
  4994.6     .12       0  5318.2     .16       0
Bank Sta=4989.7,4994.6
XS Rating Curve= 0 ,0
Exp/Cntr=0.3,0.1

Type RM Length L Ch R = 1 ,10036   ,426,426,426
BEGIN DESCRIPTION:
Stream0465 20.0
END DESCRIPTION:
XS GIS Cut Line= 3
      2531705.36     13744725.24      2531727.85       13745073.
      2532141.39     13745621.98
#Sta/Elev= 30
  4573.5  379.71  4619.5  378.88  4799.6  373.83  4810.1  372.54    4914  370.08
  4936.5  370.79  4949.5  369.13  4957.3  369.87  4963.6  363.62  4971.9  363.75
  4978.1  361.14  4986.4   361.6  5019.4  359.15  5019.7  358.65  5024.3  359.15
  5028.1  360.47  5036.4  366.73  5042.7  369.29  5063.5  371.71  5092.6  371.24
  5107.2  368.59  5136.3  371.22  5149.8  369.16  5157.2  370.02  5163.4  368.77
  5171.7  370.64  5208.9  372.93  5263.4  375.95  5442.4  378.42  5609.3  382.61
#Mann= 6 ,-1 , 0
  4573.5     .07       0  4619.5    .035       0  4810.1     .12       0
  5019.4     .06       0  5024.3     .12       0  5208.9     .16       0
Bank Sta=5019.4,5024.3
XS Rating Curve= 0 ,0
Exp/Cntr=0.3,0.1

Type RM Length L Ch R = 1 ,9610    ,492,492,492
BEGIN DESCRIPTION:
Stream0465 19.0
END DESCRIPTION:
XS GIS Cut Line= 3
      2531571.46     13744868.94      2531563.51     13745478.54
      2531790.75     13745726.92
#Sta/Elev= 30
  4394.3  375.67  4460.4  374.98  4500.4  372.96    4588  372.66  4680.4  371.38
  4700.4  372.16  4750.4   368.7  4770.4  366.12  4784.8  366.21  4820.4     368
  4900.4   365.6  4950.4  365.62  4970.4  363.09  4981.6  358.48  4987.9  357.86
  4988.3  357.36  4992.9  357.86  4999.7  360.65    5004  360.65  5009.7  364.08
  5016.5  364.44  5023.9  367.35  5030.7  367.19  5038.1  368.99  5052.3  370.12
  5073.3   370.7  5094.2     374  5109.9  374.08  5149.1  374.99  5340.6  381.88
#Mann= 8 ,-1 , 0
  4394.3    .035       0    4588     .16       0  4784.8     .12       0
  4981.6     .07       0  4987.9     .06       0  4992.9     .07       0
  5109.9     .16       0  5149.1     .07       0
Bank Sta=4987.9,4992.9
XS Rating Curve= 0 ,0
Exp/Cntr=0.3,0.1

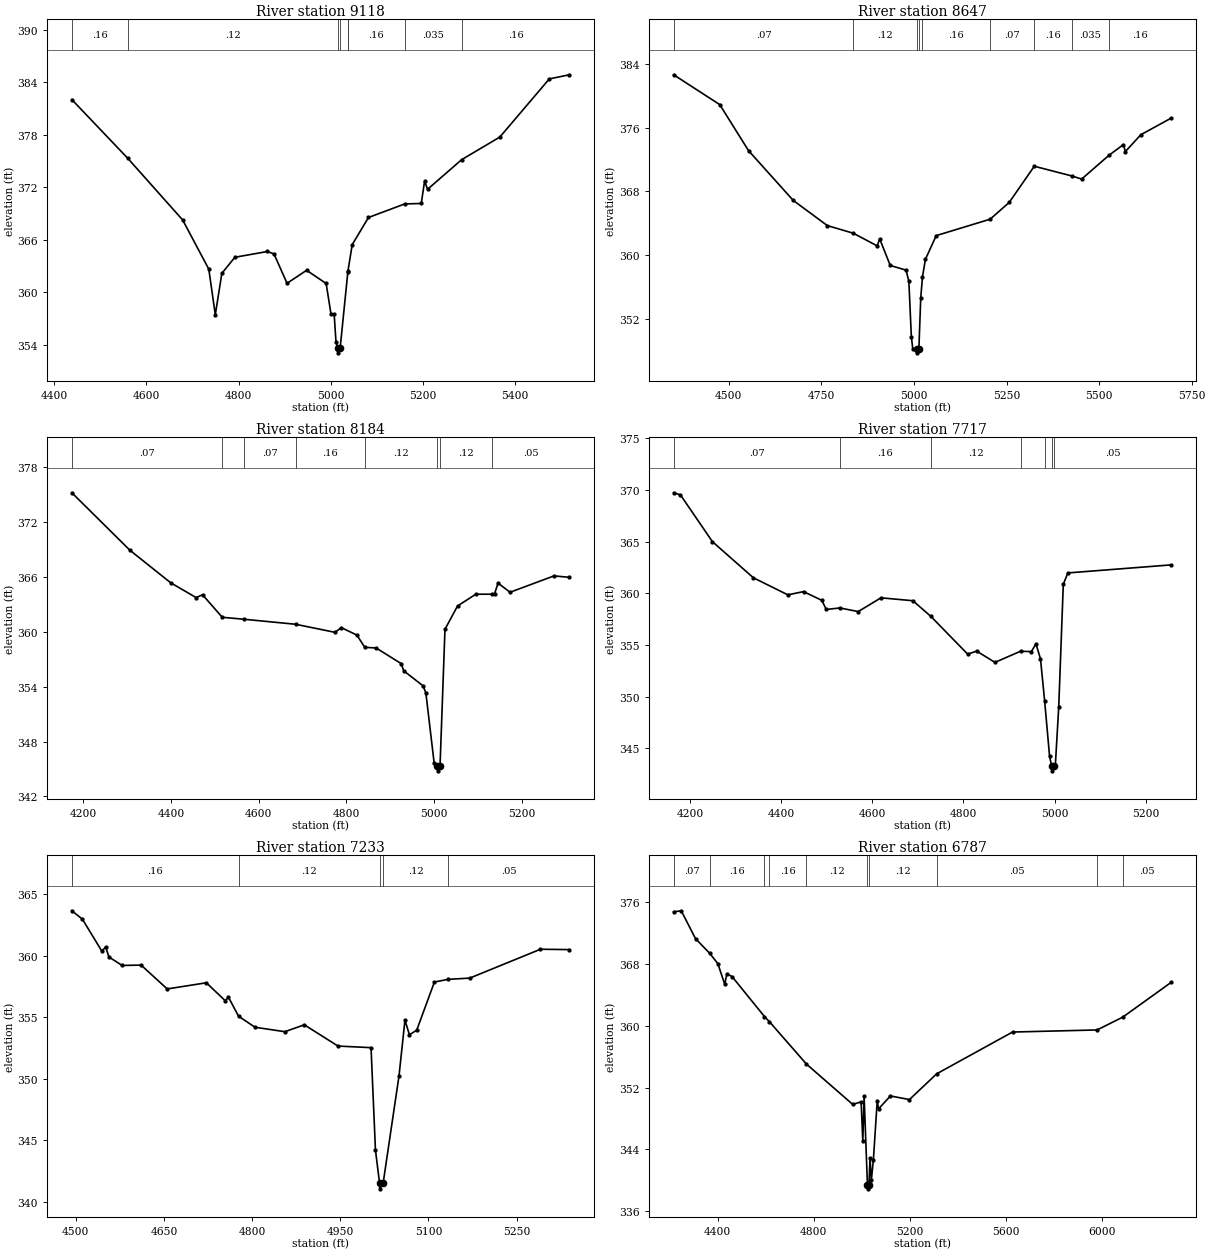
Type RM Length L Ch R = 1 ,9118    ,471,471,471
BEGIN DESCRIPTION:
Stream0465 18.0
END DESCRIPTION:
XS GIS Cut Line= 3
        2530925.       13745325.        2531325.       13745725.
      2531725.93      13746045.7
#Sta/Elev= 30
  4438.5  382.04  4559.2  375.36  4678.9  368.27  4735.5  362.65  4749.6  357.44
  4763.8  362.17  4792.1  364.01  4862.8  364.67  4876.9  364.39  4905.2  361.03
  4947.6  362.52    4990  361.01  5000.6  357.49  5007.4  357.49  5011.4  354.29
  5015.3  353.58  5015.7  353.08  5020.3  353.58  5037.1  362.35  5037.2  362.41
  5046.6  365.46  5081.8  368.56  5160.5  370.11  5196.3  370.16  5203.5  372.72
  5209.9  371.78  5283.8  375.17  5366.8  377.76    5474  384.41  5517.6  384.88
#Mann= 8 ,-1 , 0
  4438.5     .16       0  4559.2     .12       0  5015.3     .06       0
  5020.3     .12       0  5037.1     .07       0  5037.2     .16       0
  5160.5    .035       0  5283.8     .16       0
Bank Sta=5015.3,5020.3
XS Rating Curve= 0 ,0
Exp/Cntr=0.3,0.1

Type RM Length L Ch R = 1 ,8647    ,463,463,463
BEGIN DESCRIPTION:
Stream0465 17.0
END DESCRIPTION:
XS GIS Cut Line= 3
      2530598.79      13745535.6        2531025.       13746025.
        2531700.     13746189.37
#Sta/Elev= 30
  4351.1  382.62  4475.5  378.88  4553.4   373.1  4673.9  366.87    4766  363.71
  4836.2  362.75  4900.9  361.16  4907.5  362.05    4936  358.71  4978.7  358.12
  4986.3   356.7    4993  349.75  4996.8  348.28  5007.4  348.25  5007.9  347.75
  5013.3  348.25  5018.4  354.67  5023.1  357.29    5031  359.48  5060.1  362.45
  5205.8  364.51  5257.4  366.62    5325  371.15  5425.7  369.94  5452.9  369.54
  5526.3  372.51  5565.8  373.87    5571  372.99  5612.7   375.1  5694.8  377.19
#Mann= 9 ,-1 , 0
  4351.1     .07       0  4836.2     .12       0  5007.4     .06       0
  5013.3     .12       0  5023.1     .16       0  5205.8     .07       0
    5325     .16       0  5425.7    .035       0  5526.3     .16       0
Bank Sta=5007.4,5013.3
XS Rating Curve= 0 ,0
Exp/Cntr=0.3,0.1

Type RM Length L Ch R = 1 ,8184    ,467,467,467
BEGIN DESCRIPTION:
Stream0465 16.0
END DESCRIPTION:
XS GIS Cut Line= 4
      2530578.24     13745716.65      2530725.43      13746281.4
        2530925.       13746425.      2531120.12     13746659.84
#Sta/Elev= 30
  4174.3  375.15  4306.9  368.87  4399.9  365.32  4457.8  363.71  4472.3  364.02
  4517.4  361.56    4566  361.35  4684.4   360.8  4774.3  359.92    4789  360.43
  4824.6  359.61  4842.3  358.28  4868.3  358.21  4925.2  356.51  4931.4  355.71
  4975.5  354.07  4981.7   353.3  5000.7  345.62  5007.8   345.3  5008.3   344.8
    5014   345.3  5025.3  360.25  5053.9  362.79  5095.6  364.08  5131.8  364.08
  5138.5  364.15  5146.4  365.29  5173.7  364.29    5274  366.08  5309.1  365.92
#Mann= 8 ,-1 , 0
  4174.3     .07       0  4517.4     .16       0    4566     .07       0
  4684.4     .16       0  4842.3     .12       0  5007.8     .06       0
    5014     .12       0  5131.8     .05       0
Bank Sta=5007.8,5014
XS Rating Curve= 0 ,0
Exp/Cntr=0.3,0.1

Type RM Length L Ch R = 1 ,7717    ,484,484,484
BEGIN DESCRIPTION:
Stream0465 15.0
END DESCRIPTION:
XS GIS Cut Line= 3
      2530553.55     13745840.02        2530575.       13746675.
      2530582.72     13746931.83
#Sta/Elev= 30
  4163.9  369.74  4178.9  369.53  4248.9  365.01  4338.9  361.51  4414.5  359.86
    4449  360.17    4489  359.33    4499  358.44  4528.5  358.59    4569  358.24
    4619  359.57  4689.1  359.29  4728.5  357.77  4809.3  354.12  4829.1  354.41
  4869.1  353.32  4925.5   354.4  4949.1  354.36  4959.1  355.12  4969.1  353.67
  4978.3  349.55  4989.1  344.21  4993.5  343.32    4994  342.82  4999.8  343.32
  5001.7  343.32  5009.2  349.03  5019.2  360.88  5029.2  361.98  5256.1  362.76
#Mann= 7 ,-1 , 0
  4163.9     .07       0  4528.5     .16       0  4728.5     .12       0
  4925.5     .16       0  4978.3     .05       0  4993.5     .06       0
  4999.8     .05       0
Bank Sta=4993.5,4999.8
XS Rating Curve= 0 ,0
Exp/Cntr=0.3,0.1

Type RM Length L Ch R = 1 ,7233    ,446,446,446
BEGIN DESCRIPTION:
Stream0465 14.0
END DESCRIPTION:
XS GIS Cut Line= 3
      2530495.31      13745968.9        2530275.       13746425.
      2530299.16     13746764.12
#Sta/Elev= 30
  4493.4  363.67  4511.3  362.99  4544.6  360.37  4550.9  360.74  4556.4  359.91
    4579  359.22  4611.2  359.25  4655.6  357.31  4722.3  357.81  4754.3  356.35
  4759.8  356.64    4777  355.09    4805  354.19  4855.8  353.83  4888.9  354.39
  4946.2  352.66  5002.4  352.53  5009.9   344.2  5016.8  341.54  5017.3  341.04
  5023.1  341.54    5050  350.24  5060.1  354.77  5067.7  353.58  5080.1  353.95
  5110.2  357.87  5133.4  358.09  5170.3  358.19  5290.7  360.54  5339.9  360.51
#Mann= 5 ,-1 , 0
  4493.4     .16       0    4777     .12       0  5016.8     .06       0
  5023.1     .12       0  5133.4     .05       0
Bank Sta=5016.8,5023.1
XS Rating Curve= 0 ,0
Exp/Cntr=0.3,0.1

Type RM Length L Ch R = 1 ,6787    ,469,469,469
BEGIN DESCRIPTION:
Stream0465 13.0
END DESCRIPTION:
XS GIS Cut Line= 3
      2530232.68     13745461.57        2529925.       13746175.
      2530388.48     13747381.27
#Sta/Elev= 30
  4217.5  374.75    4249  374.88  4308.4  371.27  4367.3  369.38    4401  368.05
  4429.9  365.38    4439  366.74  4460.8  366.35  4595.2  361.19  4615.7  360.53
  4769.5  355.05  4961.9  349.83  4997.1  350.15  5004.1  345.11  5009.5  350.87
  5023.4   339.4  5023.9   338.9  5029.7   339.4  5034.1  342.87  5039.5  339.98
    5048  342.62  5064.1  350.32  5069.5  349.24  5118.8  350.92    5198  350.45
  5311.1  353.78  5626.8  359.19  5978.6  359.46  6085.2  361.12  6286.7  365.62
#Mann= 10 ,-1 , 0
  4217.5     .07       0  4367.3     .16       0  4595.2     .07       0
  4615.7     .16       0  4769.5     .12       0  5023.4     .06       0
  5029.7     .12       0  5311.1     .05       0  5978.6    .035       0
  6085.2     .05       0
Bank Sta=5023.4,5029.7
XS Rating Curve= 0 ,0
Exp/Cntr=0.3,0.1

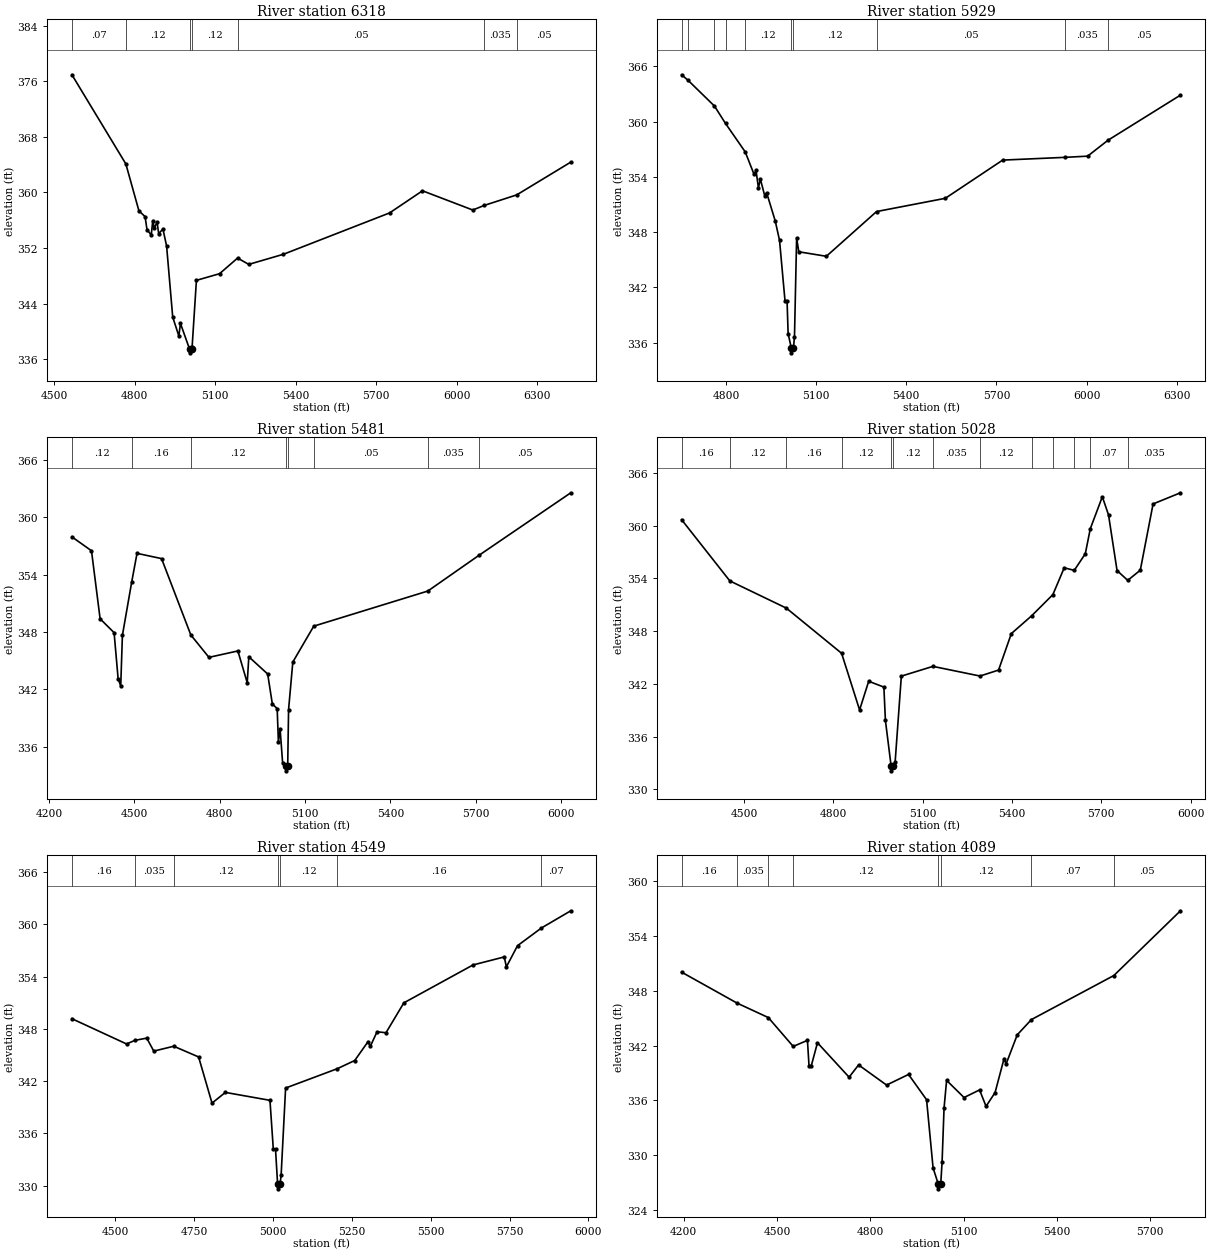
Type RM Length L Ch R = 1 ,6318    ,389,389,389
BEGIN DESCRIPTION:
Stream0465 12.0
END DESCRIPTION:
XS GIS Cut Line= 3
      2529323.74     13745796.63      2529564.94     13746231.32
      2530330.71      13747356.9
#Sta/Elev= 30
  4566.1  376.95    4767  364.11  4815.8  357.34  4838.7  356.52  4845.7  354.66
  4861.6  353.86  4867.4  355.95  4873.1  354.83  4883.4  355.75  4889.2  354.08
  4905.2  354.72  4918.8  352.29  4941.6  342.05  4964.5  339.32  4970.4  341.14
  5004.7   337.4  5005.2   336.9  5011.7   337.4  5013.9  337.76  5029.9  347.34
  5116.1   348.3  5183.3  350.55  5224.9  349.64  5354.3   351.1  5749.4  357.05
  5872.1  360.24  6059.5  357.47  6101.8  358.13  6223.2  359.65  6424.6  364.37
#Mann= 7 ,-1 , 0
  4566.1     .07       0    4767     .12       0  5004.7     .06       0
  5011.7     .12       0  5183.3     .05       0  6101.8    .035       0
  6223.2     .05       0
Bank Sta=5004.7,5011.7
XS Rating Curve= 0 ,0
Exp/Cntr=0.3,0.1

Type RM Length L Ch R = 1 ,5929    ,448,448,448
BEGIN DESCRIPTION:
Stream0465 11.0
END DESCRIPTION:
XS GIS Cut Line= 3
      2529056.05     13746204.84        2529325.       13746425.
      2530249.11     13747357.91
#Sta/Elev= 30
  4652.1   365.1  4673.9  364.49  4761.5   361.7  4798.3  359.81  4863.9  356.72
  4893.4  354.27  4899.9  354.72  4907.8  352.81  4914.3  353.77  4928.6  351.98
  4935.1  352.29  4963.8  349.22  4978.1  347.11  4996.4  340.51  5003.2  340.51
  5006.7  336.98  5017.4  335.39  5017.9  334.89  5024.4  335.39  5027.9  336.66
    5035  347.39  5042.1  345.87    5134  345.38  5301.1  350.24    5530  351.68
  5720.9  355.83    5929  356.13  6003.8  356.26  6071.6  357.99  6312.8  362.89
#Mann= 10 ,-1 , 0
  4652.1     .07       0  4673.9     .16       0  4761.5     .12       0
  4798.3     .07       0  4863.9     .12       0  5017.4     .06       0
  5024.4     .12       0  5301.1     .05       0    5929    .035       0
  6071.6     .05       0
Bank Sta=5017.4,5024.4
XS Rating Curve= 0 ,0
Exp/Cntr=0.3,0.1

Type RM Length L Ch R = 1 ,5481    ,453,453,453
BEGIN DESCRIPTION:
Stream0465 10.0
END DESCRIPTION:
XS GIS Cut Line= 4
      2528710.66     13746403.59      2529109.67     13746662.74
        2529325.       13746775.      2530175.13     13747366.19
#Sta/Elev= 30
  4280.2  357.94    4349  356.49  4379.3  349.38  4428.5  347.93  4442.6  343.13
  4451.8  342.35  4457.7  347.65  4490.3  353.21  4509.1  356.22  4595.4  355.67
  4698.3  347.69    4762  345.35  4863.7  346.02  4896.6   342.7  4902.2  345.41
  4968.5  343.61  4984.9  340.48  5001.9  339.99  5006.2  336.49  5012.3  337.82
  5021.1  334.31  5031.9  333.99  5032.4  333.49  5038.9  333.99    5042   339.9
  5056.9  344.86  5130.5  348.61  5531.6  352.28  5711.3  356.01  6034.3  362.55
#Mann= 8 ,-1 , 0
  4280.2     .12       0  4490.3     .16       0  4698.3     .12       0
  5031.9     .06       0  5038.9     .12       0  5130.5     .05       0
  5531.6    .035       0  5711.3     .05       0
Bank Sta=5031.9,5038.9
XS Rating Curve= 0 ,0
Exp/Cntr=0.3,0.1

Type RM Length L Ch R = 1 ,5028    ,479,479,479
BEGIN DESCRIPTION:
Stream0465 9.0
END DESCRIPTION:
XS GIS Cut Line= 4
      2528451.46     13746605.12        2528775.       13746925.
        2529025.       13746975.       2529763.7      13747596.5
#Sta/Elev= 30
  4290.4  360.69  4452.3  353.72  4642.2  350.62  4827.7  345.48  4888.1  339.03
  4918.7   342.3  4969.7  341.63  4974.8  337.84  4994.2   332.6  4994.7   332.1
  5001.3   332.6  5007.5  333.11  5028.3  342.88  5134.4  343.99  5292.6  342.89
  5354.8  343.57  5397.7  347.72    5466  349.75  5537.2  352.16  5575.3  355.21
    5609  354.92  5646.1  356.81  5662.9  359.66  5703.3   363.3  5724.1  361.23
  5752.7   354.9  5788.6  353.78  5830.8  354.94  5873.7  362.48  5965.7  363.75
#Mann= 13 ,-1 , 0
  4290.4     .16       0  4452.3     .12       0  4642.2     .16       0
  4827.7     .12       0  4994.2     .06       0  5001.3     .12       0
  5134.4    .035       0  5292.6     .12       0    5466     .16       0
  5537.2     .07       0    5609     .16       0  5662.9     .07       0
  5788.6    .035       0
Bank Sta=4994.2,5001.3
XS Rating Curve= 0 ,0
Exp/Cntr=0.3,0.1

Type RM Length L Ch R = 1 ,4549    ,460,460,460
BEGIN DESCRIPTION:
Stream0465 8.0
END DESCRIPTION:
XS GIS Cut Line= 4
      2528418.59     13746880.76        2528625.       13747175.
        2528825.       13747375.      2529508.59     13748020.13
#Sta/Elev= 30
    4362  349.17  4535.3  346.27  4562.2  346.69  4599.3  346.94  4621.6  345.45
  4684.9  346.01  4763.8  344.78  4806.3  339.48  4848.7  340.71  4990.1   339.8
  5000.7   334.2  5007.7   334.2  5014.4  330.14  5014.9  329.64    5022  330.14
  5025.5  331.21  5039.7  341.21  5203.5  343.43  5258.9  344.37  5301.4  346.55
  5308.3  345.99  5329.7  347.67  5358.1  347.56  5414.7  350.99    5634  355.34
    5733  356.26    5740  355.13  5775.2  357.55  5850.9  359.58  5944.2  361.56
#Mann= 7 ,-1 , 0
    4362     .16       0  4562.2    .035       0  4684.9     .12       0
  5014.4     .06       0    5022     .12       0  5203.5     .16       0
  5850.9     .07       0
Bank Sta=5014.4,5022
XS Rating Curve= 0 ,0
Exp/Cntr=0.3,0.1

Type RM Length L Ch R = 1 ,4089    ,594,594,594
BEGIN DESCRIPTION:
XS6865
END DESCRIPTION:
XS GIS Cut Line= 3
      2528357.03     13746865.21      2528473.42     13747505.33
      2529054.65     13748260.93
#Sta/Elev= 30
  4193.1  350.01  4371.4  346.63  4471.9  345.05  4551.9   341.9  4597.7  342.56
  4602.8  339.76  4609.6  339.73  4629.9   342.3  4731.6  338.54  4762.1  339.88
  4852.1  337.68  4922.7  338.84  4980.7  336.08  5001.6  328.64  5018.5  326.85
    5019  326.35  5026.2  326.85  5030.6  329.31  5036.9  335.17  5045.1  338.19
  5101.2  336.32  5151.1  337.15  5171.9  335.36  5200.9  336.86  5229.9  340.58
  5236.2  339.97  5272.3  343.17  5317.7  344.83  5582.8  349.64    5797  356.71
#Mann= 8 ,-1 , 0
  4193.1     .16       0  4371.4    .035       0  4471.9     .16       0
  4551.9     .12       0  5018.5     .06       0  5026.2     .12       0
  5317.7     .07       0  5582.8     .05       0
Bank Sta=5018.5,5026.2
XS Rating Curve= 0 ,0
Exp/Cntr=0.3,0.1

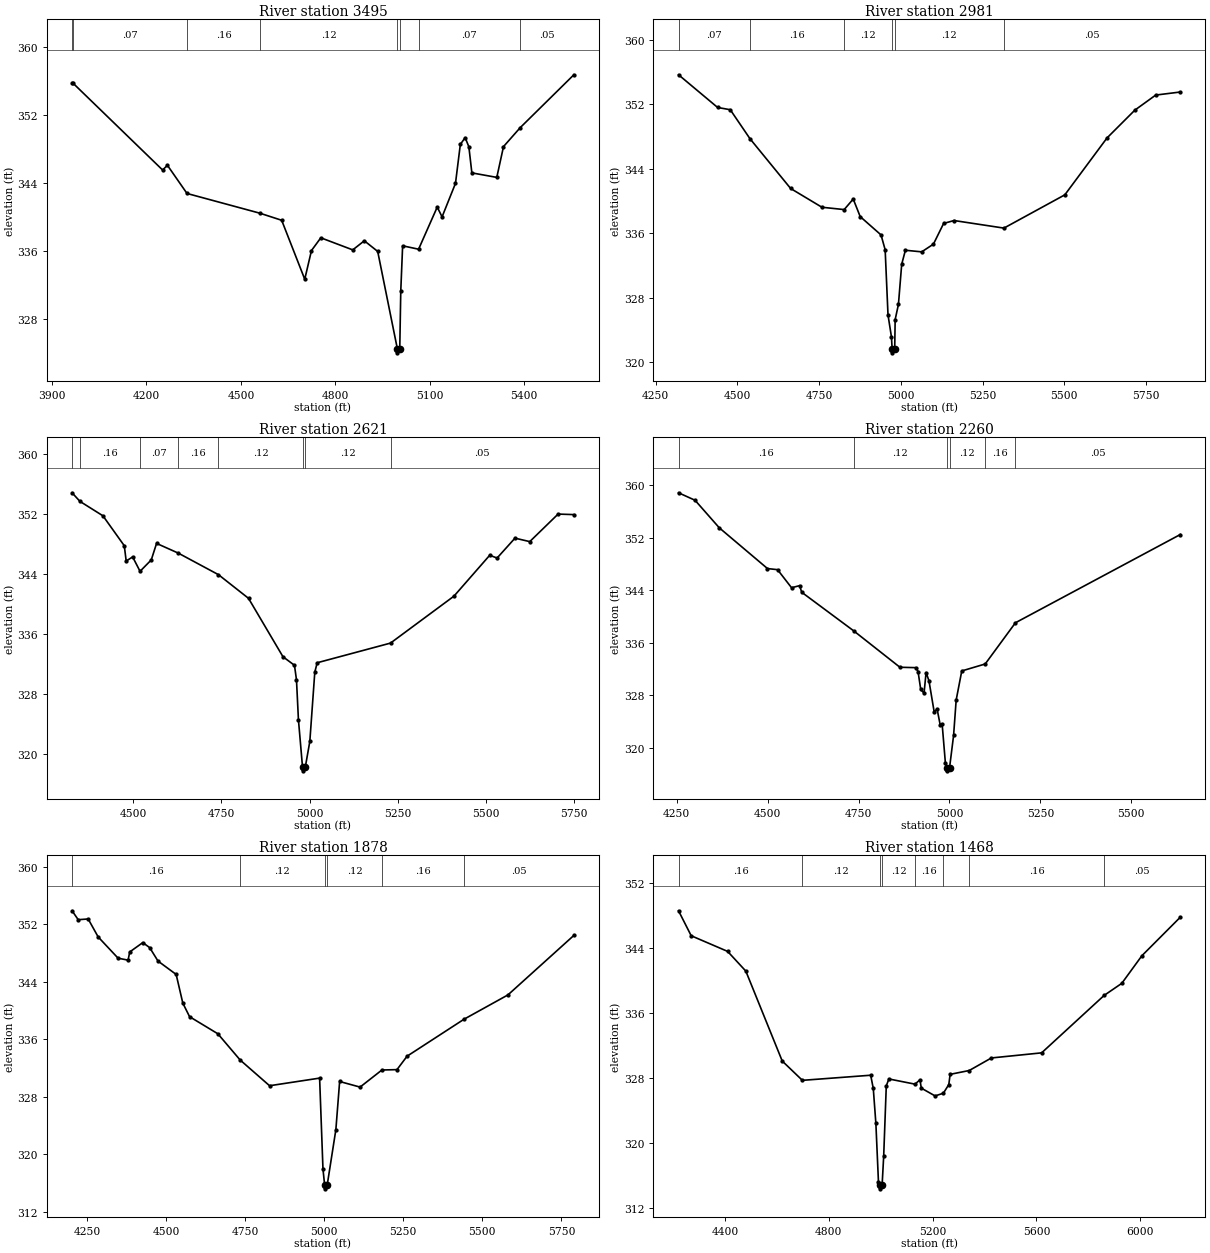
Type RM Length L Ch R = 1 ,3495    ,514,514,514
BEGIN DESCRIPTION:
XS6864
END DESCRIPTION:
XS GIS Cut Line= 2
      2527990.42     13747132.91      2528828.38     13748488.77
#Sta/Elev= 30
  3963.6  355.78  3965.3  355.78  4251.1  345.53  4266.5  346.08  4328.7  342.77
  4560.3  340.45  4629.4  339.62  4702.7  332.69    4724  336.06  4753.7  337.56
  4855.2  336.14  4891.9  337.21  4934.4  335.96  4996.7  324.54  4997.2  324.04
  5004.5  324.54  5007.7  331.32  5013.6  336.62  5064.3  336.22  5123.5  341.17
  5138.9  340.02  5181.5  343.96  5196.9  348.54  5212.2  349.33    5224  348.26
  5233.5  345.19  5312.7  344.66    5334  348.28  5387.2  350.51  5557.5  356.72
#Mann= 8 ,-1 , 0
  3963.6    .035       0  3965.3     .07       0  4328.7     .16       0
  4560.3     .12       0  4996.7     .06       0  5004.5     .12       0
  5064.3     .07       0  5387.2     .05       0
Bank Sta=4996.7,5004.5
XS Rating Curve= 0 ,0
Exp/Cntr=0.3,0.1

Type RM Length L Ch R = 1 ,2981    ,360,360,360
BEGIN DESCRIPTION:
XS6863
END DESCRIPTION:
XS GIS Cut Line= 2
       2527955.5     13747272.57      2528479.25     13748715.78
#Sta/Elev= 30
  4319.9  355.67  4439.5  351.61  4478.2  351.33  4538.5  347.73  4662.9  341.55
  4758.6  339.22  4826.7  338.93  4854.4  340.24  4875.7  338.06  4939.5  335.78
  4952.1  333.94  4960.8  325.85  4971.4   323.1  4973.4  321.64  4973.9  321.14
  4981.3  321.64  4982.7  325.27  4992.7  327.15  5002.7  332.14    5014  333.88
  5063.9  333.68  5099.8  334.64    5131  337.21  5162.9  337.57  5315.5  336.63
  5501.8  340.76    5631  347.83  5716.1  351.28  5779.9  353.15  5855.2  353.53
#Mann= 6 ,-1 , 0
  4319.9     .07       0  4538.5     .16       0  4826.7     .12       0
  4973.4     .06       0  4981.3     .12       0  5315.5     .05       0
Bank Sta=4973.4,4981.3
XS Rating Curve= 0 ,0
Exp/Cntr=0.3,0.1

Type RM Length L Ch R = 1 ,2621    ,361,361,361
BEGIN DESCRIPTION:
XS6862
END DESCRIPTION:
XS GIS Cut Line= 3
        2527682.     13747534.46      2527938.04     13748139.64
       2528374.5     13748768.14
#Sta/Elev= 30
  4326.5  354.86  4348.9  353.71    4414  351.79  4474.5   347.8  4479.9  345.76
  4498.2  346.31  4519.2  344.39    4551  345.91    4566  348.11  4627.4  346.82
  4741.5  343.94  4826.6  340.79  4924.3     333  4956.9  331.86  4962.6  329.92
  4968.1  324.62  4979.7  318.29  4980.2  317.79  4987.6  318.29  5000.4  321.71
  5014.5  330.95  5021.3   332.2  5229.1  334.82    5409  341.08  5510.3  346.53
  5531.2  346.16  5581.9  348.81  5623.8  348.35  5704.1  352.02  5748.8  351.95
#Mann= 8 ,-1 , 0
  4326.5     .07       0  4348.9     .16       0  4519.2     .07       0
  4627.4     .16       0  4741.5     .12       0  4979.7     .06       0
  4987.6     .12       0  5229.1     .05       0
Bank Sta=4979.7,4987.6
XS Rating Curve= 0 ,0
Exp/Cntr=0.3,0.1

Type RM Length L Ch R = 1 ,2260    ,382,382,382
BEGIN DESCRIPTION:
XS6861
END DESCRIPTION:
XS GIS Cut Line= 3
      2527356.08     13747714.78      2527769.28     13748506.26
      2528164.03     13748790.71
#Sta/Elev= 30
  4255.2  358.81  4300.6  357.67  4367.2  353.48  4499.7  347.28  4527.4  347.11
  4565.9  344.36    4588  344.68  4593.9  343.67  4736.5  337.81  4863.8  332.26
    4908   332.2  4913.6  331.61    4921  328.88  4930.1  328.32  4935.7  331.46
  4943.6  330.21  4957.8  325.51  4966.1  325.88  4974.3  323.54  4979.9  323.59
  4988.7  317.74  4992.3     317  4992.8   316.5  5000.3     317  5011.3  321.88
  5018.4  327.27  5033.8   331.7  5098.2  332.76  5181.3  339.03  5634.6  352.46
#Mann= 6 ,-1 , 0
  4255.2     .16       0  4736.5     .12       0  4992.3     .06       0
  5000.3     .12       0  5098.2     .16       0  5181.3     .05       0
Bank Sta=4992.3,5000.3
XS Rating Curve= 0 ,0
Exp/Cntr=0.3,0.1

Type RM Length L Ch R = 1 ,1878    ,410,410,410
BEGIN DESCRIPTION:
XS6860
END DESCRIPTION:
XS GIS Cut Line= 3
      2527123.34     13747773.06      2527396.84     13748587.73
      2528081.79     13748831.53
#Sta/Elev= 30
  4202.9  353.88  4222.3  352.64  4253.8  352.74  4285.4  350.24  4348.4  347.28
    4380  347.01  4385.2  348.15  4426.5  349.45  4448.3  348.75  4474.6  346.88
    4532  345.02    4553  341.03  4574.4  339.14  4663.8  336.76  4734.3  333.11
  4827.3  329.53  4985.5  330.59  4996.1  317.96  5001.4  315.68  5001.9  315.18
  5009.4  315.68  5036.9  323.42  5048.8  330.12  5113.4  329.34  5182.5  331.72
  5230.1  331.77    5262  333.64  5442.2  338.79  5580.9  342.17  5789.3  350.45
#Mann= 6 ,-1 , 0
  4202.9     .16       0  4734.3     .12       0  5001.4     .06       0
  5009.4     .12       0  5182.5     .16       0  5442.2     .05       0
Bank Sta=5001.4,5009.4
XS Rating Curve= 0 ,0
Exp/Cntr=0.3,0.1

Type RM Length L Ch R = 1 ,1468    ,603,603,603
BEGIN DESCRIPTION:
XS6859
END DESCRIPTION:
XS GIS Cut Line= 3
      2526931.29     13747796.26      2526989.48      13748669.2
      2528030.57     13748861.13
#Sta/Elev= 30
  4221.1   348.6  4269.9  345.52  4410.3  343.59  4480.4  341.16  4620.7  330.07
  4698.3  327.69  4961.5  328.32  4971.5  326.69  4981.5  322.37  4991.5  315.13
  4997.6  314.81  4998.1  314.31  5005.6  314.81  5011.6  318.34  5021.6  327.01
  5031.6  327.86  5132.3  327.22  5151.4  327.76  5156.5  326.73  5209.5  325.77
  5241.5   326.1  5262.5  327.17  5267.6  328.43  5341.1   328.9  5426.6  330.45
  5620.2  331.08  5861.3  338.17    5929  339.65  6006.6  343.06  6154.6  347.81
#Mann= 8 ,-1 , 0
  4221.1     .16       0  4698.3     .12       0  4997.6     .06       0
  5005.6     .12       0  5132.3     .16       0  5241.5     .07       0
  5341.1     .16       0  5861.3     .05       0
Bank Sta=4997.6,5005.6
XS Rating Curve= 0 ,0
Exp/Cntr=0.3,0.1

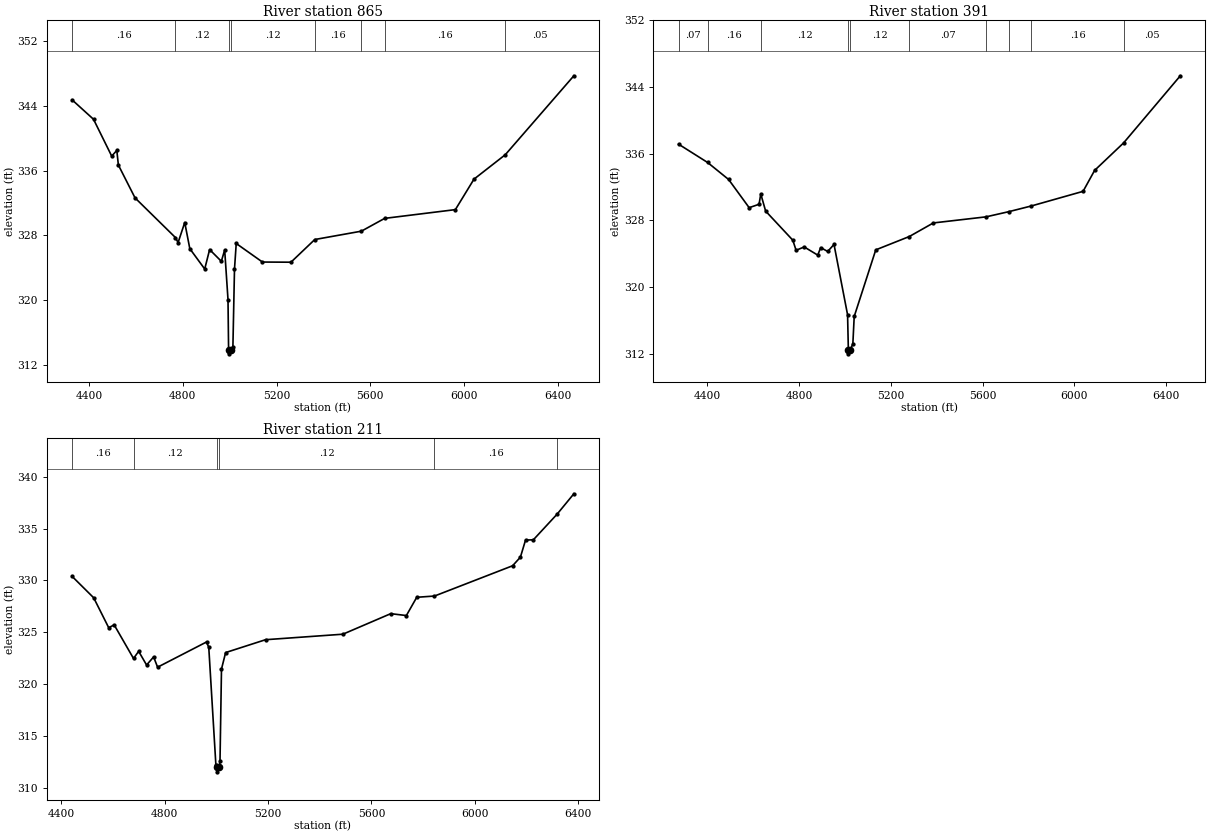
Type RM Length L Ch R = 1 ,865     ,474,474,474
BEGIN DESCRIPTION:
XS6858
END DESCRIPTION:
XS GIS Cut Line= 3
      2526099.11     13748151.27      2526669.42     13748663.38
      2528025.29     13748896.15
#Sta/Elev= 30
  4327.2  344.74  4418.8  342.34  4496.5  337.79  4518.2   338.5  4524.9  336.69
    4596  332.64  4768.6  327.74  4779.8  327.12  4808.2   329.6  4829.9  326.37
  4893.5  323.86  4914.4  326.26  4964.5  324.81  4978.7  326.21  4992.9  320.09
  4995.4  313.89  4995.9  313.39  5003.8  313.89  5013.8  314.23  5020.6  323.84
    5028  327.01  5139.9  324.72  5261.7   324.7  5363.4   327.5  5562.3  328.53
  5661.7  330.11  5963.6  331.19    6043  334.95  6176.8  337.97  6469.4  347.71
#Mann= 8 ,-1 , 0
  4327.2     .16       0  4768.6     .12       0  4995.4     .06       0
  5003.8     .12       0  5363.4     .16       0  5562.3     .07       0
  5661.7     .16       0  6176.8     .05       0
Bank Sta=4995.4,5003.8
XS Rating Curve= 0 ,0
Exp/Cntr=0.3,0.1

Type RM Length L Ch R = 1 ,391     ,180,180,180
BEGIN DESCRIPTION:
XS6857
END DESCRIPTION:
XS GIS Cut Line= 4
      2526075.82     13748465.49      2526308.62     13748872.88
      2526605.41      13749059.1      2527967.16     13748942.71
#Sta/Elev= 30
  4275.2  337.13  4401.9  334.93  4493.5  332.89  4582.9  329.51  4626.1  329.92
  4633.5  331.16  4654.7   329.1  4773.1  325.61  4787.4   324.4  4822.8   324.8
  4881.8  323.82  4894.5  324.72  4925.1  324.26  4952.6   325.1  5011.7  316.67
  5015.1  312.48  5015.6  311.98  5023.6  312.48  5034.7  313.17  5040.6  316.46
  5134.5  324.45  5280.7  326.05  5385.4  327.68  5614.9  328.41  5713.9  329.03
    5813  329.72  6037.8  331.47    6088  333.98  6214.4  337.28  6461.5  345.33
#Mann= 10 ,-1 , 0
  4275.2     .07       0  4401.9     .16       0  4633.5     .12       0
  5015.1     .06       0  5023.6     .12       0  5280.7     .07       0
  5614.9     .16       0  5713.9     .07       0    5813     .16       0
  6214.4     .05       0
Bank Sta=5015.1,5023.6
XS Rating Curve= 0 ,0
Exp/Cntr=0.3,0.1

Type RM Length L Ch R = 1 ,211     ,0,0,0
BEGIN DESCRIPTION:
E21055
END DESCRIPTION:
XS GIS Cut Line= 5
      2526065.59     13748719.54      2526283.62     13749073.31
      2526497.53     13749192.61      2527069.32     13749114.45
       2527771.4     13749065.18
#Sta/Elev= 30
    4442   330.4  4525.7  328.33  4583.7  325.45  4604.9  325.72  4679.7  322.48
  4699.6  323.17  4730.3  321.85  4757.5  322.63  4772.9  321.64  4962.2  324.07
  4970.9  323.55  4998.4  312.22  5003.7  312.05  5004.2  311.55  5012.2  312.05
  5014.4  312.63  5020.1  321.46  5036.1  323.05  5190.6  324.29  5489.7  324.82
  5674.9   326.8  5735.4  326.62  5775.5  328.38  5844.2   328.5  6146.4  331.42
  6176.6  332.25  6196.5   333.9  6226.6  333.92  6318.4  336.39  6383.4  338.36
#Mann= 6 ,-1 , 0
    4442     .16       0  4679.7     .12       0  5003.7     .06       0
  5012.2     .12       0  5844.2     .16       0  6318.4     .05       0
Bank Sta=5003.7,5012.2
XS Rating Curve= 0 ,0
Exp/Cntr=0.3,0.1

Chan Stop Cuts=-1
Use User Specified Reach Order=0
Composite Channel Slope=5