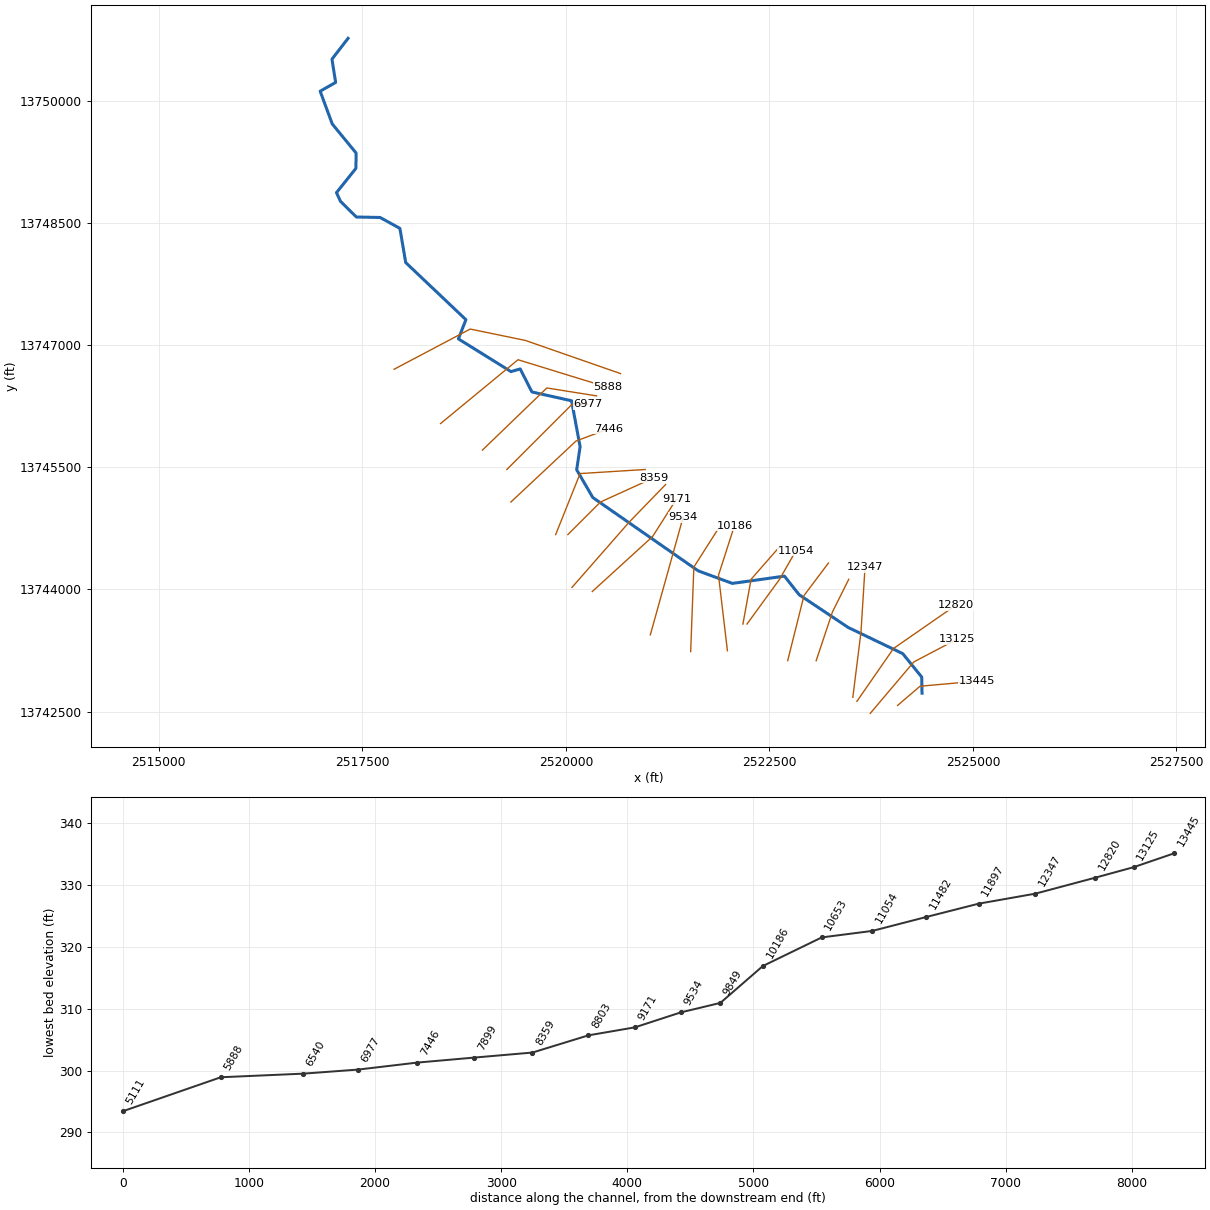
--- Stream0466.prj (project) ---

Proj Title=Stream0466 Base Level Engineering
Current Plan=p01
Default Exp/Contr=0.3,0.1
English Units
Geom File=g01
Flow File=f01
Plan File=p01
BEGIN DESCRIPTION:
Stream0466
END DESCRIPTION:

--- Stream0466.p01 (plan) ---

Plan Title=Multiple Run
Short Identifier=Multiple
Geom File=g01
Flow File=f01
Subcritical Flow
K Sum by GR= 0
Std Step Tol= 0.01
Critical Tol= 0.01
Num of Std Step Trials= 20
Max Error Tol= 0.3
Flow Tol Ratio= 0.001
Split Flow NTrial= 30
Split Flow Tol= 0.02
Split Flow Ratio= 0.02
Log Output Level= 0
Friction Slope Method= 1
Unsteady Friction Slope Method= 2
Unsteady Bridges Friction Slope Method= 1
Parabolic Critical Depth
Global Vel Dist=  1 , 1 , 1
Global Log Level= 0
CheckData=True
Encroach Param= -1, 0, 0, 0
BEGIN DESCRIPTION:
Multiple Run
END DESCRIPTION:

--- Stream0466.f01 (steady flow) ---

Flow Title=Multiple
Number of Profiles=7
Profile Names=10-year,25-year,50-year,1pct_min,100-year,1pct_plu,500-year
River Rch & RM= Stream0466,Reach-1,13445
    1014    1687    2316    1541    3075    6135    5362
River Rch & RM= Stream0466,Reach-1,11897
    1300    2179    3006    2006    4002    7985    7025
Boundary for River Rch & Prof#=Stream0466,Reach-1,1
Up Type=0
Dn Type=3
Dn Slope=0.005
Boundary for River Rch & Prof#=Stream0466,Reach-1,2
Up Type=0
Dn Type=3
Dn Slope=0.005
Boundary for River Rch & Prof#=Stream0466,Reach-1,3
Up Type=0
Dn Type=3
Dn Slope=0.005
Boundary for River Rch & Prof#=Stream0466,Reach-1,4
Up Type=0
Dn Type=3
Dn Slope=0.005
Boundary for River Rch & Prof#=Stream0466,Reach-1,5
Up Type=0
Dn Type=3
Dn Slope=0.005
Boundary for River Rch & Prof#=Stream0466,Reach-1,6
Up Type=0
Dn Type=3
Dn Slope=0.005
Boundary for River Rch & Prof#=Stream0466,Reach-1,7
Up Type=0
Dn Type=3
Dn Slope=0.005

--- Stream0466.g01 (geometry) ---

Geom Title=Existing Conditions

River Reach=Stream0466,Reach-1
Reach XY= 30
      2524375.00     13742725.00      2524371.26     13742923.45
      2524138.21     13743211.37      2523468.83     13743532.86
      2522865.32     13743935.76      2522685.32     13744163.89
      2522045.13     13744074.61      2521626.50     13744228.61
      2520330.62     13745130.62      2520133.08     13745471.70
      2520175.04     13745755.02      2520069.97     13746319.92
      2519583.30     13746428.08      2519438.79     13746711.63
      2519326.65     13746678.17      2518680.10     13747080.47
      2518772.41     13747316.50      2518032.82     13748018.81
      2517961.78     13748438.67      2517719.07     13748572.76
      2517426.46     13748578.54      2517230.80     13748772.71
      2517182.77     13748878.41      2517421.25     13749176.55
      2517423.95     13749364.57      2517130.54     13749722.58
      2516982.31     13750125.11      2517172.08     13750232.98
      2517127.14     13750519.04      2517325.00     13750775.00

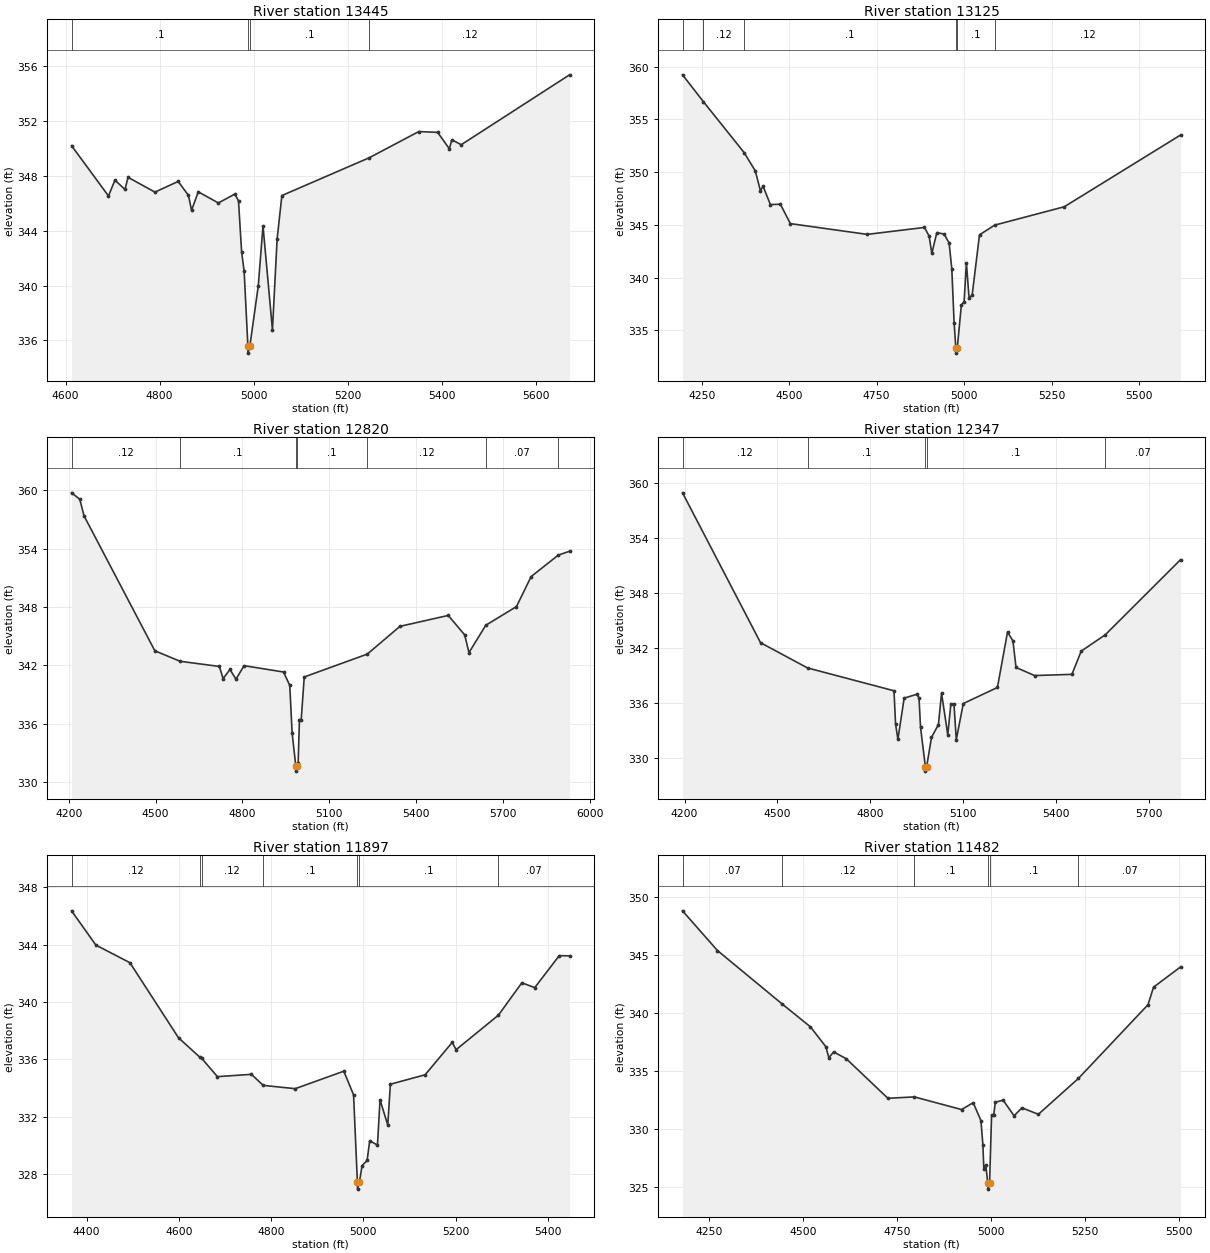
Type RM Length L Ch R = 1,13445,320,320,320
BEGIN DESCRIPTION:
Stream0466 15.0
END DESCRIPTION:
XS GIS Cut Line= 3
      2524074.97     13742574.98      2524350.00     13742810.42
      2525044.45     13742872.92
#Sta/Elev= 30
  4612.8  350.21  4691.3  346.54  4705.0  347.69  4726.4  347.02  4733.0  347.90
  4790.1  346.82  4839.5  347.60  4861.5  346.58  4868.0  345.49  4882.3  346.84
  4925.1  346.03  4960.2  346.68  4967.9  346.18  4974.5  342.47  4979.9  341.03
  4987.9  335.57  4988.1  335.07  4992.0  335.57  5010.0  339.99  5020.0  344.36
  5040.1  336.77  5050.1  343.42  5060.2  346.57  5246.1  349.33  5351.4  351.24
  5391.5  351.18  5416.5  349.98  5421.6  350.64  5441.7  350.28  5672.1  355.38
#Mann=4,-1,0
  4612.8     0.1       0  4987.9    0.05       0  4992.0     0.1       0
  5246.1    0.12       0
Bank Sta=4987.9,4992
Exp/Cntr=0.3,0.1

Type RM Length L Ch R = 1,13125,305,305,305
BEGIN DESCRIPTION:
XS6871
END DESCRIPTION:
XS GIS Cut Line= 3
      2523738.86     13742477.05      2524273.61     13743109.03
      2524800.70     13743386.44
#Sta/Elev= 30
  4195.2  359.23  4254.7  356.69  4371.2  351.86  4403.4  350.11  4417.7  348.25
  4425.5  348.66  4446.3  346.93  4474.9  346.96  4503.5  345.12  4723.2  344.10
  4886.8  344.76  4900.0  343.95  4907.8  342.29  4922.1  344.27  4942.9  344.13
  4957.2  343.29  4964.9  340.85  4971.5  335.74  4976.4  333.34  4976.6  332.84
  4980.6  333.34  4992.3  337.41  5000.1  337.71  5006.6  341.41  5014.4  338.03
  5023.1  338.35  5044.1  344.06  5087.7  344.98  5286.5  346.72  5618.7  353.52
#Mann=6,-1,0
  4195.2    0.07       0  4254.7    0.12       0  4371.2     0.1       0
  4976.4    0.05       0  4980.6     0.1       0  5087.7    0.12       0
Bank Sta=4976.4,4980.6
Exp/Cntr=0.3,0.1

Type RM Length L Ch R = 1,12820,473,473,473
BEGIN DESCRIPTION:
Stream0466 14.0
END DESCRIPTION:
XS GIS Cut Line= 3
      2523575.00     13742625.00      2524025.00     13743275.00
      2524789.37     13743805.50
#Sta/Elev= 30
  4209.4  359.72  4237.8  359.06  4252.6  357.35  4497.2  343.50  4584.5  342.42
  4720.2  341.89  4733.1  340.64  4756.7  341.58  4777.7  340.58  4805.4  341.97
  4941.9  341.32  4963.5  339.94  4971.6  335.08  4984.4  331.64  4984.6  331.14
  4988.6  331.64  4992.5  332.01  4996.9  336.42  5003.0  336.42  5013.5  340.81
  5231.5  343.16  5344.4  346.01  5511.2  347.13  5568.0  345.13  5582.8  343.31
  5640.9  346.12  5747.0  348.04  5797.6  351.12  5891.2  353.32  5930.4  353.72
#Mann=7,-1,0
  4209.4    0.12       0  4584.5     0.1       0  4984.4    0.05       0
  4988.6     0.1       0  5231.5    0.12       0  5640.9    0.07       0
  5891.2   0.035       0
Bank Sta=4984.4,4988.6
Exp/Cntr=0.3,0.1

Type RM Length L Ch R = 1,12347,450,450,450
BEGIN DESCRIPTION:
Stream0466 13.0
END DESCRIPTION:
XS GIS Cut Line= 3
      2523525.01     13742675.04      2523625.00     13743475.00
      2523675.00     13744274.96
#Sta/Elev= 30
  4193.5  358.91  4445.4  342.57  4597.1  339.82  4876.2  337.33  4881.3  333.70
  4888.8  332.03  4909.0  336.53  4949.3  336.94  4956.9  336.59  4961.9  333.35
  4977.4  329.07  4977.7  328.57  4981.7  329.07  4997.2  332.24  5019.7  333.65
  5029.7  337.07  5049.8  332.53  5059.8  335.90  5069.8  335.89  5077.3  332.00
  5099.9  335.94  5210.1  337.69  5242.7  343.73  5260.2  342.77  5270.2  339.87
  5330.3  338.99  5450.6  339.12  5480.6  341.65  5558.5  343.44  5801.2  351.62
#Mann=5,-1,0
  4193.5    0.12       0  4597.1     0.1       0  4977.4    0.05       0
  4981.7     0.1       0  5558.5    0.07       0
Bank Sta=4977.4,4981.7
Exp/Cntr=0.3,0.1

Type RM Length L Ch R = 1,11897,415,415,415
BEGIN DESCRIPTION:
Stream0466 12.0
END DESCRIPTION:
XS GIS Cut Line= 3
      2523075.00     13743124.99      2523275.00     13743725.00
      2523475.01     13744125.02
#Sta/Elev= 30
  4367.3  346.37  4420.0  343.98  4493.8  342.75  4599.2  337.51  4645.3  336.16
  4649.1  336.09  4683.5  334.80  4757.3  334.96  4782.7  334.19  4852.2  333.96
  4957.6  335.18  4978.7  333.53  4987.0  327.45  4987.3  326.95  4991.5  327.45
  4997.1  328.59  5008.1  328.95  5013.7  330.33  5030.5  330.02  5036.1  333.18
  5052.9  331.42  5058.5  334.27  5133.9  334.93  5192.6  337.19  5201.0  336.68
  5292.8  339.09  5343.6  341.35  5371.5  341.01  5424.6  343.24  5447.0  343.23
#Mann=7,-1,0
  4367.3    0.12       0  4645.3    0.07       0  4649.1    0.12       0
  4782.7     0.1       0  4987.0    0.05       0  4991.5     0.1       0
  5292.8    0.07       0
Bank Sta=4987,4991.5
Exp/Cntr=0.3,0.1

Type RM Length L Ch R = 1,11482,428,428,428
BEGIN DESCRIPTION:
Stream0466 11.0
END DESCRIPTION:
XS GIS Cut Line= 3
      2522725.00     13743124.99      2522925.00     13743925.00
      2523224.98     13744324.98
#Sta/Elev= 30
  4180.0  348.79  4272.8  345.37  4445.0  340.76  4520.2  338.79  4561.4  337.07
  4569.1  336.13  4582.0  336.63  4615.5  336.04  4726.3  332.63  4796.7  332.75
  4922.2  331.66  4953.1  332.25  4973.7  330.71  4978.9  328.64  4981.4  326.57
  4986.6  326.89  4992.0  325.30  4992.3  324.80  4996.7  325.30  5002.1  331.21
  5007.8  331.21  5011.9  332.29  5032.8  332.47  5061.9  331.12  5082.8  331.81
  5126.5  331.25  5232.9  334.34  5418.2  340.70  5432.8  342.21  5504.6  343.95
#Mann=6,-1,0
  4180.0    0.07       0  4445.0    0.12       0  4796.7     0.1       0
  4992.0    0.05       0  4996.7     0.1       0  5232.9    0.07       0
Bank Sta=4992,4996.7
Exp/Cntr=0.3,0.1

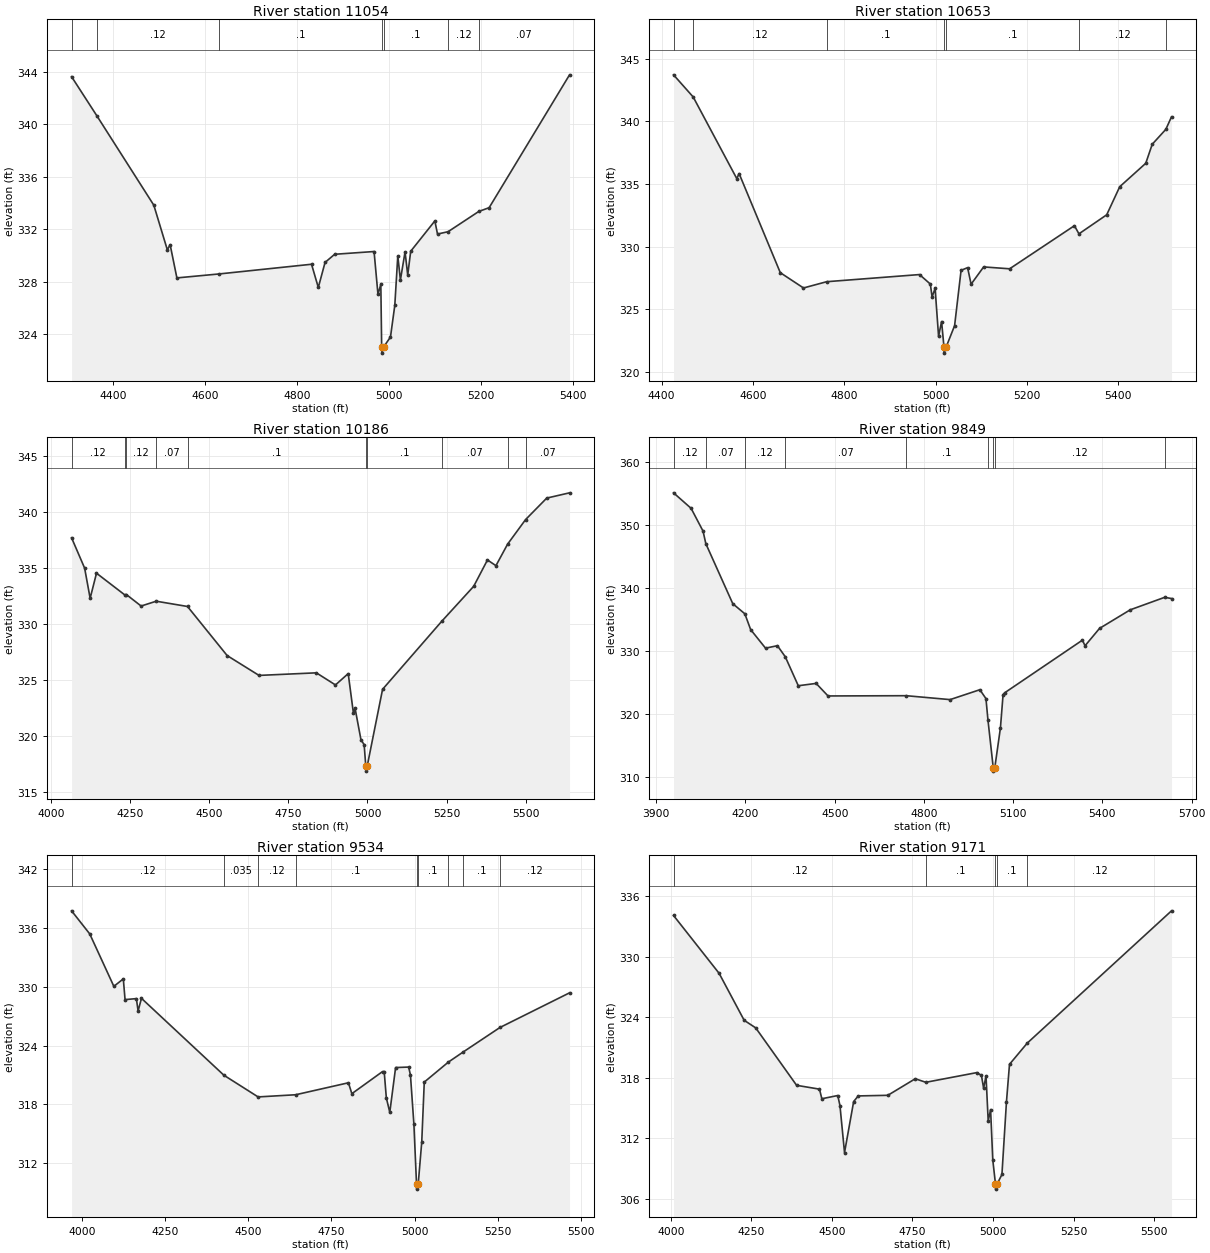
Type RM Length L Ch R = 1,11054,401,401,401
BEGIN DESCRIPTION:
Stream0466 10.0
END DESCRIPTION:
XS GIS Cut Line= 3
      2522225.00     13743575.00      2522625.00     13744125.00
      2522825.01     13744475.02
#Sta/Elev= 30
  4309.4  343.61  4364.4  340.63  4488.3  333.82  4517.7  330.42  4523.8  330.81
  4538.5  328.28  4629.9  328.58  4831.4  329.32  4846.1  327.55  4860.8  329.46
  4881.7  330.08  4967.4  330.29  4975.9  327.02  4982.1  327.80  4983.9  323.05
  4984.3  322.55  4988.8  323.05  5003.1  323.78  5012.5  326.19  5019.0  329.96
  5024.7  328.12  5034.8  330.26  5040.6  328.50  5047.1  330.31  5099.6  332.62
  5105.4  331.62  5128.4  331.80  5195.1  333.34  5217.7  333.63  5392.6  343.75
#Mann=7,-1,0
  4309.4    0.07       0  4364.4    0.12       0  4629.9     0.1       0
  4983.9    0.05       0  4988.8     0.1       0  5128.4    0.12       0
  5195.1    0.07       0
Bank Sta=4983.9,4988.8
Exp/Cntr=0.3,0.1

Type RM Length L Ch R = 1,10653,467,467,467
BEGIN DESCRIPTION:
Stream0466 9.0
END DESCRIPTION:
XS GIS Cut Line= 3
      2522175.00     13743574.98      2522275.00     13744125.00
      2522624.97     13744524.97
#Sta/Elev= 30
  4426.0  343.71  4469.1  341.94  4564.5  335.43  4569.6  335.83  4659.8  327.92
  4710.6  326.70  4761.4  327.20  4964.7  327.77  4988.4  327.01  4992.2  325.98
  4998.8  326.67  5006.4  322.85  5013.0  324.02  5018.2  322.00  5018.5  321.50
  5023.1  322.00  5041.5  323.69  5055.7  328.11  5070.0  328.32  5077.6  327.00
  5105.1  328.38  5162.0  328.23  5303.9  331.67  5313.8  331.02  5374.6  332.54
  5403.1  334.78  5460.1  336.65  5474.3  338.17  5504.1  339.36  5516.5  340.36
#Mann=7,-1,0
  4426.0    0.07       0  4469.1    0.12       0  4761.4     0.1       0
  5018.2    0.05       0  5023.1     0.1       0  5313.8    0.12       0
  5504.1    0.07       0
Bank Sta=5018.2,5023.1
Exp/Cntr=0.3,0.1

Type RM Length L Ch R = 1,10186,337,337,337
BEGIN DESCRIPTION:
Stream0466 8.0
END DESCRIPTION:
XS GIS Cut Line= 3
      2521984.56     13743246.71      2521875.00     13744175.00
      2522070.54     13744783.42
#Sta/Elev= 30
  4064.9  337.70  4106.2  334.99  4123.6  332.30  4143.7  334.54  4233.7  332.59
  4238.3  332.63  4284.7  331.61  4332.5  332.04  4431.3  331.57  4556.6  327.19
  4657.3  325.42  4838.5  325.65  4898.9  324.57  4939.2  325.58  4955.7  322.04
  4960.7  322.51  4979.5  319.68  4989.6  319.24  4994.6  317.38  4995.0  316.88
  4999.6  317.38  5047.8  324.18  5234.2  330.23  5335.8  333.37  5379.3  335.72
  5406.1  335.21  5442.9  337.13  5499.7  339.32  5566.6  341.24  5638.7  341.71
#Mann=10,-1,0
  4064.9    0.12       0  4233.7    0.07       0  4238.3    0.12       0
  4332.5    0.07       0  4431.3     0.1       0  4994.6    0.05       0
  4999.6     0.1       0  5234.2    0.07       0  5442.9    0.12       0
  5499.7    0.07       0
Bank Sta=4994.6,4999.6
Exp/Cntr=0.3,0.1

Type RM Length L Ch R = 1,9849,315,315,315
BEGIN DESCRIPTION:
Stream0466 7.0
END DESCRIPTION:
XS GIS Cut Line= 3
      2521533.22     13743235.92      2521572.22     13744275.69
      2521912.38     13744810.23
#Sta/Elev= 30
  3958.2  355.05  4017.3  352.59  4057.4  348.98  4066.8  346.99  4157.4  337.47
  4197.9  335.87  4217.5  333.36  4267.5  330.42  4307.5  330.81  4333.9  329.05
  4377.6  324.46  4437.6  324.83  4477.6  322.84  4740.8  322.88  4887.9  322.26
  4988.0  323.83  5008.5  322.42  5015.2  319.05  5033.1  311.42  5033.4  310.92
  5038.1  311.42  5057.2  317.79  5066.1  323.07  5072.0  323.36  5332.8  331.69
  5341.6  330.80  5390.3  333.55  5493.6  336.50  5609.3  338.48  5632.3  338.29
#Mann=9,-1,0
  3958.2    0.12       0  4066.8    0.07       0  4197.9    0.12       0
  4333.9    0.07       0  4740.8     0.1       0  5015.2    0.12       0
  5033.1    0.05       0  5038.1    0.12       0  5609.3    0.07       0
Bank Sta=5033.1,5038.1
Exp/Cntr=0.3,0.1

Type RM Length L Ch R = 1,9534,363,363,363
BEGIN DESCRIPTION:
XS6870
END DESCRIPTION:
XS GIS Cut Line= 2
      2521037.50     13743442.35      2521440.13     13744886.26
#Sta/Elev= 30
  3967.7  337.72  4022.4  335.37  4095.0  330.03  4123.5  330.79  4128.7  328.68
  4162.8  328.78  4168.0  327.52  4178.1  328.81  4426.2  320.98  4529.2  318.77
  4642.2  318.99  4801.1  320.21  4811.4  319.10  4903.7  321.35  4908.9  321.29
  4915.2  318.67  4925.6  317.20  4943.1  321.76  4982.4  321.81  4987.8  321.00
  4998.2  315.98  5006.1  309.88  5006.5  309.38  5011.1  309.88  5021.8  314.18
  5029.4  320.28  5101.7  322.31  5147.2  323.36  5257.2  325.84  5466.7  329.37
#Mann=9,-1,0
  3967.7    0.12       0  4426.2   0.035       0  4529.2    0.12       0
  4642.2     0.1       0  5006.1    0.05       0  5011.1     0.1       0
  5101.7   0.035       0  5147.2     0.1       0  5257.2    0.12       0
Bank Sta=5006.1,5011.1
Exp/Cntr=0.3,0.1

Type RM Length L Ch R = 1,9171,368,368,368
BEGIN DESCRIPTION:
Stream0466 6.0
END DESCRIPTION:
XS GIS Cut Line= 3
      2520325.02     13743975.02      2521065.28     13744650.69
      2521356.93     13745109.00
#Sta/Elev= 30
  4008.5  334.07  4150.0  328.34  4227.7  323.69  4263.5  322.94  4390.5  317.25
  4461.5  316.87  4468.8  315.92  4518.2  316.24  4525.0  315.25  4539.2  310.59
  4567.5  315.64  4581.7  316.20  4673.6  316.26  4758.7  317.90  4791.6  317.55
  4949.9  318.51  4964.1  318.23  4970.9  316.96  4978.3  318.19  4985.1  313.71
  4992.5  314.85  4999.3  309.87  5007.7  307.47  5008.1  306.97  5012.7  307.47
  5027.7  308.42  5041.8  315.63  5051.2  319.33  5106.3  321.43  5554.0  334.53
#Mann=5,-1,0
  4008.5    0.12       0  4791.6     0.1       0  5007.7    0.05       0
  5012.7     0.1       0  5106.3    0.12       0
Bank Sta=5007.7,5012.7
Exp/Cntr=0.3,0.1

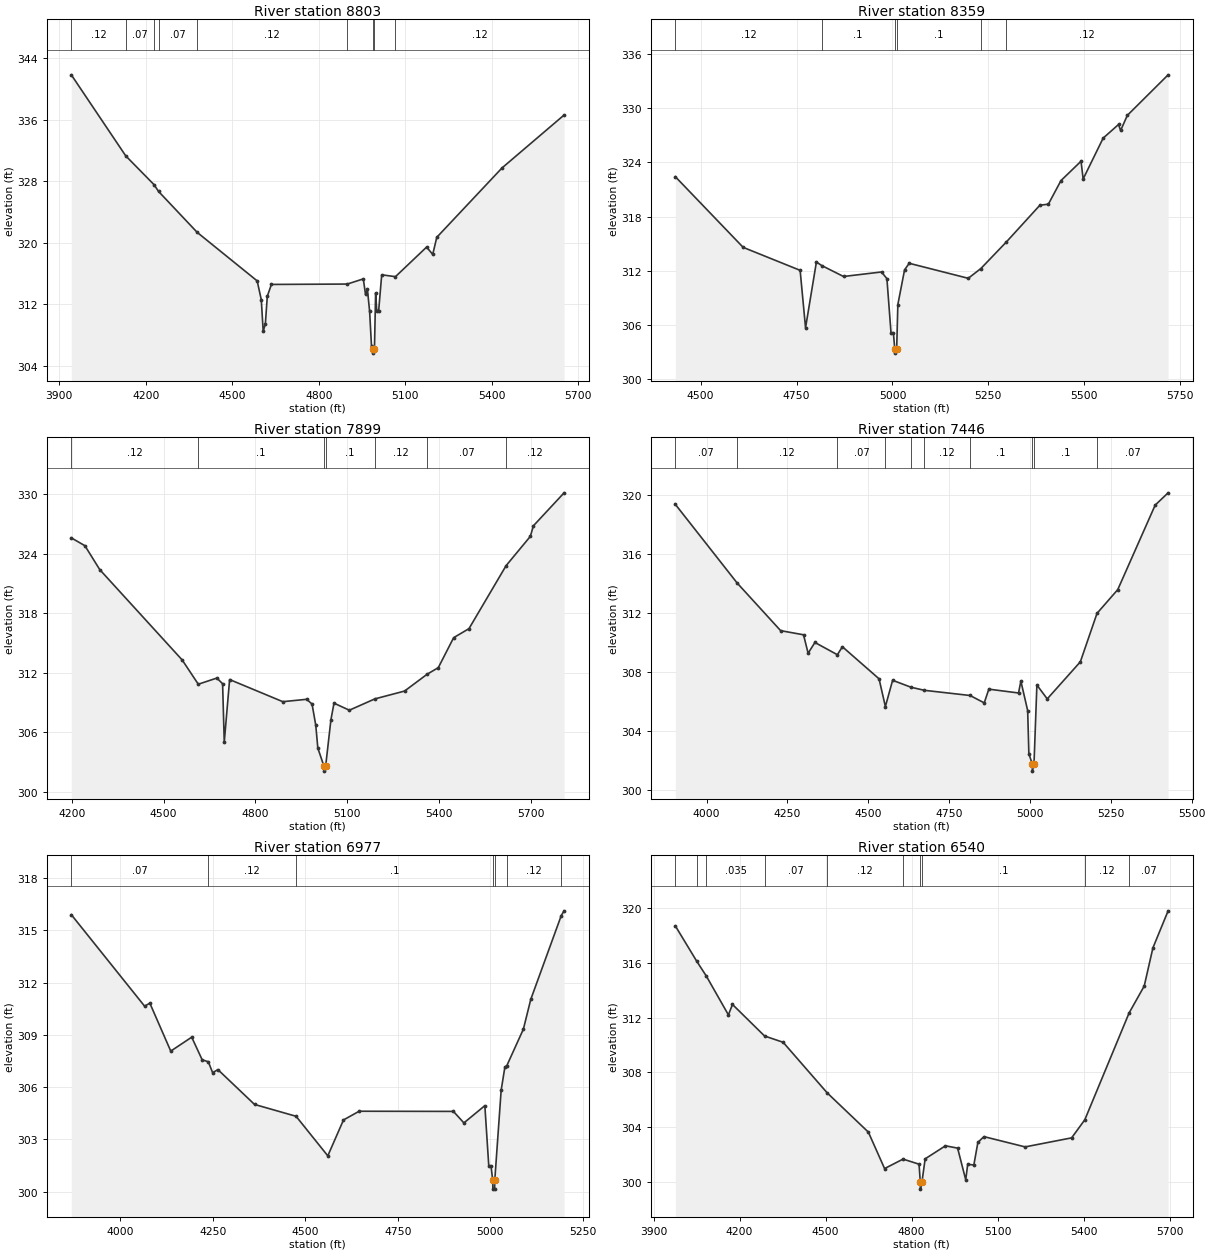
Type RM Length L Ch R = 1,8803,444,444,444
BEGIN DESCRIPTION:
Stream0466 5.0
END DESCRIPTION:
XS GIS Cut Line= 3
      2520075.01     13744025.01      2520775.00     13744825.00
      2521225.00     13745289.59
#Sta/Elev= 30
  3941.5  341.82  4130.3  331.30  4228.7  327.55  4244.2  326.68  4378.3  321.36
  4586.4  315.06  4600.7  312.61  4607.3  308.50  4614.9  309.52  4621.5  313.06
  4635.8  314.60  4899.1  314.65  4954.7  315.32  4962.3  313.30  4968.9  313.95
  4976.5  311.13  4983.1  306.55  4988.2  306.18  4988.6  305.68  4993.3  306.18
  4997.4  313.51  5001.2  311.21  5008.0  311.21  5018.5  315.85  5066.2  315.61
  5174.2  319.45  5195.5  318.50  5209.6  320.72  5436.0  329.73  5651.3  336.60
#Mann=9,-1,0
  3941.5    0.12       0  4130.3    0.07       0  4228.7    0.12       0
  4244.2    0.07       0  4378.3    0.12       0  4899.1     0.1       0
  4988.2    0.05       0  4993.3     0.1       0  5066.2    0.12       0
Bank Sta=4988.2,4993.3
Exp/Cntr=0.3,0.1

Type RM Length L Ch R = 1,8359,460,460,460
BEGIN DESCRIPTION:
Stream0466 4.0
END DESCRIPTION:
XS GIS Cut Line= 3
      2520025.00     13744675.00      2520425.00     13745075.00
      2521079.17     13745372.92
#Sta/Elev= 30
  4434.1  322.40  4610.9  314.59  4759.4  312.05  4773.5  305.70  4801.8  312.97
  4815.7  312.58  4872.5  311.37  4971.5  311.87  4985.6  311.13  4996.3  305.15
  5002.5  305.15  5006.0  303.40  5006.4  302.90  5011.1  303.40  5014.1  308.27
  5031.6  312.10  5043.7  312.83  5197.6  311.17  5230.5  312.25  5296.6  315.17
  5384.4  319.25  5406.4  319.36  5439.3  321.97  5491.6  324.11  5497.1  322.15
  5549.2  326.66  5589.3  328.17  5594.8  327.51  5612.3  329.18  5718.6  333.66
#Mann=6,-1,0
  4434.1    0.12       0  4815.7     0.1       0  5006.0    0.05       0
  5011.1     0.1       0  5230.5    0.07       0  5296.6    0.12       0
Bank Sta=5006,5011.1
Exp/Cntr=0.3,0.1

Type RM Length L Ch R = 1,7899,453,453,453
BEGIN DESCRIPTION:
Stream0466 3.0
END DESCRIPTION:
XS GIS Cut Line= 3
      2519875.00     13744674.99      2520175.00     13745425.00
      2520974.95     13745475.00
#Sta/Elev= 30
  4198.9  325.60  4243.3  324.81  4291.8  322.40  4561.1  313.29  4613.6  310.85
  4674.2  311.47  4693.0  310.90  4698.4  305.01  4715.9  311.32  4889.6  309.09
  4967.6  309.33  4985.1  308.85  4997.3  306.71  5004.0  304.41  5024.0  302.59
  5024.4  302.09  5029.5  302.59  5046.8  307.28  5056.8  308.94  5106.9  308.23
  5190.1  309.37  5287.2  310.16  5361.1  311.86  5397.4  312.52  5447.5  315.54
  5497.6  316.45  5618.8  322.80  5698.0  325.75  5708.1  326.82  5808.2  330.14
#Mann=7,-1,0
  4198.9    0.12       0  4613.6     0.1       0  5024.0    0.05       0
  5029.5     0.1       0  5190.1    0.12       0  5361.1    0.07       0
  5618.8    0.12       0
Bank Sta=5024,5029.5
Exp/Cntr=0.3,0.1

Type RM Length L Ch R = 1,7446,469,469,469
BEGIN DESCRIPTION:
Stream0466 2.0
END DESCRIPTION:
XS GIS Cut Line= 3
      2519324.99     13745074.99      2520125.00     13745825.00
      2520524.99     13745975.00
#Sta/Elev= 30
  3903.4  319.34  4094.7  314.01  4229.0  310.79  4299.8  310.51  4314.0  309.26
  4335.0  309.99  4404.5  309.16  4420.0  309.70  4533.3  307.53  4552.9  305.65
  4575.3  307.43  4632.0  306.96  4673.7  306.75  4814.8  306.40  4858.6  305.90
  4872.8  306.83  4964.6  306.57  4971.9  307.37  4992.9  305.38  4996.6  302.45
  5007.0  301.78  5007.5  301.28  5012.5  301.78  5021.4  307.11  5053.4  306.17
  5155.8  308.68  5207.3  311.96  5271.5  313.57  5387.2  319.29  5427.2  320.12
#Mann=10,-1,0
  3903.4    0.07       0  4094.7    0.12       0  4404.5    0.07       0
  4552.9    0.12       0  4632.0     0.1       0  4673.7    0.12       0
  4814.8     0.1       0  5007.0    0.05       0  5012.5     0.1       0
  5207.3    0.07       0
Bank Sta=5007,5012.5
Exp/Cntr=0.3,0.1

Type RM Length L Ch R = 1,6977,437,437,437
BEGIN DESCRIPTION:
Stream0466 1.0
END DESCRIPTION:
XS GIS Cut Line= 3
      2519274.98     13745474.98      2520075.00     13746275.00
      2520275.01     13746275.00
#Sta/Elev= 30
  3868.0  315.90  4066.0  310.65  4080.2  310.82  4136.7  308.07  4193.3  308.87
  4221.6  307.57  4238.1  307.46  4249.9  306.83  4264.0  307.01  4363.0  305.01
  4475.3  304.33  4561.0  302.06  4603.4  304.12  4645.8  304.62  4900.4  304.61
  4928.7  303.95  4985.3  304.94  4995.9  301.49  5001.9  301.49  5006.6  300.65
  5007.0  300.15  5011.7  300.15  5012.1  300.65  5029.4  305.83  5039.4  307.15
  5044.8  307.24  5089.4  309.33  5109.4  311.04  5191.8  315.85  5199.4  316.12
#Mann=7,-1,0
  3868.0    0.07       0  4238.1    0.12       0  4475.3     0.1       0
  5006.6    0.05       0  5012.1     0.1       0  5044.8    0.12       0
  5191.8    0.07       0
Bank Sta=5006.6,5012.1
Exp/Cntr=0.3,0.1

Type RM Length L Ch R = 1,6540,652,652,652
BEGIN DESCRIPTION:
XS6868
END DESCRIPTION:
XS GIS Cut Line= 3
      2518975.00     13745713.19      2519766.67     13746477.08
      2520377.36     13746379.93
#Sta/Elev= 30
  3976.1  318.69  4051.1  316.10  4084.2  315.03  4161.2  312.20  4175.4  312.96
  4287.3  310.66  4352.1  310.20  4505.7  306.51  4649.2  303.65  4705.8  300.99
  4770.2  301.68  4826.0  301.31  4830.4  299.99  4830.8  299.49  4836.0  299.99
  4847.3  301.70  4918.1  302.65  4960.5  302.48  4988.8  300.17  4995.7  301.30
  5017.1  301.25  5031.2  302.90  5052.3  303.32  5196.0  302.57  5358.1  303.23
  5404.1  304.55  5558.5  312.34  5611.2  314.30  5641.6  317.09  5694.6  319.79
#Mann=10,-1,0
  3976.1    0.07       0  4051.1    0.05       0  4084.2   0.035       0
  4287.3    0.07       0  4505.7    0.12       0  4770.2     0.1       0
  4830.4    0.05       0  4836.0     0.1       0  5404.1    0.12       0
  5558.5    0.07       0
Bank Sta=4830.4,4836
Exp/Cntr=0.3,0.1

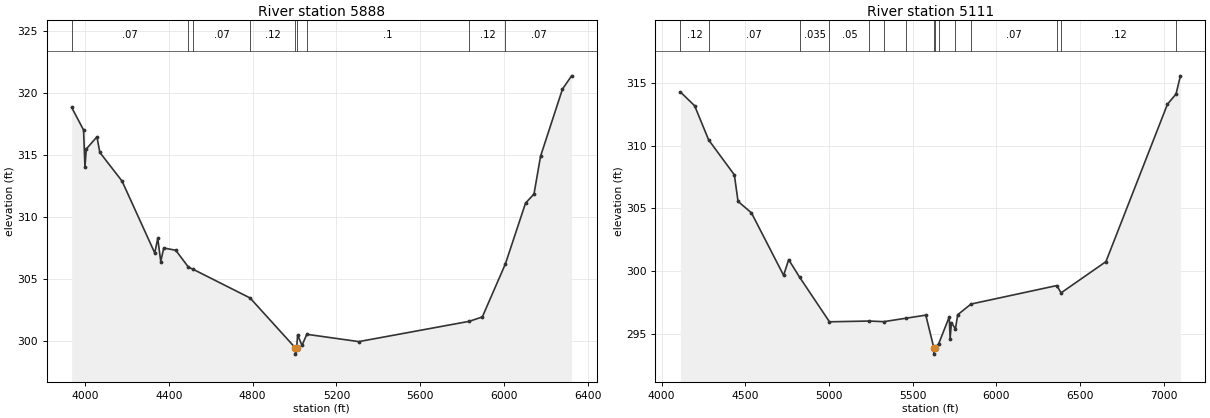
Type RM Length L Ch R = 1,5888,777,777,777
BEGIN DESCRIPTION:
XS6869
END DESCRIPTION:
XS GIS Cut Line= 3
      2518461.08     13746039.56      2519412.50     13746824.31
      2520516.66     13746484.03
#Sta/Elev= 30
  3935.1  318.81  3992.0  316.99  3998.6  314.01  4005.1  315.46  4055.9  316.44
  4069.8  315.18  4175.8  312.87  4332.1  307.07  4346.5  308.25  4360.8  306.38
  4375.1  307.47  4432.5  307.29  4493.3  305.92  4515.9  305.75  4787.5  303.44
  5004.1  299.41  5004.6  298.91  5009.9  299.41  5014.9  300.46  5035.7  299.61
  5058.6  300.51  5307.0  299.92  5835.7  301.56  5897.2  301.91  6007.3  306.18
  6103.7  311.09  6144.2  311.83  6175.6  314.88  6280.2  320.29  6323.8  321.36
#Mann=9,-1,0
  3935.1    0.07       0  4493.3   0.035       0  4515.9    0.07       0
  4787.5    0.12       0  5004.1    0.05       0  5009.9    0.12       0
  5058.6     0.1       0  5835.7    0.12       0  6007.3    0.07       0
Bank Sta=5004.1,5009.9
Exp/Cntr=0.3,0.1

Type RM Length L Ch R = 1,5111,0,0,0
BEGIN DESCRIPTION:
E21056
END DESCRIPTION:
XS GIS Cut Line= 4
      2517890.19     13746707.01      2518825.14     13747201.35
      2519502.16     13747061.64      2520671.75     13746653.90
#Sta/Elev= 30
  4113.4  314.25  4198.0  313.16  4281.5  310.45  4435.3  307.67  4457.3  305.56
  4537.4  304.65  4729.7  299.68  4759.8  300.93  4826.0  299.52  5003.6  295.99
  5241.7  296.05  5327.8  296.00  5463.4  296.28  5579.3  296.52  5627.4  293.92
  5627.9  293.42  5633.2  293.92  5656.5  294.25  5719.5  296.38  5724.6  294.64
  5732.4  295.92  5756.5  295.42  5769.8  296.55  5849.5  297.40  6362.2  298.87
  6387.7  298.29  6655.7  300.77  7023.3  313.28  7074.5  314.09  7100.9  315.54
#Mann=15,-1,0
  4113.4    0.12       0  4281.5    0.07       0  4826.0   0.035       0
  5003.6    0.05       0  5241.7    0.07       0  5327.8    0.05       0
  5463.4    0.07       0  5627.4   0.035       0  5633.2    0.07       0
  5656.5    0.12       0  5756.5     0.1       0  5849.5    0.07       0
  6362.2     0.1       0  6387.7    0.12       0  7074.5    0.07       0
Bank Sta=5627.4,5633.2
Exp/Cntr=0.3,0.1

Chan Stop Cuts=-1