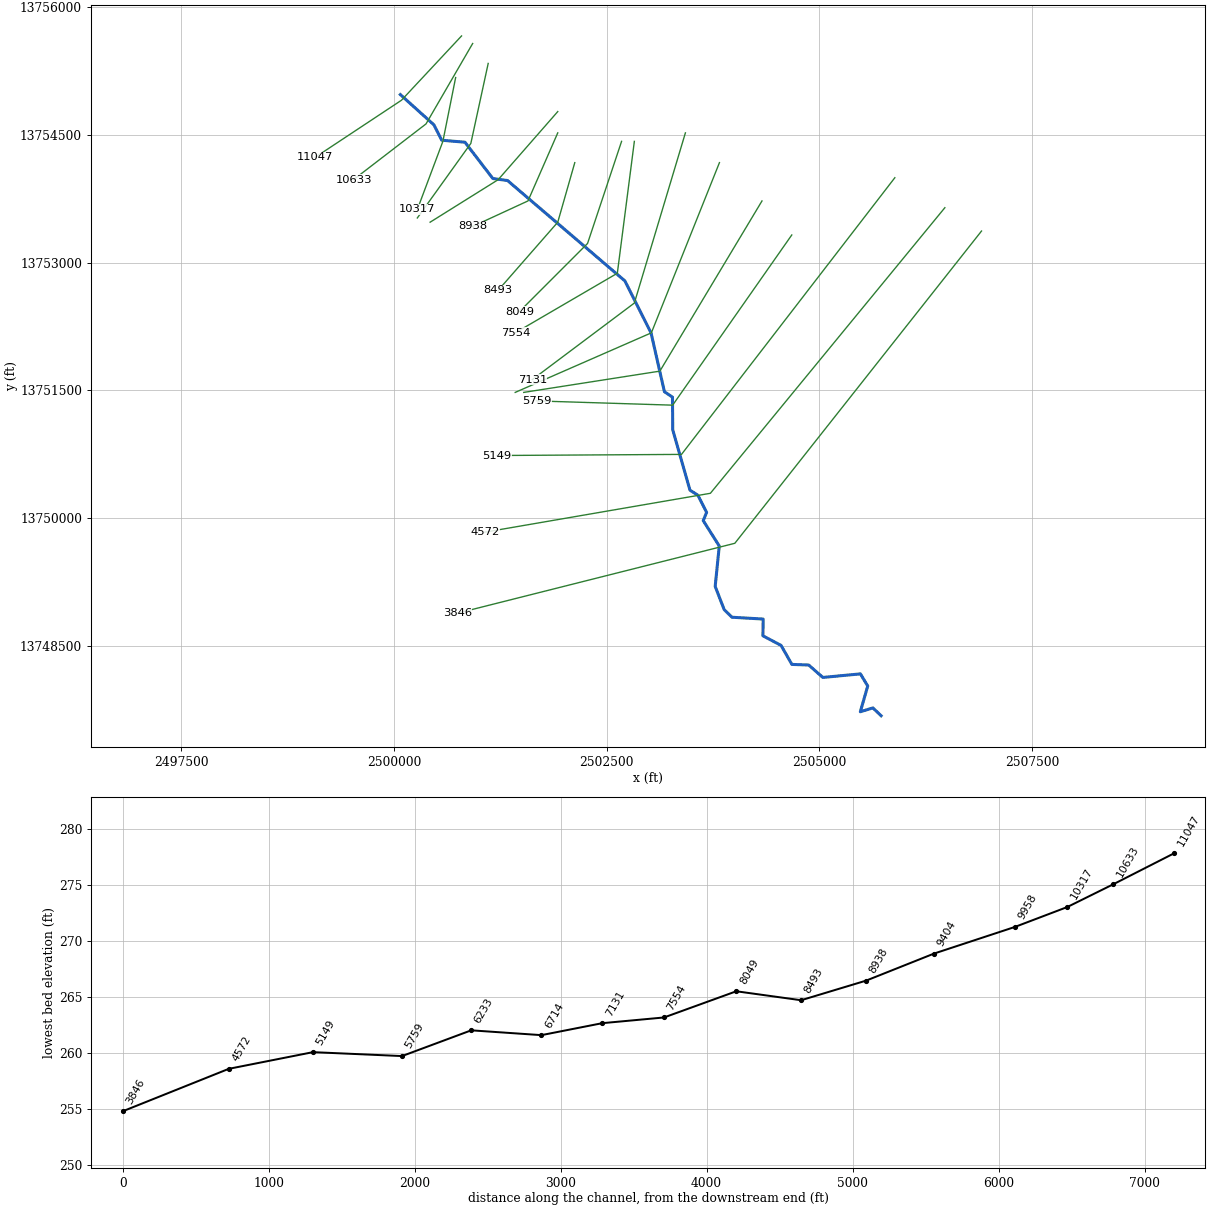
--- Stream0467.prj (project) ---

Proj Title=Stream0467 Base Level Engineering
Current Plan=p01
Default Exp/Contr=0.3,0.1
English Units
Geom File=g01
Flow File=f01
Plan File=p01
Y Axis Title=Elevation
X Axis Title(PF)=Main Channel Distance
X Axis Title(XS)=Station
BEGIN DESCRIPTION:
Stream0467
END DESCRIPTION:
DSS Export Rating Curves= 0
DSS Export Rating Curve Sorted= 0
DSS Export Volume Flow Curves= 0
DXF OffsetX= 0
DXF OffsetY= 0
DXF ScaleX= 1
DXF ScaleY= 10

--- Stream0467.p01 (plan) ---

Plan Title=Multiple Run
Short Identifier=Multiple
Geom File=g01
Flow File=f01
Subcritical Flow
K Sum by GR= 0
Std Step Tol= 0.01
Critical Tol= 0.01
Num of Std Step Trials= 20
Max Error Tol= 0.3
Flow Tol Ratio= 0.001
Split Flow NTrial= 30
Split Flow Tol= 0.02
Split Flow Ratio= 0.02
Log Output Level= 0
Friction Slope Method= 1
Unsteady Friction Slope Method= 2
Unsteady Bridges Friction Slope Method= 1
Parabolic Critical Depth
Global Vel Dist=  1 , 1 , 1
Global Log Level= 0
CheckData=True
Encroach Param= -1, 0, 0, 0
BEGIN DESCRIPTION:
Multiple Run
END DESCRIPTION:

--- Stream0467.f01 (steady flow) ---

Flow Title=Multiple
Number of Profiles=7
Profile Names=10-year,25-year,50-year,1pct_min,100-year,1pct_plu,500-year
River Rch & RM= Stream0467,Reach-1,11047
     665    1061    1416     914    1824    3640    2998
River Rch & RM= Stream0467,Reach-1,10633
     814    1315    1767    1149    2292    4572    3817
River Rch & RM= Stream0467,Reach-1,6233
     964    1561    2102    1367    2728    5444    4552
Boundary for River Rch & Prof#=Stream0467,Reach-1,1
Up Type=0
Dn Type=3
Dn Slope=0.005
Boundary for River Rch & Prof#=Stream0467,Reach-1,2
Up Type=0
Dn Type=3
Dn Slope=0.005
Boundary for River Rch & Prof#=Stream0467,Reach-1,3
Up Type=0
Dn Type=3
Dn Slope=0.005
Boundary for River Rch & Prof#=Stream0467,Reach-1,4
Up Type=0
Dn Type=3
Dn Slope=0.005
Boundary for River Rch & Prof#=Stream0467,Reach-1,5
Up Type=0
Dn Type=3
Dn Slope=0.005
Boundary for River Rch & Prof#=Stream0467,Reach-1,6
Up Type=0
Dn Type=3
Dn Slope=0.005
Boundary for River Rch & Prof#=Stream0467,Reach-1,7
Up Type=0
Dn Type=3
Dn Slope=0.005

--- Stream0467.g01 (geometry) ---

Geom Title=Existing Conditions
Program Version=4.10

River Reach=Stream0467      ,Reach-1
Reach XY= 30
        2500075.       13754975.      2500469.38     13754619.38
      2500561.43     13754438.47       2500834.7     13754414.82
      2501161.68     13753988.37       2501334.8     13753964.52
      2502714.24     13752784.68      2503021.45     13752173.53
      2503178.19     13751483.35      2503272.99     13751419.32
      2503276.36     13751034.65      2503478.48     13750326.26
      2503571.81     13750266.65      2503674.19      13750065.2
      2503634.43     13749968.39      2503822.91     13749669.51
       2503774.9      13749195.1      2503880.52     13748922.54
      2503971.65     13748832.99      2504338.77     13748811.53
      2504335.97     13748614.62      2504548.84     13748502.15
      2504676.25     13748278.45      2504873.54     13748271.46
      2505040.16     13748125.38      2505481.48     13748167.31
       2505567.5       13748025.      2505480.45     13747721.98
      2505628.33     13747767.52        2505725.       13747675.

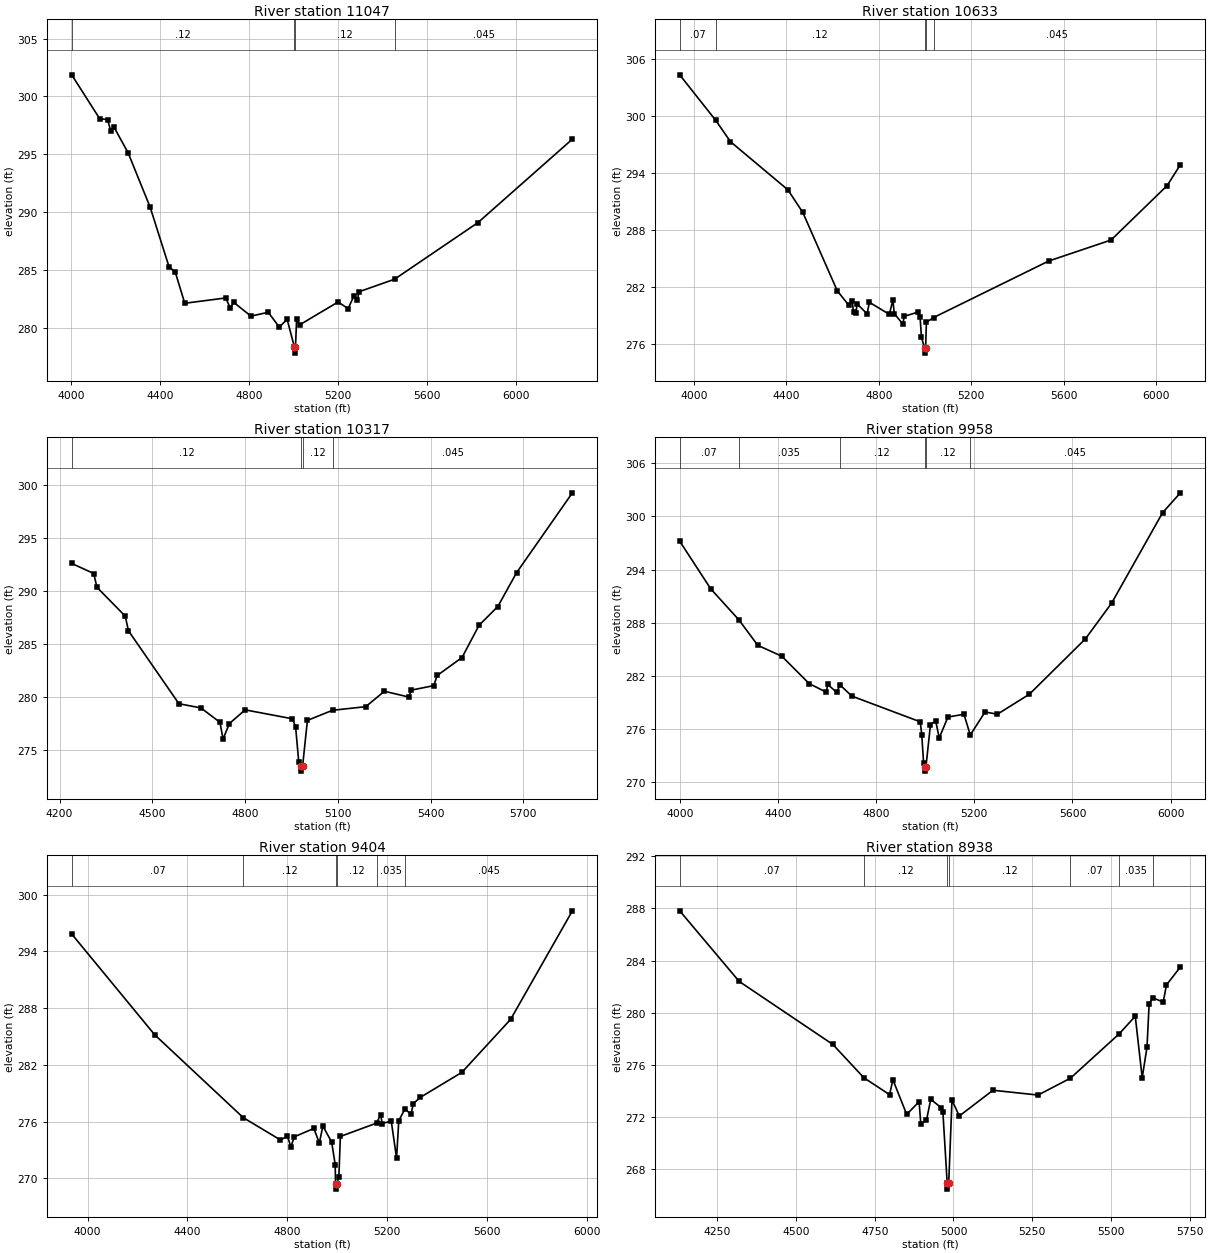
Type RM Length L Ch R = 1 ,11047   ,414,414,414
BEGIN DESCRIPTION:
XS6872
END DESCRIPTION:
XS GIS Cut Line= 3
      2500794.31     13755663.84      2500088.47      13754908.3
      2499074.45     13754237.26
#Sta/Elev= 30
  4004.1  301.86  4130.1  298.06  4165.7  297.99  4179.9  296.97  4194.1  297.34
  4257.6  295.12  4356.7  290.41  4441.2  285.28  4469.6   284.8  4512.1  282.11
  4696.2  282.57  4717.3  281.67  4731.4   282.2  4809.6     281  4887.3  281.33
  4936.6  280.06  4972.3  280.71  5005.2   278.3  5005.5   277.8  5009.6   278.3
  5014.8  280.73  5028.9  280.25  5201.1  282.22  5246.1  281.65  5273.3  282.78
  5288.3  282.39  5294.3   283.1  5454.9  284.19    5830  289.09    6254   296.3
#Mann= 4 ,-1 , 0
  4004.1     .12       0  5005.2     .05       0  5009.6     .12       0
  5454.9    .045       0
Bank Sta=5005.2,5009.6
XS Rating Curve= 0 ,0
Exp/Cntr=0.3,0.1

Type RM Length L Ch R = 1 ,10633   ,316,316,316
BEGIN DESCRIPTION:
Stream0467 19.0
END DESCRIPTION:
XS GIS Cut Line= 3
      2500925.02     13755575.03      2500376.76     13754629.95
      2499524.96     13753974.97
#Sta/Elev= 30
  3938.7  304.33    4095  299.53  4158.4   297.3    4407  292.23  4471.6  289.85
  4620.7  281.61  4669.5  280.12  4685.2  280.55    4691  279.38    4701  279.22
  4706.8  280.23  4749.8  279.18  4759.6   280.4  4845.9  279.13  4861.6  280.63
  4867.4  279.21  4904.7   278.1  4910.5  278.92  4969.2  279.36  4979.2  278.82
    4985  276.76  4998.5  275.55  4998.8  275.05    5003  275.55  5006.5   278.3
  5037.4  278.79  5535.8  284.74  5805.8  286.95  6048.7  292.68  6105.8  294.88
#Mann= 5 ,-1 , 0
  3938.7     .07       0    4095     .12       0  4998.5     .05       0
    5003     .12       0  5037.4    .045       0
Bank Sta=4998.5,5003
XS Rating Curve= 0 ,0
Exp/Cntr=0.3,0.1

Type RM Length L Ch R = 1 ,10317   ,359,359,359
BEGIN DESCRIPTION:
Stream0467 18.0
END DESCRIPTION:
XS GIS Cut Line= 3
      2500724.99     13755174.96        2500575.       13754425.
      2500275.01     13753625.01
#Sta/Elev= 30
  4239.4  292.57  4310.7  291.62  4320.9  290.33  4412.7   287.6  4422.9  286.23
  4586.1  279.36  4657.5  278.96  4718.7  277.61  4728.9  276.03  4749.3  277.49
  4800.3  278.78  4953.2  277.94  4963.4   277.2  4973.6   273.9  4981.5  273.51
  4981.8  273.01  4986.2  273.51  5001.7  277.79  5082.9  278.74  5190.2  279.08
  5250.7  280.53  5330.8  279.98  5336.2  280.63  5410.1  281.06  5421.6  282.02
  5501.7  283.71  5556.9  286.75  5617.4  288.51  5677.9  291.69  5858.6  299.22
#Mann= 4 ,-1 , 0
  4239.4     .12       0  4981.5     .05       0  4986.2     .12       0
  5082.9    .045       0
Bank Sta=4981.5,4986.2
XS Rating Curve= 0 ,0
Exp/Cntr=0.3,0.1

Type RM Length L Ch R = 1 ,9958    ,554,554,554
BEGIN DESCRIPTION:
Stream0467 17.0
END DESCRIPTION:
XS GIS Cut Line= 3
      2501107.42      13755340.7      2500903.63     13754401.31
      2500275.01     13753525.01
#Sta/Elev= 30
  3999.9   297.2  4126.3  291.82  4241.2  288.31  4317.9  285.44  4416.2   284.2
  4527.6  281.11  4597.5  280.14  4602.6  281.03  4640.2  280.11  4652.1  280.98
  4701.6   279.7  4979.8   276.8    4986  275.35  4993.5  272.12  4998.2  271.73
  4998.6  271.23  5003.1  271.73  5021.6  276.49  5042.8  276.89  5057.2  274.98
  5092.8  277.34  5157.9  277.65  5183.7  275.31  5243.8  277.91  5294.2  277.66
  5424.3  279.91  5652.8  286.17  5759.6  290.21  5967.2  300.42  6039.6  302.66
#Mann= 6 ,-1 , 0
  3999.9     .07       0  4241.2    .035       0  4652.1     .12       0
  4998.2     .05       0  5003.1     .12       0  5183.7    .045       0
Bank Sta=4998.2,5003.1
XS Rating Curve= 0 ,0
Exp/Cntr=0.3,0.1

Type RM Length L Ch R = 1 ,9404    ,466,466,466
BEGIN DESCRIPTION:
Stream0467 16.0
END DESCRIPTION:
XS GIS Cut Line= 3
        2501925.       13754775.        2501225.       13753975.
      2500425.01     13753475.01
#Sta/Elev= 30
  3936.3  295.83    4269  285.17  4623.7  276.41  4772.9  274.05  4800.5  274.45
  4814.7  273.34  4828.9  274.39  4906.8  275.27  4928.6  273.72  4942.8  275.52
    4978  273.83  4992.2  271.45  4993.5  269.35  4993.9  268.85  4998.4  269.35
    5007  270.18  5012.9  274.42  5157.8  275.83  5174.4  276.74  5180.3  275.79
  5216.9  276.04  5238.1  272.13    5247  276.09  5271.9  277.33  5295.9  276.75
  5305.3  277.89  5332.5  278.54  5499.9   281.2  5695.1   286.8  5942.7  298.28
#Mann= 6 ,-1 , 0
  3936.3     .07       0  4623.7     .12       0  4993.5     .05       0
  4998.4     .12       0  5157.8    .035       0  5271.9    .045       0
Bank Sta=4993.5,4998.4
XS Rating Curve= 0 ,0
Exp/Cntr=0.3,0.1

Type RM Length L Ch R = 1 ,8938    ,445,445,445
BEGIN DESCRIPTION:
Stream0467 15.0
END DESCRIPTION:
XS GIS Cut Line= 3
      2501924.99     13754524.98        2501575.       13753725.
      2500924.98     13753424.99
#Sta/Elev= 30
    4131  287.82    4320  282.39  4617.1  277.55  4715.6  274.99  4797.2  273.69
  4807.7  274.84  4851.4  272.17  4890.8  273.15  4896.2  271.46  4914.1  271.71
  4927.8  273.33  4960.5   272.7  4966.4  272.33  4979.9  266.93  4980.2  266.43
  4984.9  266.93  4995.2  273.27  5018.4  272.05  5125.3  274.03  5268.5  273.66
  5371.3  274.96  5525.7  278.36  5576.9  279.72  5598.9  274.99  5614.1  277.33
    5621  280.69  5632.8  281.14  5665.5   280.8    5676  282.13  5720.1   283.5
#Mann= 7 ,-1 , 0
    4131     .07       0  4715.6     .12       0  4979.9     .05       0
  4984.9     .12       0  5371.3     .07       0  5525.7    .035       0
  5632.8     .07       0
Bank Sta=4979.9,4984.9
XS Rating Curve= 0 ,0
Exp/Cntr=0.3,0.1

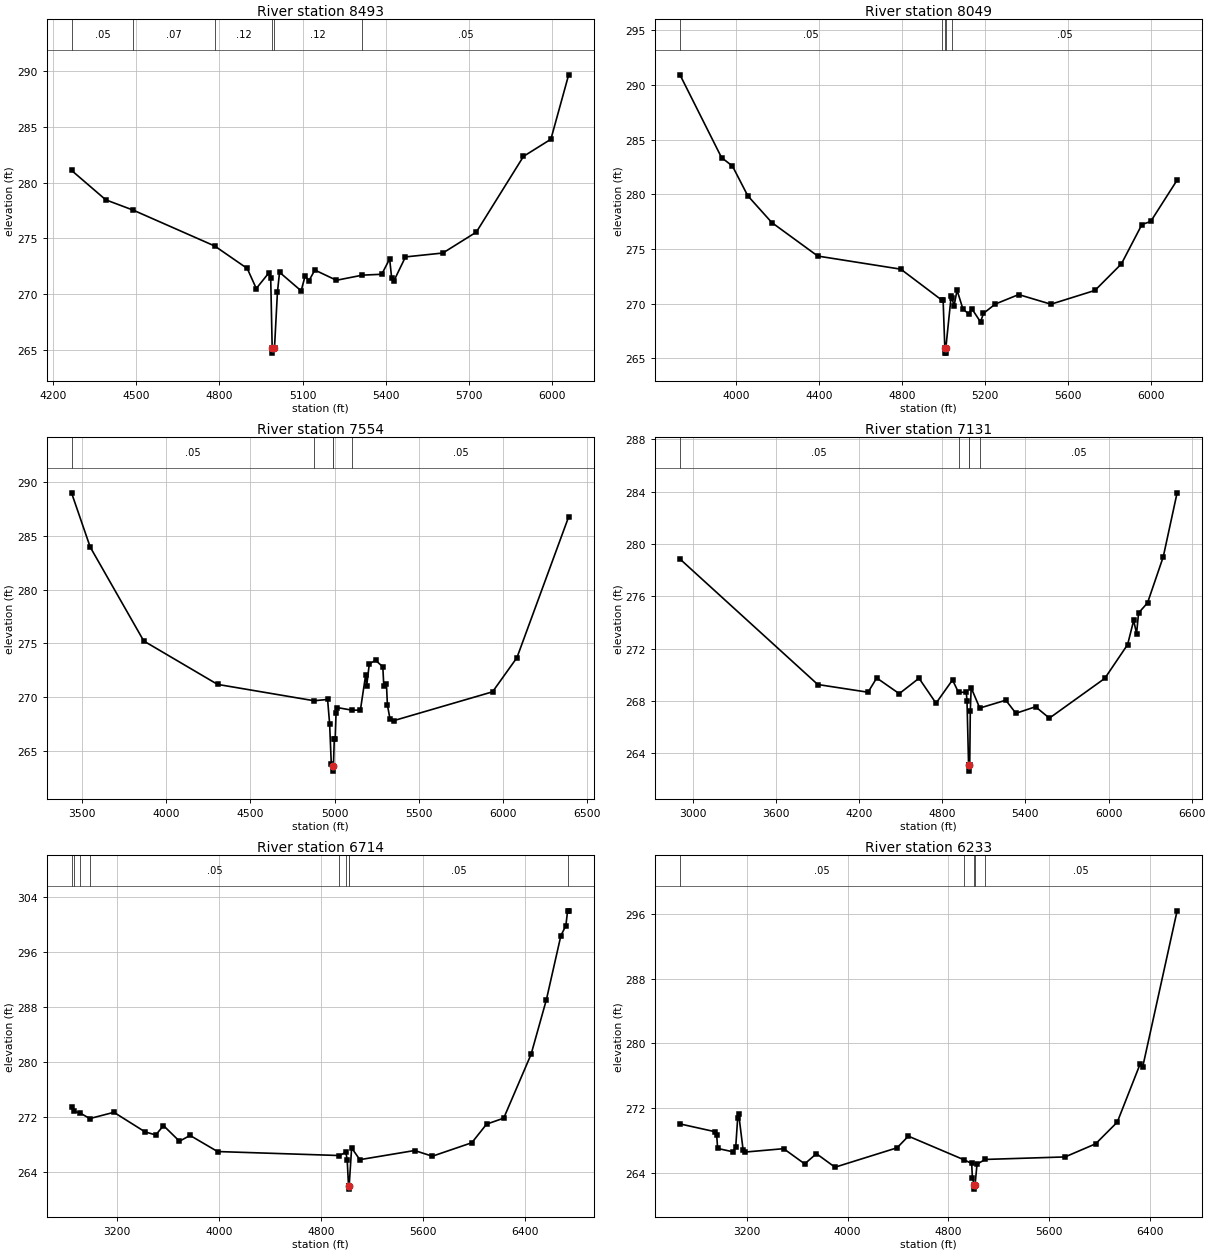
Type RM Length L Ch R = 1 ,8493    ,444,444,444
BEGIN DESCRIPTION:
Stream0467 14.0
END DESCRIPTION:
XS GIS Cut Line= 3
        2502125.     13754175.01        2501925.       13753475.
      2501225.03     13752675.03
#Sta/Elev= 30
  4267.3  281.11  4390.8  278.46    4490  277.53  4783.2  274.31  4900.4  272.29
  4932.9  270.49  4978.4   271.9  4984.9  271.42  4990.2  265.18  4990.6  264.68
  4995.3  265.18  4998.6  265.18  5009.1  270.15  5016.7  271.95  5094.5  270.28
  5108.7   271.6    5123   271.2  5143.9  272.15  5221.7  271.23  5314.9  271.69
  5384.9  271.77  5413.4  273.15  5420.5  271.47  5427.6  271.12  5470.4  273.33
  5605.1  273.68  5725.7  275.56  5895.6  282.37  5994.3  283.91  6058.3   289.7
#Mann= 6 ,-1 , 0
  4267.3     .05       0    4490     .07       0  4783.2     .12       0
  4990.2     .05       0  4995.3     .12       0  5314.9     .05       0
Bank Sta=4990.2,4995.3
XS Rating Curve= 0 ,0
Exp/Cntr=0.3,0.1

Type RM Length L Ch R = 1 ,8049    ,495,495,495
BEGIN DESCRIPTION:
Stream0467 13.0
END DESCRIPTION:
XS GIS Cut Line= 3
      2502674.99     13754424.98        2502275.       13753225.
      2501474.97     13752424.97
#Sta/Elev= 30
  3730.3  290.91  3930.6  283.35  3983.3  282.57    4057  279.86    4173  277.41
  4394.4  274.35  4794.9  273.15  4992.6  270.32  4998.7  270.32  5006.8  265.98
  5007.2  265.48  5011.5  265.48  5011.9  265.98  5037.6  270.69  5040.4  270.52
  5051.8  269.83  5065.9  271.23  5094.2  269.51  5122.5  269.05  5136.6  269.55
    5179  268.33  5193.2  269.11  5249.7  269.96  5362.9  270.83  5518.4  269.95
  5730.6  271.21  5857.9  273.63  5956.9  277.23  5999.3  277.51  6126.6  281.29
#Mann= 5 ,-1 , 0
  3730.3     .05       0  4992.6     .12       0  5006.8     .05       0
  5011.9     .12       0  5040.4     .05       0
Bank Sta=5006.8,5011.9
XS Rating Curve= 0 ,0
Exp/Cntr=0.3,0.1

Type RM Length L Ch R = 1 ,7554    ,423,423,423
BEGIN DESCRIPTION:
Stream0467 12.0
END DESCRIPTION:
XS GIS Cut Line= 3
        2502825.       13754425.        2502625.       13752875.
      2501424.99     13752174.99
#Sta/Elev= 30
  3437.2     289  3548.1  283.96  3866.3  275.23  4304.3   271.2  4877.5  269.68
  4957.8   269.8  4969.8  267.56  4979.9  263.76  4987.4  263.64  4987.8  263.14
  4992.5  263.64  4997.5  266.13  5002.9  266.13  5007.9  268.51  5013.7  269.05
  5104.2   268.8  5152.6  268.81    5184  272.09  5189.8  271.05  5205.5  273.11
  5242.7  273.44  5285.8  272.83  5291.5  271.08  5307.3  271.22    5313  269.29
  5328.8  267.95  5350.3  267.83  5937.4  270.51  6082.1  273.68  6389.3  286.77
#Mann= 5 ,-1 , 0
  3437.2     .05       0  4877.5     .12       0  4987.4     .05       0
  4992.5     .12       0  5104.2     .05       0
Bank Sta=4987.4,4992.5
XS Rating Curve= 0 ,0
Exp/Cntr=0.3,0.1

Type RM Length L Ch R = 1 ,7131    ,417,417,417
BEGIN DESCRIPTION:
Stream0467 11.0
END DESCRIPTION:
XS GIS Cut Line= 3
      2503424.99     13754524.98        2502825.       13752525.
      2501625.03     13751625.02
#Sta/Elev= 30
  2907.2  278.84  3901.6  269.25  4264.4  268.66  4327.1  269.75  4489.8  268.55
  4632.4  269.73  4755.1  267.82  4874.3   269.6  4917.7  268.64  4973.5  268.67
  4978.7  268.01  4990.1  263.13  4990.4  262.63  4995.2  263.13  4998.4  263.13
  5002.5  267.19  5008.8     269  5070.9  267.45  5258.8  268.05  5331.7  267.05
  5473.4  267.55  5573.4  266.68  5973.4  269.72  6137.9   272.3  6181.7  274.15
  6202.5  273.14  6217.1  274.72  6281.7  275.49  6395.2  279.01  6495.2   283.9
#Mann= 5 ,-1 , 0
  2907.2     .05       0  4917.7     .12       0  4990.1     .05       0
  4995.2     .12       0  5070.9     .05       0
Bank Sta=4990.1,4995.2
XS Rating Curve= 0 ,0
Exp/Cntr=0.3,0.1

Type RM Length L Ch R = 1 ,6714    ,481,481,481
BEGIN DESCRIPTION:
Stream0467 10.0
END DESCRIPTION:
XS GIS Cut Line= 3
        2503825.     13754174.99        2503025.       13752175.
      2501424.98     13751474.99
#Sta/Elev= 30
  2842.1  273.54  2861.2  272.86  2908.8  272.62  2985.6  271.81  3174.6  272.72
  3419.6  269.87  3503.1  269.43  3563.7  270.79  3688.9  268.52  3772.4  269.36
  3987.8  267.02  4944.6  266.44  4994.6  266.92  5005.1   265.8  5015.4  262.06
  5015.8  261.56  5020.6  262.06  5039.8  267.55  5104.1  265.84  5534.5  267.17
  5672.9  266.34  5982.8   268.3  6098.6     271  6233.1  271.87  6447.9  281.15
  6567.9  289.08  6681.4  298.37  6720.7  299.84  6734.4  301.99  6742.6  301.93
#Mann= 9 ,-1 , 0
  2842.1     .12       0  2861.2     .05       0  2908.8     .12       0
  2985.6     .05       0  4944.6     .12       0  4994.6     .05       0
  5015.4     .05       0  5020.6     .05       0  6734.4     .07       0
Bank Sta=5015.4,5020.6
XS Rating Curve= 0 ,0
Exp/Cntr=0.3,0.1

Type RM Length L Ch R = 1 ,6233    ,474,474,474
BEGIN DESCRIPTION:
Stream0467 9.0
END DESCRIPTION:
XS GIS Cut Line= 3
      2504325.01     13753725.02        2503125.       13751725.
      2501525.01       13751475.
#Sta/Elev= 30
  2667.6  270.05  2945.6  269.09  2959.2   268.7  2966.9  267.02  3089.4   266.6
  3110.8  267.21  3126.3   270.8  3134.1  271.29  3169.1  266.87  3184.6  266.57
  3491.7  266.99  3658.9  265.11  3752.2  266.37  3899.9   264.7  4393.6   267.1
    4483  268.54  4929.3  265.59  4986.4  265.16  4992.2  263.34  5007.2  262.49
  5007.7  261.99  5013.1  262.49  5028.8  265.08  5094.7  265.66  5728.7  265.97
  5971.6  267.59  6143.7  270.27  6324.4  277.42  6346.1  277.11  6619.4  296.39
#Mann= 5 ,-1 , 0
  2667.6     .05       0  4929.3     .12       0  5007.2     .05       0
  5013.1     .12       0  5094.7     .05       0
Bank Sta=5007.2,5013.1
XS Rating Curve= 0 ,0
Exp/Cntr=0.3,0.1

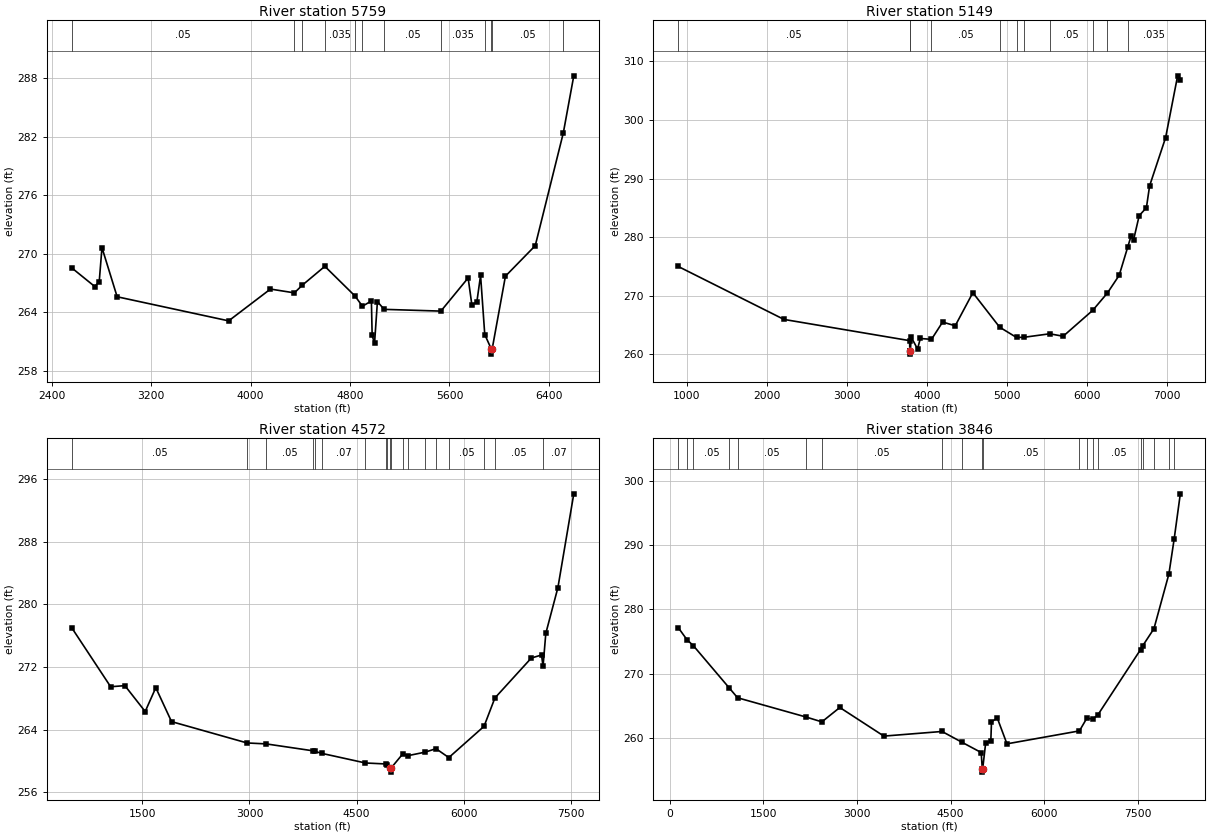
Type RM Length L Ch R = 1 ,5759    ,610,610,610
BEGIN DESCRIPTION:
Stream0467 8.0
END DESCRIPTION:
XS GIS Cut Line= 3
      2504674.97     13753324.96        2503275.       13751325.
      2501675.05       13751375.
#Sta/Elev= 30
  2558.9  268.54    2745  266.62  2780.8  267.11    2803  270.61  2925.1  265.57
  3822.7   263.1  4159.2  266.36  4351.8  265.97    4414  266.74    4597  268.69
  4840.5  265.64  4899.7   264.6  4971.8  265.14  4977.9   261.6  4997.1   260.8
  5020.2  265.07  5074.5  264.28  5531.1   264.1  5750.5   267.5  5780.5  264.74
  5820.6  265.03  5850.6  267.76  5884.3   261.7  5937.7  260.19  5938.2  259.69
  5943.6  260.19  6050.7  267.68  6290.8  270.81  6516.5  282.36  6600.9  288.22
#Mann= 12 ,-1 , 0
  2558.9     .05       0  4351.8    .035       0    4414     .05       0
    4597    .035       0  4840.5     .05       0  4899.7     .12       0
  5074.5     .05       0  5531.1    .035       0  5884.3     .05       0
  5937.7     .05       0  5943.6     .05       0  6516.5     .07       0
Bank Sta=5937.7,5943.6
XS Rating Curve= 0 ,0
Exp/Cntr=0.3,0.1

Type RM Length L Ch R = 1 ,5149    ,577,577,577
BEGIN DESCRIPTION:
Stream0467 7.0
END DESCRIPTION:
XS GIS Cut Line= 3
      2505886.19     13753997.98      2503379.02     13750746.48
      2501211.43     13750733.43
#Sta/Elev= 30
   890.1     275  2211.9  265.96  3781.6  262.34  3784.3  260.54  3784.7  260.04
  3790.2  260.54  3801.7  262.92  3880.5  260.93  3915.8  262.71  4054.8  262.56
  4193.9  265.51  4351.6  264.88  4571.7  270.52  4906.2  264.64  5117.6  262.88
  5214.4  262.92  5532.2  263.51    5700  263.09  6070.1  267.52  6253.5  270.48
    6400  273.49  6505.2  278.24    6550  280.27    6580  279.55    6650  283.67
    6740  285.02    6780  288.75    6980  296.98    7130  307.52  7163.6  306.78
#Mann= 12 ,-1 , 0
   890.1     .05       0  3781.6    .035       0  3784.3     .05       0
  3790.2    .035       0  4054.8     .05       0  4906.2     .12       0
  5117.6     .07       0  5214.4     .12       0  5532.2     .05       0
  6070.1    .035       0  6253.5     .05       0  6505.2    .035       0
Bank Sta=3784.3,3790.2
XS Rating Curve= 0 ,0
Exp/Cntr=0.3,0.1

Type RM Length L Ch R = 1 ,4572    ,726,726,726
BEGIN DESCRIPTION:
Stream0467 6.0
END DESCRIPTION:
XS GIS Cut Line= 3
      2506473.78     13753645.37      2503718.53     13750289.45
      2501068.89     13749832.62
#Sta/Elev= 30
     510  277.03  1056.1  269.47  1255.5  269.61  1539.7   266.3  1688.2  269.35
  1908.5  265.01  2966.5  262.28  3233.7  262.16  3886.5  261.28  3914.5  261.21
  4016.9  260.94  4623.8  259.72  4918.1  259.59  4925.7  259.52  4974.5  259.05
  4974.9  258.55  4980.4  259.05  5144.1  260.86  5221.4  260.66  5461.1  261.11
  5611.5  261.55  5790.9  260.41  6284.3  264.41  6436.2  268.03    6946  273.14
  7089.3  273.53  7110.4  272.07  7149.1  276.29  7318.6  282.15  7540.8  294.14
#Mann= 19 ,-1 , 0
     510     .05       0  2966.5    .035       0  3233.7     .05       0
  3886.5     .07       0  3914.5     .05       0  4016.9     .07       0
  4623.8     .05       0  4918.1     .12       0  4925.7     .07       0
  4974.5     .05       0  4980.4     .07       0  5144.1     .12       0
  5221.4     .07       0  5461.1     .12       0  5611.5     .07       0
  5790.9     .05       0  6284.3    .035       0  6436.2     .05       0
  7110.4     .07       0
Bank Sta=4974.5,4980.4
XS Rating Curve= 0 ,0
Exp/Cntr=0.3,0.1

Type RM Length L Ch R = 1 ,3846    ,0,0,0
BEGIN DESCRIPTION:
Stream0467 5.0
END DESCRIPTION:
XS GIS Cut Line= 3
      2506904.68     13753371.13      2504005.81     13749701.84
      2500742.95      13748879.6
#Sta/Elev= 30
   137.4   277.2   277.6  275.32   381.8  274.37   955.6  267.82  1088.6   266.3
  2185.9  263.31  2438.4  262.56  2725.9  264.79  3431.3  260.35  4362.9  261.07
  4686.9  259.37  4989.9   257.8  5007.4  255.26  5007.9  254.76  5013.5  255.26
  5061.8   259.3  5143.9  259.55  5154.8  262.56  5247.6  263.16  5402.3  259.15
  6562.9  261.16  6679.9   263.1  6781.5  263.03  6856.4  263.62  7541.7  273.77
  7576.6  274.37  7756.2  277.02  7995.5   285.5  8080.7  290.98  8178.5  297.95
#Mann= 20 ,-1 , 0
   137.4     .05       0   277.6    .035       0   381.8     .05       0
   955.6    .035       0  1088.6     .05       0  2185.9    .035       0
  2438.4     .05       0  4362.9     .07       0  4686.9     .05       0
  5007.4     .05       0  5013.5     .05       0  6562.9    .035       0
  6679.9     .05       0  6781.5     .07       0  6856.4     .05       0
  7541.7     .07       0  7576.6     .05       0  7756.2    .035       0
  7995.5     .07       0  8080.7     .12       0
Bank Sta=5007.4,5013.5
XS Rating Curve= 0 ,0
Exp/Cntr=0.3,0.1

Chan Stop Cuts=-1
Use User Specified Reach Order=0
Composite Channel Slope=5