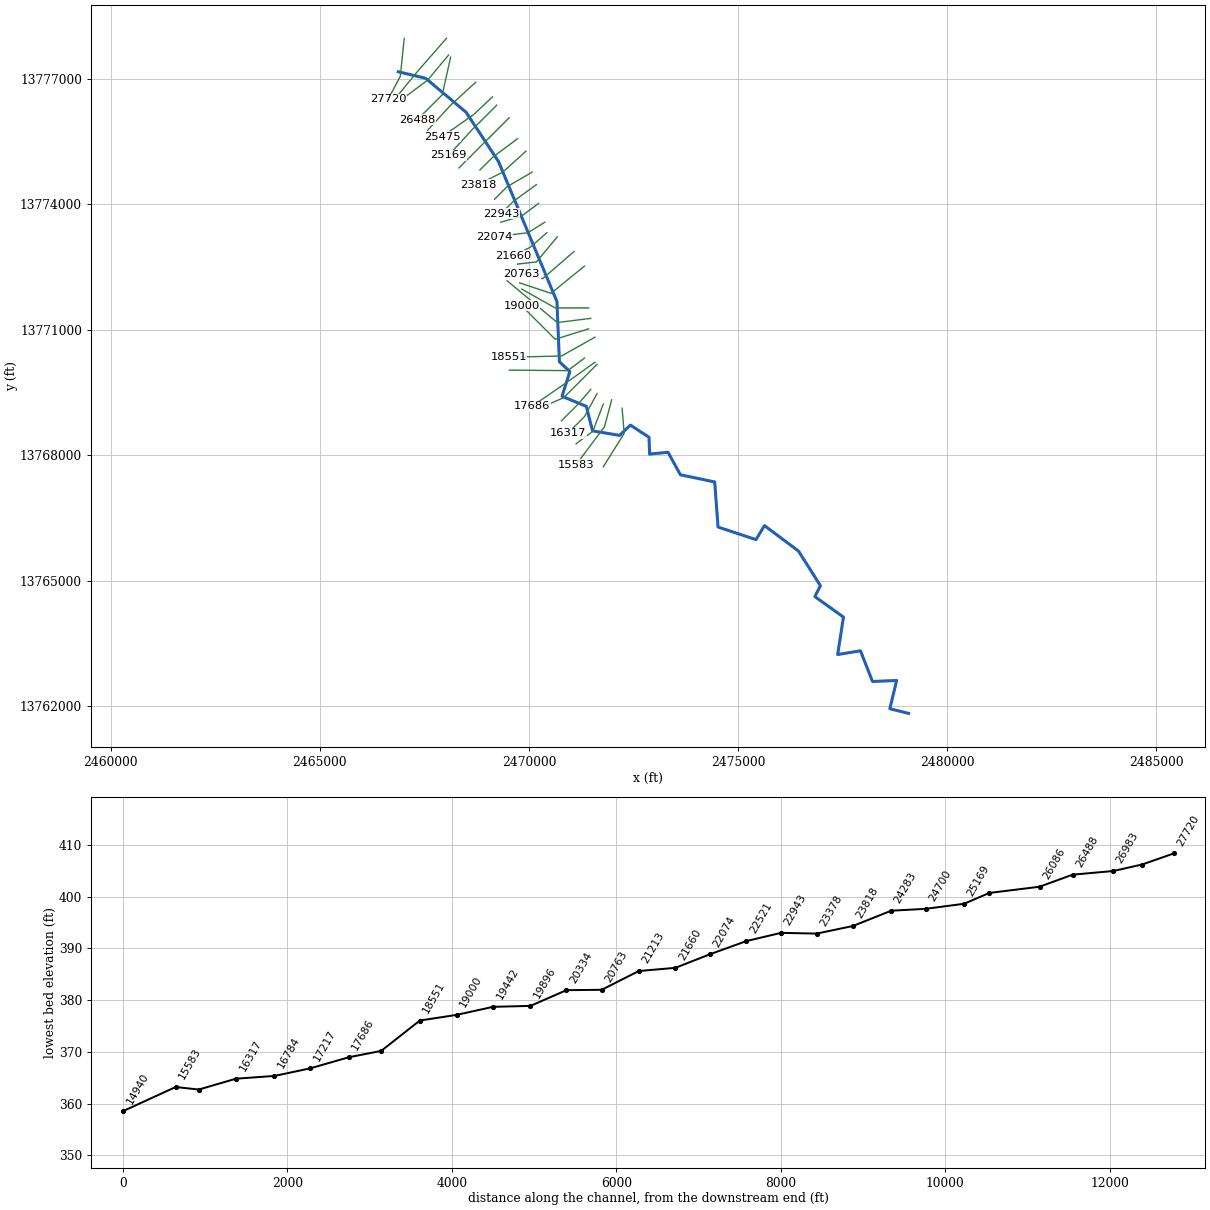
--- Stream0472.prj (project) ---

Proj Title=Stream0472 Base Level Engineering
Current Plan=p01
Default Exp/Contr=0.3,0.1
English Units
Geom File=g01
Flow File=f01
Plan File=p01
Y Axis Title=Elevation
X Axis Title(PF)=Main Channel Distance
X Axis Title(XS)=Station
BEGIN DESCRIPTION:
Stream0472
END DESCRIPTION:
DSS Export Rating Curves= 0
DSS Export Rating Curve Sorted= 0
DSS Export Volume Flow Curves= 0
DXF OffsetX= 0
DXF OffsetY= 0
DXF ScaleX= 1
DXF ScaleY= 10

--- Stream0472.p01 (plan) ---

Plan Title=Multiple Run
Short Identifier=Multiple
Geom File=g01
Flow File=f01
Subcritical Flow
K Sum by GR= 0
Std Step Tol= 0.01
Critical Tol= 0.01
Num of Std Step Trials= 20
Max Error Tol= 0.3
Flow Tol Ratio= 0.001
Split Flow NTrial= 30
Split Flow Tol= 0.02
Split Flow Ratio= 0.02
Log Output Level= 0
Friction Slope Method= 1
Unsteady Friction Slope Method= 2
Unsteady Bridges Friction Slope Method= 1
Parabolic Critical Depth
Global Vel Dist=  1 , 1 , 1
Global Log Level= 0
CheckData=True
Encroach Param= -1, 0, 0, 0
BEGIN DESCRIPTION:
Multiple Run
END DESCRIPTION:

--- Stream0472.f01 (steady flow) ---

Flow Title=Multiple
Number of Profiles=7
Profile Names=10-year,25-year,50-year,1pct_min,100-year,1pct_plu,500-year
River Rch & RM= Stream0472,Reach-1,27720
     488     759     994     630    1257    2509    1992
River Rch & RM= Stream0472,Reach-1,22521
     628     992    1313     840    1677    3346    2710
River Rch & RM= Stream0472,Reach-1,17217
    1275    2093    2844    1865    3720    7423    6310
River Rch & RM= Stream0472,Reach-1,4327
    1333    2197    2990    1965    3920    7821    6676
Boundary for River Rch & Prof#=Stream0472,Reach-1,1
Up Type=0
Dn Type=3
Dn Slope=0.005
Boundary for River Rch & Prof#=Stream0472,Reach-1,2
Up Type=0
Dn Type=3
Dn Slope=0.005
Boundary for River Rch & Prof#=Stream0472,Reach-1,3
Up Type=0
Dn Type=3
Dn Slope=0.005
Boundary for River Rch & Prof#=Stream0472,Reach-1,4
Up Type=0
Dn Type=3
Dn Slope=0.005
Boundary for River Rch & Prof#=Stream0472,Reach-1,5
Up Type=0
Dn Type=3
Dn Slope=0.005
Boundary for River Rch & Prof#=Stream0472,Reach-1,6
Up Type=0
Dn Type=3
Dn Slope=0.005
Boundary for River Rch & Prof#=Stream0472,Reach-1,7
Up Type=0
Dn Type=3
Dn Slope=0.005

--- Stream0472.g01 (geometry) ---

Geom Title=Existing Conditions
Program Version=4.10

River Reach=Stream0472      ,Reach-1
Reach XY= 30
        2466875.       13777175.      2467527.45     13777019.53
      2468492.23     13776208.76      2469269.27     13775027.55
      2470666.92     13771678.31      2470725.75     13770235.68
      2470975.39     13770004.64      2470788.19     13769411.35
      2471369.84     13769169.59      2471518.05     13768583.85
      2472163.93     13768475.53      2472423.26     13768721.69
      2472867.66     13768431.39       2472882.8     13768028.51
      2473323.27     13768071.69      2473618.61       13767533.
      2474438.57     13767361.54      2474518.81     13766282.85
       2475425.1     13765982.28      2475628.34     13766317.42
       2476441.8     13765708.59        2476967.     13764878.34
      2476832.46     13764618.95      2477517.41     13764128.33
      2477378.66     13763233.17      2477923.51     13763321.55
      2478211.43     13762588.47      2478788.73     13762611.77
      2478626.25     13761935.98        2479075.       13761825.

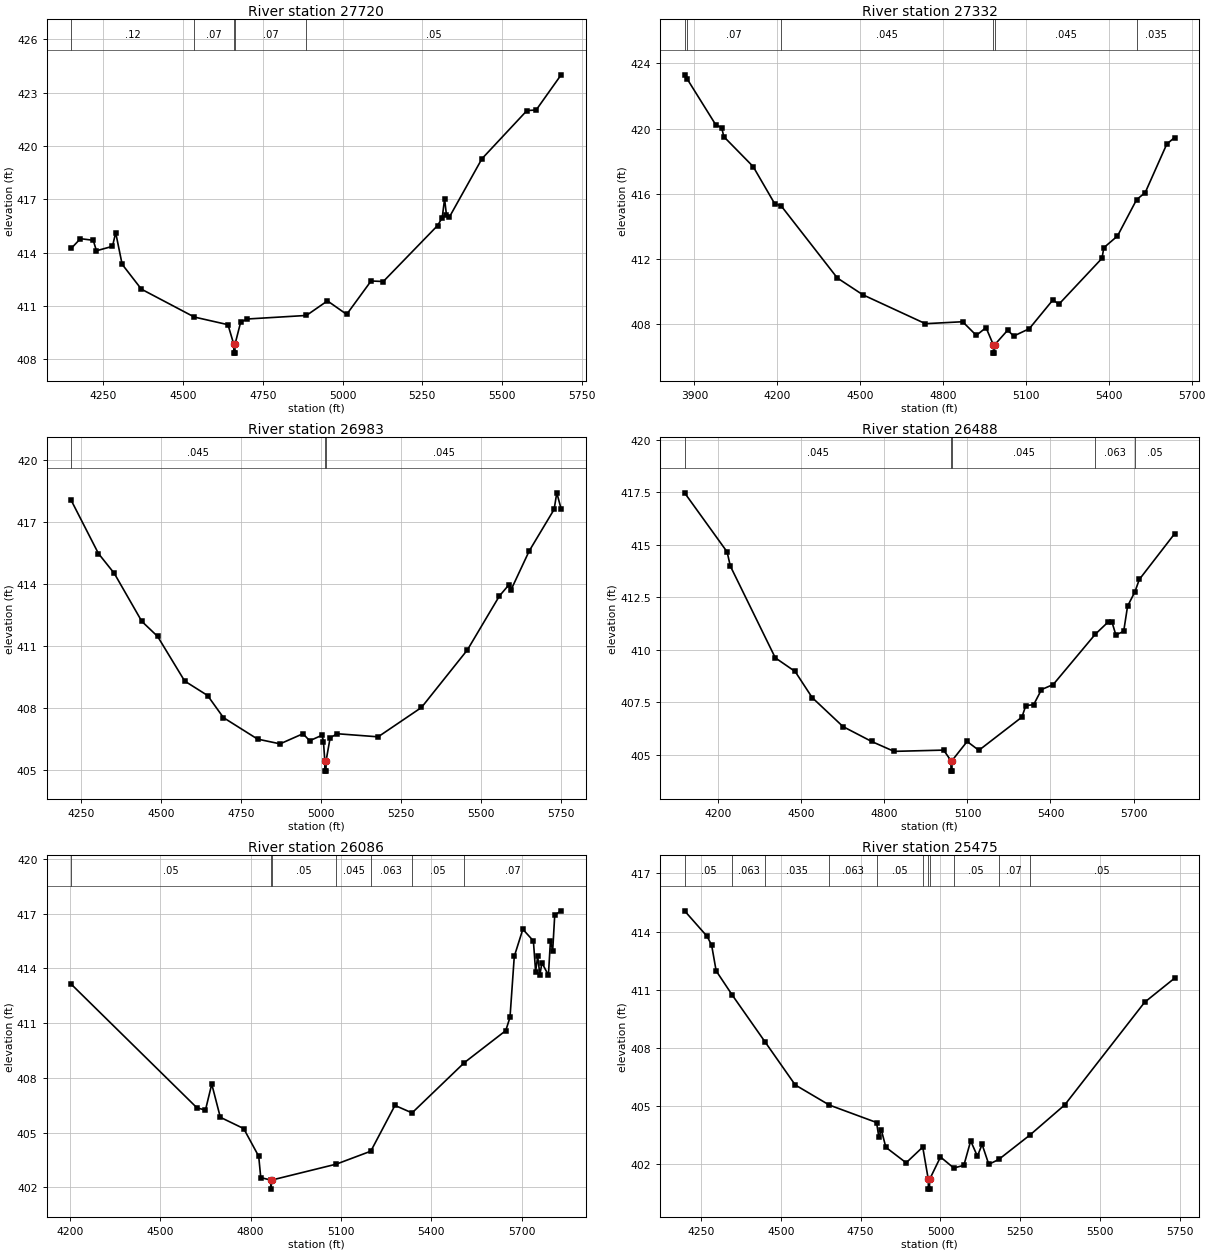
Type RM Length L Ch R = 1 ,27720   ,388,388,388
BEGIN DESCRIPTION:
XS6891
END DESCRIPTION:
XS GIS Cut Line= 3
      2467015.28      13777973.8      2466920.89     13777064.24
      2466629.56     13776515.86
#Sta/Elev= 30
  4149.6  414.23  4178.6  414.78  4218.8  414.69  4228.8   414.1  4279.1  414.35
  4289.1  415.12  4309.3  413.34  4369.6  411.94  4535.6  410.37    4641  409.94
  4659.1  408.84  4659.4  408.34  4662.9  408.34  4663.1  408.84  4680.7  410.08
  4701.3  410.26  4886.8  410.46  4952.7  411.28    5013  410.52  5089.4   412.4
  5127.7  412.37  5297.9  415.52  5312.3  415.96  5319.8  417.02  5325.5  416.13
  5334.9     416  5436.9  419.28  5577.9  421.99  5606.7  422.02    5685     424
#Mann= 5 ,-1 , 0
  4149.6     .12       0  4535.6     .07       0  4659.1     .05       0
  4663.1     .07       0  4886.8     .05       0
Bank Sta=4659.1,4663.1
XS Rating Curve= 0 ,0
Exp/Cntr=0.3,0.1

Type RM Length L Ch R = 1 ,27332   ,349,349,349
BEGIN DESCRIPTION:
Stream0472 58.0
END DESCRIPTION:
XS GIS Cut Line= 3
      2468025.02     13777975.02      2467341.33     13777192.95
      2466875.03     13776625.03
#Sta/Elev= 30
  3864.5   423.3  3873.4  423.06    3978  420.21  3998.8  420.06  4006.4   419.5
  4112.7  417.66  4190.6  415.38  4214.3  415.24  4417.4  410.81  4509.5  409.78
  4736.3     408  4871.1  408.12  4920.6  407.28  4955.7  407.76  4982.4  406.69
  4982.7  406.19  4986.2  406.19  4986.4  406.69    5034   407.6  5055.9  407.24
  5112.2  407.69  5198.2  409.47  5219.1  409.19  5375.5  412.02    5382  412.67
  5431.5  413.39  5500.9  415.63  5531.9  416.06  5610.2  419.05  5638.1  419.44
#Mann= 6 ,-1 , 0
  3864.5     .05       0  3873.4     .07       0  4214.3    .045       0
  4982.4    .045       0  4986.4    .045       0  5500.9    .035       0
Bank Sta=4982.4,4986.4
XS Rating Curve= 0 ,0
Exp/Cntr=0.3,0.1

Type RM Length L Ch R = 1 ,26983   ,495,495,495
BEGIN DESCRIPTION:
Stream0472 57.0
END DESCRIPTION:
XS GIS Cut Line= 3
      2468075.02     13777575.02        2467575.       13776975.
      2466974.96     13776524.97
#Sta/Elev= 30
  4219.2  418.05  4304.5  415.47    4354  414.51  4439.9  412.19  4489.3  411.46
  4573.9   409.3  4645.5   408.6    4695  407.53  4801.7  406.49    4872  406.26
  4943.6  406.75  4964.5  406.41  5003.4  406.68  5007.5  406.37  5011.8  405.44
    5012  404.94  5015.5  404.94  5015.8  405.44  5028.4  406.55  5050.3  406.75
  5178.4   406.6  5313.8  408.02  5457.5  410.81  5557.5  413.42  5586.7  413.95
    5593  413.69  5650.3  415.59  5728.4  417.61  5736.7  418.41  5750.3  417.63
#Mann= 3 ,-1 , 0
  4219.2    .045       0  5011.8    .045       0  5015.8    .045       0
Bank Sta=5011.8,5015.8
XS Rating Curve= 0 ,0
Exp/Cntr=0.3,0.1

Type RM Length L Ch R = 1 ,26488   ,402,402,402
BEGIN DESCRIPTION:
Stream0472 56.0
END DESCRIPTION:
XS GIS Cut Line= 3
      2468125.01     13777525.03        2467925.       13776625.
      2467325.01     13776025.01
#Sta/Elev= 30
  4077.8  417.47  4231.5  414.66    4243  413.99  4405.6  409.62  4477.3  408.97
  4538.8  407.73  4650.2  406.35  4753.9  405.64  4834.6  405.17  5013.9  405.23
  5040.2  404.73  5040.5  404.23    5044  404.23  5044.2  404.73  5098.8  405.64
  5141.2  405.22  5296.8   406.8  5310.9  407.35  5339.2  407.39  5367.5  408.11
  5409.9  408.35  5561.7  410.74  5607.9  411.32    5622  411.33  5636.2  410.71
  5664.5  410.88  5678.6  412.08    5705  412.76    5721  413.35  5848.3  415.52
#Mann= 5 ,-1 , 0
  4077.8    .045       0  5040.2    .045       0  5044.2    .045       0
  5561.7    .063       0    5705     .05       0
Bank Sta=5040.2,5044.2
XS Rating Curve= 0 ,0
Exp/Cntr=0.3,0.1

Type RM Length L Ch R = 1 ,26086   ,611,611,611
BEGIN DESCRIPTION:
Stream0472 55.0
END DESCRIPTION:
XS GIS Cut Line= 3
        2468725.       13776925.        2468125.       13776375.
      2467574.99     13775774.99
#Sta/Elev= 30
  4203.6  413.14  4621.4  406.36  4649.7  406.23  4670.7  407.66  4699.1  405.84
  4776.8  405.22  4826.7   403.7  4833.5  402.53  4866.6   402.4  4866.9   401.9
  4870.6   402.4  5084.4  403.27  5199.1  403.98  5279.3  406.49  5336.2  406.08
  5510.2  408.84  5647.4  410.59  5661.6  411.32  5675.8  414.66  5704.2  416.15
  5739.3  415.51  5746.7  413.83  5753.5  414.66  5760.9  413.65  5767.7  414.31
  5789.2  413.63    5796  415.52  5803.4  414.97  5810.2  416.93  5831.5  417.16
#Mann= 7 ,-1 , 0
  4203.6     .05       0  4866.6     .05       0  4870.6     .05       0
  5084.4    .045       0  5199.1    .063       0  5336.2     .05       0
  5510.2     .07       0
Bank Sta=4866.6,4870.6
XS Rating Curve= 0 ,0
Exp/Cntr=0.3,0.1

Type RM Length L Ch R = 1 ,25475   ,306,306,306
BEGIN DESCRIPTION:
Stream0472 54.0
END DESCRIPTION:
XS GIS Cut Line= 3
      2469124.97     13776574.97      2468679.87     13776154.72
      2467925.03     13775625.02
#Sta/Elev= 30
  4198.7  415.07  4269.3  413.75  4283.4   413.3  4297.6  411.97    4348  410.72
  4451.7  408.28  4545.2  406.08  4652.1  405.04  4799.9  404.14  4806.9   403.4
    4815  403.74    4829  402.86  4892.5  402.06  4944.5  402.87  4961.9   401.2
  4962.2   400.7  4965.7   400.7  4965.9   401.2  5000.1  402.36  5041.6  401.79
  5073.3  401.93  5094.6  403.19  5115.6   402.4  5130.4  403.01  5151.3  401.98
  5182.3  402.23  5279.9  403.49  5389.2  405.05  5639.4  410.35    5733  411.59
#Mann= 11 ,-1 , 0
  4198.7     .05       0    4348    .063       0  4451.7    .035       0
  4652.1    .063       0  4799.9     .05       0  4944.5     .07       0
  4961.9     .05       0  4965.9     .07       0  5041.6     .05       0
  5182.3     .07       0  5279.9     .05       0
Bank Sta=4961.9,4965.9
XS Rating Curve= 0 ,0
Exp/Cntr=0.3,0.1

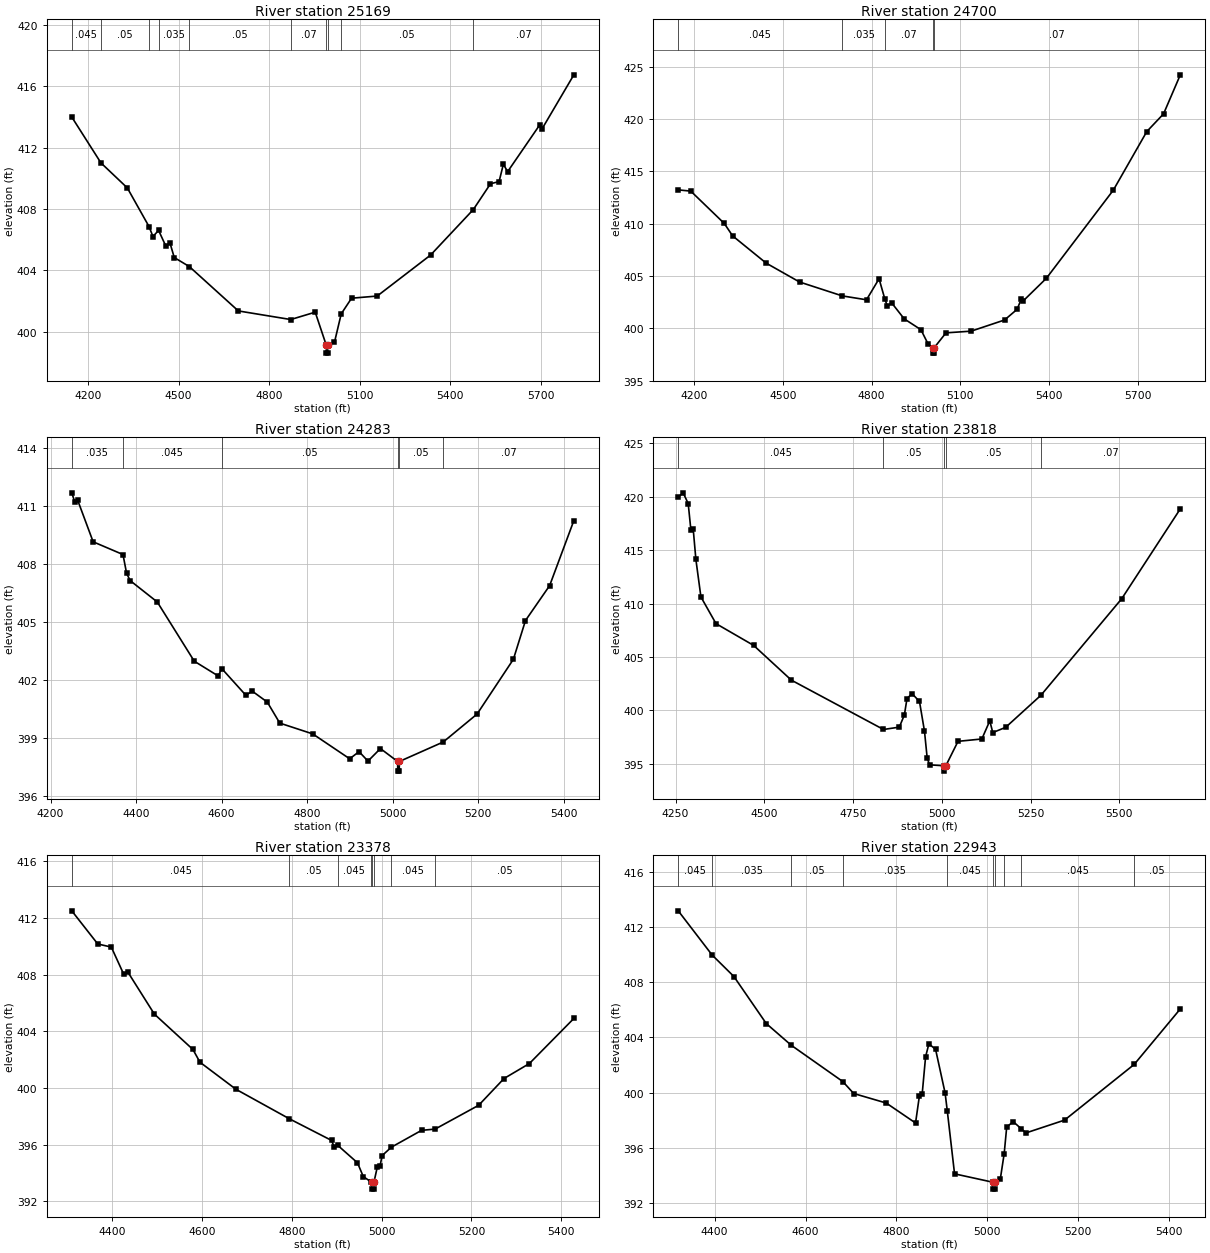
Type RM Length L Ch R = 1 ,25169   ,469,469,469
BEGIN DESCRIPTION:
Stream0472 53.0
END DESCRIPTION:
XS GIS Cut Line= 3
      2469225.01     13776375.01        2468625.       13775775.
      2468074.98     13775174.98
#Sta/Elev= 30
  4146.3     414  4242.9  411.01  4330.2  409.38  4402.4  406.85    4415  406.21
  4433.8  406.61  4457.4   405.6  4471.6  405.78  4485.7  404.84  4535.7  404.25
  4697.9  401.36  4871.4   400.8  4952.4  401.28  4989.3  399.11  4989.6  398.61
  4993.1  398.61  4993.3  399.11  5016.1  399.31  5038.5  401.17  5072.8  402.19
  5157.6  402.33  5334.3     405    5476  407.97  5532.8  409.65  5561.2  409.79
  5575.4  410.92  5589.6  410.44  5695.6  413.48  5702.4  413.19  5808.8  416.75
#Mann= 10 ,-1 , 0
  4146.3    .045       0  4242.9     .05       0  4402.4    .063       0
  4433.8    .035       0  4535.7     .05       0  4871.4     .07       0
  4989.3     .05       0  4993.3     .07       0  5038.5     .05       0
    5476     .07       0
Bank Sta=4989.3,4993.3
XS Rating Curve= 0 ,0
Exp/Cntr=0.3,0.1

Type RM Length L Ch R = 1 ,24700   ,417,417,417
BEGIN DESCRIPTION:
Stream0472 52.0
END DESCRIPTION:
XS GIS Cut Line= 3
      2469525.01     13776075.01        2468925.       13775475.
      2468324.98     13774874.98
#Sta/Elev= 30
  4146.7  413.24  4189.1  413.12  4302.3  410.03  4330.6  408.84  4443.7  406.24
  4556.8  404.43  4701.4   403.1  4783.1  402.73  4825.5  404.74  4844.7  402.84
  4853.8   402.1    4868  402.44  4910.4  400.91    4967  399.87  4991.7  398.48
  5007.4  398.13  5007.6  397.63  5011.1  397.63  5011.4  398.13  5051.8  399.57
  5136.7  399.73  5249.8   400.8  5292.2  401.82  5306.4  402.81  5313.4  402.64
  5391.2  404.79  5617.5  413.22  5730.6  418.82  5787.2  420.51  5843.8  424.24
#Mann= 5 ,-1 , 0
  4146.7    .045       0  4701.4    .035       0  4844.7     .07       0
  5007.4     .05       0  5011.4     .07       0
Bank Sta=5007.4,5011.4
XS Rating Curve= 0 ,0
Exp/Cntr=0.3,0.1

Type RM Length L Ch R = 1 ,24283   ,465,465,465
BEGIN DESCRIPTION:
Stream0472 51.0
END DESCRIPTION:
XS GIS Cut Line= 3
      2469725.03     13775575.03        2469125.       13775125.
        2468825.       13774825.
#Sta/Elev= 30
  4249.7   411.7    4257  411.21  4263.3  411.33  4299.7  409.16  4369.5   408.5
  4377.9  407.53  4386.2  407.15  4449.7  406.04  4536.2  402.97  4592.5   402.2
  4600.4  402.59    4657   401.2  4671.6  401.42    4707  400.85  4736.2  399.76
  4813.3   399.2  4899.7  397.91  4921.6  398.28  4942.5  397.79  4971.6  398.44
  5011.9  397.77  5012.1  397.27  5015.6  397.27  5015.9  397.77  5118.5  398.78
  5197.7  400.23  5282.6  403.07  5310.9  405.08  5367.4  406.89    5424  410.26
#Mann= 6 ,-1 , 0
  4249.7    .035       0  4369.5    .045       0  4600.4     .05       0
  5011.9     .05       0  5015.9     .05       0  5118.5     .07       0
Bank Sta=5011.9,5015.9
XS Rating Curve= 0 ,0
Exp/Cntr=0.3,0.1

Type RM Length L Ch R = 1 ,23818   ,440,440,440
BEGIN DESCRIPTION:
Stream0472 50.0
END DESCRIPTION:
XS GIS Cut Line= 3
      2469925.01     13775275.01        2469375.       13774775.
      2468775.03     13774475.01
#Sta/Elev= 30
  4257.7  419.98  4271.6  420.38  4285.8  419.37  4293.2  416.94  4299.9  416.98
  4307.4  414.14  4321.6  410.63  4364.1  408.13  4470.2  406.09  4576.3  402.84
  4835.8  398.22  4880.4  398.44  4894.6  399.58    4902  401.11  4916.2  401.58
  4937.2  400.84  4951.3  398.05  4958.8  395.56  4965.5  394.91  5007.4  394.82
  5007.6  394.32  5011.4  394.82  5045.7  397.11  5112.8  397.33  5135.2  399.03
  5143.6  397.93  5179.9  398.42  5279.1  401.42  5506.9  410.47  5671.8  418.88
#Mann= 5 ,-1 , 0
  4257.7    .045       0  4835.8     .05       0  5007.4     .05       0
  5011.4     .05       0  5279.1     .07       0
Bank Sta=5007.4,5011.4
XS Rating Curve= 0 ,0
Exp/Cntr=0.3,0.1

Type RM Length L Ch R = 1 ,23378   ,435,435,435
BEGIN DESCRIPTION:
Stream0472 49.0
END DESCRIPTION:
XS GIS Cut Line= 3
        2470075.       13774775.        2469475.       13774425.
      2469174.99     13774124.99
#Sta/Elev= 30
  4309.3   412.5  4367.2  410.16  4397.4  409.94  4425.1  408.02  4434.6  408.16
  4493.3  405.21  4579.3  402.71    4595  401.81  4675.2   399.9    4794  397.82
  4888.2  396.29  4894.4   395.8  4902.1  395.94    4946  394.71  4958.9  393.74
  4975.8  393.37  4978.8  393.35    4979  392.85  4982.5  392.85  4982.8  393.35
  4990.3  394.43  4996.1  394.46    5001  395.22  5021.5  395.81  5088.8     397
  5119.1  397.09  5216.1  398.77  5272.6  400.66  5329.2  401.72  5428.2   404.9
#Mann= 8 ,-1 , 0
  4309.3    .045       0    4794     .05       0  4902.1    .045       0
  4975.8     .05       0  4978.8     .05       0  4982.8     .05       0
  5021.5    .045       0  5119.1     .05       0
Bank Sta=4978.8,4982.8
XS Rating Curve= 0 ,0
Exp/Cntr=0.3,0.1

Type RM Length L Ch R = 1 ,22943   ,422,422,422
BEGIN DESCRIPTION:
Stream0472 48.0
END DESCRIPTION:
XS GIS Cut Line= 3
      2470175.01     13774475.01        2469625.       13774075.
      2469324.97     13773774.97
#Sta/Elev= 30
  4319.9  413.19  4394.5  409.98  4442.4  408.42  4513.5  405.01  4568.6  403.43
  4681.8   400.8  4705.9  399.93  4777.4  399.24  4841.9  397.79  4850.4  399.76
  4856.6  399.93    4864   402.6  4871.3  403.54    4886  403.13  4906.9  399.97
  4911.8  398.65  4927.7   394.1  5012.1  393.49  5012.4  392.99  5015.9  392.99
  5016.1  393.49  5028.3  393.71  5036.9  395.57  5042.4  397.49  5056.6  397.89
  5074.9  397.36  5084.8  397.07  5169.7     398  5322.8  402.04  5424.3  406.07
#Mann= 10 ,-1 , 0
  4319.9    .045       0  4394.5    .035       0  4568.6     .05       0
  4681.8    .035       0  4911.8    .045       0  5012.1    .045       0
  5016.1    .045       0  5036.9     .05       0  5074.9    .045       0
  5322.8     .05       0
Bank Sta=5012.1,5016.1
XS Rating Curve= 0 ,0
Exp/Cntr=0.3,0.1

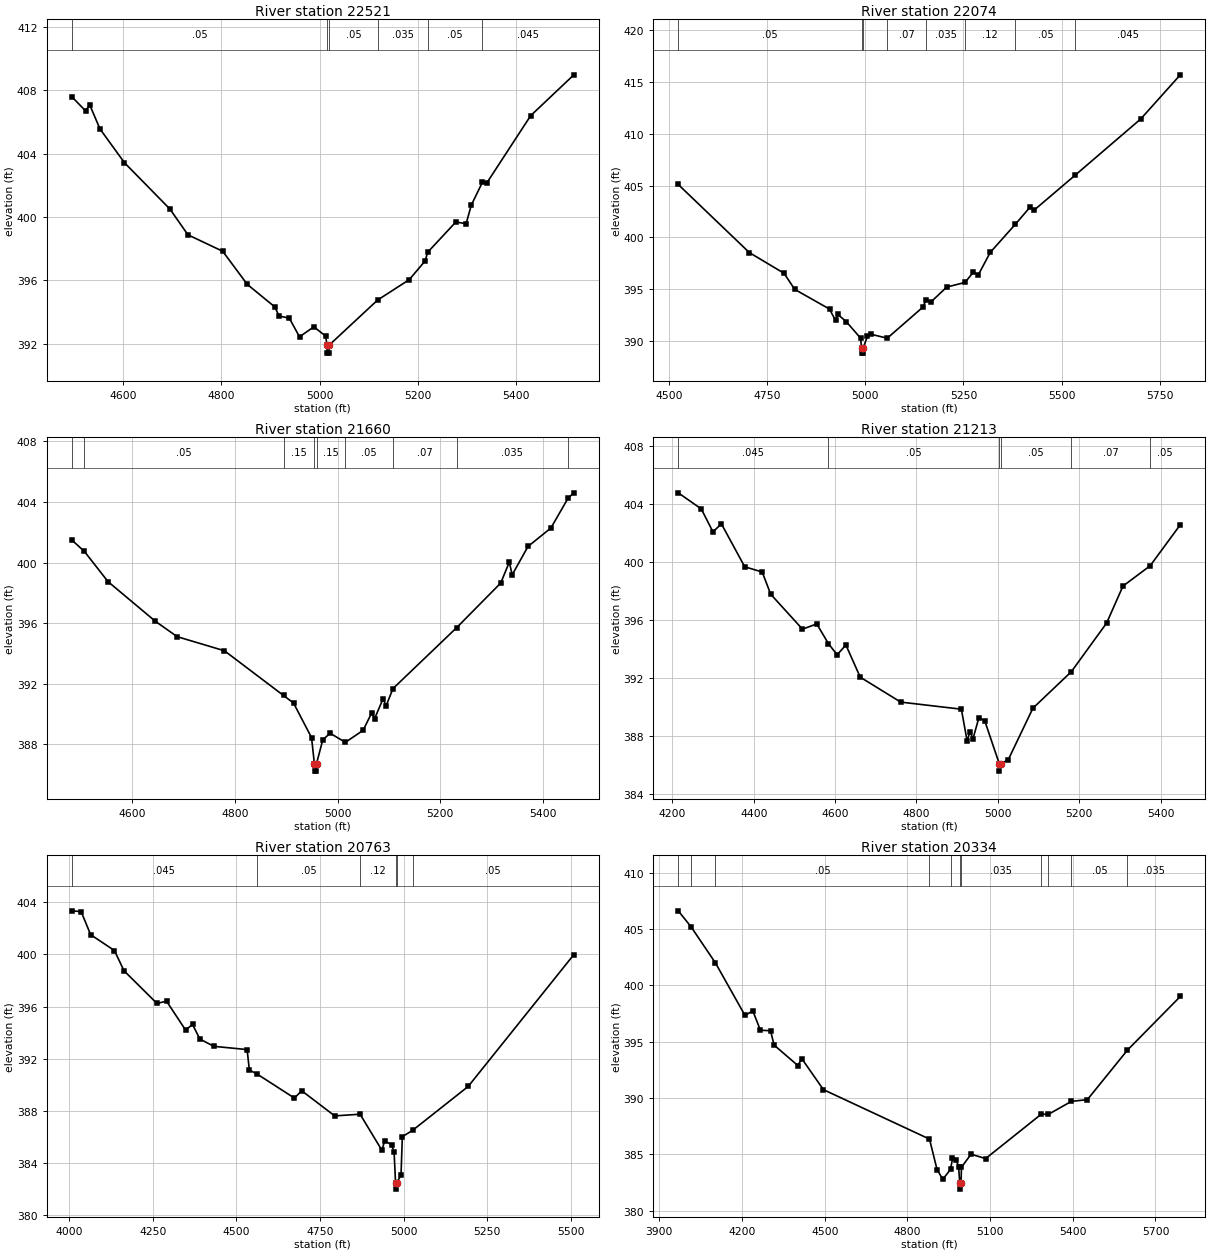
Type RM Length L Ch R = 1 ,22521   ,447,447,447
BEGIN DESCRIPTION:
Stream0472 47.0
END DESCRIPTION:
XS GIS Cut Line= 3
      2470225.04     13774025.03        2469825.       13773725.
      2469324.96     13773574.99
#Sta/Elev= 30
  4495.4  407.59  4523.6  406.69  4531.9  407.08  4552.7  405.56  4602.7  403.42
  4695.4  400.49  4731.9  398.87  4802.7  397.83  4852.7  395.74    4909  394.31
  4917.3  393.74  4938.2  393.61    4959  392.43  4988.2  393.06    5012  392.48
  5015.1   391.9  5015.4   391.4    5019   391.4  5019.2   391.9    5118  394.75
  5182.5  396.04  5214.7  397.22    5220  397.77  5277.3  399.68  5298.2  399.57
  5308.7  400.74  5331.4  402.19    5340  402.13  5429.6  406.39  5517.5  408.97
#Mann= 6 ,-1 , 0
  4495.4     .05       0  5015.1     .05       0  5019.2     .05       0
    5118    .035       0    5220     .05       0  5331.4    .045       0
Bank Sta=5015.1,5019.2
XS Rating Curve= 0 ,0
Exp/Cntr=0.3,0.1

Type RM Length L Ch R = 1 ,22074   ,414,414,414
BEGIN DESCRIPTION:
Stream0472 46.0
END DESCRIPTION:
XS GIS Cut Line= 3
      2470374.97     13773574.98        2469975.       13773325.
      2469174.99       13773225.
#Sta/Elev= 30
    4524   405.1    4705  398.53  4793.4  396.53  4820.5  394.98    4909  393.08
  4924.3  391.99  4930.2  392.56  4951.4  391.88    4988  390.28  4990.6  389.33
  4990.9  388.83  4994.5  388.83  4994.8  389.33  5005.7  390.47  5015.8  390.64
    5056  390.27  5146.8  393.27  5154.9  393.99    5167  393.76  5207.3   395.2
  5253.8  395.65  5275.3  396.64  5287.9  396.39  5318.2  398.55    5382  401.26
  5418.9  402.89    5429   402.6    5535  406.02  5701.1  411.42  5801.9  415.68
#Mann= 8 ,-1 , 0
    4524     .05       0  4990.6     .05       0  4994.8     .05       0
    5056     .07       0  5154.9    .035       0  5253.8     .12       0
    5382     .05       0    5535    .045       0
Bank Sta=4990.6,4994.8
XS Rating Curve= 0 ,0
Exp/Cntr=0.3,0.1

Type RM Length L Ch R = 1 ,21660   ,447,447,447
BEGIN DESCRIPTION:
Stream0472 45.0
END DESCRIPTION:
XS GIS Cut Line= 3
      2470425.01       13773325.        2470025.       13772975.
      2469625.02     13772775.01
#Sta/Elev= 30
  4481.7  401.49  4506.4  400.73  4552.4  398.74  4644.5  396.13  4687.2  395.11
  4779.3  394.18  4894.5  391.23    4914  390.73  4949.1  388.45  4954.6  386.74
  4954.9  386.24  4958.6  386.24  4958.8  386.74    4971   388.3  4985.2  388.74
    5015  388.14  5049.6  388.93  5066.3  390.08  5071.9  389.69  5088.7  391.03
  5094.3  390.53  5107.7  391.68  5232.1  395.71  5317.9  398.65  5334.6  400.03
  5340.2  399.19    5371  401.06  5415.7  402.28  5449.2  404.25  5460.4   404.6
#Mann= 9 ,-1 , 0
  4481.7    .045       0  4506.4     .05       0  4894.5     .15       0
  4954.6     .05       0  4958.8     .15       0    5015     .05       0
  5107.7     .07       0  5232.1    .035       0  5449.2     .05       0
Bank Sta=4954.6,4958.8
XS Rating Curve= 0 ,0
Exp/Cntr=0.3,0.1

Type RM Length L Ch R = 1 ,21213   ,450,450,450
BEGIN DESCRIPTION:
Stream0472 44.0
END DESCRIPTION:
XS GIS Cut Line= 3
      2470675.01     13773225.01        2470175.       13772625.
      2469725.01       13772575.
#Sta/Elev= 30
  4214.5   404.8  4271.1  403.69  4299.8  402.11  4320.6  402.66  4377.9   399.7
  4420.8  399.34  4441.7  397.81  4519.8   395.4  4554.9  395.76  4583.6   394.4
    4605  393.63  4626.5  394.31  4661.7  392.09  4761.2  390.37  4910.3  389.88
  4924.6  387.66  4931.1  388.34  4938.9  387.85  4953.2  389.28  4967.6  389.09
  5003.5  386.11  5003.8  385.61  5007.7  386.11  5025.7  386.41  5086.1  389.95
  5180.6  392.47  5267.2  395.82  5307.4  398.37  5374.2  399.77  5448.3   402.6
#Mann= 6 ,-1 , 0
  4214.5    .045       0  4583.6     .05       0  5003.5     .05       0
  5007.7     .05       0  5180.6     .07       0  5374.2     .05       0
Bank Sta=5003.5,5007.7
XS Rating Curve= 0 ,0
Exp/Cntr=0.3,0.1

Type RM Length L Ch R = 1 ,20763   ,429,429,429
BEGIN DESCRIPTION:
Stream0472 43.0
END DESCRIPTION:
XS GIS Cut Line= 3
        2471075.       13772875.        2470325.       13772225.
      2469824.97     13772325.01
#Sta/Elev= 30
  4007.1  403.35  4035.1  403.29  4063.6  401.52  4134.8   400.3  4163.4  398.75
  4262.1  396.24  4290.6  396.42  4347.6   394.2  4368.5  394.63  4390.3  393.51
  4432.1  392.95  4531.8   392.7  4538.5  391.13  4560.6  390.84  4673.3  388.98
  4695.2  389.54    4794  387.61  4869.8  387.74  4935.4  384.96  4943.1   385.7
  4963.9   385.4  4971.6  384.84    4976  382.49  4976.3  381.99  4980.3  382.49
  4992.4  383.11  4996.3  386.02    5027   386.5  5193.3  389.87  5509.5  399.99
#Mann= 6 ,-1 , 0
  4007.1    .045       0  4560.6     .05       0  4869.8     .12       0
    4976     .05       0  4980.3     .12       0    5027     .05       0
Bank Sta=4976,4980.3
XS Rating Curve= 0 ,0
Exp/Cntr=0.3,0.1

Type RM Length L Ch R = 1 ,20334   ,438,438,438
BEGIN DESCRIPTION:
Stream0472 42.0
END DESCRIPTION:
XS GIS Cut Line= 3
      2471325.03     13772525.03        2470525.       13771875.
      2469774.99       13772125.
#Sta/Elev= 30
  3968.7  406.62  4014.7  405.22  4103.6     402  4210.8  397.34  4239.3  397.74
  4266.8  396.02  4303.5  395.98  4316.6   394.7  4402.6  392.89    4417   393.5
  4495.3  390.75  4880.2  386.36  4907.6  383.66  4928.4  382.79  4956.6  383.67
  4963.6  384.64    4978  384.47  4985.9  383.86  4990.1  382.42  4990.4  381.92
  4994.5  382.42  4996.3  383.87  5031.1  385.02  5083.8  384.63  5285.6  388.57
  5311.6  388.56  5395.2  389.71  5452.8  389.86  5598.4  394.26  5790.1  399.02
#Mann= 11 ,-1 , 0
  3968.7    .045       0  4014.7     .12       0  4103.6     .05       0
  4880.2     .12       0  4956.6    .035       0  4990.1    .035       0
  4994.5    .035       0  5285.6     .05       0  5311.6    .035       0
  5395.2     .05       0  5598.4    .035       0
Bank Sta=4990.1,4994.5
XS Rating Curve= 0 ,0
Exp/Cntr=0.3,0.1

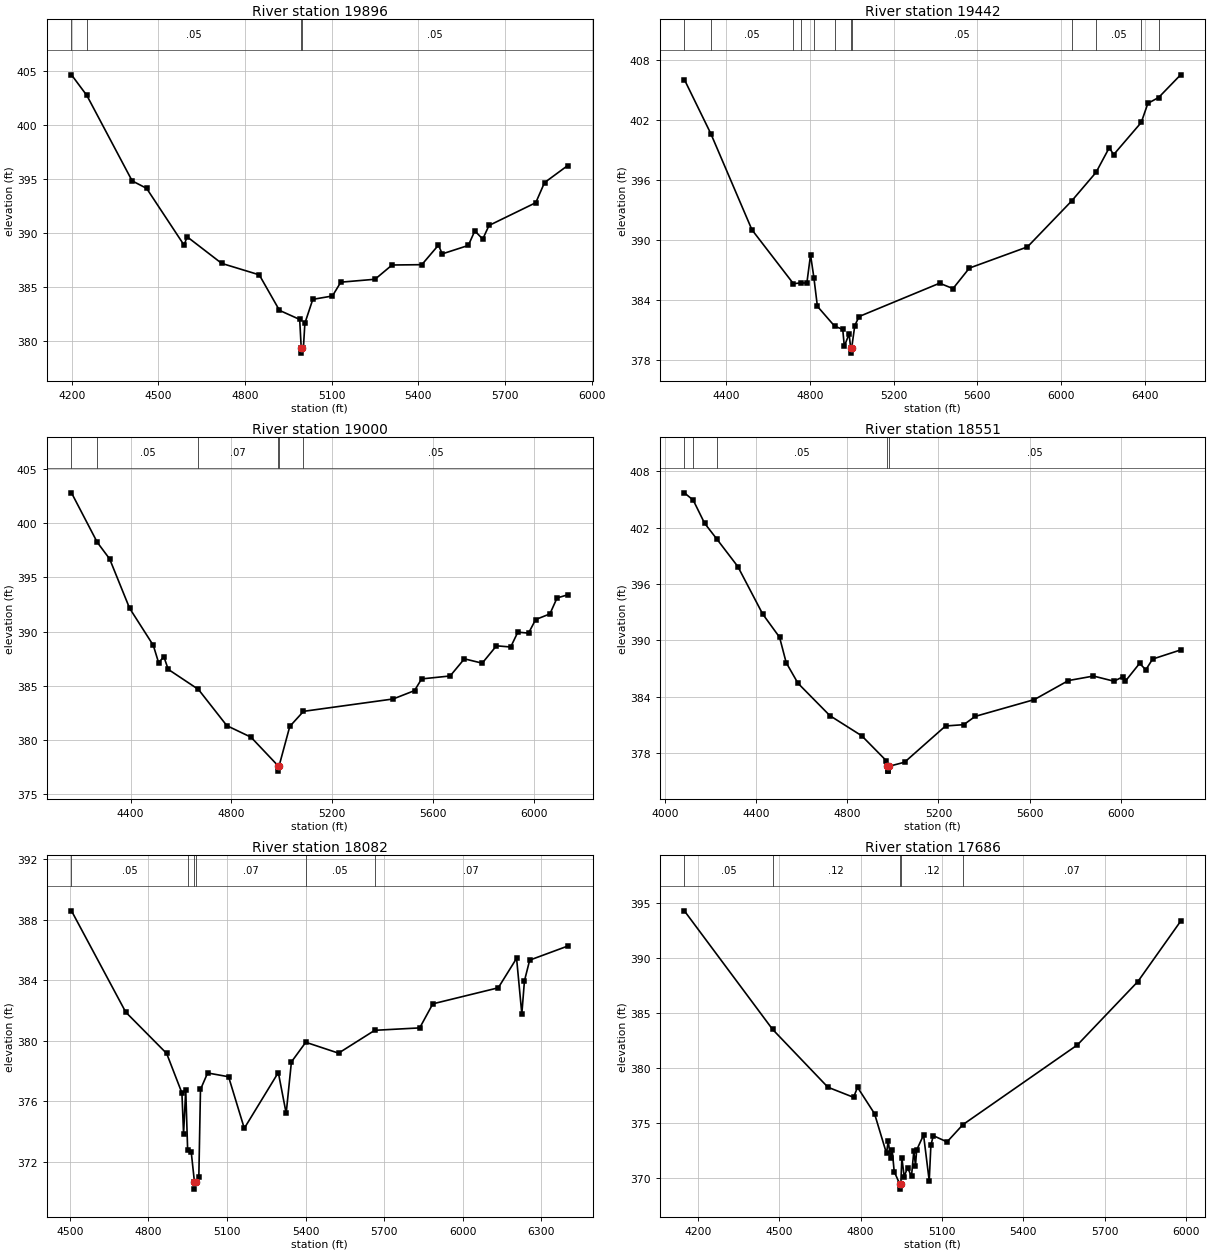
Type RM Length L Ch R = 1 ,19896   ,454,454,454
BEGIN DESCRIPTION:
Stream0472 41.0
END DESCRIPTION:
XS GIS Cut Line= 3
      2471425.03       13771525.        2470625.       13771525.
        2469825.       13771975.
#Sta/Elev= 30
  4199.4  404.65  4252.6  402.74  4409.4  394.83  4459.4  394.14  4589.4  388.87
  4599.4  389.66  4719.4  387.19  4849.4  386.13  4919.4  382.84  4989.4     382
  4994.7  379.38    4995  378.88  4999.1  379.38  5002.3  379.38  5007.4  381.65
  5034.8  383.86  5102.7  384.17  5131.7  385.45  5250.2  385.72  5309.2  387.04
  5412.2  387.07  5469.8  388.88  5482.9  388.07  5573.1  388.85  5595.7   390.2
  5623.1  389.44  5644.8   390.7  5806.7  392.81    5837  394.67  5917.3  396.25
#Mann= 4 ,-1 , 0
  4199.4     .07       0  4252.6     .05       0  4994.7     .05       0
  4999.1     .05       0
Bank Sta=4994.7,4999.1
XS Rating Curve= 0 ,0
Exp/Cntr=0.3,0.1

Type RM Length L Ch R = 1 ,19442   ,442,442,442
BEGIN DESCRIPTION:
Stream0472 40.0
END DESCRIPTION:
XS GIS Cut Line= 3
      2471475.04       13771275.        2470675.       13771175.
      2469475.01     13772174.99
#Sta/Elev= 30
  4201.5  406.05    4328  400.63    4524  391.03    4722  385.64  4757.8  385.72
  4786.1   385.7  4803.7  388.52  4819.6  386.26  4836.4  383.38  4918.4   381.4
  4957.4  381.07  4964.9  379.38  4987.6  380.62  4995.4   379.2  4995.7   378.7
  4999.9   379.2  5014.9  381.46  5035.7  382.36  5419.8  385.69  5483.5  385.15
  5561.6   387.2  5838.9  389.32  6049.8  393.91  6166.3  396.77  6229.4  399.24
  6250.2  398.54    6382  401.76  6413.6  403.67  6464.8  404.25  6569.8  406.52
#Mann= 12 ,-1 , 0
  4201.5     .07       0    4328     .05       0    4722     .07       0
  4757.8     .05       0  4819.6     .07       0  4918.4     .05       0
  4995.4     .05       0  4999.9     .05       0  6049.8     .12       0
  6166.3     .05       0    6382    .035       0  6464.8     .05       0
Bank Sta=4995.4,4999.9
XS Rating Curve= 0 ,0
Exp/Cntr=0.3,0.1

Type RM Length L Ch R = 1 ,19000   ,449,449,449
BEGIN DESCRIPTION:
Stream0472 39.0
END DESCRIPTION:
XS GIS Cut Line= 3
      2471424.99       13771025.        2470625.       13770775.
      2469825.01     13771574.99
#Sta/Elev= 30
  4165.7   402.8    4268  398.24  4317.1  396.71  4396.2  392.17  4490.5  388.74
  4511.4  387.15  4532.4  387.69  4549.7  386.53  4669.5  384.68  4782.3  381.34
  4878.1  380.28  4985.3  377.65  4985.7  377.15  4989.9  377.65  5032.1  381.27
  5086.5  382.66  5442.3   383.8  5527.1  384.57  5555.4  385.65  5668.5  385.92
  5725.1   387.5  5795.8   387.1  5852.4   388.7  5908.9  388.59  5937.2  389.96
  5979.7  389.87  6007.9  391.12  6064.5  391.64  6092.8  393.11  6135.2   393.4
#Mann= 6 ,-1 , 0
  4165.7     .07       0    4268     .05       0  4669.5     .07       0
  4985.3     .05       0  4989.9     .07       0  5086.5     .05       0
Bank Sta=4985.3,4989.9
XS Rating Curve= 0 ,0
Exp/Cntr=0.3,0.1

Type RM Length L Ch R = 1 ,18551   ,469,469,469
BEGIN DESCRIPTION:
Stream0472 38.0
END DESCRIPTION:
XS GIS Cut Line= 3
      2471575.02     13770825.01        2470775.       13770375.
      2469512.14     13770345.78
#Sta/Elev= 30
    4083   405.7  4121.9  404.92  4171.9  402.46  4224.3  400.82  4317.9  397.85
  4427.2  392.79  4501.5  390.31  4530.5  387.61  4582.4  385.41  4722.7  381.96
  4862.9  379.81  4971.3  377.14  4975.7  376.55    4976  376.05    4980  376.05
  4980.3  376.55  5050.9     377    5231  380.86    5311     381    5361  381.88
  5621.1  383.67  5771.1   385.7  5881.1  386.18  5971.2  385.63  6011.2  386.11
  6021.2  385.63  6083.9  387.53  6111.2  386.85  6141.2  387.99  6264.1  388.96
#Mann= 5 ,-1 , 0
    4083     .05       0  4121.9     .07       0  4224.3     .05       0
  4975.7     .05       0  4980.3     .05       0
Bank Sta=4975.7,4980.3
XS Rating Curve= 0 ,0
Exp/Cntr=0.3,0.1

Type RM Length L Ch R = 1 ,18082   ,396,396,396
BEGIN DESCRIPTION:
Stream0472 37.0
END DESCRIPTION:
XS GIS Cut Line= 3
      2471324.97     13770324.98        2470925.       13770025.
      2469529.72     13770036.88
#Sta/Elev= 30
  4505.9  388.59  4713.2  381.89  4869.4  379.16  4927.7  376.55    4934  373.84
  4942.3  376.76  4949.5  372.81  4963.2  372.65  4975.4  370.69  4975.7  370.19
  4980.1  370.69  4992.3     371  4998.6  376.78  5025.9  377.87  5105.9  377.62
  5165.9  374.21  5295.9   377.9  5325.9   375.2  5345.9   378.6  5400.7   379.9
  5525.9  379.18  5664.1  380.69  5835.9  380.85  5885.9  382.44  6135.9   383.5
  6205.9  385.45  6225.9  381.77  6235.9  383.96  6255.9  385.33  6401.2  386.26
#Mann= 6 ,-1 , 0
  4505.9     .05       0  4949.5     .07       0  4975.4     .05       0
  4980.1     .07       0  5400.7     .05       0  5664.1     .07       0
Bank Sta=4975.4,4980.1
XS Rating Curve= 0 ,0
Exp/Cntr=0.3,0.1

Type RM Length L Ch R = 1 ,17686   ,469,469,469
BEGIN DESCRIPTION:
Stream0472 36.0
END DESCRIPTION:
XS GIS Cut Line= 3
      2471574.99     13770224.99        2470875.       13769725.
      2470075.03     13769175.02
#Sta/Elev= 30
  4149.5  394.29  4474.9   383.5  4679.1  378.23  4773.8  377.31  4788.5  378.22
  4851.2  375.82  4895.4   372.2  4901.6  373.35  4910.2  371.78  4916.3  372.53
  4923.7  370.55  4943.5  369.45  4943.8  368.95  4948.2  369.45    4952  371.81
  4960.6  370.09  4972.9   370.9  4987.6  370.12  4996.2  372.45  5002.3  371.09
  5006.6  372.51  5032.1  373.88    5053   369.7  5059.1  372.93  5067.9  373.82
  5118.7  373.25  5177.2  374.82  5599.7  382.08  5822.8  387.85  5980.5  393.34
#Mann= 5 ,-1 , 0
  4149.5     .05       0  4474.9     .12       0  4943.5     .05       0
  4948.2     .12       0  5177.2     .07       0
Bank Sta=4943.5,4948.2
XS Rating Curve= 0 ,0
Exp/Cntr=0.3,0.1

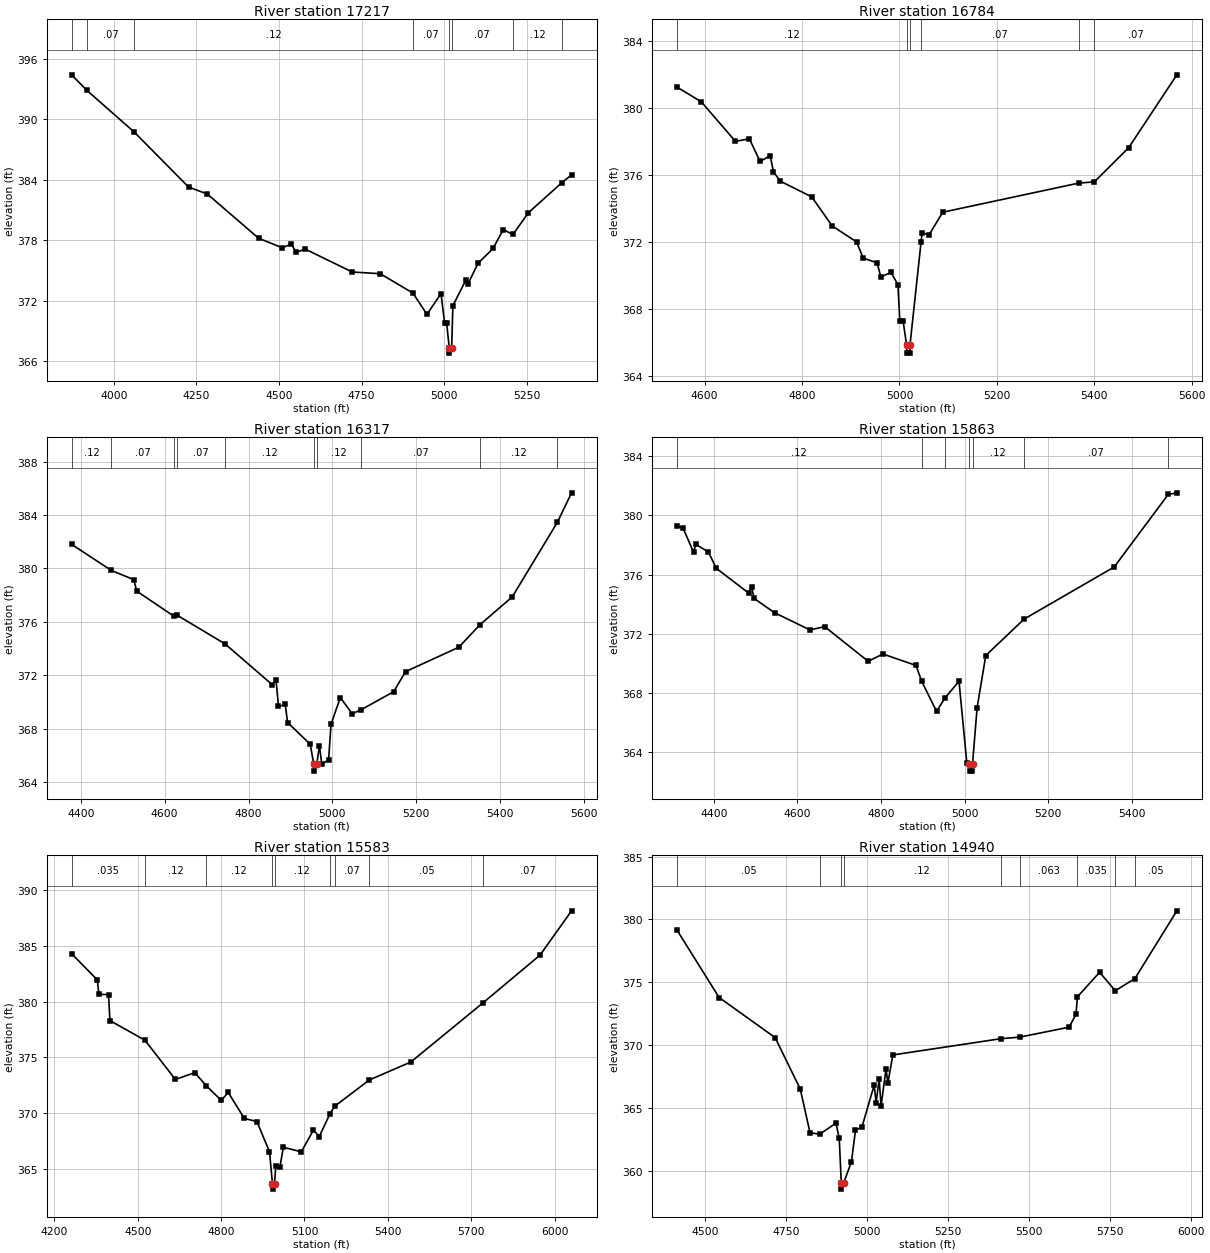
Type RM Length L Ch R = 1 ,17217   ,433,433,433
BEGIN DESCRIPTION:
Stream0472 35.0
END DESCRIPTION:
XS GIS Cut Line= 3
      2471625.03     13770175.03        2470825.       13769375.
        2470475.       13769225.
#Sta/Elev= 30
  3872.7  394.39    3919  392.84  4062.2  388.71  4226.3  383.27  4282.9  382.58
  4438.4  378.19  4509.1  377.26  4537.4   377.6  4551.6  376.81  4579.8  377.11
  4721.3  374.85  4806.1  374.68  4905.1  372.76  4947.5  370.65    4990  372.71
  5000.6  369.84  5006.8  369.84  5015.1  367.31  5015.6  366.81  5022.1  367.31
  5025.9  371.51  5065.8   374.1  5071.2  373.63    5102  375.72  5147.4  377.18
  5178.2  379.05  5207.6  378.57  5254.3  380.72  5355.7  383.71  5384.9  384.47
#Mann= 8 ,-1 , 0
  3872.7     .05       0    3919     .07       0  4062.2     .12       0
  4905.1     .07       0  5015.1     .05       0  5022.1     .07       0
  5207.6     .12       0  5355.7     .07       0
Bank Sta=5015.1,5022.1
XS Rating Curve= 0 ,0
Exp/Cntr=0.3,0.1

Type RM Length L Ch R = 1 ,16784   ,467,467,467
BEGIN DESCRIPTION:
Stream0472 34.0
END DESCRIPTION:
XS GIS Cut Line= 3
      2471474.99     13769574.98        2471175.       13769225.
      2470775.03     13768825.03
#Sta/Elev= 30
  4543.1  381.23    4593  380.35  4663.3  377.99  4691.8  378.14  4713.8  376.79
  4734.6  377.14  4741.2  376.17  4755.5  375.61  4819.7  374.68  4861.9  372.94
  4911.9  371.99  4925.6  371.02  4954.1  370.74  4961.8   369.9  4982.7  370.17
  4996.9  369.43  5000.8  367.24  5007.6  367.24  5014.6  365.85  5015.1  365.35
  5021.2  365.35  5021.7  365.85  5044.5  372.01  5046.5  372.54  5060.6   372.4
  5088.9  373.76  5368.5   375.5  5400.1  375.57  5470.7  377.61  5569.7  381.96
#Mann= 6 ,-1 , 0
  4543.1     .12       0  5014.6     .05       0  5021.7     .12       0
  5044.5     .07       0  5368.5     .12       0  5400.1     .07       0
Bank Sta=5014.6,5021.7
XS Rating Curve= 0 ,0
Exp/Cntr=0.3,0.1

Type RM Length L Ch R = 1 ,16317   ,454,454,454
BEGIN DESCRIPTION:
Stream0472 33.0
END DESCRIPTION:
XS GIS Cut Line= 3
      2471625.02     13769475.03        2471325.       13768925.
      2470925.01     13768525.01
#Sta/Elev= 30
  4378.2   381.8  4472.6  379.85  4526.3  379.16  4533.4   378.3    4623   376.4
    4630  376.49  4743.9  374.35  4856.7  371.29  4865.7  371.64  4871.4  369.66
  4887.5  369.81  4893.2  368.46  4947.3  366.83  4955.6  365.32  4956.1  364.82
  4962.7  365.32  4969.1  366.72  4974.8  365.33    4991  365.67  4996.7  368.32
  5018.9  370.33  5047.2  369.12  5068.8  369.42  5146.2  370.77  5174.4  372.27
  5301.7   374.1  5352.1  375.79    5429  377.87  5536.3  383.44  5570.4  385.66
#Mann= 10 ,-1 , 0
  4378.2     .12       0  4472.6     .07       0    4623     .12       0
    4630     .07       0  4743.9     .12       0  4955.6     .05       0
  4962.7     .12       0  5068.8     .07       0  5352.1     .12       0
  5536.3     .07       0
Bank Sta=4955.6,4962.7
XS Rating Curve= 0 ,0
Exp/Cntr=0.3,0.1

Type RM Length L Ch R = 1 ,15863   ,280,280,280
BEGIN DESCRIPTION:
Stream0472 32.0
END DESCRIPTION:
XS GIS Cut Line= 3
      2471775.01     13769225.01        2471525.       13768575.
      2471125.03     13768275.02
#Sta/Elev= 30
  4311.6  379.28  4326.6  379.12  4351.3   377.5  4356.6  378.04  4386.6  377.53
  4405.9  376.42    4483  374.75  4490.5  375.18  4495.9  374.39  4545.2  373.42
  4629.8  372.26  4665.2  372.48  4769.1  370.14  4804.5  370.63  4883.7  369.86
  4897.4  368.78    4933  366.75  4952.3  367.64  4986.6  368.79  5005.4  363.25
  5011.7  363.22  5012.2  362.72  5018.5  362.72    5019  363.22  5029.9     367
  5050.7  370.53  5142.4  372.99    5358  376.51  5487.3  381.41    5508  381.52
#Mann= 7 ,-1 , 0
  4311.6     .12       0  4897.4     .12       0  4952.3     .12       0
  5011.7     .05       0    5019     .12       0  5142.4     .07       0
  5487.3     .12       0
Bank Sta=5011.7,5019
XS Rating Curve= 0 ,0
Exp/Cntr=0.3,0.1

Type RM Length L Ch R = 1 ,15583   ,643,643,643
BEGIN DESCRIPTION:
Stream0472 31.0
END DESCRIPTION:
XS GIS Cut Line= 3
        2471975.     13769325.02      2471803.14     13768681.18
      2471125.01     13767775.01
#Sta/Elev= 30
  4262.5  384.29    4355  381.94  4360.2  380.65  4395.1  380.63  4400.2   378.3
  4525.9  376.55  4635.6  373.03  4705.4  373.64  4746.5  372.47  4800.7  371.16
  4825.7  371.87  4883.5  369.54  4928.9  369.26  4974.1  366.56  4984.8  363.71
  4985.3  363.21  4992.2  363.71  4996.8  365.25  5011.4  365.17    5024  366.96
  5088.5  366.55  5132.3   368.5  5153.1  367.92    5192  369.97  5208.5  370.63
  5333.5  372.99  5482.4  374.59  5743.1  379.91  5947.1  384.16  6060.7  388.13
#Mann= 9 ,-1 , 0
  4262.5    .035       0  4525.9     .12       0  4746.5     .12       0
  4984.8     .05       0  4992.2     .12       0    5192     .12       0
  5208.5     .07       0  5333.5     .05       0  5743.1     .07       0
Bank Sta=4984.8,4992.2
XS Rating Curve= 0 ,0
Exp/Cntr=0.3,0.1

Type RM Length L Ch R = 1 ,14940   ,459,459,459
BEGIN DESCRIPTION:
Stream0472 30.0
END DESCRIPTION:
XS GIS Cut Line= 3
        2472225.       13769125.        2472275.       13768525.
      2471774.99     13767724.98
#Sta/Elev= 30
  4412.1  379.15  4542.5  373.78  4715.6  370.59  4793.4  366.49  4823.5  363.01
  4853.7  362.91  4903.8  363.78  4913.8  362.57  4920.1  359.03  4920.6  358.53
  4927.6  359.03  4951.5  360.71    4964  363.21  4984.1  363.48  5021.8  366.81
  5027.7  365.41  5037.2  367.27  5043.1  365.16  5058.4  368.07  5064.3     367
  5079.6  369.21  5412.6   370.5  5472.4  370.63  5624.4  371.42  5645.7  372.45
  5650.2  373.84  5718.8  375.79  5767.2  374.32  5827.9  375.29  5957.6  380.68
#Mann= 9 ,-1 , 0
  4412.1     .05       0  4853.7     .12       0  4920.1     .05       0
  4927.6     .12       0  5412.6     .07       0  5472.4    .063       0
  5650.2    .035       0  5767.2    .063       0  5827.9     .05       0
Bank Sta=4920.1,4927.6
XS Rating Curve= 0 ,0
Exp/Cntr=0.3,0.1