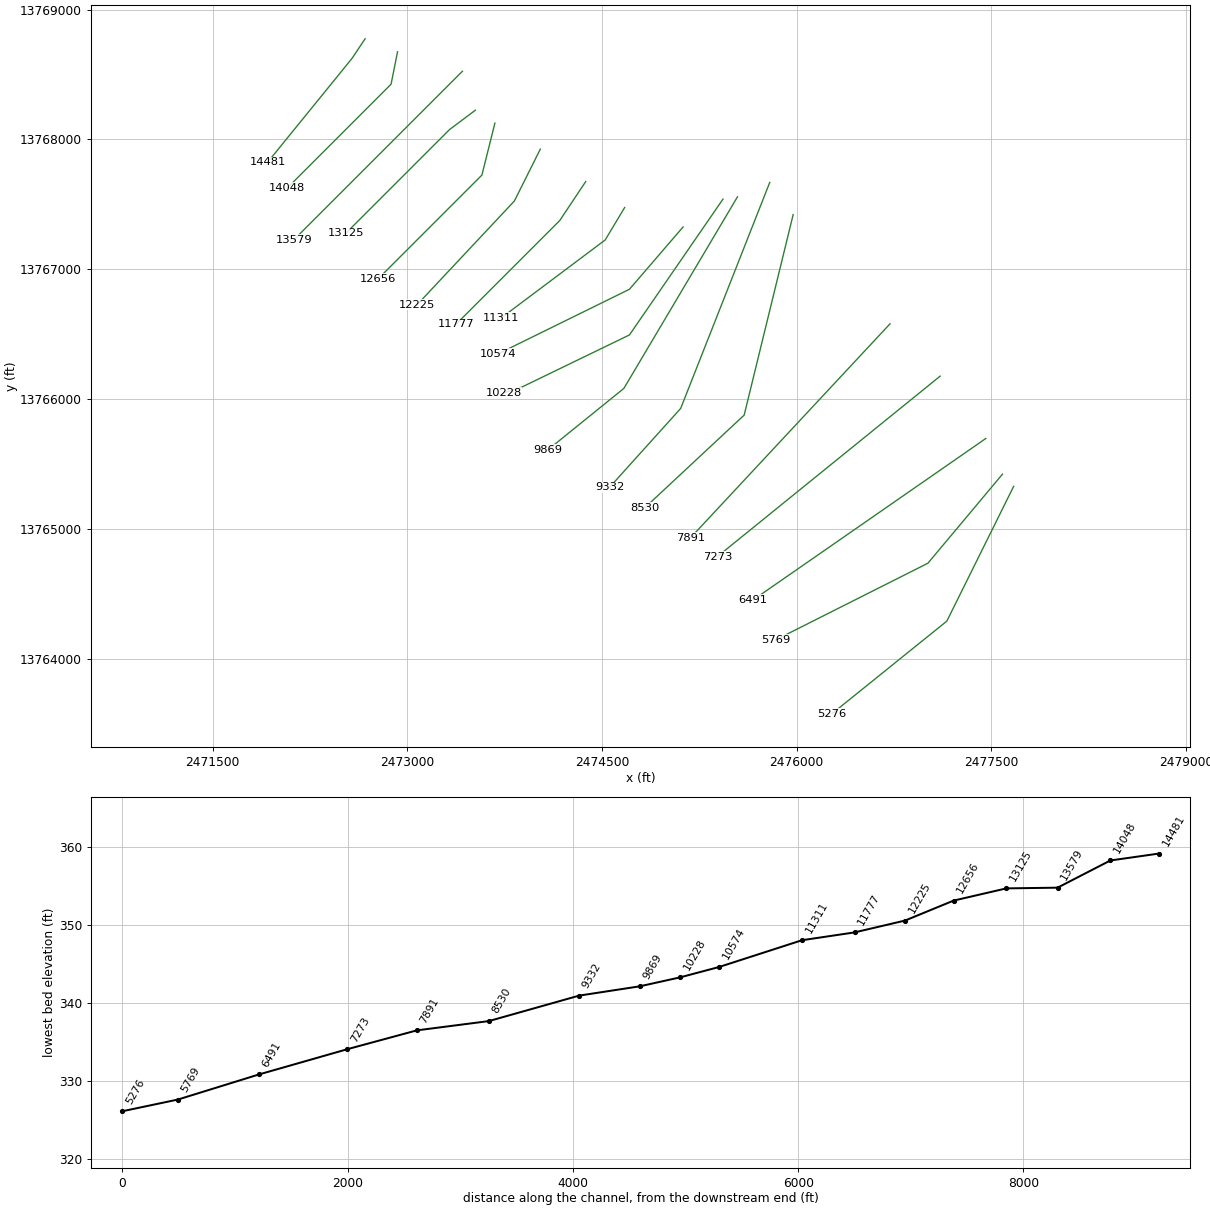
HEC-RAS study Stream0472.prj: Stream0472 Base Level Engineering

--- Stream0472.g01 (geometry) --- (continued)

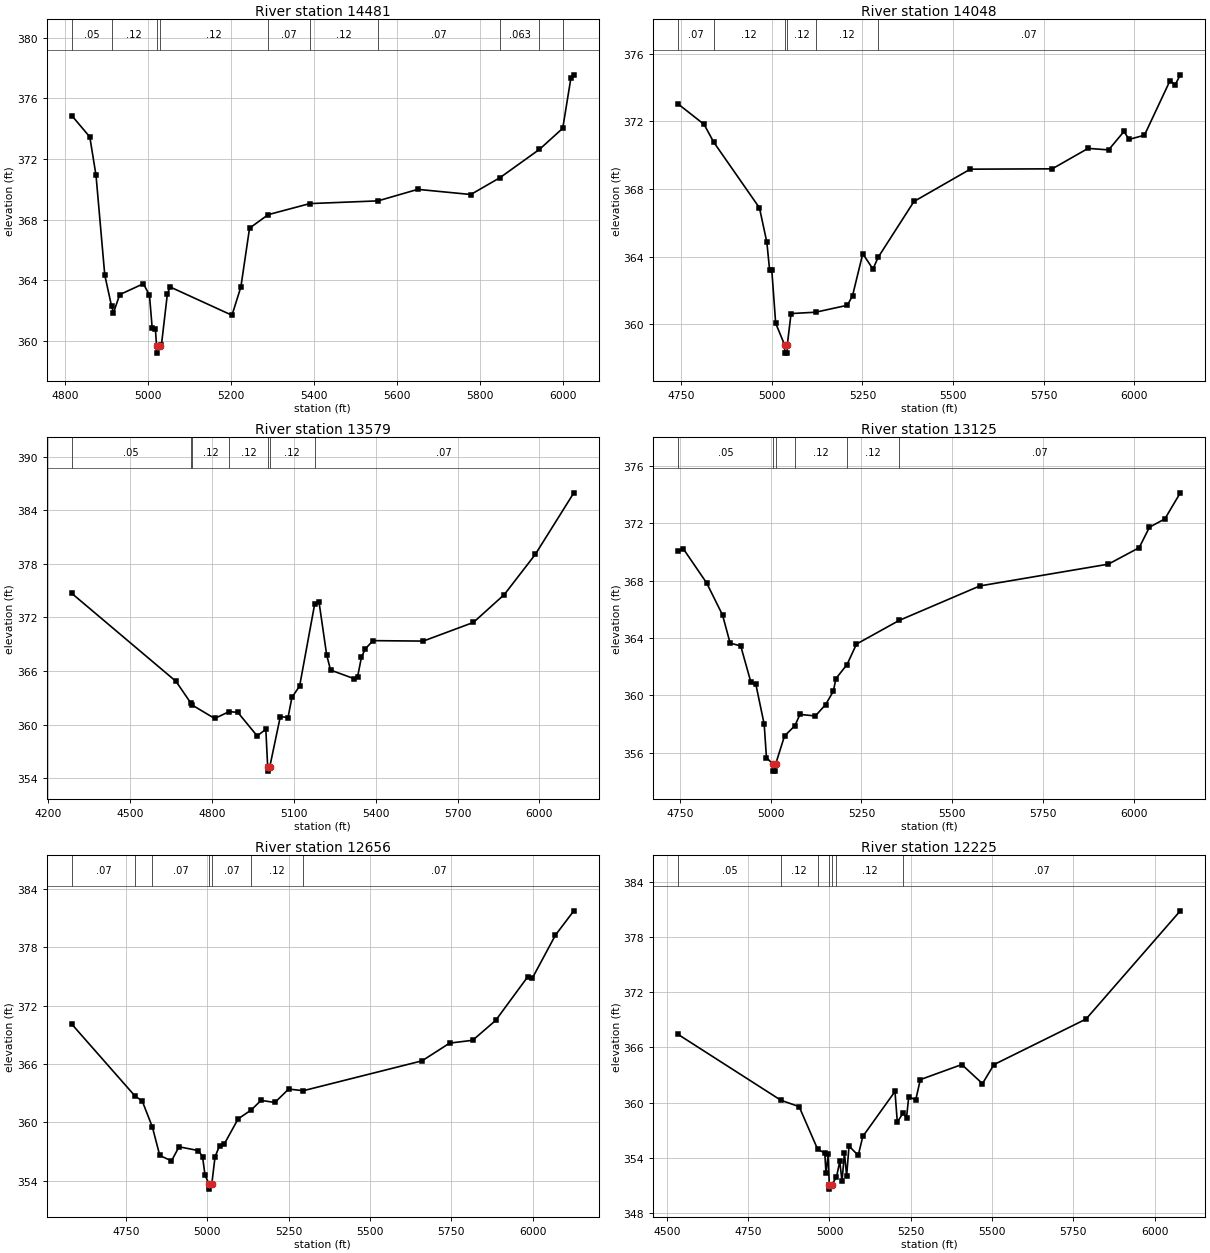
Type RM Length L Ch R = 1 ,14481   ,433,433,433
BEGIN DESCRIPTION:
Stream0472 29.0
END DESCRIPTION:
XS GIS Cut Line= 3
      2472674.98     13768774.97        2472575.       13768625.
      2471925.01     13767825.01
#Sta/Elev= 30
  4815.3  374.86  4858.8  373.45  4873.8  370.91  4894.9  364.33  4911.2  362.29
  4915.9  361.84  4930.9  363.04    4988  363.76  5002.7  363.01  5009.2  360.85
  5017.1  360.75  5019.7  359.68  5020.2  359.18  5027.3  359.68  5031.5   359.7
  5045.8  363.07  5052.3  363.55  5201.7  361.68  5223.2  363.55  5244.1  367.43
  5289.1  368.32  5389.3  369.05  5553.9  369.23  5649.9  369.99  5777.8  369.65
  5848.6  370.77  5943.4  372.63  5999.5  374.02  6019.1  377.32  6026.3  377.55
#Mann= 10 ,-1 , 0
  4815.3     .05       0  4911.2     .12       0  5019.7     .05       0
  5027.3     .12       0  5289.1     .07       0  5389.3     .12       0
  5553.9     .07       0  5848.6    .063       0  5943.4    .035       0
  5999.5    .063       0
Bank Sta=5019.7,5027.3
XS Rating Curve= 0 ,0
Exp/Cntr=0.3,0.1

Type RM Length L Ch R = 1 ,14048   ,469,469,469
BEGIN DESCRIPTION:
Stream0472 28.0
END DESCRIPTION:
XS GIS Cut Line= 3
      2472924.99     13768674.95        2472875.       13768425.
      2472074.98     13767624.98
#Sta/Elev= 30
  4741.4  373.02  4812.7  371.82  4839.3  370.77  4965.7  366.88  4986.1  364.84
  4993.8  363.18  4999.8  363.18  5010.4  360.06  5034.9  358.79  5035.4  358.29
  5042.1  358.29  5042.6  358.79  5052.9  360.63  5120.8  360.71  5208.4  361.12
  5222.6  361.68  5250.9  364.17  5279.1  363.26  5293.2  363.95  5392.3  367.26
  5547.8  369.17  5774.1  369.19  5873.1   370.4  5929.7  370.31  5972.1   371.4
  5986.3  370.93  6028.7  371.18  6099.4  374.41  6113.5  374.16  6127.7  374.75
#Mann= 6 ,-1 , 0
  4741.4     .07       0  4839.3     .12       0  5034.9     .05       0
  5042.6     .12       0  5120.8     .12       0  5293.2     .07       0
Bank Sta=5034.9,5042.6
XS Rating Curve= 0 ,0
Exp/Cntr=0.3,0.1

Type RM Length L Ch R = 1 ,13579   ,454,454,454
BEGIN DESCRIPTION:
Stream0472 27.0
END DESCRIPTION:
XS GIS Cut Line= 3
      2473424.97     13768524.97        2472925.       13768025.
      2472125.02     13767225.02
#Sta/Elev= 30
  4287.5  374.69  4669.3  364.84  4722.9  362.44  4728.5  362.19  4810.7  360.69
  4863.9  361.46  4895.6  361.37  4966.3  358.74  4998.1  359.48  5004.8   355.3
  5005.3   354.8  5012.6   355.3  5051.1   360.9  5079.4   360.8  5093.6  363.05
  5121.8  364.32  5176.9  373.49  5192.6  373.77  5220.8  367.81    5235  366.11
  5319.8  365.16    5334  365.35  5348.1  367.54  5362.3  368.48  5390.5   369.4
  5574.4  369.35  5758.2  371.44  5871.4  374.56  5984.5  379.04  6125.9  385.94
#Mann= 7 ,-1 , 0
  4287.5     .05       0  4722.9     .07       0  4728.5     .12       0
  4863.9     .12       0  5004.8     .05       0  5012.6     .12       0
  5176.9     .07       0
Bank Sta=5004.8,5012.6
XS Rating Curve= 0 ,0
Exp/Cntr=0.3,0.1

Type RM Length L Ch R = 1 ,13125   ,469,469,469
BEGIN DESCRIPTION:
Stream0472 26.0
END DESCRIPTION:
XS GIS Cut Line= 3
        2473525.       13768225.        2473325.       13768075.
      2472524.98     13767274.98
#Sta/Elev= 30
  4745.9  370.07  4759.4  370.25    4824  367.85  4867.8  365.61  4888.6  363.65
  4917.8  363.45  4945.9  360.91  4959.4  360.78  4982.4  357.98  4988.6  355.65
  5006.1  355.21  5006.6  354.71  5013.5  354.71    5014  355.21  5038.3  357.16
  5067.1  357.89  5080.8  358.67  5123.2  358.56  5151.5  359.36  5172.7  360.29
  5179.7  361.17  5210.3  362.15  5236.3  363.58  5353.6  365.23  5575.7  367.64
  5929.3  369.16  6014.1  370.31  6042.4  371.74  6084.8  372.32  6127.3  374.14
#Mann= 6 ,-1 , 0
  4745.9     .05       0  5006.1     .05       0    5014     .05       0
  5067.1     .12       0  5210.3     .12       0  5353.6     .07       0
Bank Sta=5006.1,5014
XS Rating Curve= 0 ,0
Exp/Cntr=0.3,0.1

Type RM Length L Ch R = 1 ,12656   ,431,431,431
BEGIN DESCRIPTION:
Stream0472 25.0
END DESCRIPTION:
XS GIS Cut Line= 3
      2473674.99     13768124.95        2473575.       13767725.
      2472775.02     13766925.02
#Sta/Elev= 30
  4583.2  370.09  4777.7   362.7  4799.6  362.21  4831.1  359.51  4853.7   356.6
  4889.8  356.04    4913  357.49  4972.3   357.1  4985.2  356.49  4992.9  354.57
  5005.6  353.64  5006.1  353.14  5013.6  353.64  5023.7  356.46  5037.9  357.62
    5052  357.77  5094.5  360.35  5135.2  361.28  5165.2  362.26  5207.6  362.04
    5250  363.42    5295  363.25  5660.1  366.32    5745  368.14  5815.7  368.43
  5886.4  370.47  5985.4  374.97  5999.6  374.84  6070.3  379.24  6126.8  381.73
#Mann= 7 ,-1 , 0
  4583.2     .07       0  4777.7     .12       0  4831.1     .07       0
  5005.6     .05       0  5013.6     .07       0  5135.2     .12       0
    5295     .07       0
Bank Sta=5005.6,5013.6
XS Rating Curve= 0 ,0
Exp/Cntr=0.3,0.1

Type RM Length L Ch R = 1 ,12225   ,448,448,448
BEGIN DESCRIPTION:
Stream0472 24.0
END DESCRIPTION:
XS GIS Cut Line= 3
        2474025.       13767925.        2473825.       13767525.
        2473075.       13766725.
#Sta/Elev= 30
  4534.9  367.41  4850.7  360.25  4906.6  359.56  4963.6  354.92  4985.5  354.51
  4989.2   352.3    4996  354.37  4999.3  351.08  4999.8  350.58  5007.4  351.08
  5021.3  351.87  5031.7   353.6  5038.5  351.42  5045.9  354.51  5052.7  352.02
    5060  355.27  5088.3  354.25  5102.5  356.32  5201.4  361.21  5208.5  357.88
  5226.7  358.88  5236.8  358.34  5243.7  360.63  5265.2   360.3  5279.3   362.5
  5406.8  364.14  5470.3  362.06  5505.5  364.13  5788.8  369.09  6078.7  380.87
#Mann= 7 ,-1 , 0
  4534.9     .05       0  4850.7     .12       0  4963.6     .12       0
  4999.3     .05       0  5007.4     .12       0  5021.3     .12       0
  5226.7     .07       0
Bank Sta=4999.3,5007.4
XS Rating Curve= 0 ,0
Exp/Cntr=0.3,0.1

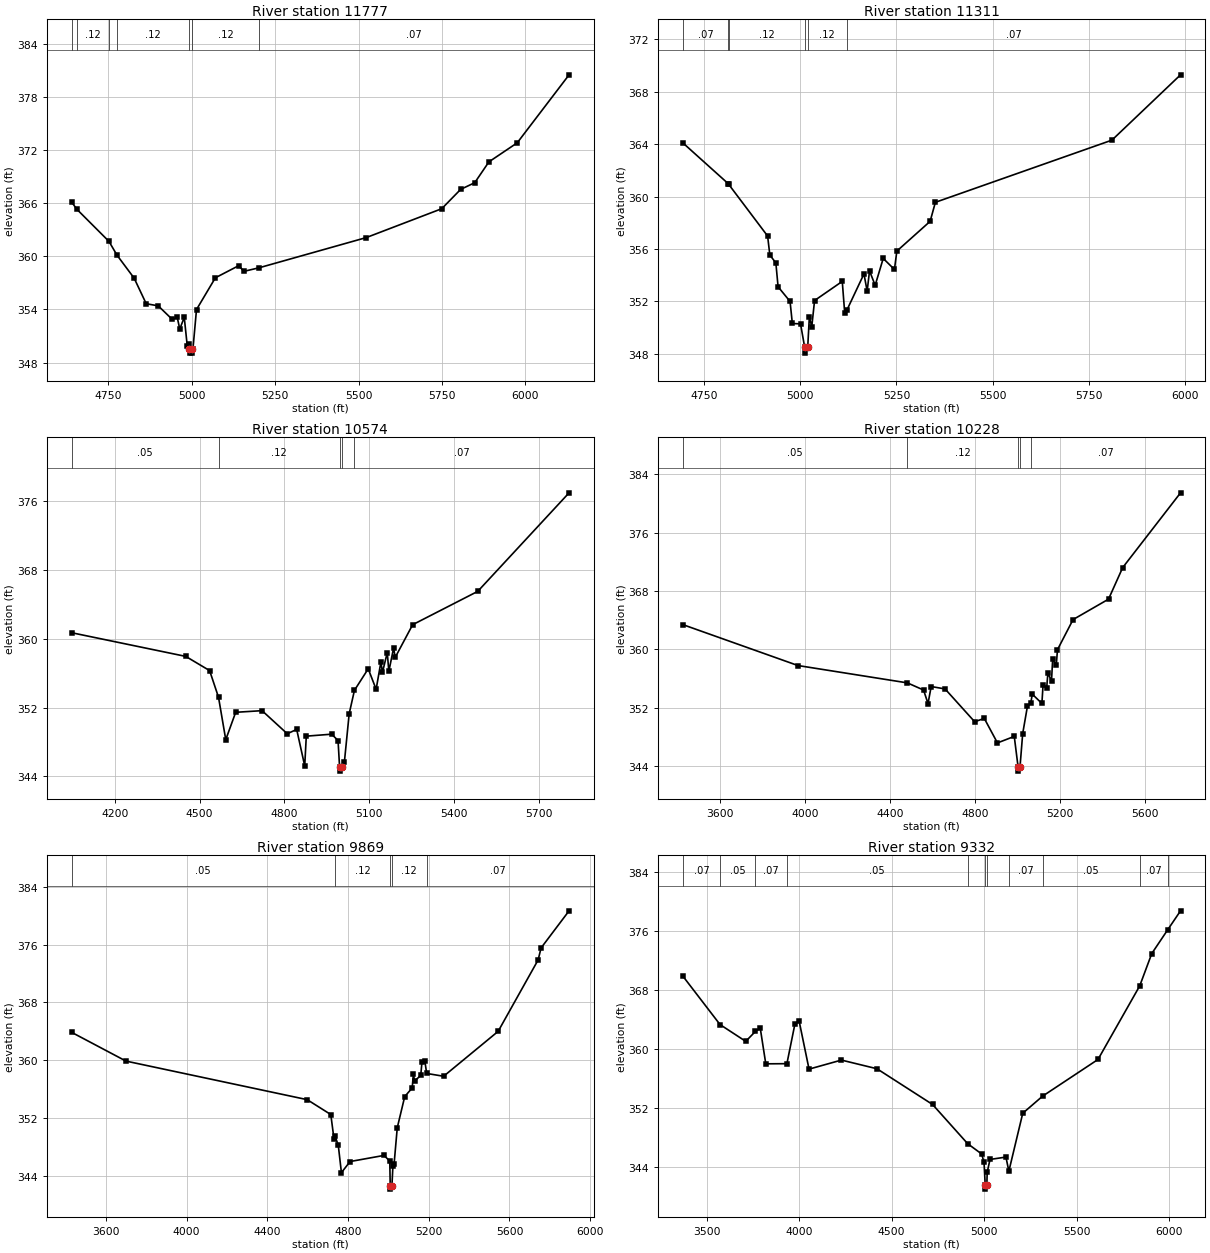
Type RM Length L Ch R = 1 ,11777   ,466,466,466
BEGIN DESCRIPTION:
Stream0472 23.0
END DESCRIPTION:
XS GIS Cut Line= 3
      2474375.01     13767675.01        2474175.       13767375.
      2473375.03     13766575.03
#Sta/Elev= 30
  4639.3  366.14  4654.9  365.32  4751.5  361.68  4775.5  360.13  4827.1  357.52
  4863.2  354.64  4899.2   354.4  4941.3  352.87  4956.3  353.09  4963.8  351.78
  4977.3   353.1  4986.4  349.83  4992.4  350.13  4992.8  349.56  4993.3  349.06
  5000.5  349.06    5001  349.56  5003.4  349.56    5014  353.98  5070.6  357.57
  5141.3  358.95  5155.4  358.29  5201.8   358.7  5523.1  362.11  5749.4  365.37
    5806  367.55  5848.4  368.31  5890.8  370.66  5975.7  372.81  6131.2  380.49
#Mann= 7 ,-1 , 0
  4639.3     .07       0  4654.9     .12       0  4751.5     .07       0
  4775.5     .12       0  4992.8     .05       0    5001     .12       0
  5201.8     .07       0
Bank Sta=4992.8,5001
XS Rating Curve= 0 ,0
Exp/Cntr=0.3,0.1

Type RM Length L Ch R = 1 ,11311   ,737,737,737
BEGIN DESCRIPTION:
Stream0472 22.0
END DESCRIPTION:
XS GIS Cut Line= 3
      2474674.99     13767474.98        2474525.       13767225.
      2473725.02     13766625.02
#Sta/Elev= 30
  4695.9  364.08  4813.7  360.97  4814.2  360.94  4915.5  356.99  4921.3  355.54
  4936.9  354.94  4942.7  353.12  4973.8     352  4979.7  350.32    5001  350.29
  5011.4  348.56  5011.9  348.06  5019.7  348.56  5023.9  350.83  5030.1  350.07
  5037.4  352.07  5109.3  353.53  5115.6  351.13    5121  351.32  5165.6   354.1
  5173.9  352.79  5180.1  354.33  5194.7  353.23  5215.6  355.28  5244.7  354.44
    5251  355.84  5337.4  358.11    5351  359.56  5809.3   364.3  5987.4  369.28
#Mann= 6 ,-1 , 0
  4695.9     .07       0  4813.7     .05       0  4814.2     .12       0
  5011.4     .05       0  5019.7     .12       0    5121     .07       0
Bank Sta=5011.4,5019.7
XS Rating Curve= 0 ,0
Exp/Cntr=0.3,0.1

Type RM Length L Ch R = 1 ,10574   ,346,346,346
BEGIN DESCRIPTION:
Stream0472 21.0
END DESCRIPTION:
XS GIS Cut Line= 3
      2475125.01     13767325.01       2474711.9     13766844.97
      2473699.69     13766347.44
#Sta/Elev= 30
  4046.9  360.69  4451.2  357.94  4535.7  356.29  4567.2  353.19  4592.8  348.27
  4627.9  351.45  4721.3  351.64  4810.5  348.96  4843.9  349.46  4872.3  345.23
  4877.9  348.68  4967.8  348.91  4990.3  348.17  4995.7  345.12  4996.2  344.62
  5004.1  345.12  5012.7  345.66  5029.7  351.28  5048.3     354  5097.1   356.5
  5125.1  354.12    5142  357.28  5147.6  356.09  5164.5  358.39  5170.1   356.2
    5187  358.93  5192.6  357.82  5254.4  361.62  5484.8  365.49  5808.1  376.93
#Mann= 5 ,-1 , 0
  4046.9     .05       0  4567.2     .12       0  4995.7     .05       0
  5004.1     .12       0  5048.3     .07       0
Bank Sta=4995.7,5004.1
XS Rating Curve= 0 ,0
Exp/Cntr=0.3,0.1

Type RM Length L Ch R = 1 ,10228   ,359,359,359
BEGIN DESCRIPTION:
XS6890
END DESCRIPTION:
XS GIS Cut Line= 4
      2475432.65     13767539.98       2474711.9     13766493.17
       2473879.6     13766089.89      2473742.34       13766047.
#Sta/Elev= 30
  3425.8  363.37  3966.1  357.77    4481  355.39    4557  354.41  4577.9  352.55
  4592.8  354.89  4658.1  354.56  4797.3  350.06  4842.5  350.52  4904.4  347.16
  4983.5  348.05  5001.8  343.79  5002.3  343.29  5010.3  343.79  5023.1  348.43
  5045.7  352.23  5060.8  352.57  5068.3  353.84  5113.4  352.57    5119  355.13
    5136  354.69  5141.5  356.74  5158.6  355.66  5164.1  358.63  5181.1  357.83
  5186.7  359.94    5260  364.07  5426.7  366.87  5493.4   371.2  5765.4  381.45
#Mann= 5 ,-1 , 0
  3425.8     .05       0    4481     .12       0  5001.8     .05       0
  5010.3     .12       0  5060.8     .07       0
Bank Sta=5001.8,5010.3
XS Rating Curve= 0 ,0
Exp/Cntr=0.3,0.1

Type RM Length L Ch R = 1 ,9869    ,537,537,537
BEGIN DESCRIPTION:
XS6889
END DESCRIPTION:
XS GIS Cut Line= 3
       2475544.2     13767557.14        2474669.     13766081.31
      2474085.88     13765609.67
#Sta/Elev= 30
  3429.5  363.86  3699.4  359.87  4597.4  354.53  4714.4  352.47    4730  349.14
  4734.8  349.52  4751.4  348.23    4767  344.42  4809.9  345.96  4978.3  346.81
  5006.7  346.02  5008.9  342.64  5009.4  342.14  5017.4  342.64  5022.3  345.36
  5028.2  345.66  5043.8  350.64  5080.8  354.96  5117.8  356.15  5123.7  358.06
  5129.5   357.1  5160.1  357.89  5166.5  359.81  5180.9  359.82  5189.5  358.16
  5273.6  357.77  5543.8  363.99  5742.1  373.89  5756.5  375.54  5895.3  380.68
#Mann= 5 ,-1 , 0
  3429.5     .05       0  4734.8     .12       0  5008.9     .05       0
  5017.4     .12       0  5189.5     .07       0
Bank Sta=5008.9,5017.4
XS Rating Curve= 0 ,0
Exp/Cntr=0.3,0.1

Type RM Length L Ch R = 1 ,9332    ,802,802,802
BEGIN DESCRIPTION:
XS6888
END DESCRIPTION:
XS GIS Cut Line= 3
      2475793.02     13767668.65       2475106.6     13765926.87
      2474559.76     13765320.21
#Sta/Elev= 30
  3372.4  369.84  3572.5  363.29  3711.4  361.01  3763.8  362.36  3789.9   362.8
  3819.7  357.96  3933.9  357.98  3976.8  363.32  3999.7   363.8  4053.5  357.24
  4228.5  358.47  4420.7  357.29  4721.2  352.44  4910.8  347.12  4986.5  345.72
  4999.3  344.58  5005.8  341.45  5006.3  340.95  5014.4  341.45  5016.3  343.23
  5031.6  344.98  5117.6   345.3  5133.5  343.39  5208.5  351.25  5315.7  353.57
  5615.1  358.55  5840.7  368.54  5905.8  372.93  5991.7  376.15  6061.3  378.73
#Mann= 11 ,-1 , 0
  3372.4     .07       0  3572.5     .05       0  3763.8     .07       0
  3933.9     .05       0  4910.8     .12       0  5005.8     .05       0
  5014.4     .12       0  5133.5     .07       0  5315.7     .05       0
  5840.7     .07       0  5991.7     .05       0
Bank Sta=5005.8,5014.4
XS Rating Curve= 0 ,0
Exp/Cntr=0.3,0.1

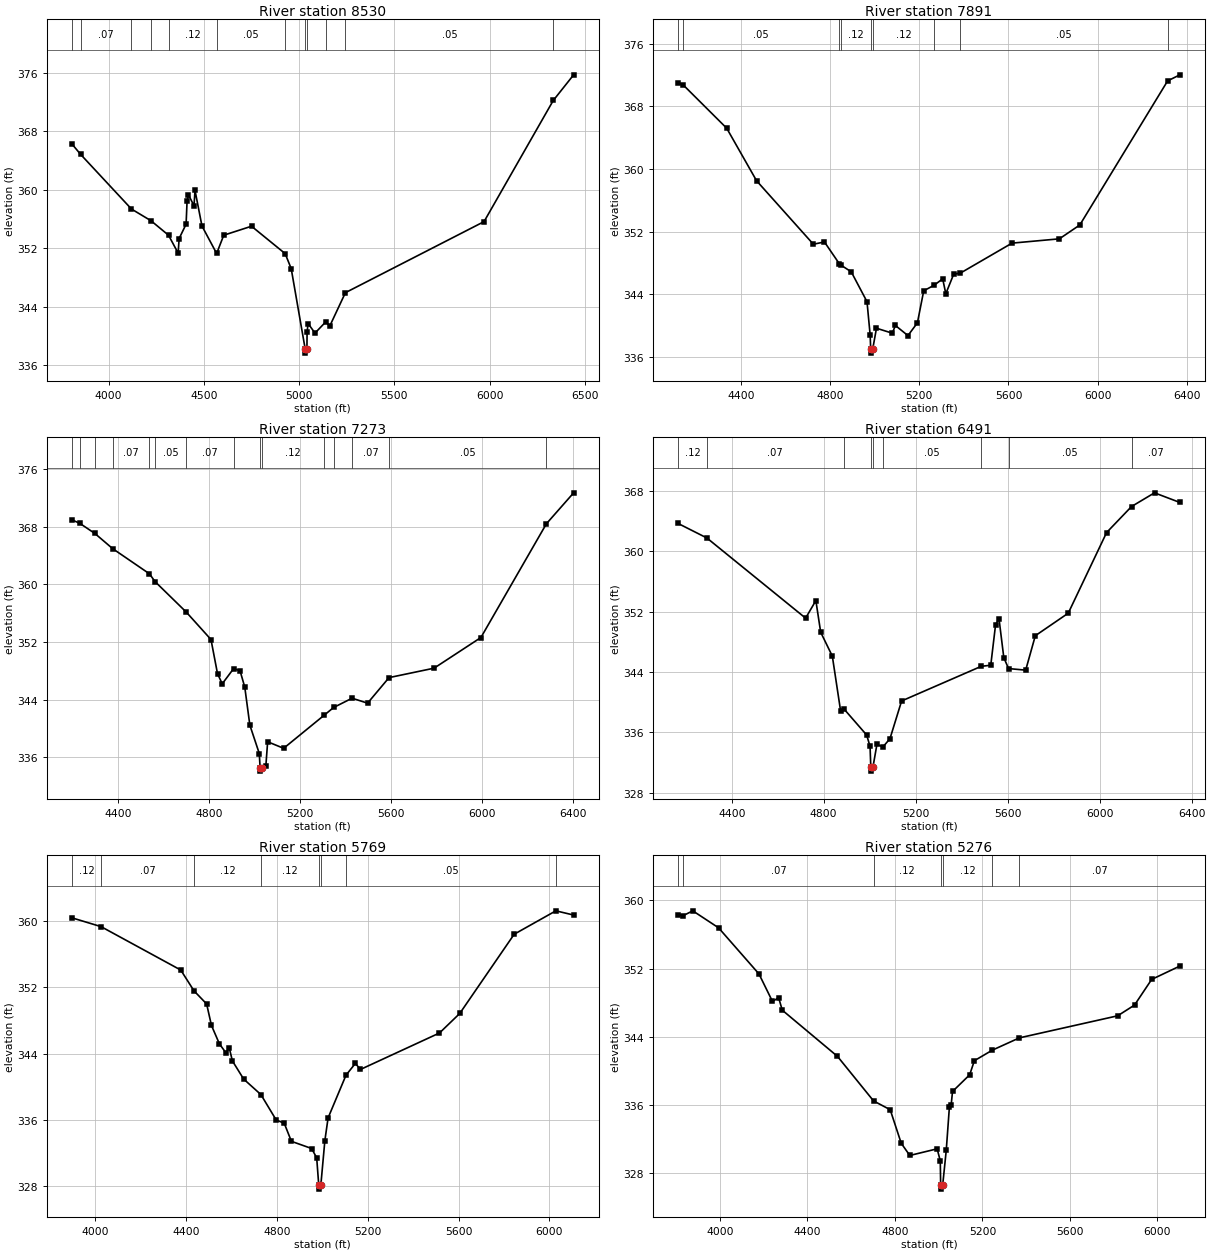
Type RM Length L Ch R = 1 ,8530    ,639,639,639
BEGIN DESCRIPTION:
XS6887
END DESCRIPTION:
XS GIS Cut Line= 3
      2475973.23     13767419.89      2475595.69     13765875.38
      2474832.02      13765163.2
#Sta/Elev= 30
  3806.9  366.32  3853.3  364.87  4120.4  357.39  4222.8  355.79  4314.8  353.81
  4365.3  351.36  4370.5  353.36    4407  355.32  4412.1  358.46  4419.3  359.35
  4448.6  357.83  4453.8  359.94  4490.3  355.07  4567.4  351.31  4604.6  353.81
  4750.4  355.04    4927  351.29  4958.7  349.24  5032.5  338.18    5033  337.68
  5041.2  338.18    5042  340.57  5047.3  341.73  5083.6  340.42  5141.2  341.99
  5160.5  341.35  5243.2  345.95  5970.9  355.67  6334.1  372.24  6441.1  375.75
#Mann= 12 ,-1 , 0
  3806.9     .05       0  3853.3     .07       0  4120.4     .05       0
  4222.8     .07       0  4314.8     .12       0  4567.4     .05       0
    4927     .12       0  5032.5     .05       0  5041.2     .12       0
  5141.2     .12       0  5243.2     .05       0  6334.1     .07       0
Bank Sta=5032.5,5041.2
XS Rating Curve= 0 ,0
Exp/Cntr=0.3,0.1

Type RM Length L Ch R = 1 ,7891    ,618,618,618
BEGIN DESCRIPTION:
XS6886
END DESCRIPTION:
XS GIS Cut Line= 2
      2476719.73     13766578.99       2475183.8     13764931.51
#Sta/Elev= 30
    4117  371.02  4138.5   370.8  4335.5  365.22  4469.8   358.5  4724.4   350.4
  4774.2  350.69  4840.9  347.91  4847.8  347.74  4894.4  346.88  4965.2  343.06
  4979.4  338.78  4981.7  336.99  4982.2  336.49  4990.7  336.99  5007.7  339.67
  5078.6  339.04  5092.7  340.02  5148.9  338.73  5191.4  340.36  5219.7  344.45
  5266.8  345.17  5304.8  345.98  5318.9  344.08  5354.1  346.57  5384.7  346.72
    5616  350.54  5828.5  351.09  5920.3  352.86  6314.5  371.27  6369.4  372.04
#Mann= 9 ,-1 , 0
    4117     .12       0  4138.5     .05       0  4840.9     .12       0
  4847.8     .12       0  4981.7     .05       0  4990.7     .12       0
  5266.8     .07       0  5384.7     .05       0  6314.5     .07       0
Bank Sta=4981.7,4990.7
XS Rating Curve= 0 ,0
Exp/Cntr=0.3,0.1

Type RM Length L Ch R = 1 ,7273    ,782,782,782
BEGIN DESCRIPTION:
XS6885
END DESCRIPTION:
XS GIS Cut Line= 2
      2477105.84      13766175.7      2475389.85     13764785.75
#Sta/Elev= 30
    4196  368.99  4231.5  368.49  4297.9  367.08  4375.8  364.98  4537.8  361.48
  4562.4   360.4  4699.9  356.16  4808.6  352.35  4837.3  347.61  4858.1   346.2
  4908.1  348.31  4936.5  348.01  4957.3  345.73  4979.6  340.46  5021.2  336.51
  5024.6  334.57  5025.1  334.07  5033.7  334.57    5050  334.78  5057.9  338.15
  5128.3  337.24  5305.6  341.81  5348.2  342.91  5429.5   344.2  5497.6  343.51
    5592  347.06  5790.1  348.37  5996.3  352.63  6284.6  368.44  6404.3  372.73
#Mann= 15 ,-1 , 0
    4196     .12       0  4231.5     .07       0  4297.9     .12       0
  4375.8     .07       0  4537.8     .12       0  4562.4     .05       0
  4699.9     .07       0  4908.1     .12       0  5024.6     .05       0
  5033.7     .12       0  5305.6     .07       0  5348.2     .05       0
  5429.5     .07       0    5592     .05       0  6284.6     .07       0
Bank Sta=5024.6,5033.7
XS Rating Curve= 0 ,0
Exp/Cntr=0.3,0.1

Type RM Length L Ch R = 1 ,6491    ,722,722,722
BEGIN DESCRIPTION:
XS6884
END DESCRIPTION:
XS GIS Cut Line= 2
      2477457.61     13765695.18      2475664.33     13764451.04
#Sta/Elev= 30
  4166.5  363.71    4292  361.78  4721.4  351.14    4766  353.47    4787  349.27
  4837.6   346.1  4873.4  338.87  4886.8  339.14  4986.9  335.63  5001.7  334.12
  5004.9  331.34  5005.4  330.84  5014.1  331.34  5031.5  334.38  5057.9  334.06
  5088.2  335.14  5138.9  340.15  5485.4  344.75  5526.6  344.89  5547.5  350.26
  5562.4  351.08  5583.3  345.91  5603.9  344.45  5678.5  344.24  5720.4  348.81
  5863.6   351.8  6030.4   362.5  6138.7  365.95  6238.7  367.77  6349.1  366.49
#Mann= 9 ,-1 , 0
  4166.5     .12       0    4292     .07       0  4886.8     .12       0
  5004.9     .05       0  5014.1     .12       0  5057.9     .05       0
  5485.4     .07       0  5603.9     .05       0  6138.7     .07       0
Bank Sta=5004.9,5014.1
XS Rating Curve= 0 ,0
Exp/Cntr=0.3,0.1

Type RM Length L Ch R = 1 ,5769    ,493,493,493
BEGIN DESCRIPTION:
XS6883
END DESCRIPTION:
XS GIS Cut Line= 3
      2477586.33     13765420.61      2477011.45     13764734.19
      2475835.98     13764142.16
#Sta/Elev= 30
  3895.8  360.42  4024.8  359.35  4376.1   354.1  4434.6  351.58  4490.1     350
  4511.4   347.4  4546.5  345.17  4575.1  344.09  4589.4  344.73  4603.7  343.11
  4653.2  340.92  4729.3  339.04  4796.6  335.97    4832  335.58  4863.6  333.39
  4952.8  332.52  4975.1  331.39  4984.1  328.11  4984.6  327.61  4993.4  328.11
  5011.1  333.48  5025.3  336.22  5104.3  341.39  5145.5  342.81  5167.9  342.08
  5516.2  346.49  5605.5  348.85  5845.3  358.43    6029  361.26  6107.3  360.75
#Mann= 8 ,-1 , 0
  3895.8     .12       0  4024.8     .07       0  4434.6     .12       0
  4729.3     .12       0  4984.1     .05       0  4993.4     .12       0
  5104.3     .05       0    6029     .07       0
Bank Sta=4984.1,4993.4
XS Rating Curve= 0 ,0
Exp/Cntr=0.3,0.1

Type RM Length L Ch R = 1 ,5276    ,949,949,949
BEGIN DESCRIPTION:
XS6882
END DESCRIPTION:
XS GIS Cut Line= 3
      2477672.13      13765326.2      2477157.32     13764288.01
      2476273.57     13763575.86
#Sta/Elev= 30
  3808.6   358.3  3833.4  358.22  3876.1  358.77  3993.8  356.78  4178.7  351.36
  4240.4  348.13  4268.4  348.58  4285.2  347.11  4537.4  341.69  4702.4  336.46
  4778.4  335.43  4828.8  331.49    4868  330.06  4992.9  330.84  5007.3  329.43
    5009  326.61  5009.5  326.11  5018.4  326.61  5034.6  330.67  5048.9  335.73
  5056.9  335.97  5063.3  337.57  5141.7  339.53    5163  341.18  5245.2  342.42
  5368.7  343.86    5818  346.45  5895.1  347.71  5973.4  350.72  6102.4  352.29
#Mann= 7 ,-1 , 0
  3808.6     .12       0  3833.4     .07       0  4702.4     .12       0
    5009     .05       0  5018.4     .12       0  5245.2     .05       0
  5368.7     .07       0
Bank Sta=5009,5018.4
XS Rating Curve= 0 ,0
Exp/Cntr=0.3,0.1