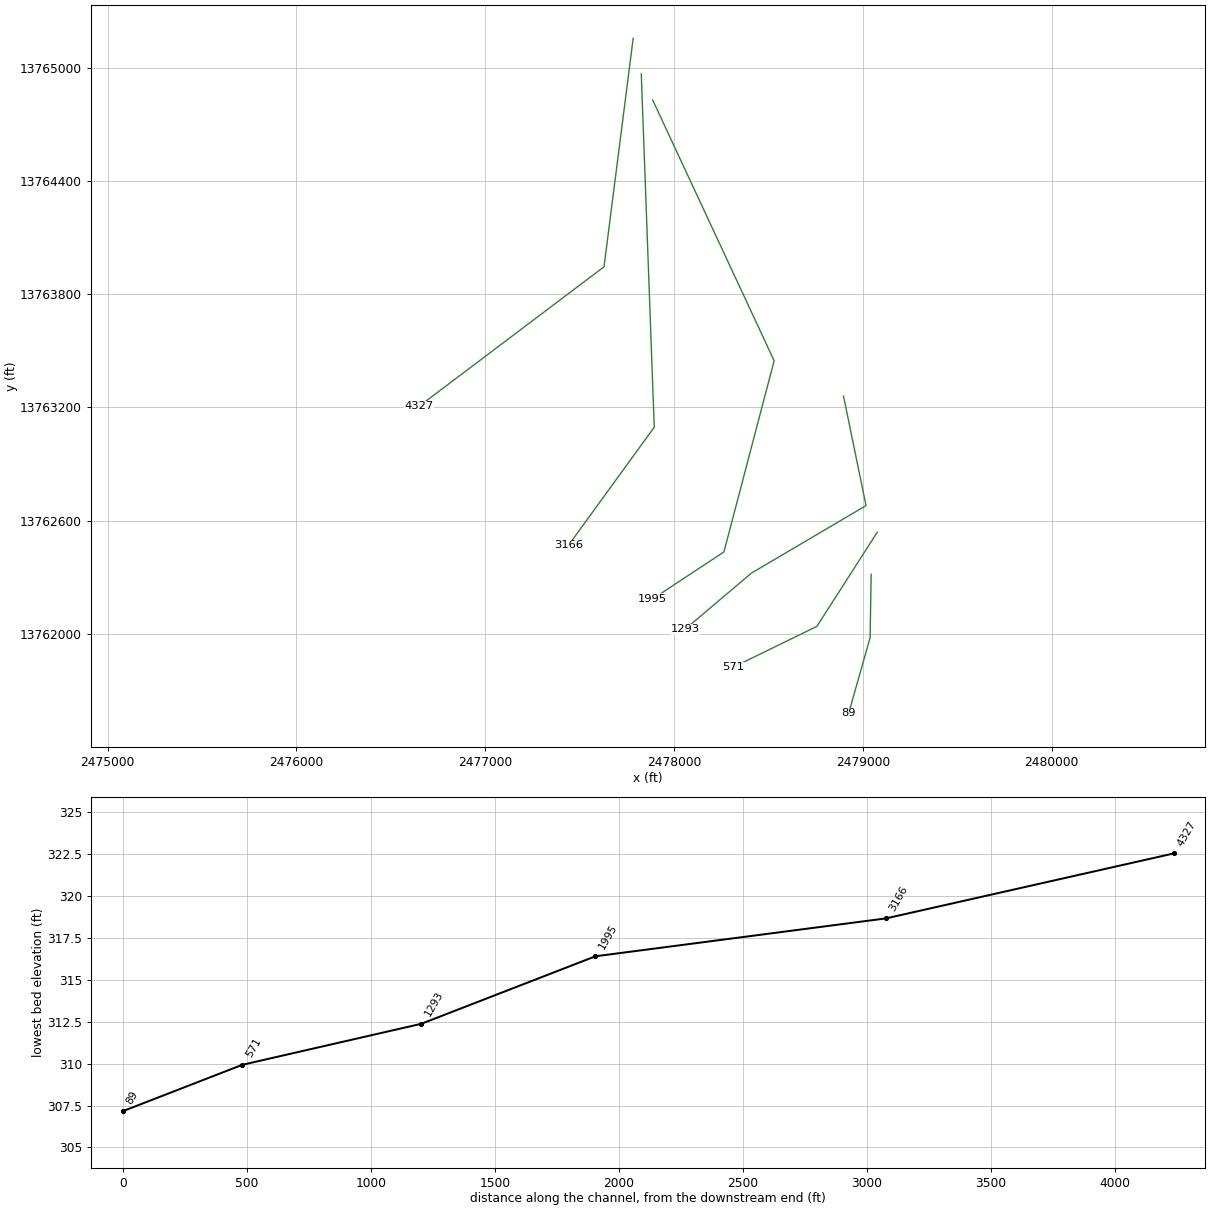
HEC-RAS study Stream0472.prj: Stream0472 Base Level Engineering

--- Stream0472.g01 (geometry) --- (continued)

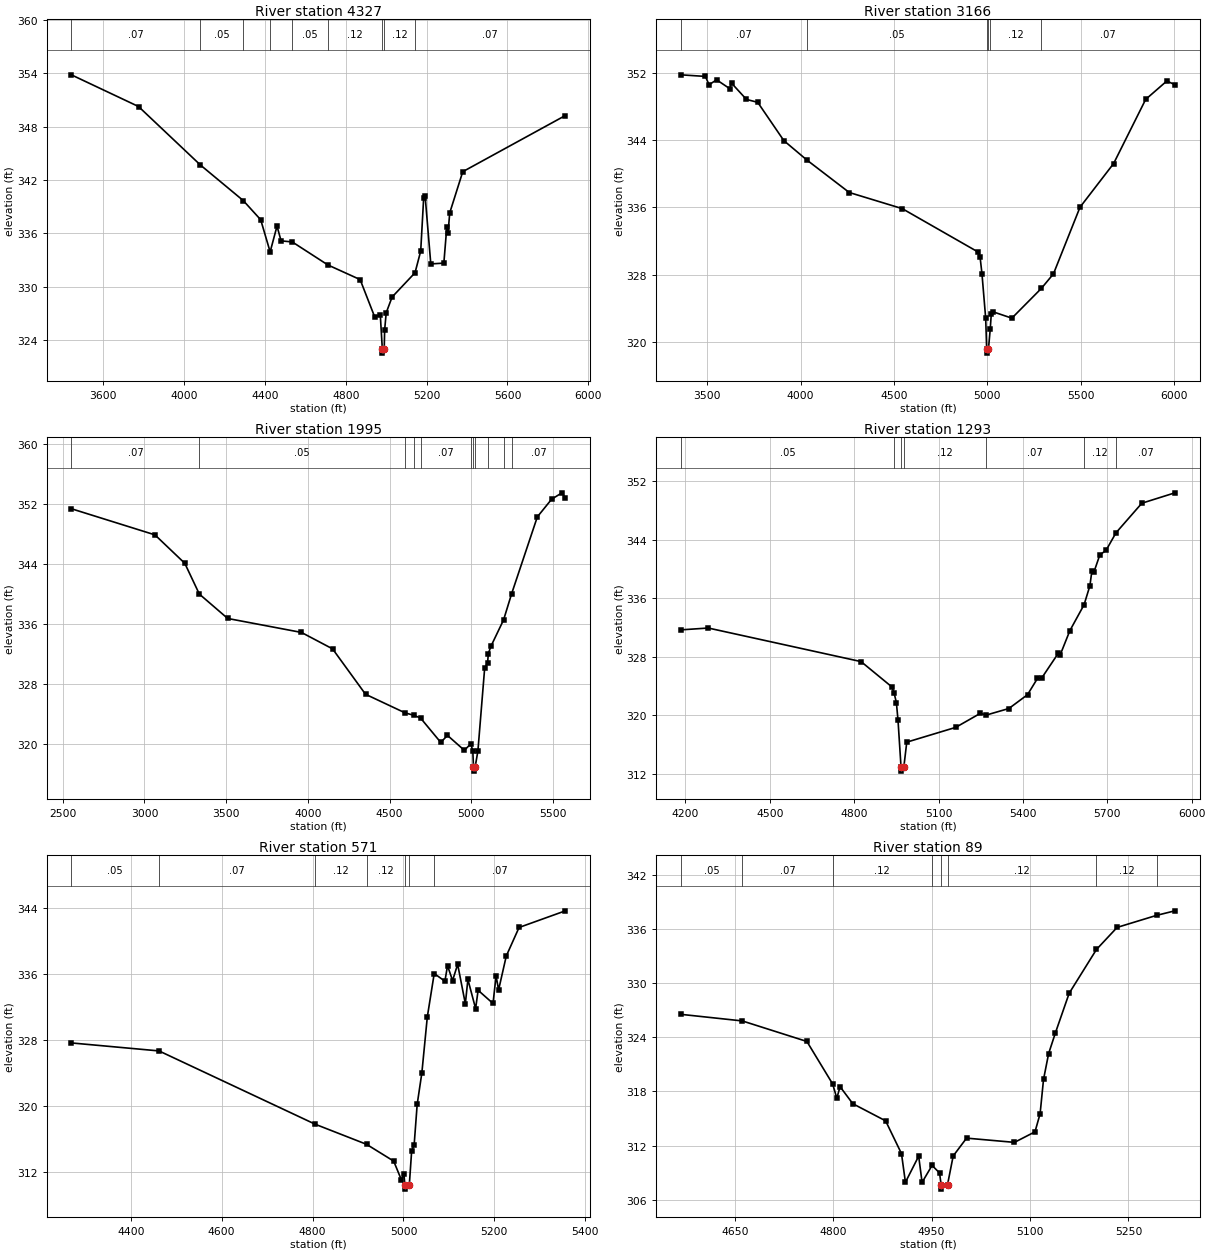
Type RM Length L Ch R = 1 ,4327    ,1161,1161,1161
BEGIN DESCRIPTION:
XS6881
END DESCRIPTION:
XS GIS Cut Line= 3
      2477783.68     13765154.58      2477629.24     13763944.79
      2476651.07     13763206.87
#Sta/Elev= 30
  3441.6  353.81  3773.9  350.25  4080.3  343.68  4292.1  339.69  4378.7  337.53
  4425.4  333.92  4459.4  336.82  4479.5  335.16  4534.9  335.04  4711.5  332.45
  4870.8  330.81  4942.1  326.66  4970.7  326.79  4980.5  323.05    4981  322.55
    4990  323.05  4992.2  325.18  4999.9  327.09    5029  328.85  5142.5  331.58
  5170.6  334.02  5185.1  339.94  5192.6  340.16  5220.5  332.57  5285.1  332.66
  5299.6  336.69  5305.9  336.06  5314.2   338.3  5378.7  342.93  5886.5  349.24
#Mann= 9 ,-1 , 0
  3441.6     .07       0  4080.3     .05       0  4292.1     .07       0
  4425.4     .12       0  4534.9     .05       0  4711.5     .12       0
  4980.5     .05       0    4990     .12       0  5142.5     .07       0
Bank Sta=4980.5,4990
XS Rating Curve= 0 ,0
Exp/Cntr=0.3,0.1

Type RM Length L Ch R = 1 ,3166    ,1171,1171,1171
BEGIN DESCRIPTION:
XS6880
END DESCRIPTION:
XS GIS Cut Line= 3
      2477826.59     13764965.81      2477895.24     13763095.33
      2477440.88     13762469.52
#Sta/Elev= 30
  3358.9  351.78  3489.8  351.59  3509.8   350.6  3549.8  351.19  3619.9  350.14
  3629.9  350.79  3709.9  348.85    3770  348.51  3910.1  343.95  4034.1  341.63
  4260.3  337.78    4544  335.86  4950.8  330.69  4960.8  330.08  4970.8  328.12
  4990.8   322.8    4996  319.17  4996.5  318.67  5005.6  319.17    5015   321.5
  5020.8  323.36  5030.8  323.58  5130.9  322.83  5288.4  326.36  5353.6   328.1
  5495.8  336.03  5675.9  341.23  5847.5  348.86  5960.4  351.04    6004  350.61
#Mann= 6 ,-1 , 0
  3358.9     .07       0  4034.1     .05       0    4996     .05       0
  5005.6     .05       0    5015     .12       0  5288.4     .07       0
Bank Sta=4996,5005.6
XS Rating Curve= 0 ,0
Exp/Cntr=0.3,0.1

Type RM Length L Ch R = 1 ,1995    ,702,702,702
BEGIN DESCRIPTION:
XS6879
END DESCRIPTION:
XS GIS Cut Line= 4
      2477886.64      13764828.6      2478530.19     13763447.13
      2478264.19     13762434.64      2477886.68     13762185.82
#Sta/Elev= 30
  2552.6  351.37    3064  347.89  3246.7   344.1  3335.7     340  3509.3  336.75
  3960.4  334.89    4151   332.7  4352.8  326.65    4595  324.17  4648.4  323.85
  4689.6  323.48  4812.9  320.24  4854.3  321.17  4957.7  319.18  4997.2  320.06
  5009.4  319.04  5013.4  316.91  5013.9  316.41  5023.1  316.91  5040.4  319.09
  5081.7  330.11  5099.8  330.83  5104.1  332.07  5120.7  333.07  5197.7  336.57
  5246.4  340.02  5404.2  350.29  5491.6  352.64  5554.7  353.49  5575.6   352.8
#Mann= 11 ,-1 , 0
  2552.6     .07       0  3335.7     .05       0    4595     .07       0
  4648.4     .05       0  4689.6     .07       0  4997.2     .12       0
  5013.4     .05       0  5023.1     .12       0  5099.8     .07       0
  5197.7     .12       0  5246.4     .07       0
Bank Sta=5013.4,5023.1
XS Rating Curve= 0 ,0
Exp/Cntr=0.3,0.1

Type RM Length L Ch R = 1 ,1293    ,722,722,722
BEGIN DESCRIPTION:
E21061
END DESCRIPTION:
XS GIS Cut Line= 4
      2478897.47     13763260.27      2479016.74     13762680.21
      2478409.55      13762322.4      2478058.59     13762025.44
#Sta/Elev= 30
  4183.8  331.69  4281.1  331.94  4824.4  327.35  4934.3  323.88  4941.6   323.1
    4950  321.75  4955.8  319.33  4966.6  312.88  4967.1  312.38  4976.3  312.88
  4986.9  316.34    5161  318.36  5248.6  320.28  5269.3  320.04  5350.1  320.94
  5416.4  322.83  5451.6  325.05  5467.2  325.13  5525.2  328.46  5531.8   328.2
  5566.9  331.58  5617.5  335.13  5638.3  337.74  5644.9  339.67  5652.6   339.6
  5673.5  341.94  5695.5  342.55    5731  344.96  5822.9     349  5940.5  350.42
#Mann= 7 ,-1 , 0
  4183.8     .05       0  4941.6     .12       0  4966.6     .05       0
  4976.3     .12       0  5269.3     .07       0  5617.5     .12       0
    5731     .07       0
Bank Sta=4966.6,4976.3
XS Rating Curve= 0 ,0
Exp/Cntr=0.3,0.1

Type RM Length L Ch R = 1 ,571     ,482,482,482
BEGIN DESCRIPTION:
E21060
END DESCRIPTION:
XS GIS Cut Line= 3
      2479076.35     13762539.22      2478756.51      13762040.5
      2478311.95     13761823.64
#Sta/Elev= 30
  4269.2  327.67  4462.1   326.7    4806   317.8  4918.7  315.37  4978.5  313.33
  4995.5  311.05    5001  311.79  5003.1  310.43  5003.6  309.93  5012.9  310.43
    5018  314.53  5023.6  315.34  5030.2  320.21  5040.5  324.03  5052.5  330.82
  5067.7  336.09  5091.2  335.16    5097  337.04  5108.1  335.24  5119.3  337.21
  5136.2  332.42  5141.8  335.38  5158.8  331.83  5164.3  334.06  5197.1  332.46
  5203.8   335.8  5209.4  334.11  5226.3  338.22  5254.4  341.68  5356.3   343.7
#Mann= 7 ,-1 , 0
  4269.2     .05       0  4462.1     .07       0    4806     .12       0
  4918.7     .12       0  5003.1     .05       0  5012.9     .12       0
  5067.7     .07       0
Bank Sta=5003.1,5012.9
XS Rating Curve= 0 ,0
Exp/Cntr=0.3,0.1

Type RM Length L Ch R = 1 ,89      ,0,0,0
BEGIN DESCRIPTION:
E21059
END DESCRIPTION:
XS GIS Cut Line= 3
      2479043.84     13762316.97      2479038.42     13761980.86
      2478924.62     13761579.85
#Sta/Elev= 30
  4567.9  326.56  4661.4  325.83  4759.9  323.55  4799.2  318.83  4805.5  317.25
  4810.5  318.53  4829.9  316.64  4879.9  314.74  4904.1   311.1  4910.1  307.92
  4930.3  310.82  4935.5  307.91  4950.7  309.79  4962.1  308.96  4964.5  307.66
    4965  307.16  4974.3  307.66  4982.9  310.84  5003.3  312.82  5076.3  312.35
  5107.6  313.52  5115.4  315.53  5120.6  319.33  5128.4  322.21  5138.8  324.52
  5159.7   328.9  5201.3  333.76  5232.8  336.21  5293.1  337.55  5320.9  338.05
#Mann= 8 ,-1 , 0
  4567.9     .05       0  4661.4     .07       0  4799.2     .12       0
  4950.7     .12       0  4964.5     .05       0  4974.3     .12       0
  5201.3     .12       0  5293.1     .07       0
Bank Sta=4964.5,4974.3
XS Rating Curve= 0 ,0
Exp/Cntr=0.3,0.1

Chan Stop Cuts=-1
Use User Specified Reach Order=0
Composite Channel Slope=5