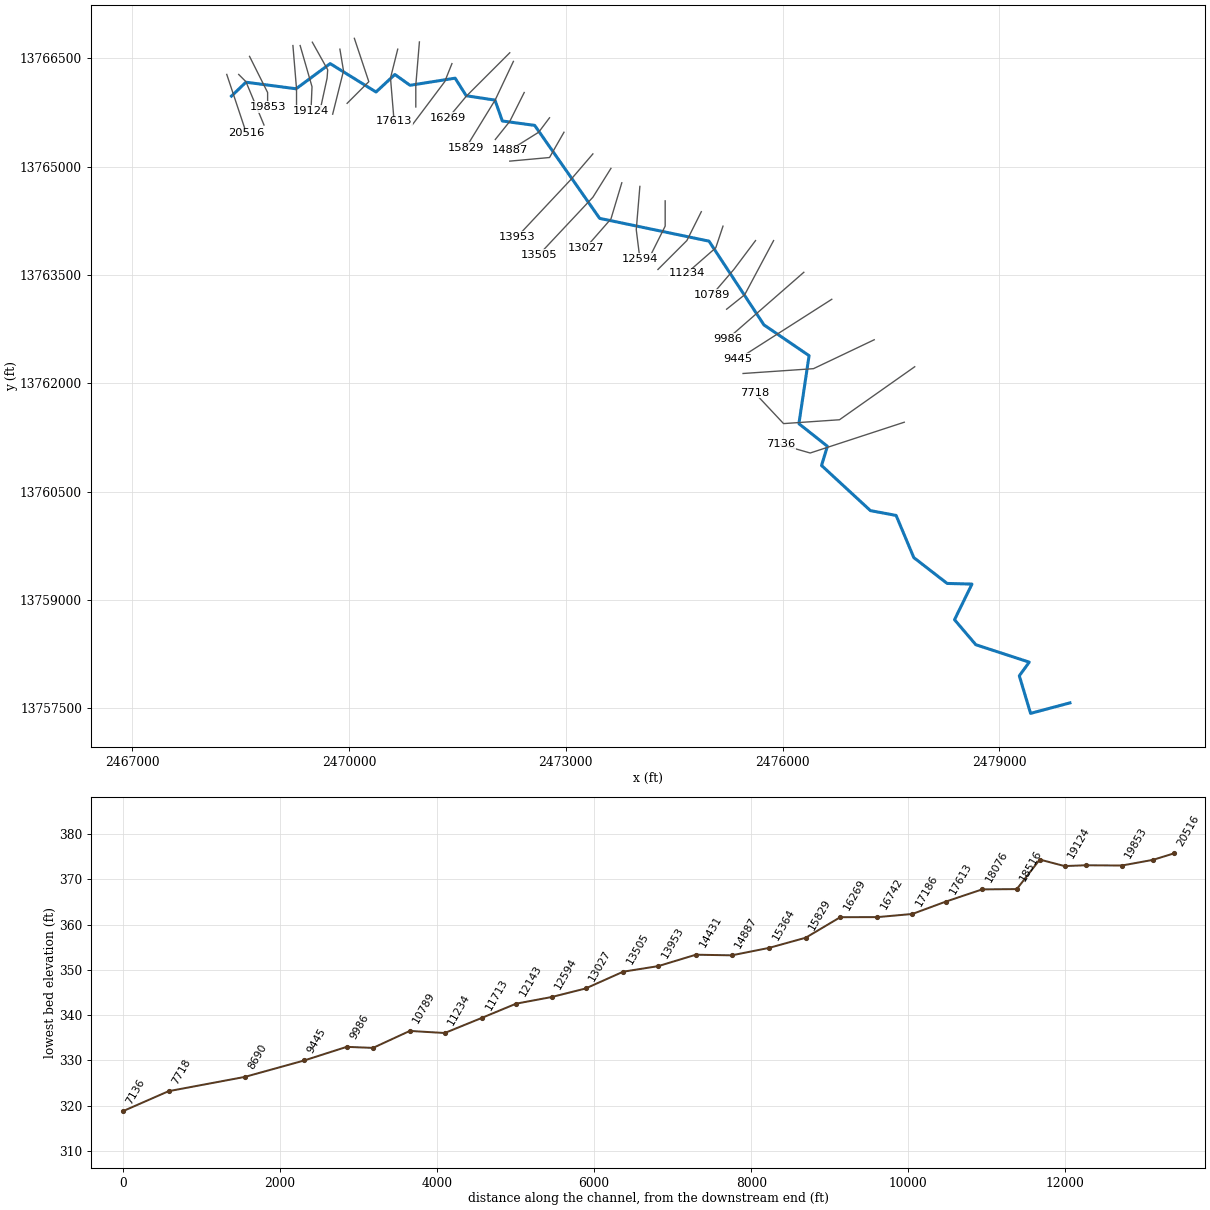
--- Stream0474.prj (project) ---

Proj Title=Stream0474 Base Level Engineering
Current Plan=p01
Default Exp/Contr=0.3,0.1
English Units
Geom File=g01
Flow File=f01
Plan File=p01
BEGIN DESCRIPTION:
Stream0474
END DESCRIPTION:

--- Stream0474.p01 (plan) ---

Plan Title=Multiple Run
Short Identifier=Multiple
Geom File=g01
Flow File=f01
Subcritical Flow
K Sum by GR= 0
Std Step Tol= 0.01
Critical Tol= 0.01
Num of Std Step Trials= 20
Max Error Tol= 0.3
Flow Tol Ratio= 0.001
Split Flow NTrial= 30
Split Flow Tol= 0.02
Split Flow Ratio= 0.02
Log Output Level= 0
Friction Slope Method= 1
Unsteady Friction Slope Method= 2
Unsteady Bridges Friction Slope Method= 1
Parabolic Critical Depth
Global Vel Dist=  1 , 1 , 1
Global Log Level= 0
CheckData=True
Encroach Param= -1, 0, 0, 0
BEGIN DESCRIPTION:
Multiple Run
END DESCRIPTION:

--- Stream0474.f01 (steady flow) ---

Flow Title=Multiple
Number of Profiles=7
Profile Names=10-year,25-year,50-year,1pct_min,100-year,1pct_plu,500-year
River Rch & RM= Stream0474,Reach-1,20516
     522     817    1076     686    1368    2730    2189
River Rch & RM= Stream0474,Reach-1,15364
     914    1483    1999    1302    2597    5183    4346
Boundary for River Rch & Prof#=Stream0474,Reach-1,1
Up Type=0
Dn Type=3
Dn Slope=0.005
Boundary for River Rch & Prof#=Stream0474,Reach-1,2
Up Type=0
Dn Type=3
Dn Slope=0.005
Boundary for River Rch & Prof#=Stream0474,Reach-1,3
Up Type=0
Dn Type=3
Dn Slope=0.005
Boundary for River Rch & Prof#=Stream0474,Reach-1,4
Up Type=0
Dn Type=3
Dn Slope=0.005
Boundary for River Rch & Prof#=Stream0474,Reach-1,5
Up Type=0
Dn Type=3
Dn Slope=0.005
Boundary for River Rch & Prof#=Stream0474,Reach-1,6
Up Type=0
Dn Type=3
Dn Slope=0.005
Boundary for River Rch & Prof#=Stream0474,Reach-1,7
Up Type=0
Dn Type=3
Dn Slope=0.005

--- Stream0474.g01 (geometry) ---

Geom Title=Existing Conditions

River Reach=Stream0474,Reach-1
Reach XY= 30
      2468375.00     13765975.00      2468574.78     13766167.54
      2469268.97     13766076.62      2469740.34     13766425.04
      2470374.79     13766031.98      2470635.64     13766274.45
      2470844.99     13766124.94      2471469.17     13766223.47
      2471622.70     13765980.11      2472020.07     13765919.96
      2472122.55     13765630.47      2472569.62     13765569.82
      2473468.48     13764282.68      2474981.21     13763967.24
      2475741.44     13762807.86      2476365.78     13762381.93
      2476225.36     13761440.27      2476619.20     13761127.29
      2476538.41     13760861.67      2477214.98     13760236.23
      2477569.97     13760169.92      2477815.17     13759585.52
      2478276.27     13759228.47      2478619.42     13759219.43
      2478378.02     13758726.39      2478672.69     13758380.09
      2479411.74     13758138.69      2479274.38     13757949.92
      2479430.29     13757429.58      2479975.00     13757575.00

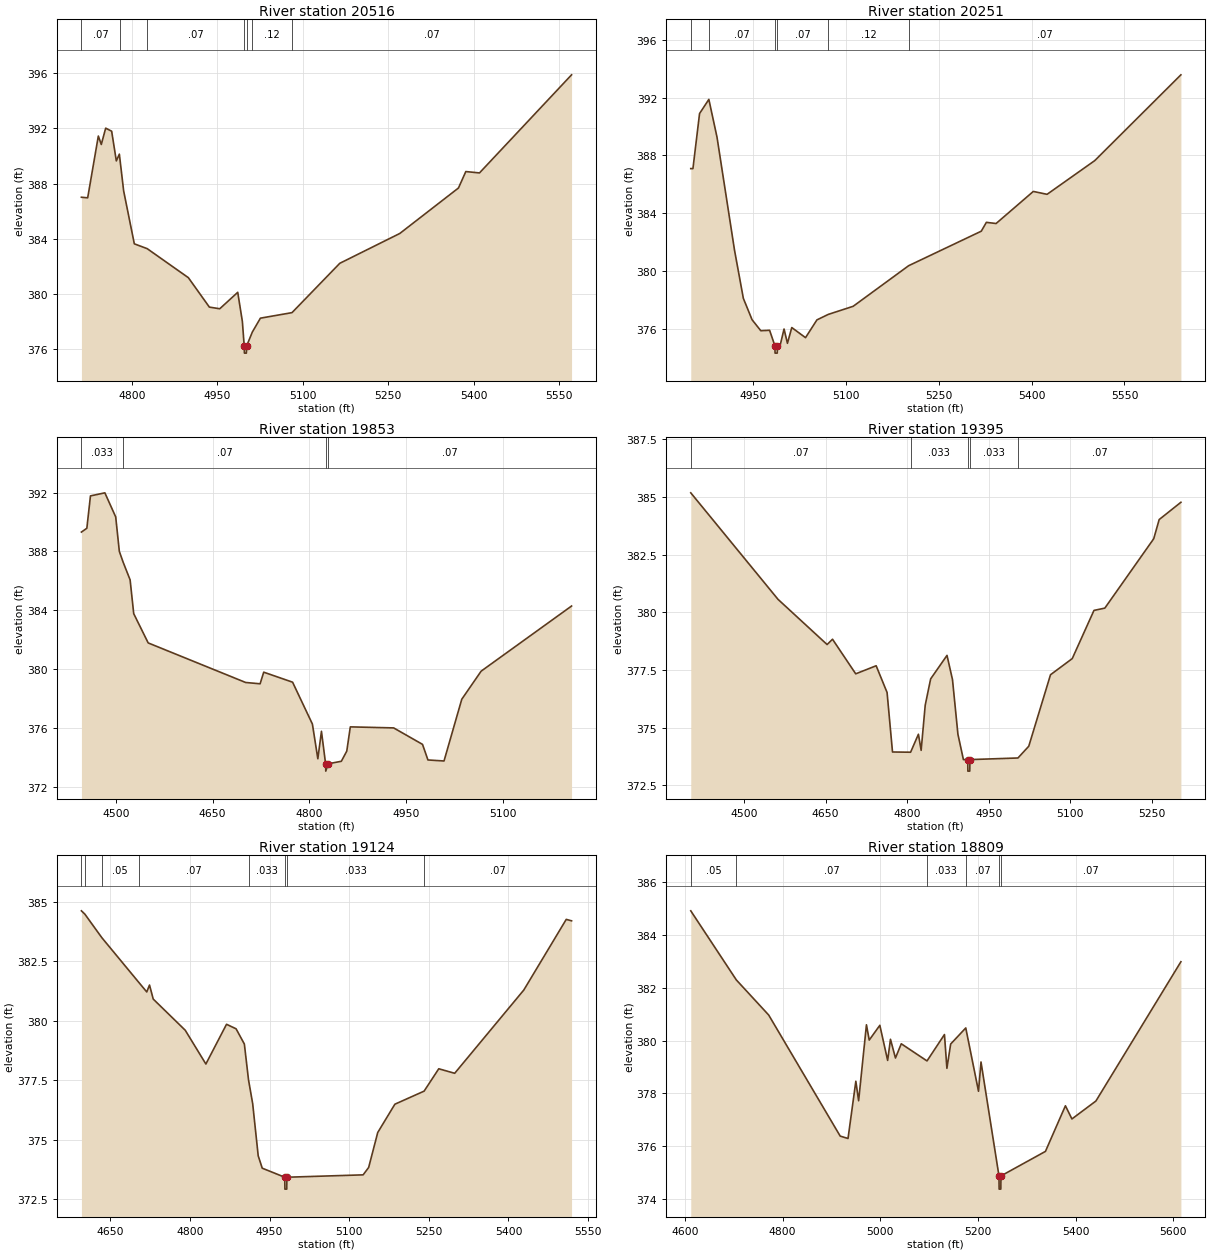
Type RM Length L Ch R = 1,20516,265,265,265
BEGIN DESCRIPTION:
XS6896
END DESCRIPTION:
XS GIS Cut Line= 2
      2468309.71     13766275.41      2468581.89     13765458.87
#Sta/Elev= 30
  4711.5  387.01  4722.5  386.97  4741.2  391.44  4746.4  390.83  4754.1  392.01
  4764.6  391.79  4772.8  389.64  4778.1  390.13  4779.7  389.57  4785.7  387.46
  4804.4  383.64  4827.0  383.29  4899.3  381.19  4936.2  379.06  4954.4  378.94
  4986.0  380.13  4994.1  378.03  4997.4  376.23  4997.7  375.73  5001.2  375.73
  5001.4  376.23  5011.7  377.26  5025.8  378.26  5081.3  378.66  5165.2  382.23
  5270.6  384.39  5373.6  387.68  5386.5  388.87  5410.5  388.77  5572.2  395.87
#Mann=7,-1,0
  4711.5    0.07       0  4779.7    0.05       0  4827.0    0.07       0
  4997.4    0.05       0  5001.4    0.07       0  5011.7    0.12       0
  5081.3    0.07       0
Bank Sta=4997.4,5001.4
Exp/Cntr=0.3,0.1

Type RM Length L Ch R = 1,20251,398,398,398
BEGIN DESCRIPTION:
Stream0474 45.0
END DESCRIPTION:
XS GIS Cut Line= 3
      2468474.99     13766275.01      2468575.00     13766175.00
      2468824.99     13765575.03
#Sta/Elev= 30
  4849.7  387.08  4853.2  387.08  4863.9  390.89  4878.9  391.87  4892.1  389.25
  4920.4  381.42  4934.6  378.10  4948.7  376.62  4962.8  375.86  4977.0  375.89
  4985.6  374.81  4985.8  374.31  4989.3  374.31  4989.6  374.81  4993.8  374.81
  5000.3  375.98  5005.8  374.99  5012.8  376.08  5035.0  375.38  5053.4  376.61
  5071.7  376.99  5111.9  377.55  5201.5  380.36  5318.8  382.75  5327.0  383.36
  5342.7  383.28  5402.8  385.50  5425.0  385.30  5501.9  387.63  5641.1  393.57
#Mann=6,-1,0
  4849.7   0.033       0  4878.9    0.07       0  4985.6    0.05       0
  4989.6    0.07       0  5071.7    0.12       0  5201.5    0.07       0
Bank Sta=4985.6,4989.6
Exp/Cntr=0.3,0.1

Type RM Length L Ch R = 1,19853,458,458,458
BEGIN DESCRIPTION:
Stream0474 44.0
END DESCRIPTION:
XS GIS Cut Line= 3
      2468625.01     13766524.98      2468875.00     13766025.00
      2468875.00     13765825.00
#Sta/Elev= 30
  4446.9  389.31  4455.3  389.57  4460.9  391.77  4483.2  391.98  4500.0  390.34
  4505.6  388.00  4511.6  387.25  4522.3  386.06  4527.9  383.76  4550.3  381.77
  4701.2  379.08  4723.6  378.99  4729.2  379.78  4773.9  379.10  4804.6  376.25
  4813.0  373.89  4818.6  375.76  4825.0  373.55  4825.3  373.05  4829.0  373.55
  4849.4  373.72  4857.8  374.41  4863.3  376.06  4930.4  375.99  4975.1  374.87
  4983.5  373.81  5008.4  373.74  5035.9  377.94  5065.9  379.85  5205.9  384.28
#Mann=4,-1,0
  4446.9   0.033       0  4511.6    0.07       0  4825.0    0.05       0
  4829.0    0.07       0
Bank Sta=4825,4829
Exp/Cntr=0.3,0.1

Type RM Length L Ch R = 1,19395,271,271,271
BEGIN DESCRIPTION:
Stream0474 43.0
END DESCRIPTION:
XS GIS Cut Line= 3
      2469225.00     13766675.02      2469275.00     13766075.00
      2469275.00     13765775.00
#Sta/Elev= 30
  4401.7  385.18  4562.3  380.56  4652.6  378.60  4662.6  378.83  4705.3  377.33
  4742.9  377.68  4763.0  376.52  4773.0  373.94  4806.3  373.93  4820.7  374.71
  4825.7  374.01  4833.2  375.97  4843.2  377.11  4873.3  378.13  4883.4  377.08
  4893.4  374.71  4903.5  373.61  4911.5  373.61  4911.7  373.11  4915.2  373.11
  4915.5  373.61  5003.9  373.68  5023.8  374.19  5063.8  377.29  5103.8  377.99
  5143.8  380.08  5163.8  380.18  5253.8  383.19  5263.8  384.02  5303.8  384.77
#Mann=5,-1,0
  4401.7    0.07       0  4806.3   0.033       0  4911.5   0.033       0
  4915.5   0.033       0  5003.9    0.07       0
Bank Sta=4911.5,4915.5
Exp/Cntr=0.3,0.1

Type RM Length L Ch R = 1,19124,315,315,315
BEGIN DESCRIPTION:
Stream0474 42.0
END DESCRIPTION:
XS GIS Cut Line= 3
      2469324.99     13766675.05      2469489.23     13766105.18
      2469475.00     13765775.05
#Sta/Elev= 30
  4595.4  384.63  4601.9  384.49  4633.9  383.50  4703.2  381.63  4718.5  381.22
  4723.7  381.51  4730.7  380.92  4791.0  379.61  4829.9  378.19  4868.8  379.86
  4886.8  379.67  4902.4  379.03  4910.2  377.53  4918.1  376.52  4928.5  374.33
  4936.1  373.81  4978.5  373.43  4978.8  372.93  4982.3  372.93  4982.5  373.43
  5126.2  373.53  5136.6  373.84  5153.7  375.31  5186.0  376.50  5241.1  377.05
  5268.7  377.99  5298.7  377.80  5428.9  381.30  5508.9  384.27  5518.9  384.21
#Mann=8,-1,0
  4595.4    0.05       0  4601.9    0.07       0  4633.9    0.05       0
  4703.2    0.07       0  4910.2   0.033       0  4978.5   0.033       0
  4982.5   0.033       0  5241.1    0.07       0
Bank Sta=4978.5,4982.5
Exp/Cntr=0.3,0.1

Type RM Length L Ch R = 1,18809,293,293,293
BEGIN DESCRIPTION:
E21080
END DESCRIPTION:
XS GIS Cut Line= 4
      2469493.57     13766721.49      2469706.24     13766339.55
      2469697.56     13766222.37      2469602.07     13765784.01
#Sta/Elev= 30
  4612.0  384.92  4705.3  382.30  4771.5  380.97  4917.9  376.38  4933.9  376.29
  4949.9  378.46  4955.6  377.72  4971.6  380.60  4977.3  380.02  4999.0  380.58
  5015.0  379.25  5020.8  380.05  5031.0  379.34  5042.9  379.88  5095.6  379.23
  5131.3  380.23  5136.3  378.95  5144.0  379.87  5174.9  380.48  5201.0  378.08
  5206.1  379.19  5242.9  374.87  5243.2  374.37  5246.7  374.37  5246.9  374.87
  5338.0  375.80  5378.9  377.53  5392.2  377.03  5441.3  377.71  5615.3  382.99
#Mann=6,-1,0
  4612.0    0.05       0  4705.3    0.07       0  5095.6   0.033       0
  5174.9    0.07       0  5242.9    0.05       0  5246.9    0.07       0
Bank Sta=5242.9,5246.9
Exp/Cntr=0.3,0.1

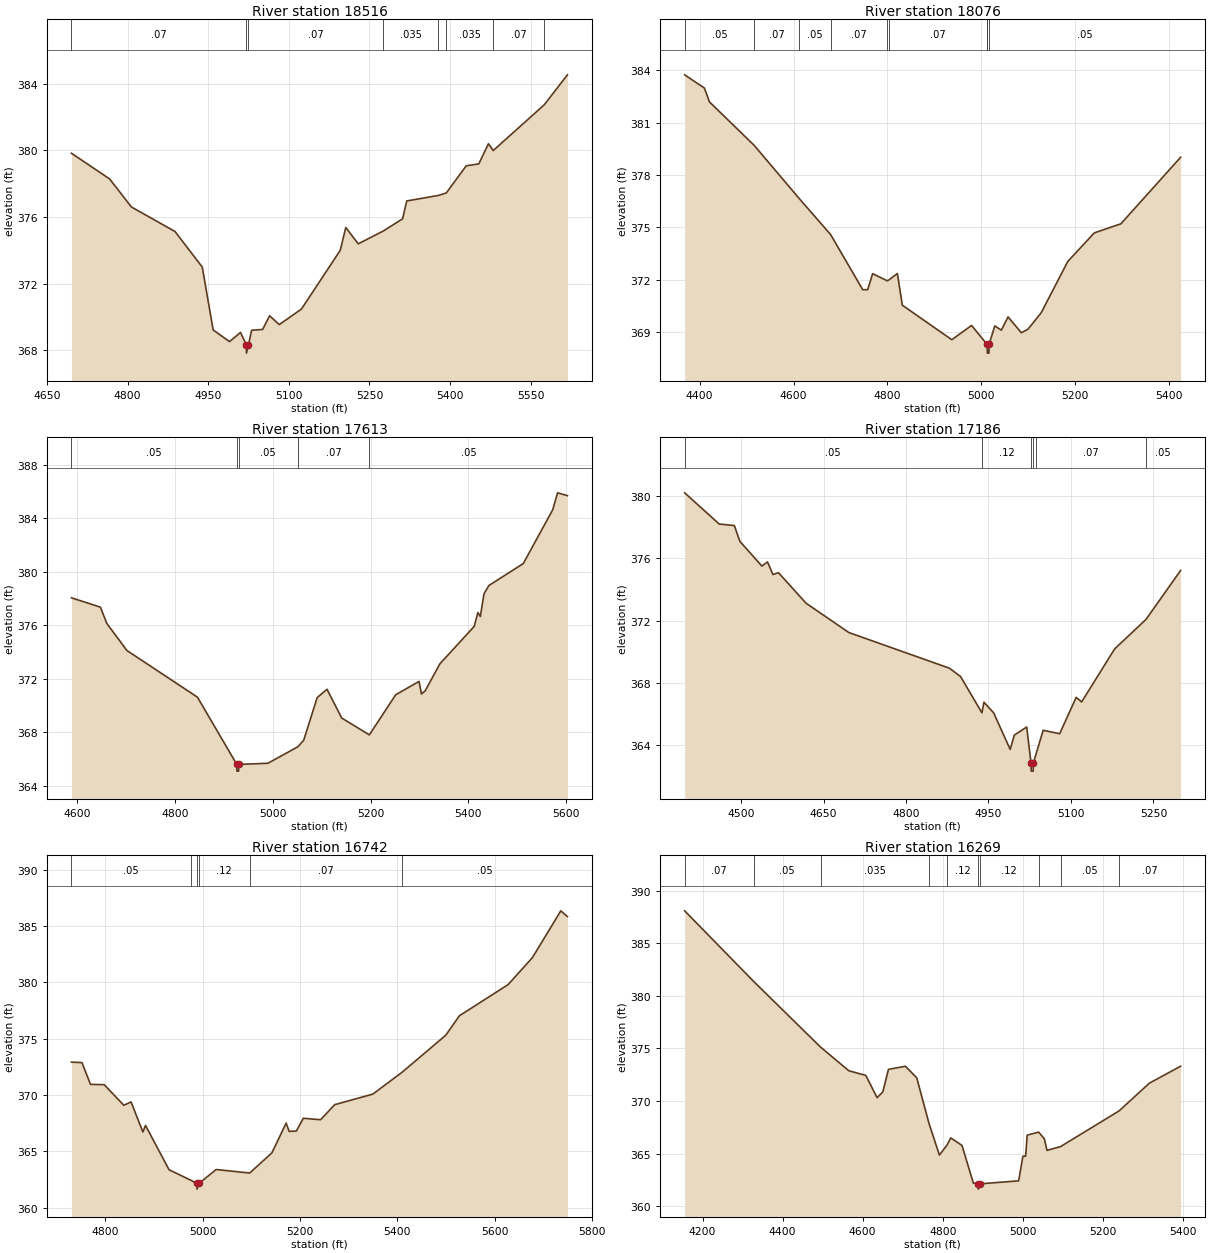
Type RM Length L Ch R = 1,18516,440,440,440
BEGIN DESCRIPTION:
Stream0474 41.0
END DESCRIPTION:
XS GIS Cut Line= 3
      2469875.00     13766625.01      2469925.00     13766325.00
      2469775.00     13765725.02
#Sta/Elev= 30
  4695.7  379.82  4766.7  378.28  4807.2  376.60  4888.3  375.13  4939.0  373.00
  4959.3  369.23  4989.7  368.53  5010.2  369.08  5021.0  368.34  5021.3  367.84
  5025.0  368.34  5030.8  369.21  5051.4  369.26  5064.3  370.08  5082.3  369.55
  5123.5  370.48  5195.7  374.00  5206.0  375.37  5229.2  374.39  5275.8  375.16
  5311.7  375.89  5319.4  376.96  5378.0  377.29  5393.0  377.44  5430.2  379.07
  5453.4  379.18  5471.4  380.39  5480.2  379.98  5575.1  382.72  5618.3  384.52
#Mann=8,-1,0
  4695.7    0.07       0  5021.0    0.05       0  5025.0    0.07       0
  5275.8   0.035       0  5378.0    0.05       0  5393.0   0.035       0
  5480.2    0.07       0  5575.1    0.05       0
Bank Sta=5021,5025
Exp/Cntr=0.3,0.1

Type RM Length L Ch R = 1,18076,463,463,463
BEGIN DESCRIPTION:
Stream0474 40.0
END DESCRIPTION:
XS GIS Cut Line= 3
      2470075.01     13766774.97      2470275.00     13766175.00
      2469974.99     13765874.99
#Sta/Elev= 30
  4368.1  383.75  4410.2  382.99  4420.8  382.20  4516.3  379.70  4611.6  376.67
  4679.2  374.58  4747.5  371.42  4758.1  371.42  4768.6  372.34  4799.8  371.93
  4802.7  371.97  4821.3  372.35  4831.9  370.53  4937.3  368.55  4979.4  369.37
  5011.3  368.32  5012.7  368.28  5012.9  367.78  5016.4  367.78  5016.7  368.28
  5028.8  369.34  5042.9  369.10  5057.1  369.86  5085.4  368.95  5099.5  369.15
  5127.8  370.10  5184.4  373.04  5240.9  374.68  5297.5  375.20  5424.8  379.02
#Mann=9,-1,0
  4368.1    0.05       0  4516.3    0.07       0  4611.6    0.05       0
  4679.2    0.07       0  4799.8   0.035       0  4802.7    0.07       0
  5011.3    0.05       0  5012.7    0.05       0  5016.7    0.05       0
Bank Sta=5012.7,5016.7
Exp/Cntr=0.3,0.1

Type RM Length L Ch R = 1,17613,427,427,427
BEGIN DESCRIPTION:
Stream0474 39.0
END DESCRIPTION:
XS GIS Cut Line= 3
      2470675.00     13766625.01      2470575.00     13766225.00
      2470625.00     13765625.00
#Sta/Elev= 30
  4588.2  378.04  4647.5  377.34  4660.4  376.13  4701.6  374.10  4845.9  370.61
  4926.4  365.58  4926.6  365.08  4930.1  365.08  4930.4  365.58  4990.2  365.67
  5051.2  366.90  5063.2  367.39  5090.8  370.58  5110.9  371.20  5141.0  369.05
  5197.5  367.79  5251.4  370.79  5299.1  371.79  5304.1  370.85  5311.6  371.08
  5341.7  373.10  5411.9  375.90  5419.5  376.94  5424.5  376.64  5432.0  378.34
  5442.0  378.96  5512.3  380.60  5572.5  384.62  5582.5  385.89  5602.6  385.68
#Mann=5,-1,0
  4588.2    0.05       0  4926.4    0.05       0  4930.4    0.05       0
  5051.2    0.07       0  5197.5    0.05       0
Bank Sta=4926.4,4930.4
Exp/Cntr=0.3,0.1

Type RM Length L Ch R = 1,17186,444,444,444
BEGIN DESCRIPTION:
Stream0474 38.0
END DESCRIPTION:
XS GIS Cut Line= 3
      2470975.00     13766725.04      2470925.00     13766125.00
      2470925.00     13765825.02
#Sta/Elev= 30
  4397.4  380.19  4460.2  378.19  4487.8  378.09  4497.8  377.08  4537.9  375.49
  4548.0  375.76  4558.0  374.95  4568.0  375.07  4618.2  373.11  4696.0  371.23
  4879.1  368.94  4899.2  368.41  4938.1  366.08  4941.8  366.76  4959.4  366.08
  4989.5  363.73  4997.0  364.65  5019.5  365.17  5027.5  362.84  5027.8  362.34
  5031.3  362.34  5031.5  362.84  5036.9  363.48  5049.5  364.96  5079.5  364.74
  5109.5  367.07  5119.5  366.78  5179.5  370.18  5236.5  372.07  5299.5  375.21
#Mann=6,-1,0
  4397.4    0.05       0  4938.1    0.12       0  5027.5    0.05       0
  5031.5    0.12       0  5036.9    0.07       0  5236.5    0.05       0
Bank Sta=5027.5,5031.5
Exp/Cntr=0.3,0.1

Type RM Length L Ch R = 1,16742,473,473,473
BEGIN DESCRIPTION:
Stream0474 37.0
END DESCRIPTION:
XS GIS Cut Line= 3
      2471425.01     13766425.03      2471325.00     13766175.00
      2470874.99     13765574.99
#Sta/Elev= 30
  4730.3  372.92  4751.9  372.88  4769.4  370.95  4797.6  370.92  4838.0  369.09
  4852.8  369.39  4877.1  366.72  4882.5  367.30  4930.9  363.37  4975.1  362.45
  4988.2  362.15  4988.4  361.65  4992.2  362.15  5027.7  363.39  5096.6  363.08
  5142.3  364.87  5171.5  367.51  5177.7  366.78  5192.3  366.80  5206.9  367.94
  5242.3  367.81  5271.5  369.15  5349.6  370.08  5410.6  372.05  5499.6  375.31
  5527.7  377.04  5627.7  379.80  5677.7  382.20  5736.0  386.35  5749.6  385.84
#Mann=6,-1,0
  4730.3    0.05       0  4975.1    0.12       0  4988.2    0.05       0
  4992.2    0.12       0  5096.6    0.07       0  5410.6    0.05       0
Bank Sta=4988.2,4992.2
Exp/Cntr=0.3,0.1

Type RM Length L Ch R = 1,16269,440,440,440
BEGIN DESCRIPTION:
Stream0474 36.0
END DESCRIPTION:
XS GIS Cut Line= 3
      2472224.99     13766574.99      2471625.00     13765975.00
      2471375.02     13765675.02
#Sta/Elev= 30
  4155.4  388.08  4327.5  381.38  4494.9  375.13  4565.5  372.88  4607.9  372.44
  4636.2  370.32  4650.4  370.87  4664.5  373.01  4706.9  373.31  4735.2  372.21
  4765.7  367.89  4791.8  364.87  4811.0  365.83  4820.1  366.50  4848.3  365.78
  4876.6  362.20  4888.8  362.13  4889.0  361.63  4892.8  362.13  4989.8  362.42
  5000.4  364.76  5007.2  364.76  5011.1  366.76  5039.8  367.05  5054.0  366.41
  5060.5  365.31  5094.8  365.68  5240.9  369.07  5316.3  371.70  5394.4  373.31
#Mann=10,-1,0
  4155.4    0.07       0  4327.5    0.05       0  4494.9   0.035       0
  4765.7    0.07       0  4811.0    0.12       0  4888.8    0.05       0
  4892.8    0.12       0  5039.8    0.07       0  5094.8    0.05       0
  5240.9    0.07       0
Bank Sta=4888.8,4892.8
Exp/Cntr=0.3,0.1

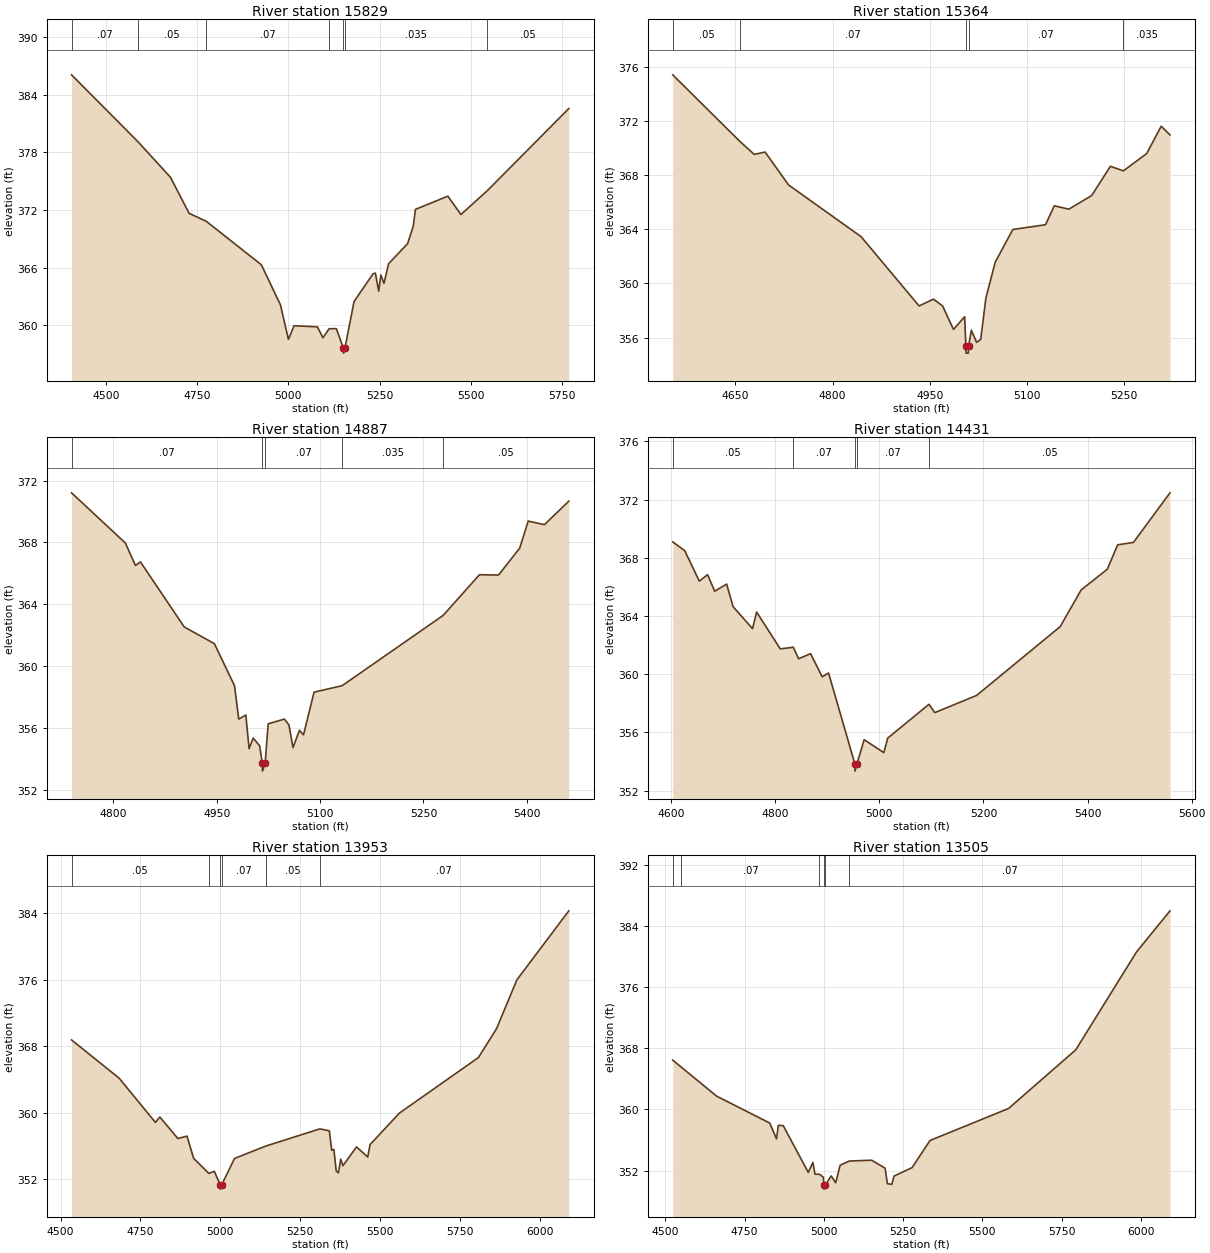
Type RM Length L Ch R = 1,15829,465,465,465
BEGIN DESCRIPTION:
Stream0474 35.0
END DESCRIPTION:
XS GIS Cut Line= 3
      2472275.43     13766455.87      2472025.00     13765925.00
      2471619.47     13765262.77
#Sta/Elev= 30
  4405.5  386.08  4587.7  379.11  4676.7  375.41  4727.8  371.66  4775.1  370.82
  4926.1  366.29  4978.3  362.12  5000.2  358.52  5015.6  359.94  5079.5  359.83
  5095.0  358.69  5111.7  359.63  5131.7  359.64  5151.0  357.59  5151.3  357.09
  5155.0  357.59  5180.2  362.47  5232.3  365.36  5238.7  365.42  5247.8  363.55
  5253.6  365.23  5262.2  364.36  5274.9  366.40  5327.1  368.50  5342.6  370.33
  5348.4  372.06  5437.3  373.44  5473.2  371.53  5545.8  374.02  5769.0  382.57
#Mann=7,-1,0
  4405.5    0.07       0  4587.7    0.05       0  4775.1    0.07       0
  5111.7   0.035       0  5151.0    0.05       0  5155.0   0.035       0
  5545.8    0.05       0
Bank Sta=5151,5155
Exp/Cntr=0.3,0.1

Type RM Length L Ch R = 1,15364,477,477,477
BEGIN DESCRIPTION:
Stream0474 34.0
END DESCRIPTION:
XS GIS Cut Line= 3
      2472424.98     13766024.96      2472225.00     13765625.00
      2472025.02     13765375.02
#Sta/Elev= 30
  4553.2  375.42  4657.0  370.49  4678.9  369.54  4695.7  369.71  4732.0  367.28
  4843.8  363.46  4933.3  358.34  4955.6  358.84  4969.6  358.34  4986.4  356.60
  5003.6  357.54  5005.6  355.35  5005.8  354.85  5009.3  354.85  5009.6  355.35
  5014.0  356.54  5022.0  355.65  5028.4  355.86  5036.4  358.92  5050.8  361.57
  5078.0  363.99  5128.4  364.34  5142.0  365.74  5164.4  365.49  5199.7  366.50
  5228.5  368.66  5248.6  368.32  5284.5  369.60  5306.9  371.62  5320.5  370.98
#Mann=5,-1,0
  4553.2    0.05       0  4657.0    0.07       0  5005.6    0.05       0
  5009.6    0.07       0  5248.6   0.035       0
Bank Sta=5005.6,5009.6
Exp/Cntr=0.3,0.1

Type RM Length L Ch R = 1,14887,456,456,456
BEGIN DESCRIPTION:
Stream0474 33.0
END DESCRIPTION:
XS GIS Cut Line= 3
      2472775.02     13765675.02      2472625.00     13765475.00
      2472225.02     13765225.01
#Sta/Elev= 30
  4739.3  371.21  4817.5  367.96  4832.0  366.51  4839.3  366.74  4902.9  362.53
  4946.6  361.45  4975.8  358.73  4982.0  356.57  4992.3  356.83  4997.0  354.65
  5002.9  355.34  5012.3  354.84  5016.2  353.70  5016.4  353.20  5020.3  353.70
  5024.7  356.26  5048.3  356.57  5054.8  356.19  5060.7  354.72  5070.1  355.84
  5076.0  355.55  5091.3  358.31  5132.1  358.73  5278.7  363.28  5331.3  365.91
  5359.0  365.89  5389.7  367.63  5402.1  369.38  5425.6  369.15  5461.0  370.67
#Mann=5,-1,0
  4739.3    0.07       0  5016.2    0.05       0  5020.3    0.07       0
  5132.1   0.035       0  5278.7    0.05       0
Bank Sta=5016.2,5020.3
Exp/Cntr=0.3,0.1

Type RM Length L Ch R = 1,14431,478,478,478
BEGIN DESCRIPTION:
Stream0474 32.0
END DESCRIPTION:
XS GIS Cut Line= 3
      2472974.99     13765474.98      2472775.00     13765125.00
      2472224.96     13765075.00
#Sta/Elev= 30
  4603.0  369.09  4626.0  368.49  4654.1  366.39  4669.9  366.84  4683.6  365.70
  4706.6  366.19  4718.9  364.64  4756.3  363.13  4764.2  364.27  4809.6  361.74
  4834.7  361.85  4844.8  361.06  4867.9  361.41  4890.2  359.82  4902.4  360.08
  4952.9  353.84  4953.2  353.34  4957.0  353.84  4970.8  355.50  5008.6  354.61
  5016.1  355.61  5095.3  357.93  5106.5  357.36  5186.8  358.54  5347.5  363.27
  5387.7  365.79  5437.9  367.21  5457.9  368.89  5488.1  369.05  5558.4  372.46
#Mann=5,-1,0
  4603.0    0.05       0  4834.7    0.07       0  4952.9    0.05       0
  4957.0    0.07       0  5095.3    0.05       0
Bank Sta=4952.9,4957
Exp/Cntr=0.3,0.1

Type RM Length L Ch R = 1,13953,448,448,448
BEGIN DESCRIPTION:
Stream0474 31.0
END DESCRIPTION:
XS GIS Cut Line= 3
      2473374.99     13765174.99      2473075.00     13764825.00
      2472325.03     13764025.03
#Sta/Elev= 30
  4534.3  368.78  4683.0  364.19  4797.1  358.85  4810.9  359.50  4867.4  356.91
  4895.9  357.20  4916.8  354.52  4964.2  352.72  4981.5  352.96  5000.2  351.32
  5000.5  350.82  5004.4  351.32  5044.8  354.51  5141.9  355.99  5311.8  358.07
  5341.8  357.84  5349.1  355.50  5356.0  355.60  5363.3  353.00  5370.2  352.79
  5377.5  354.43  5384.3  353.64  5426.8  355.90  5462.0  354.69  5469.3  356.18
  5561.1  359.97  5808.8  366.66  5865.4  370.13  5929.0  376.00  6091.8  384.32
#Mann=6,-1,0
  4534.3    0.05       0  4964.2    0.07       0  5000.2    0.05       0
  5004.4    0.07       0  5141.9    0.05       0  5311.8    0.07       0
Bank Sta=5000.2,5004.4
Exp/Cntr=0.3,0.1

Type RM Length L Ch R = 1,13505,478,478,478
BEGIN DESCRIPTION:
Stream0474 30.0
END DESCRIPTION:
XS GIS Cut Line= 3
      2473625.01     13764975.02      2473375.00     13764575.00
      2472625.00     13763775.00
#Sta/Elev= 30
  4523.6  366.45  4550.2  365.54  4662.2  361.73  4829.6  358.22  4850.9  356.15
  4856.8  357.92  4872.1  357.88  4951.1  351.77  4965.8  353.06  4972.3  351.53
  4986.4  351.53  4998.7  351.13  5000.3  350.08  5000.6  349.58  5004.5  350.08
  5023.4  351.31  5037.6  350.41  5051.7  352.72  5080.3  353.25  5150.9  353.36
  5193.4  352.32  5200.7  350.29  5214.6  350.20  5221.7  351.29  5278.4  352.39
  5335.0  355.94  5582.7  360.12  5794.7  367.79  5985.7  380.55  6091.9  385.96
#Mann=6,-1,0
  4523.6    0.05       0  4550.2    0.07       0  4986.4    0.12       0
  5000.3    0.05       0  5004.5    0.12       0  5080.3    0.07       0
Bank Sta=5000.3,5004.5
Exp/Cntr=0.3,0.1

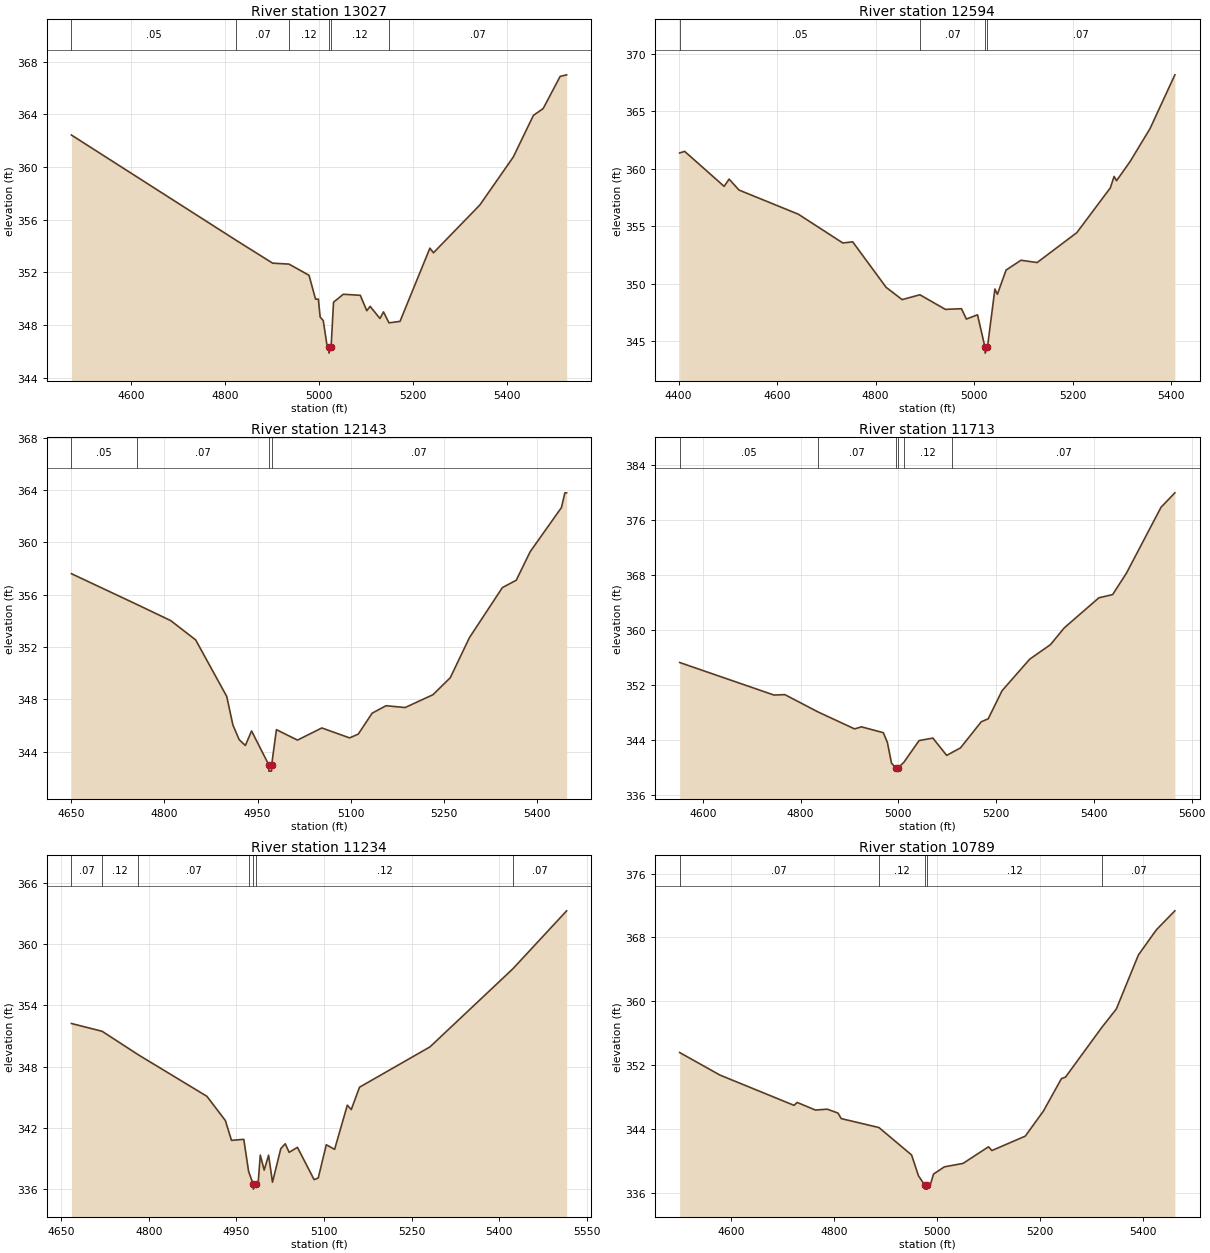
Type RM Length L Ch R = 1,13027,433,433,433
BEGIN DESCRIPTION:
Stream0474 29.0
END DESCRIPTION:
XS GIS Cut Line= 3
      2473775.01     13764775.04      2473625.00     13764275.00
      2473274.98     13763874.97
#Sta/Elev= 30
  4473.5  362.43  4824.7  354.42  4901.6  352.70  4936.4  352.63  4979.0  351.78
  4992.9  349.97  4998.9  349.97  5002.7  348.61  5009.3  348.34  5016.9  346.55
  5021.2  346.37  5021.5  345.87  5026.0  346.37  5031.2  349.74  5052.0  350.34
  5088.1  350.26  5101.9  349.09  5109.0  349.42  5129.9  348.50  5137.5  349.00
  5149.1  348.17  5172.6  348.28  5236.2  353.84  5243.8  353.49  5342.5  357.12
  5413.6  360.76  5456.4  363.92  5477.2  364.44  5513.3  366.88  5527.1  367.00
#Mann=6,-1,0
  4473.5    0.05       0  4824.7    0.07       0  4936.4    0.12       0
  5021.2    0.05       0  5026.0    0.12       0  5149.1    0.07       0
Bank Sta=5021.2,5026
Exp/Cntr=0.3,0.1

Type RM Length L Ch R = 1,12594,451,451,451
BEGIN DESCRIPTION:
Stream0474 28.0
END DESCRIPTION:
XS GIS Cut Line= 3
      2474025.00     13764725.03      2473975.00     13764125.00
      2474025.00     13763725.02
#Sta/Elev= 30
  4402.2  361.37  4412.3  361.51  4492.5  358.47  4502.6  359.10  4522.6  358.15
  4643.1  356.05  4733.4  353.55  4753.4  353.65  4821.2  349.70  4853.8  348.63
  4889.8  349.05  4941.6  347.78  4974.2  347.84  4984.2  346.94  5006.8  347.31
  5022.0  344.48  5022.4  343.98  5026.9  344.48  5042.1  349.55  5047.1  349.09
  5064.8  351.20  5095.0  352.05  5127.8  351.85  5208.4  354.45  5276.4  358.34
  5284.0  359.33  5289.0  358.96  5316.7  360.64  5357.0  363.49  5407.4  368.16
#Mann=4,-1,0
  4402.2    0.05       0  4889.8    0.07       0  5022.0    0.05       0
  5026.9    0.07       0
Bank Sta=5022,5026.9
Exp/Cntr=0.3,0.1

Type RM Length L Ch R = 1,12143,430,430,430
BEGIN DESCRIPTION:
Stream0474 27.0
END DESCRIPTION:
XS GIS Cut Line= 3
      2474375.00     13764524.97      2474375.00     13764175.00
      2474174.99     13763774.99
#Sta/Elev= 30
  4650.4  357.61  4755.8  355.26  4810.4  354.02  4850.4  352.55  4900.4  348.23
  4910.4  346.04  4920.4  344.93  4930.4  344.48  4940.4  345.59  4967.9  343.02
  4968.3  342.52  4972.5  342.52  4972.8  343.02  4980.4  345.69  5014.3  344.89
  5053.5  345.82  5098.2  345.06  5112.2  345.35  5134.5  346.95  5156.9  347.52
  5187.6  347.38  5232.4  348.36  5260.3  349.66  5291.1  352.72  5344.2  356.55
  5366.5  357.11  5388.9  359.29  5439.2  362.66  5444.8  363.79  5447.6  363.79
#Mann=4,-1,0
  4650.4    0.05       0  4755.8    0.07       0  4967.9    0.05       0
  4972.8    0.07       0
Bank Sta=4967.9,4972.8
Exp/Cntr=0.3,0.1

Type RM Length L Ch R = 1,11713,479,479,479
BEGIN DESCRIPTION:
Stream0474 26.0
END DESCRIPTION:
XS GIS Cut Line= 3
      2474875.01     13764375.02      2474675.00     13763975.00
      2474275.02     13763575.02
#Sta/Elev= 30
  4552.8  355.24  4745.7  350.50  4768.0  350.56  4836.1  348.03  4910.6  345.57
  4924.6  345.87  4969.3  345.02  4977.7  343.60  4986.1  340.58  4994.7  339.92
  4995.1  339.42  4999.3  339.42  4999.7  339.92  5011.4  340.71  5042.5  343.87
  5070.7  344.23  5099.0  341.71  5110.2  342.15  5127.3  342.81  5169.7  346.61
  5183.9  347.04  5212.2  351.13  5268.7  355.72  5311.2  357.84  5339.4  360.28
  5410.2  364.66  5438.4  365.13  5466.7  368.26  5537.4  377.85  5565.7  379.95
#Mann=6,-1,0
  4552.8    0.05       0  4836.1    0.07       0  4994.7    0.05       0
  4999.7    0.07       0  5011.4    0.12       0  5110.2    0.07       0
Bank Sta=4994.7,4999.7
Exp/Cntr=0.3,0.1

Type RM Length L Ch R = 1,11234,445,445,445
BEGIN DESCRIPTION:
Stream0474 25.0
END DESCRIPTION:
XS GIS Cut Line= 3
      2475174.99     13764174.96      2475075.00     13763875.00
      2474675.00     13763525.00
#Sta/Elev= 30
  4667.5  352.23  4720.0  351.47  4782.3  349.16  4899.4  345.11  4931.0  342.74
  4941.5  340.80  4962.6  340.90  4970.8  337.76  4978.6  336.53  4978.9  336.03
  4983.6  336.53  4987.0  336.53  4990.8  339.36  4997.5  337.89  5005.0  339.35
  5011.7  336.71  5025.9  339.99  5033.5  340.47  5040.2  339.63  5054.4  340.12
  5082.9  336.96  5090.0  337.12  5103.8  340.37  5118.0  339.92  5139.8  344.24
  5146.5  343.81  5160.7  346.00  5281.2  349.94  5423.0  357.57  5515.2  363.25
#Mann=7,-1,0
  4667.5    0.07       0  4720.0    0.12       0  4782.3    0.07       0
  4970.8    0.12       0  4978.6    0.05       0  4983.6    0.12       0
  5423.0    0.07       0
Bank Sta=4978.6,4983.6
Exp/Cntr=0.3,0.1

Type RM Length L Ch R = 1,10789,468,468,468
BEGIN DESCRIPTION:
Stream0474 24.0
END DESCRIPTION:
XS GIS Cut Line= 3
      2475624.99     13763974.98      2475325.00     13763575.00
      2475024.97     13763224.96
#Sta/Elev= 30
  4500.5  353.59  4578.6  350.77  4722.4  346.98  4728.6  347.34  4764.0  346.39
  4786.9  346.50  4807.8  346.01  4814.0  345.32  4887.2  344.20  4950.5  340.77
  4964.0  338.15  4976.1  336.99  4976.5  336.49  4980.8  336.49  4981.2  336.99
  4986.9  337.04  4993.2  338.38  5014.2  339.28  5050.4  339.71  5099.8  341.79
  5106.4  341.32  5171.1  343.12  5206.3  346.25  5241.4  350.33  5249.1  350.50
  5320.0  356.76  5347.9  359.04  5390.7  365.80  5425.8  368.97  5461.5  371.33
#Mann=5,-1,0
  4500.5    0.07       0  4887.2    0.12       0  4976.1    0.05       0
  4981.2    0.12       0  5320.0    0.07       0
Bank Sta=4976.1,4981.2
Exp/Cntr=0.3,0.1

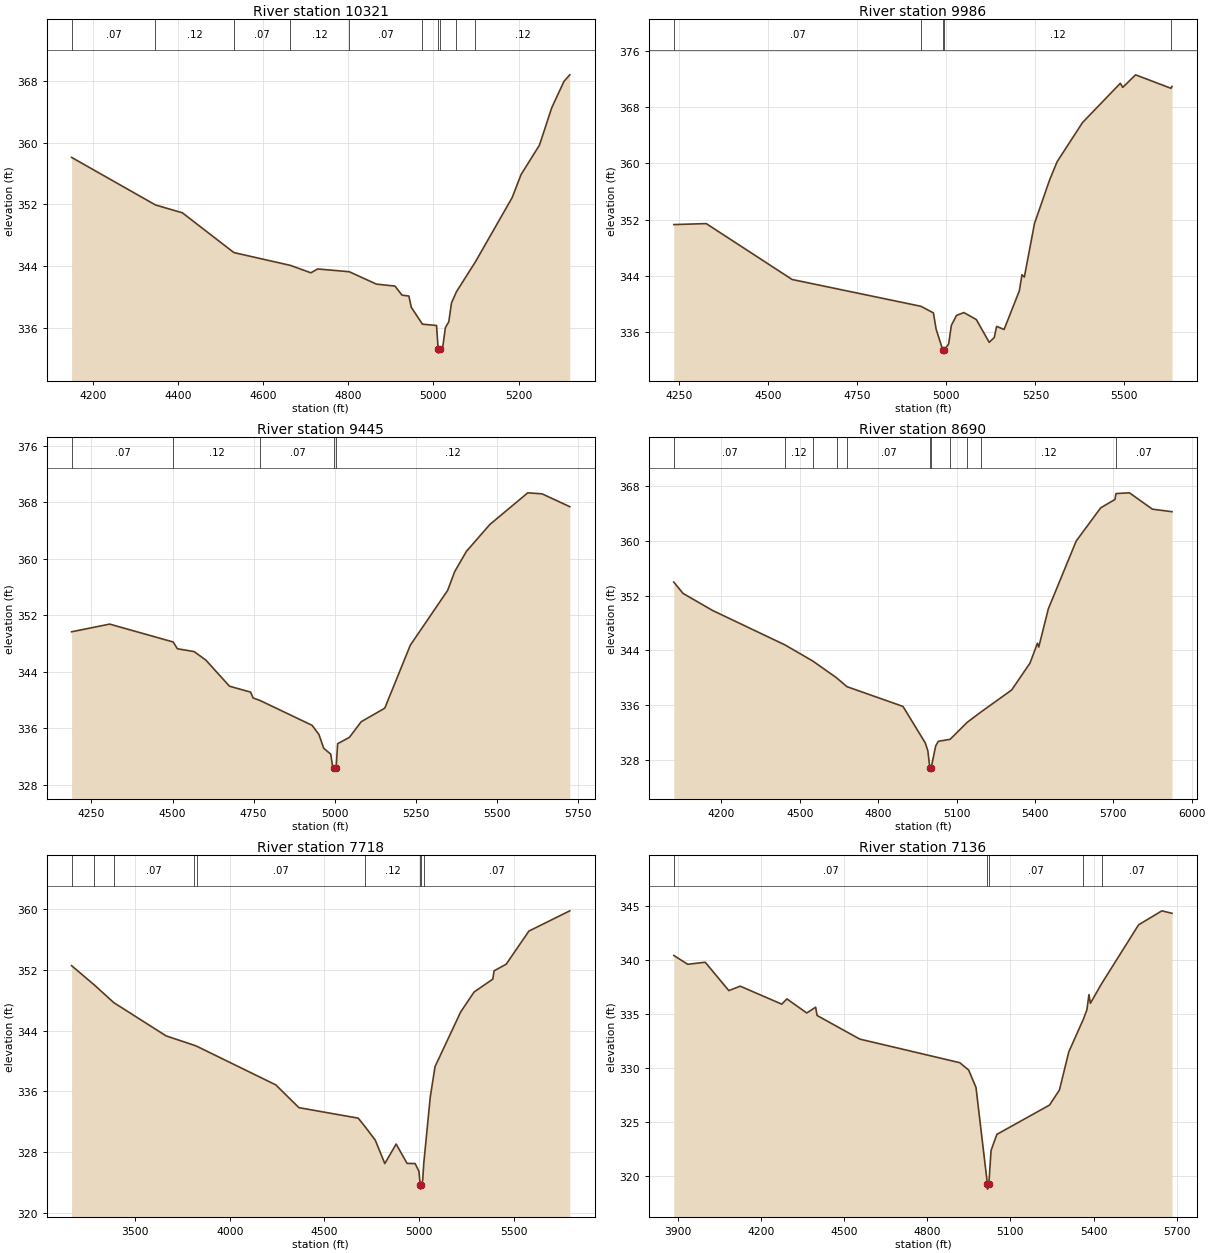
Type RM Length L Ch R = 1,10321,335,335,335
BEGIN DESCRIPTION:
Stream0474 23.0
END DESCRIPTION:
XS GIS Cut Line= 3
      2475875.01     13763975.02      2475475.00     13763225.00
      2475224.98     13763024.99
#Sta/Elev= 30
  4150.1  358.09  4347.1  351.93  4410.4  350.91  4531.4  345.76  4664.2  344.10
  4712.2  343.14  4728.1  343.64  4802.4  343.28  4865.9  341.68  4909.8  341.42
  4926.1  340.25  4942.4  340.13  4948.1  338.67  4974.2  336.49  5007.3  336.32
  5011.2  333.24  5011.6  332.74  5016.3  333.24  5021.7  333.45  5028.1  336.04
  5036.1  336.80  5042.5  339.25  5054.1  340.69  5098.7  344.57  5185.0  352.89
  5205.8  355.86  5249.0  359.67  5277.9  364.52  5306.7  367.94  5320.3  368.78
#Mann=10,-1,0
  4150.1    0.07       0  4347.1    0.12       0  4531.4    0.07       0
  4664.2    0.12       0  4802.4    0.07       0  4974.2    0.12       0
  5011.2    0.05       0  5016.3    0.12       0  5054.1    0.07       0
  5098.7    0.12       0
Bank Sta=5011.2,5016.3
Exp/Cntr=0.3,0.1

Type RM Length L Ch R = 1,9986,541,541,541
BEGIN DESCRIPTION:
XS6895
END DESCRIPTION:
XS GIS Cut Line= 2
      2476293.14     13763535.95      2475239.54     13762615.72
#Sta/Elev= 30
  4234.7  351.28  4325.8  351.42  4566.9  343.46  4928.6  339.64  4963.7  338.70
  4971.3  336.38  4989.6  333.47  4990.0  332.97  4994.7  333.47  5006.4  334.27
  5014.0  336.91  5028.2  338.33  5049.1  338.75  5084.2  337.75  5120.3  334.51
  5134.5  335.19  5141.2  336.78  5162.1  336.34  5204.8  341.82  5212.4  344.14
  5219.0  343.81  5247.5  351.44  5290.2  357.68  5311.1  360.24  5382.3  365.81
  5488.6  371.41  5495.2  370.82  5531.3  372.61  5630.7  370.69  5633.6  370.96
#Mann=5,-1,0
  4234.7    0.07       0  4928.6    0.12       0  4989.6    0.05       0
  4994.7    0.12       0  5630.7    0.07       0
Bank Sta=4989.6,4994.7
Exp/Cntr=0.3,0.1

Type RM Length L Ch R = 1,9445,755,755,755
BEGIN DESCRIPTION:
XS6894
END DESCRIPTION:
XS GIS Cut Line= 2
      2476680.03     13763162.36      2475385.90     13762335.18
#Sta/Elev= 30
  4188.6  349.67  4305.9  350.76  4501.7  348.23  4515.0  347.27  4566.4  346.87
  4602.7  345.66  4675.5  341.97  4740.5  341.14  4748.2  340.31  4770.2  339.94
  4930.1  336.44  4951.2  335.14  4966.0  333.19  4987.6  332.36  4993.5  330.56
  4999.0  330.46  4999.4  329.96  5004.2  330.46  5008.8  333.84  5045.1  334.74
  5081.5  336.95  5154.2  338.87  5232.9  347.78  5348.0  355.53  5369.5  358.17
  5405.5  361.03  5478.2  364.86  5595.0  369.33  5638.9  369.19  5724.5  367.37
#Mann=5,-1,0
  4188.6    0.07       0  4501.7    0.12       0  4770.2    0.07       0
  4999.0    0.05       0  5004.2    0.12       0
Bank Sta=4999,5004.2
Exp/Cntr=0.3,0.1

Type RM Length L Ch R = 1,8690,972,972,972
BEGIN DESCRIPTION:
XS6893
END DESCRIPTION:
XS GIS Cut Line= 3
      2477267.06     13762601.99      2476426.55     13762201.75
      2475452.57     13762135.04
#Sta/Elev= 30
  4017.6  353.97  4053.1  352.31  4165.6  349.83  4442.9  344.79  4549.6  342.43
  4640.5  339.98  4680.4  338.68  4894.9  335.79  4980.2  330.46  4990.2  329.31
  4997.6  326.83  4998.0  326.33  5002.9  326.83  5020.3  330.03  5030.3  330.69
  5075.3  330.98  5140.9  333.47  5195.5  335.03  5310.9  338.19  5381.1  342.12
  5409.7  345.03  5414.7  344.47  5451.3  350.05  5558.0  359.97  5651.7  364.82
  5706.4  366.05  5710.3  366.91  5762.0  367.02  5849.7  364.63  5924.8  364.26
#Mann=11,-1,0
  4017.6    0.07       0  4442.9    0.12       0  4549.6    0.07       0
  4640.5    0.12       0  4680.4    0.07       0  4997.6    0.05       0
  5002.9    0.07       0  5075.3    0.12       0  5140.9    0.07       0
  5195.5    0.12       0  5710.3    0.07       0
Bank Sta=4997.6,5002.9
Exp/Cntr=0.3,0.1

Type RM Length L Ch R = 1,7718,582,582,582
BEGIN DESCRIPTION:
XS6892
END DESCRIPTION:
XS GIS Cut Line= 4
      2477827.46     13762228.44      2476786.78     13761494.63
      2476012.95     13761441.26      2475612.67     13761868.22
#Sta/Elev= 30
  3162.9  352.52  3282.5  350.00  3386.2  347.66  3662.4  343.30  3809.5  342.08
  3824.4  341.94  4242.7  336.86  4365.0  333.87  4678.6  332.49  4714.9  331.37
  4768.8  329.60  4819.0  326.53  4879.1  329.09  4936.9  326.55  4979.3  326.53
  4999.4  325.53  5006.8  323.67  5007.2  323.17  5012.1  323.67  5019.4  324.36
  5025.2  326.58  5059.5  335.28  5084.7  339.26  5220.1  346.43  5290.9  349.05
  5390.1  350.75  5396.9  351.84  5460.9  352.71  5581.1  357.06  5797.2  359.72
#Mann=9,-1,0
  3162.9    0.07       0  3282.5    0.12       0  3386.2    0.07       0
  3809.5   0.035       0  3824.4    0.07       0  4714.9    0.12       0
  5006.8    0.05       0  5012.1    0.12       0  5025.2    0.07       0
Bank Sta=5006.8,5012.1
Exp/Cntr=0.3,0.1

Type RM Length L Ch R = 1,7136,460,460,460
BEGIN DESCRIPTION:
E21079
END DESCRIPTION:
XS GIS Cut Line= 3
      2477682.72     13761460.42      2476380.99     13761034.12
      2475969.94     13761152.11
#Sta/Elev= 30
  3885.6  340.42  3935.8  339.60  3999.0  339.79  4084.1  337.16  4125.2  337.57
  4275.2  335.90  4293.6  336.39  4365.4  335.08  4397.3  335.62  4402.6  334.85
  4556.5  332.66  4917.4  330.47  4949.3  329.79  4975.9  328.17  5016.9  319.24
  5017.4  318.74  5022.3  319.24  5030.2  322.33  5051.2  323.82  5241.2  326.54
  5276.9  327.94  5310.7  331.48  5363.0  334.49  5376.0  335.38  5383.3  336.79
  5388.5  335.98  5429.5  337.82  5562.4  343.26  5646.5  344.56  5683.0  344.33
#Mann=5,-1,0
  3885.6    0.07       0  5016.9    0.05       0  5022.3    0.07       0
  5363.0    0.12       0  5429.5    0.07       0
Bank Sta=5016.9,5022.3
Exp/Cntr=0.3,0.1