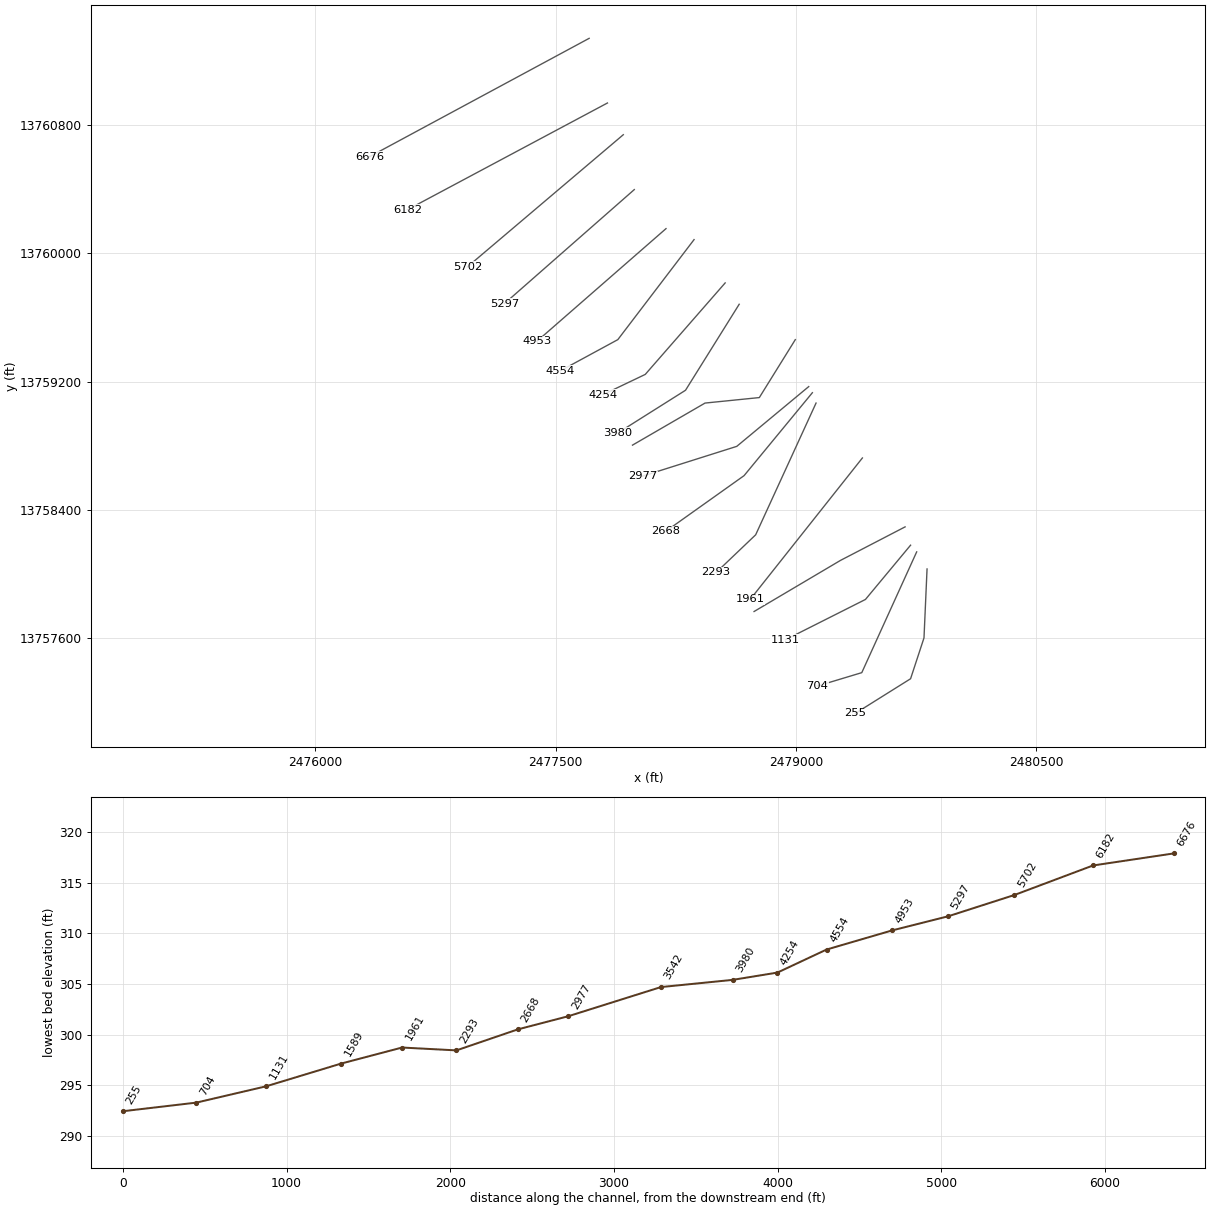
HEC-RAS study Stream0474.prj: Stream0474 Base Level Engineering

--- Stream0474.g01 (geometry) --- (continued)

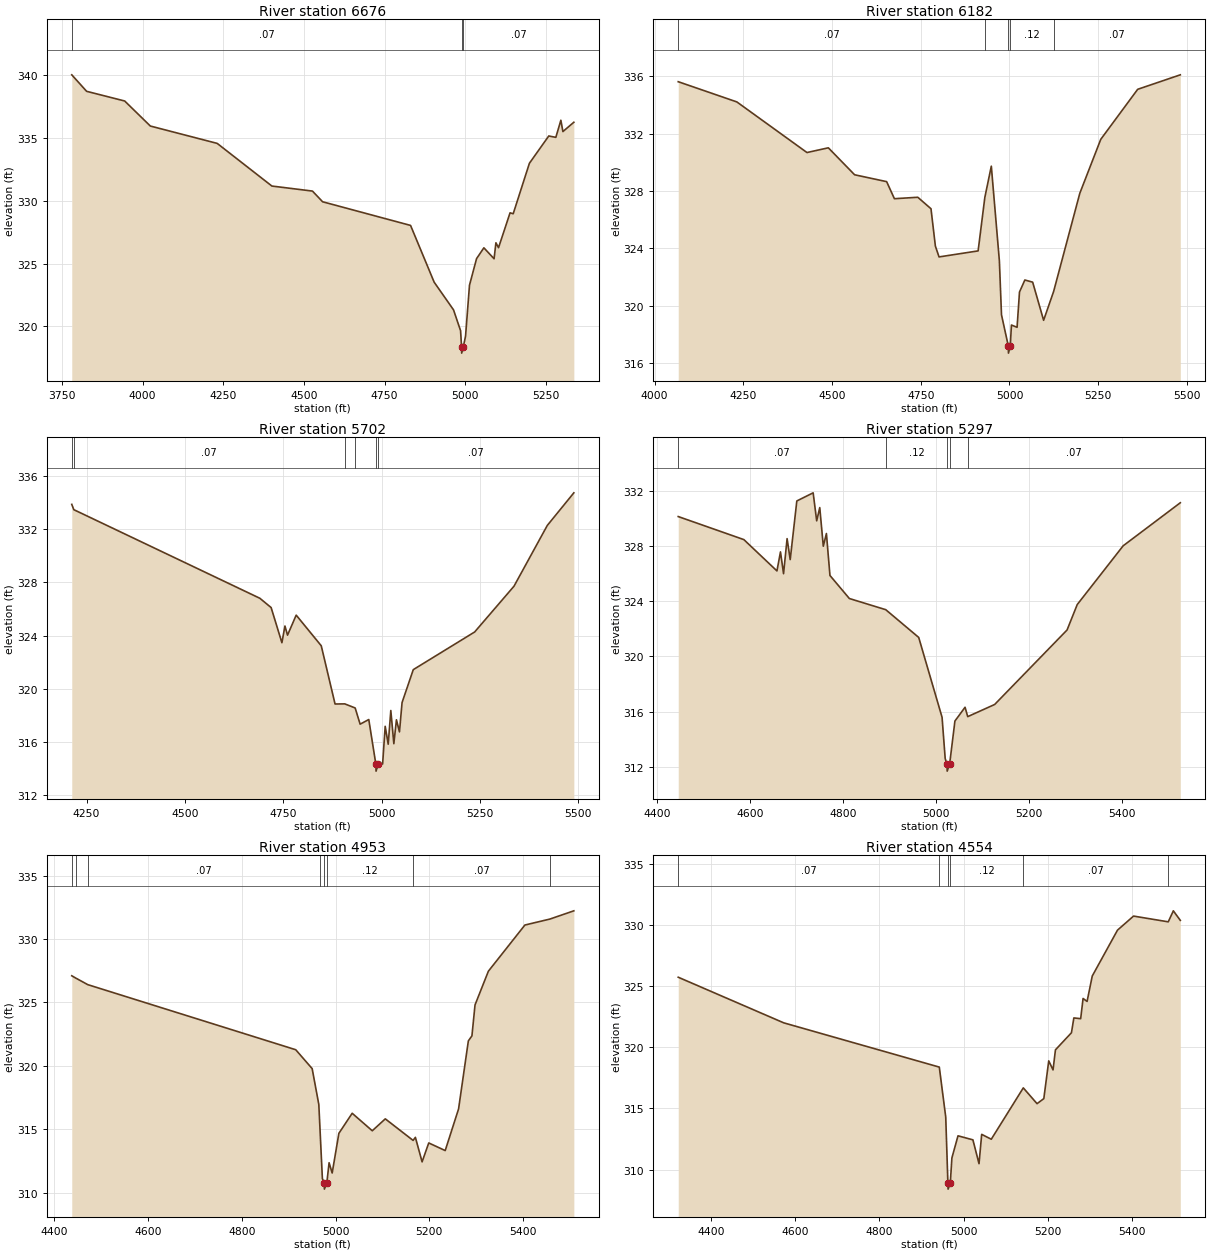
Type RM Length L Ch R = 1,6676,494,494,494
BEGIN DESCRIPTION:
E21078
END DESCRIPTION:
XS GIS Cut Line= 2
      2477709.34     13761342.43      2476339.57     13760604.27
#Sta/Elev= 30
  3780.3  340.00  3826.3  338.69  3944.3  337.92  4023.8  335.93  4231.0  334.55
  4400.5  331.16  4526.2  330.76  4557.7  329.91  4830.3  328.03  4903.4  323.52
  4963.4  321.32  4985.3  319.66  4988.3  318.38  4988.7  317.88  4993.7  318.38
  5000.7  319.23  5012.9  323.28  5034.8  325.39  5057.5  326.25  5089.1  325.38
  5094.8  326.65  5102.9  326.26  5138.6  329.03  5148.4  328.96  5198.6  332.97
  5258.6  335.14  5280.5  335.03  5296.1  336.39  5302.4  335.49  5336.3  336.23
#Mann=3,-1,0
  3780.3    0.07       0  4988.3    0.05       0  4993.7    0.07       0
Bank Sta=4988.3,4993.7
Exp/Cntr=0.3,0.1

Type RM Length L Ch R = 1,6182,480,480,480
BEGIN DESCRIPTION:
E21077
END DESCRIPTION:
XS GIS Cut Line= 2
      2477823.47     13760938.95      2476575.14     13760272.92
#Sta/Elev= 30
  4066.6  335.62  4231.8  334.21  4429.4  330.68  4489.6  331.01  4563.6  329.13
  4653.9  328.65  4675.8  327.46  4741.7  327.56  4778.9  326.76  4791.3  324.15
  4801.6  323.40  4911.7  323.82  4930.7  327.56  4948.9  329.73  4971.6  323.13
  4977.6  319.36  4996.8  317.19  4997.2  316.69  5002.3  317.19  5005.6  318.65
  5021.5  318.49  5028.3  320.95  5043.4  321.79  5065.4  321.64  5096.3  318.98
  5124.5  320.99  5198.3  327.84  5257.3  331.60  5361.4  335.09  5481.5  336.10
#Mann=5,-1,0
  4066.6    0.07       0  4930.7    0.12       0  4996.8    0.05       0
  5002.3    0.12       0  5124.5    0.07       0
Bank Sta=4996.8,5002.3
Exp/Cntr=0.3,0.1

Type RM Length L Ch R = 1,5702,405,405,405
BEGIN DESCRIPTION:
E21076
END DESCRIPTION:
XS GIS Cut Line= 2
      2477922.45     13760741.04      2476949.02     13759915.90
#Sta/Elev= 30
  4212.3  333.89  4217.5  333.49  4690.4  326.81  4719.0  326.11  4746.4  323.46
  4754.1  324.72  4760.7  324.03  4782.7  325.54  4846.4  323.23  4881.5  318.84
  4906.2  318.85  4932.6  318.54  4945.2  317.32  4967.2  317.67  4985.3  314.28
  4985.7  313.78  4990.8  314.28  5002.4  314.32  5008.9  317.16  5016.6  315.81
  5023.2  318.35  5030.9  315.85  5037.5  317.65  5045.2  316.74  5051.8  318.95
  5080.3  321.43  5236.3  324.27  5336.3  327.72  5420.9  332.30  5488.4  334.76
#Mann=6,-1,0
  4212.3    0.12       0  4217.5    0.07       0  4906.2    0.12       0
  4932.6    0.07       0  4985.3    0.05       0  4990.8    0.07       0
Bank Sta=4985.3,4990.8
Exp/Cntr=0.3,0.1

Type RM Length L Ch R = 1,5297,344,344,344
BEGIN DESCRIPTION:
E21075
END DESCRIPTION:
XS GIS Cut Line= 2
      2477990.99     13760398.52      2477180.29     13759686.78
#Sta/Elev= 30
  4446.0  330.13  4587.0  328.46  4658.1  326.19  4665.7  327.57  4672.3  325.99
  4679.9  328.53  4686.6  327.01  4700.8  331.26  4735.9  331.85  4743.5  329.82
  4750.1  330.78  4757.7  327.98  4764.4  328.90  4772.0  325.86  4813.7  324.19
  4891.9  323.38  4962.7  321.37  5012.9  315.58  5019.6  312.59  5023.5  312.18
  5023.9  311.68  5029.1  312.18  5040.5  315.31  5062.3  316.31  5068.0  315.63
  5125.9  316.51  5281.5  321.91  5303.3  323.75  5402.0  328.01  5524.8  331.13
#Mann=5,-1,0
  4446.0    0.07       0  4891.9    0.12       0  5023.5    0.05       0
  5029.1    0.12       0  5068.0    0.07       0
Bank Sta=5023.5,5029.1
Exp/Cntr=0.3,0.1

Type RM Length L Ch R = 1,4953,399,399,399
BEGIN DESCRIPTION:
E21074
END DESCRIPTION:
XS GIS Cut Line= 2
      2478188.92     13760154.94      2477381.97     13759450.76
#Sta/Elev= 30
  4437.3  327.10  4446.2  326.91  4471.5  326.40  4915.0  321.27  4950.1  319.78
  4964.3  316.95  4967.1  314.80  4971.9  311.11  4975.8  310.78  4976.2  310.28
  4981.4  310.78  4986.2  312.36  4992.8  311.55  5007.1  314.68  5035.5  316.26
  5078.3  314.88  5106.1  315.82  5165.4  314.12  5170.3  314.36  5184.6  312.43
  5198.8  313.92  5233.9  313.32  5262.4  316.60  5283.3  321.97  5290.9  322.36
  5297.5  324.80  5326.0  327.46  5403.9  331.10  5457.2  331.57  5508.3  332.22
#Mann=8,-1,0
  4437.3    0.07       0  4446.2   0.035       0  4471.5    0.07       0
  4967.1    0.12       0  4975.8    0.05       0  4981.4    0.12       0
  5165.4    0.07       0  5457.2    0.05       0
Bank Sta=4975.8,4981.4
Exp/Cntr=0.3,0.1

Type RM Length L Ch R = 1,4554,300,300,300
BEGIN DESCRIPTION:
E21073
END DESCRIPTION:
XS GIS Cut Line= 3
      2478363.95     13760086.37      2477888.21     13759462.20
      2477530.47     13759268.11
#Sta/Elev= 30
  4322.7  325.73  4573.1  322.00  4942.4  318.38  4957.7  314.29  4962.8  308.90
  4963.3  308.40  4968.5  308.90  4972.3  310.95  4986.8  312.76  5022.2  312.43
  5036.7  310.48  5043.0  312.88  5065.8  312.48  5141.8  316.68  5174.4  315.39
  5190.5  315.80  5202.2  318.89  5212.4  318.15  5218.1  319.79  5256.1  321.19
  5261.8  322.40  5278.0  322.34  5283.7  323.99  5293.2  323.75  5305.5  325.83
  5365.4  329.58  5403.5  330.73  5485.9  330.26  5498.0  331.16  5514.5  330.38
#Mann=6,-1,0
  4322.7    0.07       0  4942.4    0.12       0  4962.8    0.05       0
  4968.5    0.12       0  5141.8    0.07       0  5485.9    0.05       0
Bank Sta=4962.8,4968.5
Exp/Cntr=0.3,0.1

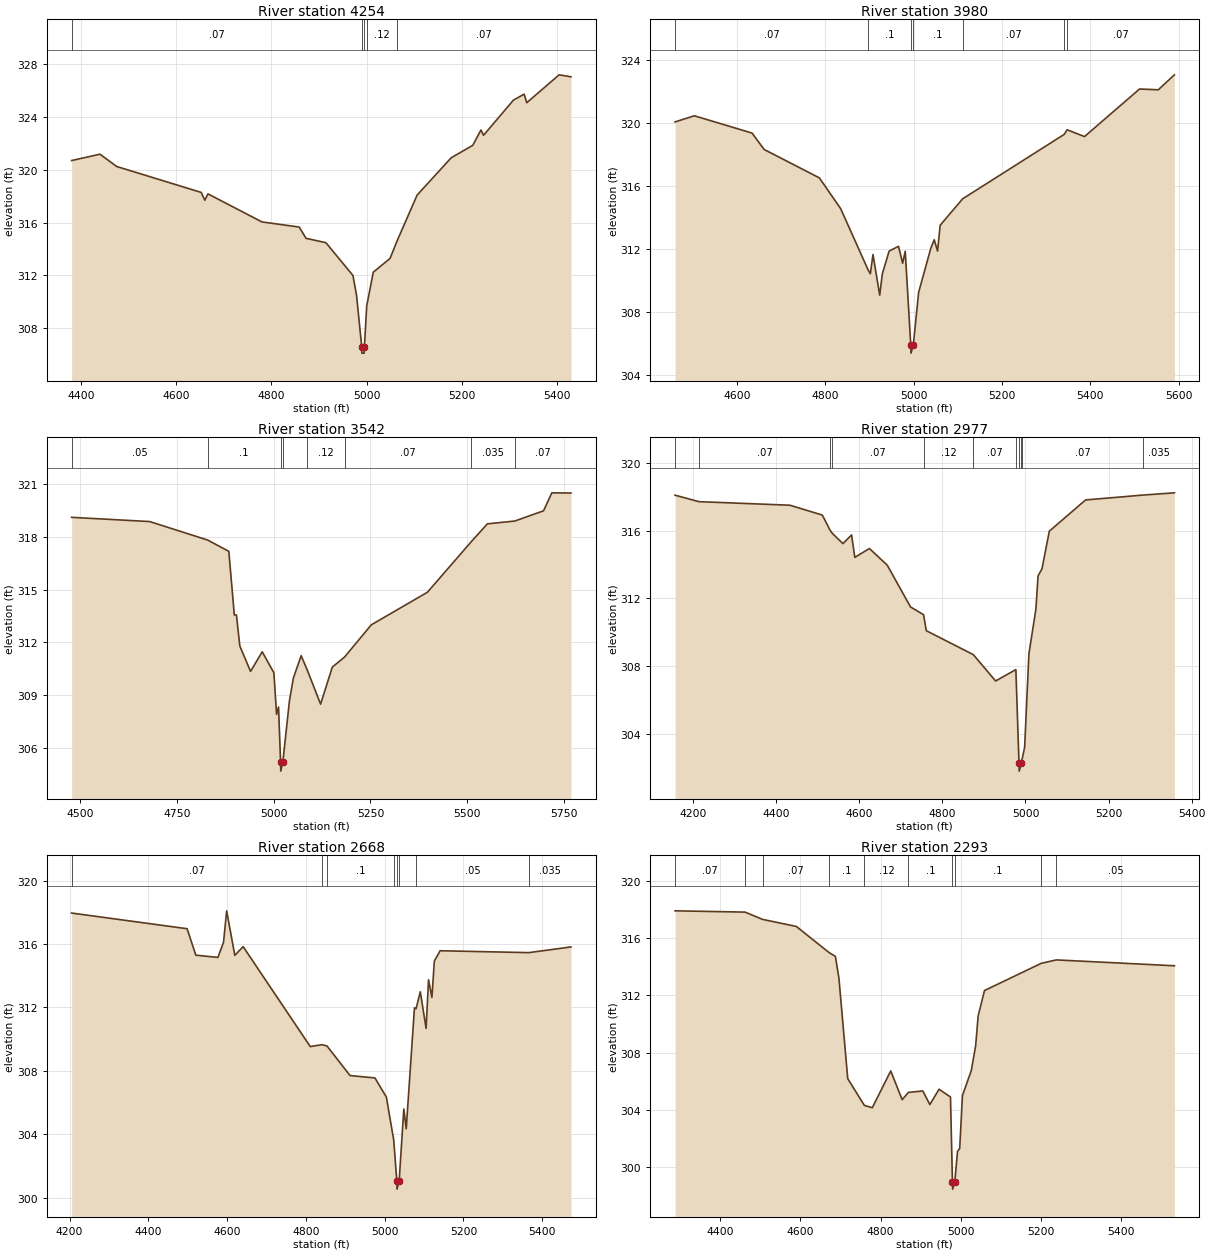
Type RM Length L Ch R = 1,4254,274,274,274
BEGIN DESCRIPTION:
E21072
END DESCRIPTION:
XS GIS Cut Line= 3
      2478558.05     13759816.13      2478059.48     13759245.25
      2477796.82     13759119.63
#Sta/Elev= 30
  4380.3  320.69  4439.8  321.17  4475.0  320.24  4652.5  318.28  4660.1  317.69
  4666.7  318.17  4780.1  316.05  4858.5  315.66  4872.7  314.81  4914.5  314.48
  4971.4  312.00  4979.0  310.48  4989.7  306.63  4990.1  306.13  4994.9  306.13
  4995.4  306.63  5000.3  309.71  5014.1  312.25  5049.3  313.29  5064.4  314.64
  5106.2  318.08  5177.8  320.90  5223.1  321.84  5240.3  323.00  5245.8  322.60
  5308.3  325.25  5331.0  325.71  5336.5  325.06  5404.5  327.17  5429.4  327.02
#Mann=5,-1,0
  4380.3    0.07       0  4989.7    0.05       0  4995.4    0.07       0
  5000.3    0.12       0  5064.4    0.07       0
Bank Sta=4989.7,4995.4
Exp/Cntr=0.3,0.1

Type RM Length L Ch R = 1,3980,438,438,438
BEGIN DESCRIPTION:
E21071
END DESCRIPTION:
XS GIS Cut Line= 3
      2478645.61     13759682.93      2478310.69     13759146.29
      2477889.18     13758880.48
#Sta/Elev= 30
  4459.7  320.09  4503.3  320.48  4634.1  319.38  4661.4  318.34  4786.4  316.54
  4834.8  314.58  4897.3  310.67  4902.0  310.45  4907.9  311.67  4923.2  309.09
  4929.1  310.45  4944.5  311.89  4965.7  312.19  4975.1  311.12  4981.0  311.88
  4993.5  305.91  4994.0  305.41  4999.2  305.91  5011.3  309.27  5038.8  312.06
  5046.6  312.61  5054.2  311.89  5060.1  313.53  5111.1  315.21  5341.1  319.30
  5347.5  319.59  5387.0  319.16  5511.7  322.18  5554.1  322.13  5590.6  323.08
#Mann=7,-1,0
  4459.7    0.07       0  4897.3     0.1       0  4993.5    0.05       0
  4999.2     0.1       0  5111.1    0.07       0  5341.1   0.035       0
  5347.5    0.07       0
Bank Sta=4993.5,4999.2
Exp/Cntr=0.3,0.1

Type RM Length L Ch R = 1,3542,565,565,565
BEGIN DESCRIPTION:
E21070
END DESCRIPTION:
XS GIS Cut Line= 4
      2478995.77     13759462.17      2478771.22     13759100.62
      2478432.48     13759066.36      2477979.75     13758803.86
#Sta/Elev= 30
  4478.4  319.10  4680.0  318.86  4829.7  317.81  4884.3  317.17  4898.5  313.56
  4904.0  313.56  4912.7  311.80  4940.4  310.36  4970.6  311.47  5000.7  310.28
  5007.6  307.92  5012.7  308.34  5018.0  305.20  5018.4  304.70  5023.7  305.20
  5040.9  308.70  5051.0  309.98  5071.1  311.25  5086.6  310.45  5121.3  308.50
  5151.5  310.60  5183.1  311.17  5252.2  313.00  5397.2  314.85  5510.8  317.73
  5552.0  318.73  5622.8  318.89  5697.0  319.47  5718.5  320.49  5767.8  320.48
#Mann=8,-1,0
  4478.4    0.05       0  4829.7     0.1       0  5018.0    0.05       0
  5023.7     0.1       0  5086.6    0.12       0  5183.1    0.07       0
  5510.8   0.035       0  5622.8    0.07       0
Bank Sta=5018,5023.7
Exp/Cntr=0.3,0.1

Type RM Length L Ch R = 1,2977,309,309,309
BEGIN DESCRIPTION:
E21069
END DESCRIPTION:
XS GIS Cut Line= 3
      2479079.52     13759169.13      2478630.40     13758796.13
      2478041.06     13758609.82
#Sta/Elev= 30
  4156.6  318.08  4213.9  317.70  4433.0  317.49  4511.1  316.91  4529.0  316.05
  4534.8  315.84  4560.6  315.23  4581.4  315.74  4589.2  314.42  4624.4  314.94
  4667.3  313.96  4723.3  311.50  4754.8  311.04  4761.3  310.10  4874.5  308.69
  4928.1  307.14  4976.9  307.81  4984.4  302.33  4984.9  301.83  4990.2  302.33
  4991.5  302.48  4998.0  303.24  5008.3  308.74  5025.1  311.37  5030.3  313.33
  5039.7  313.74  5057.4  315.96  5144.6  317.80  5283.9  318.09  5358.5  318.22
#Mann=11,-1,0
  4156.6    0.05       0  4213.9    0.07       0  4529.0     0.1       0
  4534.8    0.07       0  4754.8    0.12       0  4874.5    0.07       0
  4976.9    0.12       0  4984.4    0.05       0  4990.2    0.12       0
  4991.5    0.07       0  5283.9   0.035       0
Bank Sta=4984.4,4990.2
Exp/Cntr=0.3,0.1

Type RM Length L Ch R = 1,2668,375,375,375
BEGIN DESCRIPTION:
E21068
END DESCRIPTION:
XS GIS Cut Line= 3
      2479102.35     13759131.06      2478676.07     13758613.44
      2478189.47     13758267.49
#Sta/Elev= 30
  4205.3  317.96  4498.4  316.97  4520.6  315.30  4576.6  315.16  4590.9  316.11
  4598.8  318.10  4619.6  315.29  4640.7  315.84  4811.1  309.53  4841.3  309.65
  4853.8  309.56  4912.1  307.70  4975.3  307.55  5004.3  306.34  5022.9  303.64
  5030.9  301.03  5031.4  300.53  5036.7  301.03  5048.6  305.59  5054.7  304.34
  5075.6  311.98  5079.7  311.92  5090.4  312.99  5105.2  310.68  5111.3  313.75
  5119.9  312.63  5126.1  314.93  5140.8  315.58  5365.9  315.46  5472.9  315.82
#Mann=8,-1,0
  4205.3    0.07       0  4841.3    0.12       0  4853.8     0.1       0
  5022.9    0.12       0  5030.9    0.05       0  5036.7    0.12       0
  5079.7    0.05       0  5365.9   0.035       0
Bank Sta=5030.9,5036.7
Exp/Cntr=0.3,0.1

Type RM Length L Ch R = 1,2293,332,332,332
BEGIN DESCRIPTION:
E21067
END DESCRIPTION:
XS GIS Cut Line= 3
      2479125.18     13759066.33      2478748.39     13758244.24
      2478501.87     13758009.10
#Sta/Elev= 30
  4287.7  317.91  4462.2  317.82  4506.0  317.31  4589.9  316.82  4671.8  314.99
  4687.4  314.73  4696.2  313.21  4718.2  306.18  4759.7  304.31  4779.4  304.15
  4825.4  306.72  4853.9  304.71  4869.4  305.22  4905.4  305.32  4922.9  304.37
  4945.9  305.44  4974.4  304.90  4979.3  298.96  4979.8  298.46  4985.1  298.96
  4991.9  301.09  4997.4  301.31  5004.2  305.00  5026.2  306.74  5037.2  308.50
  5043.4  310.57  5059.2  312.34  5200.7  314.24  5238.3  314.48  5532.7  314.07
#Mann=10,-1,0
  4287.7    0.07       0  4462.2    0.05       0  4506.0    0.07       0
  4671.8     0.1       0  4759.7    0.12       0  4869.4     0.1       0
  4979.3    0.05       0  4985.1     0.1       0  5200.7    0.07       0
  5238.3    0.05       0
Bank Sta=4979.3,4985.1
Exp/Cntr=0.3,0.1

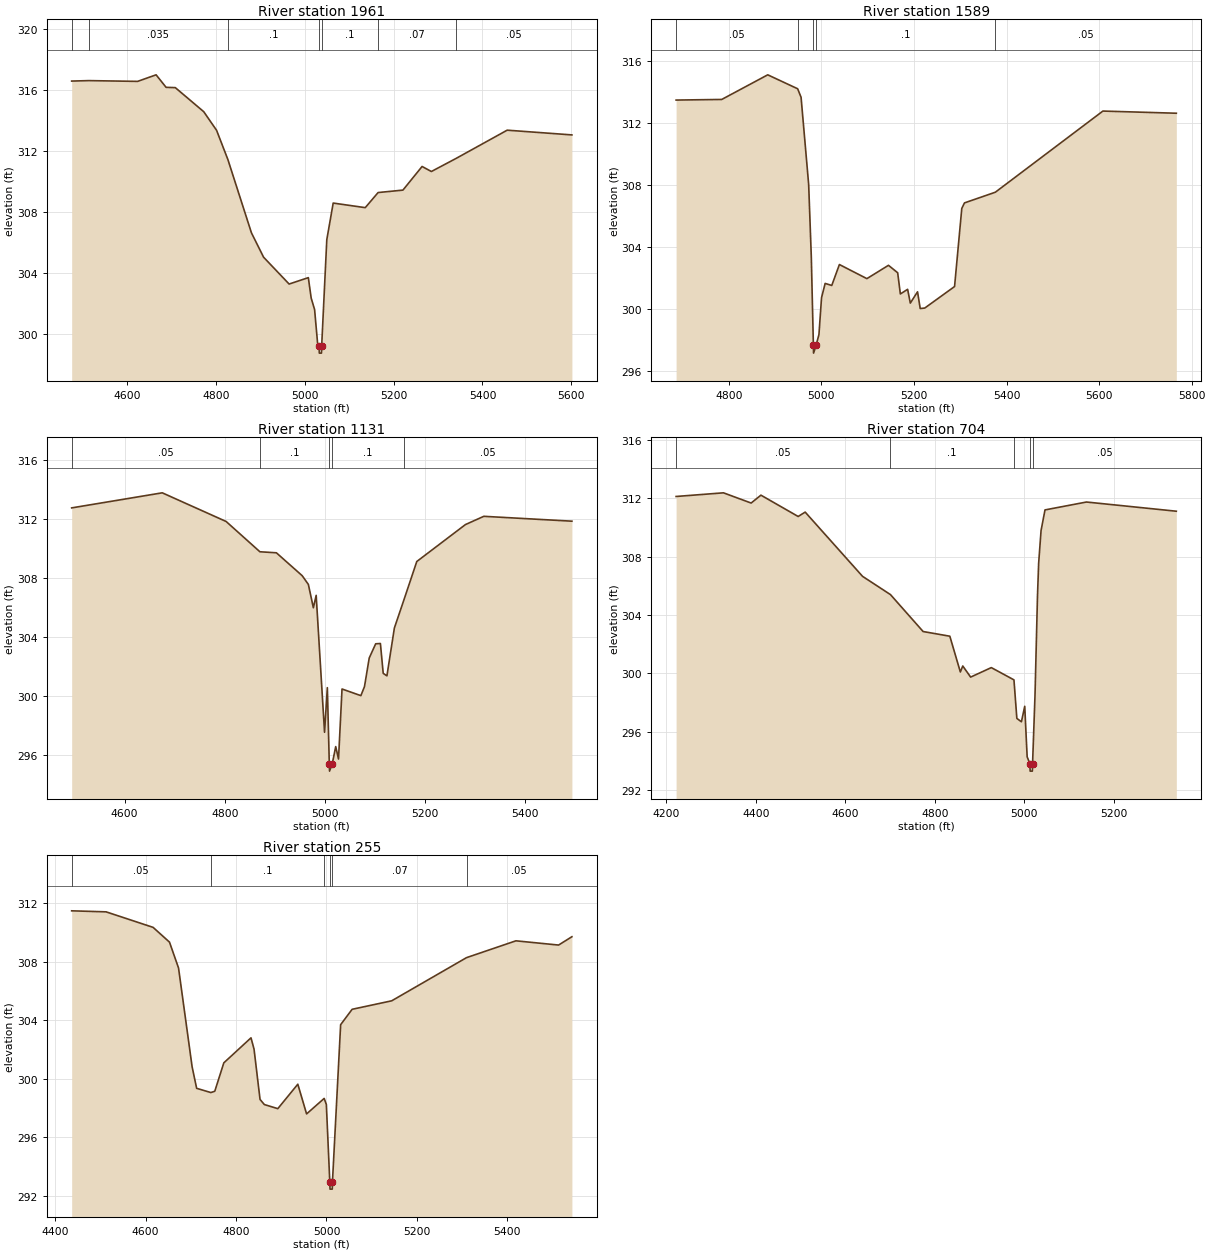
Type RM Length L Ch R = 1,1961,372,372,372
BEGIN DESCRIPTION:
E21066
END DESCRIPTION:
XS GIS Cut Line= 2
      2479414.44     13758723.79      2478714.13     13757840.79
#Sta/Elev= 30
  4474.5  316.58  4513.1  316.61  4623.1  316.56  4664.7  316.99  4687.2  316.17
  4708.0  316.15  4772.1  314.57  4801.0  313.35  4826.5  311.43  4879.5  306.63
  4906.9  305.03  4964.4  303.27  5007.7  303.69  5014.1  302.35  5021.8  301.60
  5028.5  299.40  5032.0  299.24  5032.4  298.74  5037.3  298.74  5037.8  299.24
  5049.3  306.18  5063.7  308.58  5135.9  308.28  5164.9  309.27  5220.8  309.43
  5264.0  310.98  5284.9  310.65  5340.7  311.51  5455.7  313.36  5601.5  313.05
#Mann=7,-1,0
  4474.5    0.05       0  4513.1   0.035       0  4826.5     0.1       0
  5032.0    0.05       0  5037.8     0.1       0  5164.9    0.07       0
  5340.7    0.05       0
Bank Sta=5032,5037.8
Exp/Cntr=0.3,0.1

Type RM Length L Ch R = 1,1589,458,458,458
BEGIN DESCRIPTION:
E21065
END DESCRIPTION:
XS GIS Cut Line= 3
      2479680.84     13758293.70      2479277.44     13758084.39
      2478738.45     13757765.55
#Sta/Elev= 30
  4686.2  313.50  4784.8  313.54  4884.2  315.13  4948.8  314.23  4956.2  313.68
  4972.6  308.05  4978.3  303.38  4982.8  297.66  4983.2  297.16  4988.6  297.66
  4994.8  298.36  5000.4  300.74  5008.2  301.66  5022.5  301.53  5039.0  302.88
  5098.4  301.97  5145.0  302.83  5164.9  302.35  5170.7  300.98  5186.4  301.28
  5192.2  300.39  5207.8  301.12  5213.6  300.04  5223.4  300.07  5287.8  301.46
  5303.4  306.50  5309.2  306.86  5375.9  307.55  5608.3  312.79  5766.9  312.65
#Mann=5,-1,0
  4686.2    0.05       0  4948.8     0.1       0  4982.8    0.05       0
  4988.6     0.1       0  5375.9    0.05       0
Bank Sta=4982.8,4988.6
Exp/Cntr=0.3,0.1

Type RM Length L Ch R = 1,1131,427,427,427
BEGIN DESCRIPTION:
E21064
END DESCRIPTION:
XS GIS Cut Line= 3
      2479715.12     13758179.52      2479433.49     13757840.80
      2478935.26     13757589.78
#Sta/Elev= 30
  4494.5  312.74  4675.3  313.76  4802.8  311.82  4870.2  309.77  4903.1  309.70
  4954.6  308.15  4966.9  307.56  4976.9  305.98  4982.5  306.82  4999.2  297.55
  5004.8  300.57  5008.7  295.42  5009.2  294.92  5014.6  295.42  5021.5  296.58
  5027.1  295.74  5034.1  300.48  5071.7  300.03  5078.9  300.64  5088.4  302.58
  5101.3  303.54  5110.7  303.56  5116.3  301.54  5123.7  301.37  5138.6  304.61
  5158.0  306.55  5183.3  309.11  5280.4  311.61  5317.1  312.17  5492.9  311.84
#Mann=5,-1,0
  4494.5    0.05       0  4870.2     0.1       0  5008.7    0.05       0
  5014.6     0.1       0  5158.0    0.05       0
Bank Sta=5008.7,5014.6
Exp/Cntr=0.3,0.1

Type RM Length L Ch R = 1,704,449,449,449
BEGIN DESCRIPTION:
E21063
END DESCRIPTION:
XS GIS Cut Line= 3
      2479753.18     13758137.63      2479410.65     13757384.06
      2479132.76     13757300.31
#Sta/Elev= 30
  4221.6  312.12  4327.4  312.37  4389.3  311.67  4411.2  312.21  4494.4  310.75
  4510.1  311.05  4638.3  306.65  4700.7  305.40  4773.7  302.87  4833.4  302.55
  4856.9  300.10  4862.3  300.51  4879.9  299.75  4926.1  300.40  4976.7  299.56
  4983.2  296.92  4993.4  296.69  5000.8  297.75  5006.2  294.29  5012.4  293.81
  5012.9  293.31  5017.8  293.31  5018.3  293.81  5023.8  298.55  5029.3  305.30
  5031.9  307.54  5037.3  309.79  5046.1  311.20  5138.8  311.74  5339.6  311.11
#Mann=5,-1,0
  4221.6    0.05       0  4700.7     0.1       0  4976.7    0.05       0
  5012.4    0.05       0  5018.3    0.05       0
Bank Sta=5012.4,5018.3
Exp/Cntr=0.3,0.1

Type RM Length L Ch R = 1,255,0,0,0
BEGIN DESCRIPTION:
E21062
END DESCRIPTION:
XS GIS Cut Line= 4
      2479817.90     13758031.07      2479798.87     13757601.01
      2479715.14     13757346.00      2479370.12     13757129.89
#Sta/Elev= 30
  4436.6  311.48  4512.7  311.41  4616.6  310.35  4652.9  309.34  4672.9  307.57
  4702.9  300.82  4712.9  299.35  4744.4  299.06  4753.0  299.15  4773.0  301.09
  4833.1  302.80  4839.8  302.03  4853.1  298.59  4862.6  298.24  4892.4  297.96
  4936.6  299.63  4956.0  297.60  4994.9  298.66  4999.7  298.24  5007.3  292.96
  5007.8  292.46  5012.7  292.46  5013.2  292.96  5031.3  303.70  5056.7  304.75
  5144.2  305.33  5309.6  308.28  5418.8  309.43  5513.2  309.14  5542.6  309.71
#Mann=6,-1,0
  4436.6    0.05       0  4744.4     0.1       0  4994.9    0.07       0
  5007.3    0.05       0  5013.2    0.07       0  5309.6    0.05       0
Bank Sta=5007.3,5013.2
Exp/Cntr=0.3,0.1

Chan Stop Cuts=-1