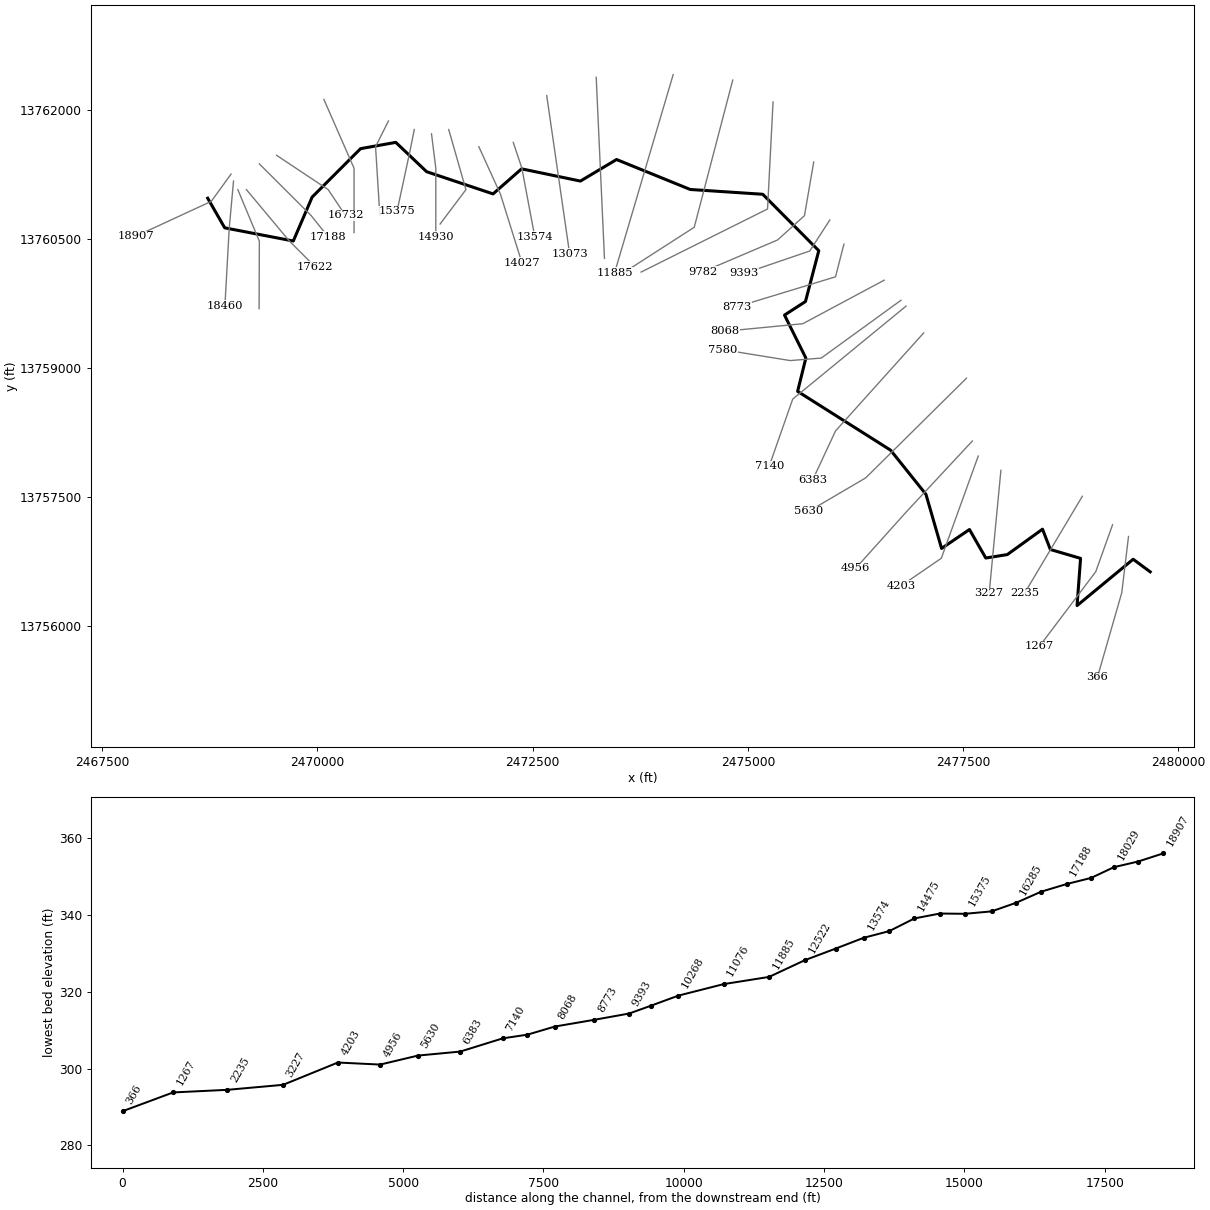
--- Stream0475.prj (project) ---

Proj Title=Stream0475 Base Level Engineering
Current Plan=p01
Default Exp/Contr=0.3,0.1
English Units
Geom File=g01
Flow File=f01
Plan File=p01
Y Axis Title=Elevation
X Axis Title(PF)=Main Channel Distance
X Axis Title(XS)=Station
BEGIN DESCRIPTION:
Stream0475
END DESCRIPTION:
DSS Export Rating Curves= 0
DSS Export Rating Curve Sorted= 0
DSS Export Volume Flow Curves= 0
DXF OffsetX= 0
DXF OffsetY= 0
DXF ScaleX= 1
DXF ScaleY= 10

--- Stream0475.p01 (plan) ---

Plan Title=Multiple Run
Short Identifier=Multiple
Geom File=g01
Flow File=f01
Subcritical Flow
K Sum by GR= 0
Std Step Tol= 0.01
Critical Tol= 0.01
Num of Std Step Trials= 20
Max Error Tol= 0.3
Flow Tol Ratio= 0.001
Split Flow NTrial= 30
Split Flow Tol= 0.02
Split Flow Ratio= 0.02
Log Output Level= 0
Friction Slope Method= 1
Unsteady Friction Slope Method= 2
Unsteady Bridges Friction Slope Method= 1
Parabolic Critical Depth
Global Vel Dist=  1 , 1 , 1
Global Log Level= 0
CheckData=True
Encroach Param= -1, 0, 0, 0
BEGIN DESCRIPTION:
Multiple Run
END DESCRIPTION:

--- Stream0475.f01 (steady flow) ---

Flow Title=Multiple
Number of Profiles=7
Profile Names=10-year,25-year,50-year,1pct_min,100-year,1pct_plu,500-year
River Rch & RM= Stream0475,Reach-1,18907
     723    1170    1574    1026    2047    4083    3426
River Rch & RM= Stream0475,Reach-1,16285
     954    1557    2107    1379    2751    5490    4647
River Rch & RM= Stream0475,Reach-1,7140
    1295    2145    2933    1937    3864    7710    6646
River Rch & RM= Stream0475,Reach-1,4956
    1390    2305    3154    2083    4156    8291    7151
Boundary for River Rch & Prof#=Stream0475,Reach-1,1
Up Type=0
Dn Type=3
Dn Slope=0.005
Boundary for River Rch & Prof#=Stream0475,Reach-1,2
Up Type=0
Dn Type=3
Dn Slope=0.005
Boundary for River Rch & Prof#=Stream0475,Reach-1,3
Up Type=0
Dn Type=3
Dn Slope=0.005
Boundary for River Rch & Prof#=Stream0475,Reach-1,4
Up Type=0
Dn Type=3
Dn Slope=0.005
Boundary for River Rch & Prof#=Stream0475,Reach-1,5
Up Type=0
Dn Type=3
Dn Slope=0.005
Boundary for River Rch & Prof#=Stream0475,Reach-1,6
Up Type=0
Dn Type=3
Dn Slope=0.005
Boundary for River Rch & Prof#=Stream0475,Reach-1,7
Up Type=0
Dn Type=3
Dn Slope=0.005

--- Stream0475.g01 (geometry) ---

Geom Title=Existing Conditions
Program Version=4.10

River Reach=Stream0475      ,Reach-1
Reach XY= 30
        2468725.       13760975.      2468922.57      13760630.4
      2469719.32     13760476.99       2469938.5     13760988.69
      2470500.97     13761552.35      2470909.84     13761625.47
      2471268.25     13761284.14      2472040.22     13761025.49
      2472371.58     13761317.21       2473054.9      13761174.9
      2473474.96     13761425.86      2474330.86     13761077.07
      2475173.44     13761021.24       2475824.4     13760364.39
      2475669.58     13759772.25      2475426.19      13759614.5
       2475674.4     13759114.38      2475578.38      13758726.4
      2476658.58      13758041.8      2477069.52     13757527.44
       2477251.1     13756897.68      2477574.98     13757117.93
      2477764.56     13756785.94      2478014.56     13756826.06
      2478423.75     13757121.65      2478514.82     13756885.32
      2478865.88     13756781.76      2478824.98     13756232.08
      2479476.73     13756771.69        2479675.       13756625.

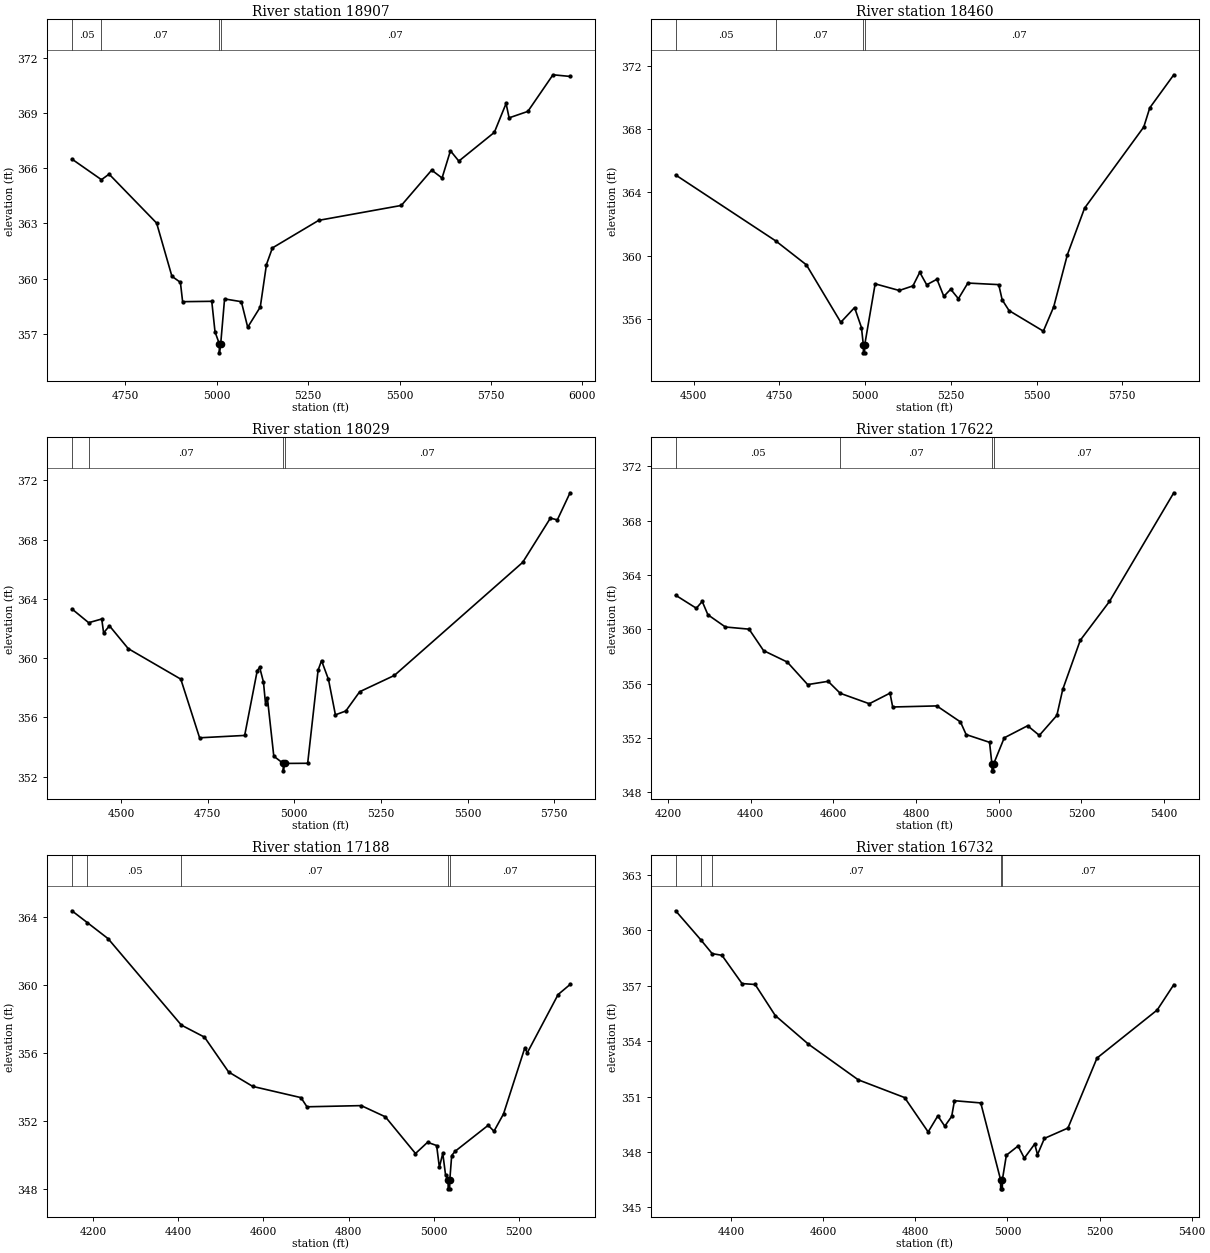
Type RM Length L Ch R = 1 ,18907   ,447,447,447
BEGIN DESCRIPTION:
Stream0475 40.0
END DESCRIPTION:
XS GIS Cut Line= 3
      2468996.68      13761256.7      2468766.83     13760939.05
      2467886.25     13760531.04
#Sta/Elev= 30
  4603.6   366.5  4684.4  365.38  4705.4  365.68  4835.4  363.02  4877.2  360.13
  4900.4   359.8  4906.5  358.75  4986.2  358.77  4995.1  357.11  5006.7  356.47
    5007  355.97  5010.7  356.47  5021.2   358.9  5067.1  358.75  5084.5  357.36
  5118.9  358.46  5135.8  360.77    5152  361.67  5278.8  363.17  5504.7  363.98
  5587.7   365.9  5616.1  365.47    5639  366.95    5662  366.39  5759.1  367.95
  5791.2  369.52  5799.5  368.74  5850.8  369.09  5919.5  371.08  5966.2  370.99
#Mann= 4 ,-1 , 0
  4603.6     .05       0  4684.4     .07       0  5006.7     .05       0
  5010.7     .07       0
Bank Sta=5006.7,5010.7
XS Rating Curve= 0 ,0
Exp/Cntr=0.3,0.1

Type RM Length L Ch R = 1 ,18460   ,431,431,431
BEGIN DESCRIPTION:
Stream0475 39.0
END DESCRIPTION:
XS GIS Cut Line= 3
        2469025.     13761175.03        2468975.       13760625.
        2468925.     13759724.99
#Sta/Elev= 30
  4446.9   365.1  4739.2  360.93  4828.5  359.42  4928.9  355.79  4969.1  356.72
  4989.2  355.46  4994.7  354.36  4994.9  353.86  4998.4  353.86  4998.7  354.36
  5029.2  358.22  5099.4   357.8  5139.4  358.09  5159.4  358.95  5179.5  358.16
  5209.5  358.51  5229.6  357.43  5249.6  357.88  5272.1  357.28  5299.7  358.27
  5389.8  358.17  5399.8  357.21  5419.9  356.53    5520  355.23  5550.1  356.76
  5590.1  360.06  5640.2     363    5813  368.13  5830.5  369.34  5900.6  371.43
#Mann= 4 ,-1 , 0
  4446.9     .05       0  4739.2     .07       0  4994.7     .05       0
  4998.7     .07       0
Bank Sta=4994.7,4998.7
XS Rating Curve= 0 ,0
Exp/Cntr=0.3,0.1

Type RM Length L Ch R = 1 ,18029   ,407,407,407
BEGIN DESCRIPTION:
Stream0475 38.0
END DESCRIPTION:
XS GIS Cut Line= 3
      2469075.01     13761074.97        2469325.       13760475.
      2469322.03     13759688.27
#Sta/Elev= 30
  4358.7  363.32  4407.1  362.39  4444.8  362.64  4450.2   361.7    4467  362.18
  4521.2  360.64  4672.8  358.58    4727  354.62    4857  354.78  4893.3  359.16
  4900.3  359.37  4911.2  358.38  4917.1  356.93  4922.5  357.31    4941  353.38
  4968.2  352.89  4968.5  352.39  4972.2  352.89  5038.7   352.9  5068.7  359.18
  5078.7  359.83  5098.7  358.56  5118.7  356.17  5148.7  356.43  5188.7  357.73
  5288.7  358.83  5658.7  366.46  5738.7  369.45  5758.7  369.33  5795.4  371.16
#Mann= 4 ,-1 , 0
  4358.7     .05       0  4407.1     .07       0  4968.2     .05       0
  4972.2     .07       0
Bank Sta=4968.2,4972.2
XS Rating Curve= 0 ,0
Exp/Cntr=0.3,0.1

Type RM Length L Ch R = 1 ,17622   ,434,434,434
BEGIN DESCRIPTION:
Stream0475 37.0
END DESCRIPTION:
XS GIS Cut Line= 3
      2469175.02     13761074.98        2469675.       13760475.
      2469975.03     13760174.97
#Sta/Elev= 30
  4218.3  362.52  4268.4  361.56  4282.7  362.06  4296.4  361.08  4338.7  360.18
    4396  360.02  4431.1  358.44  4488.4   357.6  4537.8  355.94  4587.3  356.18
  4616.5   355.3  4686.9  354.53    4737  355.31  4743.5  354.29  4850.2  354.37
  4907.5  353.19  4921.2  352.26  4977.8  351.69  4983.6  350.09  4983.9  349.59
  4987.4  349.59  4987.6  350.09  5013.4  352.02    5070  352.91  5098.3   352.2
  5140.7  353.67  5154.9  355.58  5197.3   359.2    5268  362.06  5423.6  370.06
#Mann= 4 ,-1 , 0
  4218.3     .05       0  4616.5     .07       0  4983.6     .05       0
  4987.6     .07       0
Bank Sta=4983.6,4987.6
XS Rating Curve= 0 ,0
Exp/Cntr=0.3,0.1

Type RM Length L Ch R = 1 ,17188   ,456,456,456
BEGIN DESCRIPTION:
Stream0475 36.0
END DESCRIPTION:
XS GIS Cut Line= 3
        2469325.       13761375.        2469925.       13760775.
      2470125.01     13760524.99
#Sta/Elev= 30
  4150.9  364.38  4187.3  363.68  4235.8  362.74  4407.7  357.65    4462  356.94
  4518.6  354.89  4575.2  354.04  4688.3  353.38  4702.4  352.84  4829.7  352.91
  4886.3  352.25    4957  350.09  4985.3  350.75  5006.6  350.56    5013  349.28
    5021   350.1  5027.4  348.85  5033.4  348.51  5033.7  348.01  5037.2  348.01
  5037.4  348.51  5041.9  349.97  5049.9  350.22  5127.5  351.75  5141.1   351.4
  5163.5  352.42  5213.1  356.28  5219.5  356.03  5291.6  359.45  5319.6  360.04
#Mann= 5 ,-1 , 0
  4150.9     .07       0  4187.3     .05       0  4407.7     .07       0
  5033.4     .05       0  5037.4     .07       0
Bank Sta=5033.4,5037.4
XS Rating Curve= 0 ,0
Exp/Cntr=0.3,0.1

Type RM Length L Ch R = 1 ,16732   ,447,447,447
BEGIN DESCRIPTION:
Stream0475 35.0
END DESCRIPTION:
XS GIS Cut Line= 3
      2469525.04     13761474.98        2470125.       13761075.
      2470324.99     13760775.02
#Sta/Elev= 30
  4279.5  361.06  4333.8   359.5  4358.9  358.74  4380.1  358.65  4423.7  357.12
  4452.2  357.07  4495.8  355.39  4567.9  353.84  4676.1  351.91  4776.7  350.95
  4827.8  349.09  4848.8  349.96  4863.9   349.4  4878.9  349.93  4884.9  350.78
    4942  350.66    4985  346.51  4985.3  346.01  4988.8  346.01    4989  346.51
  4997.6  347.83  5023.1  348.33  5036.6  347.67  5059.2  348.44  5065.2  347.86
  5080.2  348.74  5131.3   349.3  5194.4  353.09  5325.1  355.69  5361.1  357.06
#Mann= 5 ,-1 , 0
  4279.5     .07       0  4333.8     .05       0  4358.9     .07       0
    4985     .05       0    4989     .07       0
Bank Sta=4985,4989
XS Rating Curve= 0 ,0
Exp/Cntr=0.3,0.1

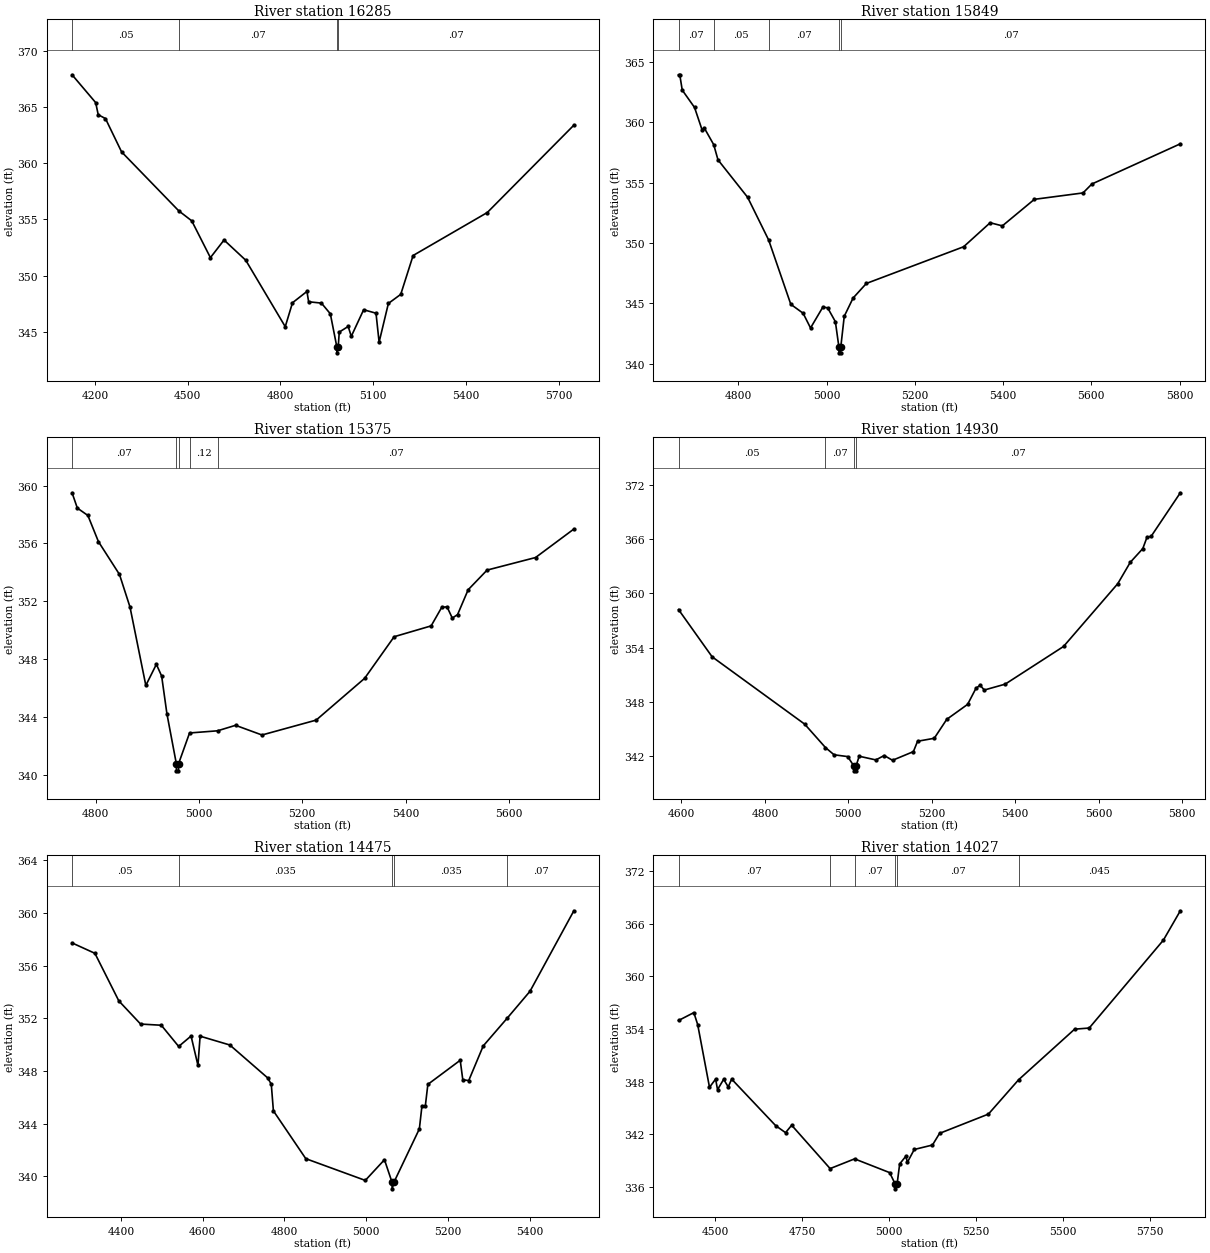
Type RM Length L Ch R = 1 ,16285   ,436,436,436
BEGIN DESCRIPTION:
Stream0475 34.0
END DESCRIPTION:
XS GIS Cut Line= 3
      2470074.99     13762125.01        2470425.       13761325.
        2470425.     13760575.03
#Sta/Elev= 30
  4126.4  367.89  4202.8  365.41    4211  364.33  4234.4  363.99  4286.6  361.02
  4471.5  355.77  4513.5  354.88  4573.9   351.6    4618  353.17  4688.2  351.37
    4816  345.45  4839.4  347.58  4886.2  348.59  4891.6  347.67    4933  347.55
  4961.8   346.6  4983.1  343.62  4983.4  343.12  4987.3  343.62  4990.7  344.97
  5019.6  345.47  5029.6  344.59  5069.6  346.96  5109.6  346.65  5119.6  344.07
  5149.6  347.52  5189.6  348.33  5229.6  351.79  5469.6  355.62  5749.6   363.4
#Mann= 4 ,-1 , 0
  4126.4     .05       0  4471.5     .07       0  4983.1     .05       0
  4987.3     .07       0
Bank Sta=4983.1,4987.3
XS Rating Curve= 0 ,0
Exp/Cntr=0.3,0.1

Type RM Length L Ch R = 1 ,15849   ,474,474,474
BEGIN DESCRIPTION:
Stream0475 33.0
END DESCRIPTION:
XS GIS Cut Line= 3
        2470825.       13761875.        2470675.       13761575.
        2470725.     13760774.97
#Sta/Elev= 30
  4664.6  363.93  4667.4  363.93    4673  362.66  4700.9  361.22  4717.7  359.39
  4723.3   359.5  4744.3  358.14    4754  356.88  4821.1  353.78  4868.8  350.24
    4919  344.91  4946.9  344.17  4963.7  342.95  4991.6  344.68  5002.5  344.62
    5020  343.47  5027.9  341.39  5028.2  340.89    5032  340.89  5032.3  341.39
  5040.1  343.92  5060.1  345.43  5090.2  346.64  5310.6  349.68  5370.7  351.67
  5398.3  351.41  5470.9  353.61  5581.1  354.14  5601.2  354.88  5801.6  358.21
#Mann= 5 ,-1 , 0
  4664.6     .07       0  4744.3     .05       0  4868.8     .07       0
  5027.9     .05       0  5032.3     .07       0
Bank Sta=5027.9,5032.3
XS Rating Curve= 0 ,0
Exp/Cntr=0.3,0.1

Type RM Length L Ch R = 1 ,15375   ,445,445,445
BEGIN DESCRIPTION:
Stream0475 32.0
END DESCRIPTION:
XS GIS Cut Line= 3
      2471124.99     13761774.97        2471075.       13761525.
        2470925.     13760825.01
#Sta/Elev= 30
  4754.6   359.5  4764.8  358.44  4785.2  357.93  4805.6  356.12  4846.3  353.85
  4866.7  351.59  4897.3  346.17  4917.7  347.63  4927.9  346.82  4938.1  344.21
  4956.3  340.76  4956.6  340.26  4960.4  340.26  4960.7  340.76  4981.9  342.88
  5036.1  343.03  5070.9  343.41    5122  342.74  5226.8  343.77  5320.6  346.66
  5377.7  349.54  5449.3  350.29  5469.7  351.57    5480  351.61  5490.2  350.83
  5500.4  351.07  5520.9  352.79  5557.5  354.15  5651.3  355.02  5725.4  356.99
#Mann= 5 ,-1 , 0
  4754.6     .07       0  4956.3     .05       0  4960.7     .07       0
  4981.9     .12       0  5036.1     .07       0
Bank Sta=4956.3,4960.7
XS Rating Curve= 0 ,0
Exp/Cntr=0.3,0.1

Type RM Length L Ch R = 1 ,14930   ,455,455,455
BEGIN DESCRIPTION:
Stream0475 31.0
END DESCRIPTION:
XS GIS Cut Line= 3
        2471325.     13761725.02        2471375.       13761325.
        2471375.     13760525.03
#Sta/Elev= 30
  4592.9  358.21  4673.5  352.97  4895.3  345.51  4945.2  342.91  4965.8  342.11
  4998.5  341.91  5013.8  340.83  5014.1  340.33    5018  340.33  5018.3  340.83
    5026  341.95    5066  341.54    5086  342.03    5106   341.5    5156  342.46
    5166  343.61    5206  343.94    5236  346.04    5286   347.7    5306  349.48
    5316  349.82    5326  349.29    5376  349.94    5516  354.12    5646  361.08
    5676  363.45    5706  364.97    5716  366.22    5726  366.33    5796  371.16
#Mann= 4 ,-1 , 0
  4592.9     .05       0  4945.2     .07       0  5013.8     .05       0
  5018.3     .07       0
Bank Sta=5013.8,5018.3
XS Rating Curve= 0 ,0
Exp/Cntr=0.3,0.1

Type RM Length L Ch R = 1 ,14475   ,448,448,448
BEGIN DESCRIPTION:
Stream0475 30.0
END DESCRIPTION:
XS GIS Cut Line= 3
      2471524.99     13761775.02        2471725.       13761075.
      2471425.02     13760675.03
#Sta/Elev= 30
  4280.2  357.73  4336.1  356.94  4394.6  353.33  4447.9  351.57  4498.6  351.48
  4541.1  349.87  4571.4  350.66  4588.3  348.43  4593.5  350.65  4666.3  349.98
  4758.6  347.49  4767.7  347.01  4772.9  344.98  4852.2  341.35  4997.8   339.7
  5044.7  341.27  5063.2  339.56  5063.5  339.06  5067.9  339.56  5130.1  343.61
  5136.4  345.34  5144.7  345.35  5150.9  346.99  5230.1  348.82  5236.4  347.34
  5250.9  347.28  5286.4  349.91  5344.9  352.01  5400.9  354.06  5508.2  360.17
#Mann= 5 ,-1 , 0
  4280.2     .05       0  4541.1    .035       0  5063.2    .035       0
  5067.9    .035       0  5344.9     .07       0
Bank Sta=5063.2,5067.9
XS Rating Curve= 0 ,0
Exp/Cntr=0.3,0.1

Type RM Length L Ch R = 1 ,14027   ,453,453,453
BEGIN DESCRIPTION:
Stream0475 29.0
END DESCRIPTION:
XS GIS Cut Line= 3
      2471874.98     13761575.03        2472125.       13761025.
      2472374.99     13760225.04
#Sta/Elev= 30
  4395.3  354.97  4439.3  355.87  4450.3  354.51  4484.3  347.35  4501.9  348.28
  4507.4  347.08    4525  348.26  4538.1  347.39    4548  348.28  4674.3  342.98
  4702.9  342.17  4720.5  343.02    4831  338.07  4901.3  339.18  5002.1  337.61
  5018.6  336.26  5018.9  335.76  5023.4  336.26  5030.9   338.6  5048.2  339.46
  5053.4  338.81  5072.8  340.25  5125.2  340.76  5145.6  342.09    5286  344.29
  5372.6   348.2  5533.8  353.98  5575.7  354.11  5788.9  364.14  5837.6  367.49
#Mann= 6 ,-1 , 0
  4395.3     .07       0    4831     .05       0  4901.3     .07       0
  5018.6     .05       0  5023.4     .07       0  5372.6    .045       0
Bank Sta=5018.6,5023.4
XS Rating Curve= 0 ,0
Exp/Cntr=0.3,0.1

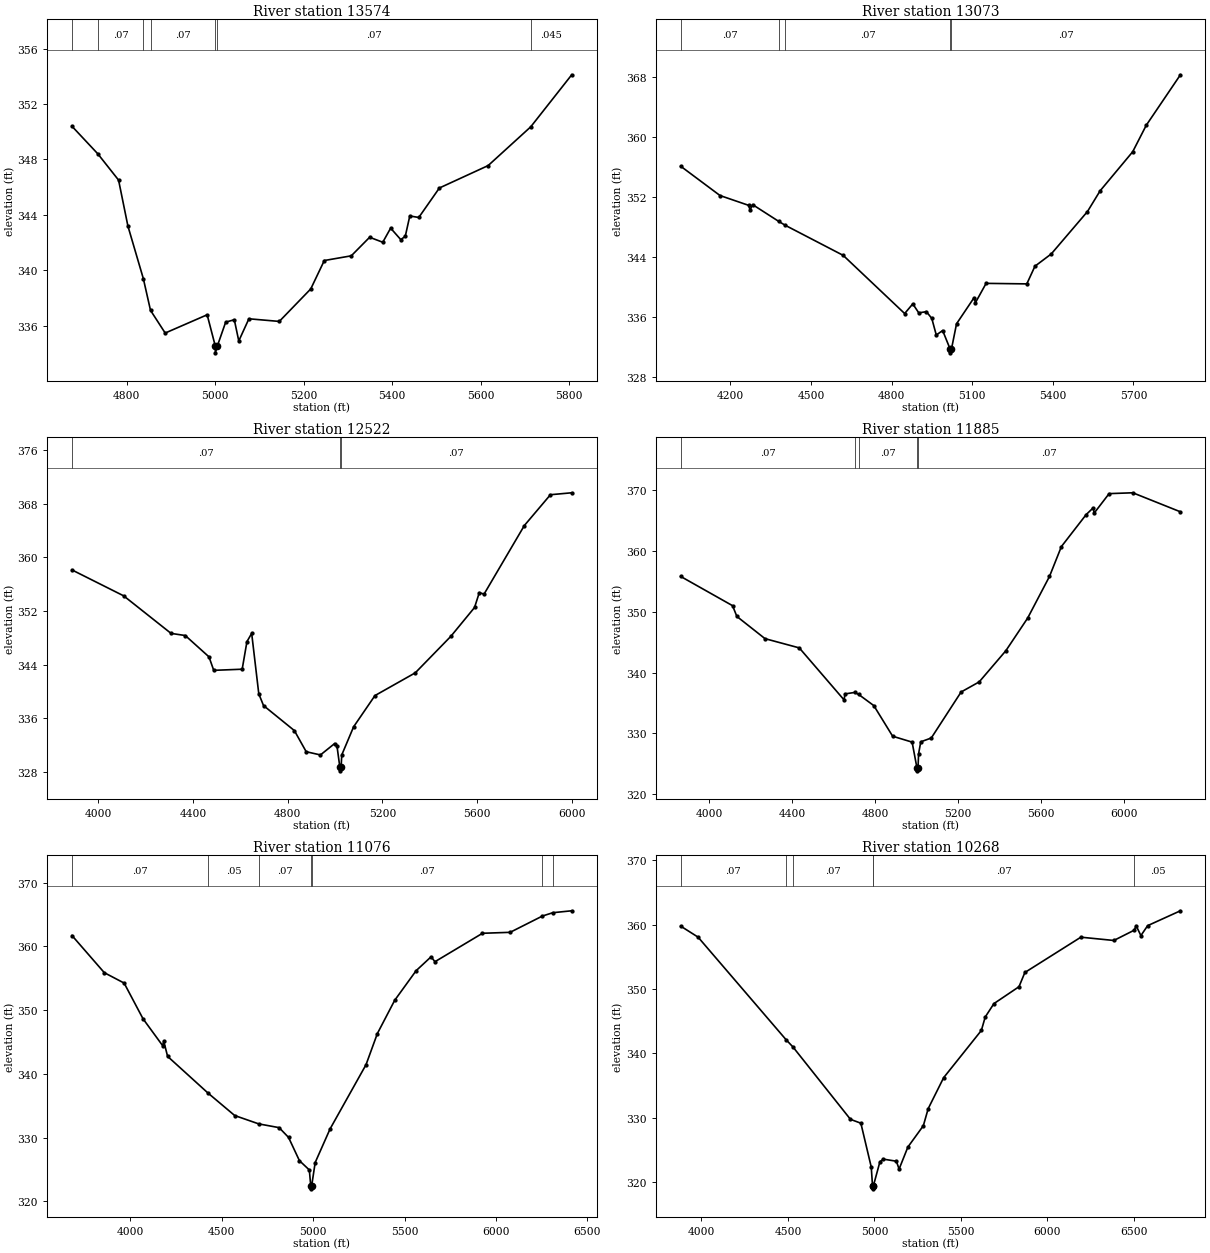
Type RM Length L Ch R = 1 ,13574   ,501,501,501
BEGIN DESCRIPTION:
Stream0475 28.0
END DESCRIPTION:
XS GIS Cut Line= 3
      2472275.01     13761624.97        2472375.       13761325.
      2472524.99     13760525.04
#Sta/Elev= 30
  4676.1   350.4  4734.5  348.41  4781.5  346.51  4802.6  343.19  4837.5  339.39
  4853.7   337.1  4886.9  335.46  4981.8  336.78  5000.1  334.53  5000.4  334.03
  5004.9  334.53  5023.7  336.25  5043.2  336.42  5053.3  334.89  5076.2  336.49
  5144.9   336.3  5216.1  338.65  5246.7   340.7  5307.7  341.04  5349.2  342.38
  5378.9  342.02  5396.7  343.04  5419.6  342.21  5429.8  342.45    5440  343.92
  5460.3  343.81  5506.9  345.94  5617.2  347.56  5713.5  350.36  5806.2  354.12
#Mann= 7 ,-1 , 0
  4676.1     .05       0  4734.5     .07       0  4837.5     .05       0
  4853.7     .07       0  5000.1     .05       0  5004.9     .07       0
  5713.5    .045       0
Bank Sta=5000.1,5004.9
XS Rating Curve= 0 ,0
Exp/Cntr=0.3,0.1

Type RM Length L Ch R = 1 ,13073   ,551,551,551
BEGIN DESCRIPTION:
XS6904
END DESCRIPTION:
XS GIS Cut Line= 2
      2472663.71     13762169.98      2472929.72      13760329.2
#Sta/Elev= 30
  4015.1  356.15  4161.6  352.23  4268.2  350.92  4273.3   350.3  4282.8  351.02
    4380  348.78  4403.6  348.27  4619.9  344.24  4848.7  336.47    4879  337.76
  4901.2  336.56  4929.5  336.72  4949.7  335.82  4966.4   333.6  4990.1   334.2
    5018  331.72  5018.4  331.22  5022.9  331.72  5041.8   335.1  5107.1  338.59
  5112.1  337.92  5151.8   340.5  5303.3  340.43  5333.6  342.79  5394.3  344.43
    5529  350.09  5576.1  352.86  5697.4  358.08  5747.9  361.62    5875  368.36
#Mann= 5 ,-1 , 0
  4015.1     .07       0    4380     .05       0  4403.6     .07       0
    5018     .05       0  5022.9     .07       0
Bank Sta=5018,5022.9
XS Rating Curve= 0 ,0
Exp/Cntr=0.3,0.1

Type RM Length L Ch R = 1 ,12522   ,637,637,637
BEGIN DESCRIPTION:
XS6903
END DESCRIPTION:
XS GIS Cut Line= 2
      2473238.55      13762382.9      2473334.35     13760275.17
#Sta/Elev= 30
  3889.7  358.14  4107.8  354.28    4308  348.68  4368.1  348.36  4468.2  345.18
  4488.2  343.17  4608.3  343.34  4628.4  347.45  4648.4  348.68  4678.4  339.67
  4698.4  337.92  4828.6  334.19  4878.6  331.04  4938.7  330.56  4998.7  332.26
  5008.7  331.85  5020.8  328.69  5021.1  328.19  5025.8  328.69  5028.8  330.57
  5078.8  334.76  5168.9  339.41  5339.1   342.8  5489.2  348.24  5589.3  352.54
  5609.4  354.76  5629.4  354.53  5799.6  364.76  5909.7  369.35  5999.6  369.64
#Mann= 3 ,-1 , 0
  3889.7     .07       0  5020.8     .05       0  5025.8     .07       0
Bank Sta=5020.8,5025.8
XS Rating Curve= 0 ,0
Exp/Cntr=0.3,0.1

Type RM Length L Ch R = 1 ,11885   ,809,809,809
BEGIN DESCRIPTION:
XS6902
END DESCRIPTION:
XS GIS Cut Line= 2
      2474132.75     13762414.86      2473451.45     13760104.83
#Sta/Elev= 30
  3863.3   355.8  4113.4  350.99  4134.2  349.22  4269.8  345.57    4435  344.05
  4650.5  335.51  4655.7  336.49  4702.3  336.73  4721.4  336.39  4794.2  334.56
  4884.9  329.53  4978.7  328.56  5001.9  324.34  5002.3  323.84  5007.1  324.34
    5010  326.67  5020.4  328.61  5071.1  329.24  5214.8   336.8  5301.9  338.46
  5430.3  343.58  5535.5  348.95  5640.6  355.79  5698.1  360.71  5817.6  365.97
    5851  367.06  5856.2  366.22    5928  369.41  6042.2  369.55  6271.7  366.42
#Mann= 5 ,-1 , 0
  3863.3     .07       0  4702.3     .12       0  4721.4     .07       0
  5001.9     .05       0  5007.1     .07       0
Bank Sta=5001.9,5007.1
XS Rating Curve= 0 ,0
Exp/Cntr=0.3,0.1

Type RM Length L Ch R = 1 ,11076   ,808,808,808
BEGIN DESCRIPTION:
XS6901
END DESCRIPTION:
XS GIS Cut Line= 3
      2474824.67     13762350.92      2474377.58      13760637.1
      2473569.29     13760115.96
#Sta/Elev= 30
  3681.4  361.71  3858.2  355.88  3966.6  354.25  4069.9  348.65  4176.8  344.45
  4183.6   345.1  4204.3  342.75  4425.5  336.99  4571.3  333.47  4702.6  332.16
  4814.2  331.57  4865.7  330.04  4925.2  326.39  4979.4  324.93    4987  322.47
  4987.4  321.97  4992.3  322.47  5011.4   326.1    5093  331.38  5289.5  341.45
  5351.4  346.33  5446.3  351.55  5563.3  356.19  5645.1  358.37  5666.3   357.6
  5926.3  362.06  6077.5  362.21  6254.3  364.77  6311.3  365.29  6414.3  365.59
#Mann= 7 ,-1 , 0
  3681.4     .07       0  4425.5     .05       0  4702.6     .07       0
    4987     .05       0  4992.3     .07       0  6254.3     .05       0
  6311.3     .07       0
Bank Sta=4987,4992.3
XS Rating Curve= 0 ,0
Exp/Cntr=0.3,0.1

Type RM Length L Ch R = 1 ,10268   ,486,486,486
BEGIN DESCRIPTION:
XS6900
END DESCRIPTION:
XS GIS Cut Line= 3
      2475293.07      13762095.5      2475229.19       13760850.
      2473760.13     13760115.47
#Sta/Elev= 30
  3879.7  359.76  3980.3  358.05  4489.9   342.1  4528.9     341  4861.5  329.76
  4921.6  329.16  4981.7  322.35  4988.9  319.47  4989.4  318.97  4994.4  319.47
  5031.7  323.17  5051.7  323.58  5126.8  323.26  5142.7  322.04  5193.5  325.46
  5282.9  328.77  5310.9  331.42  5400.3  336.23  5618.3  343.56  5640.7  345.65
    5691  347.73  5835.9  350.35  5869.9  352.56  6193.7  358.04  6384.2  357.53
  6503.2  359.14  6512.8  359.84  6540.7  358.29  6579.8  359.83  6769.3  362.14
#Mann= 6 ,-1 , 0
  3879.7     .07       0  4489.9     .05       0  4528.9     .07       0
  4988.9     .05       0  4994.4     .07       0  6503.2     .05       0
Bank Sta=4988.9,4994.4
XS Rating Curve= 0 ,0
Exp/Cntr=0.3,0.1

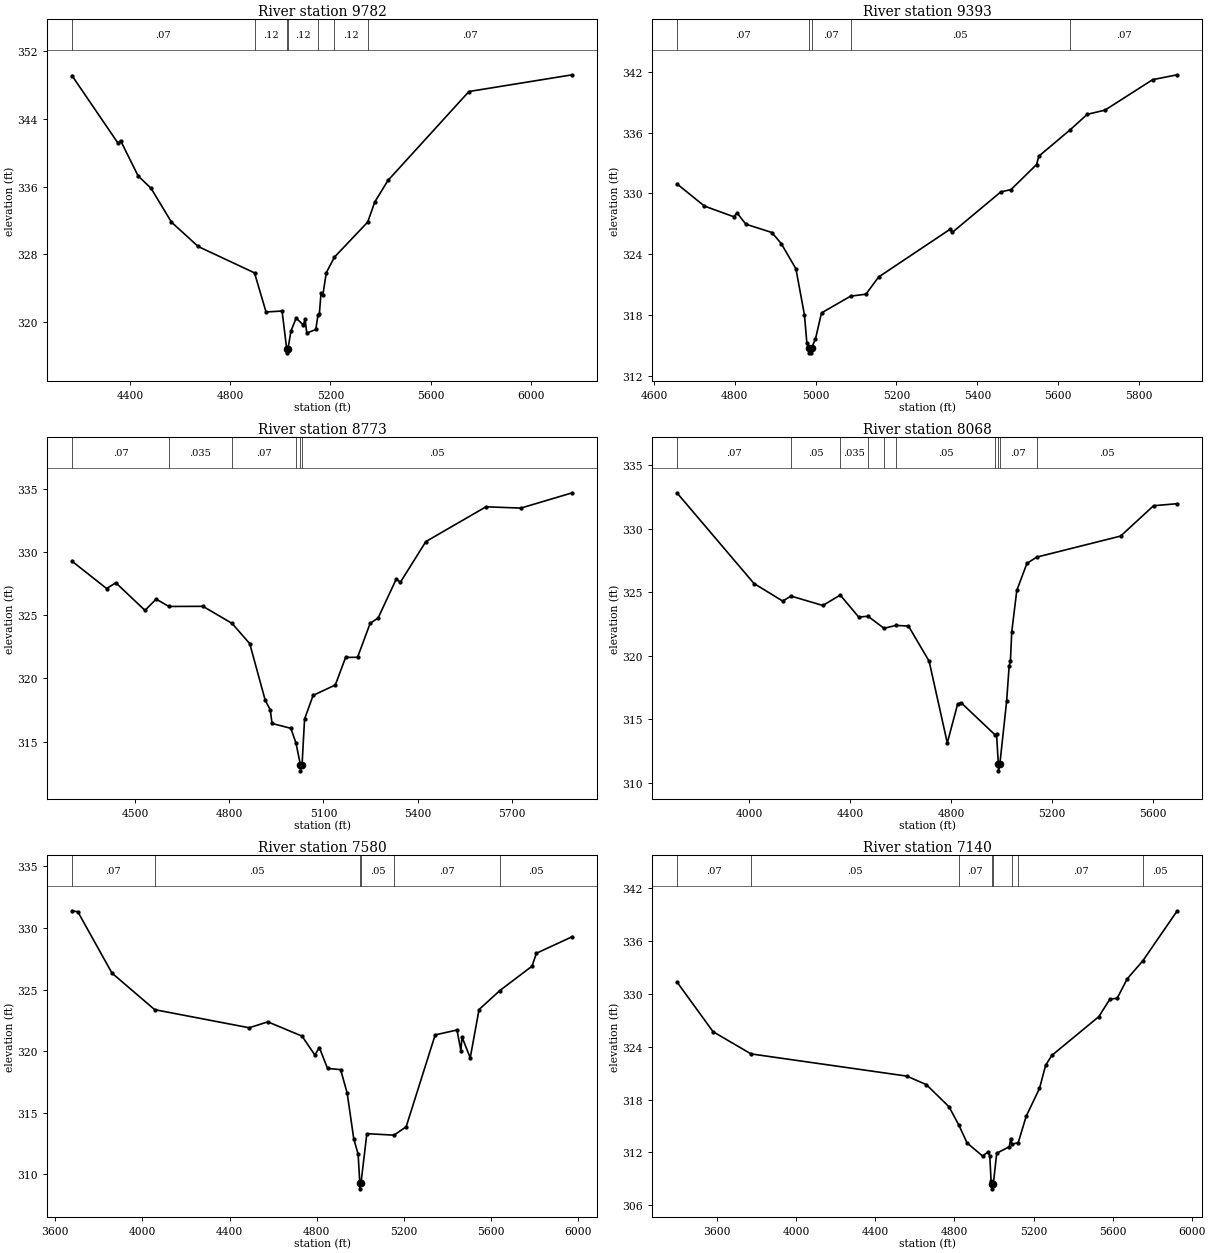
Type RM Length L Ch R = 1 ,9782    ,389,389,389
BEGIN DESCRIPTION:
E21092
END DESCRIPTION:
XS GIS Cut Line= 4
      2475765.37     13761396.36      2475658.08     13760772.15
      2475345.98     13760489.31      2474477.95     13760118.69
#Sta/Elev= 30
    4168  349.12    4352  341.13  4362.2  341.43    4432  337.27  4483.9   335.8
  4565.1  331.81  4671.8  328.93    4897  325.81  4942.9  321.19  5007.1   321.3
  5025.3  316.86  5025.7  316.36  5030.8  316.86  5042.3  318.92  5063.2  320.46
  5091.6  319.66    5099  320.32  5105.8  318.69  5141.6  319.12  5150.5  320.81
  5155.8   320.9  5162.6  323.42  5169.9  323.17  5183.5  325.82  5216.2  327.67
  5349.2  331.82  5377.4   334.2  5430.2  336.74  5753.3  347.24  6166.4  349.22
#Mann= 7 ,-1 , 0
    4168     .07       0    4897     .12       0  5025.3     .05       0
  5030.8     .12       0  5150.5     .07       0  5216.2     .12       0
  5349.2     .07       0
Bank Sta=5025.3,5030.8
XS Rating Curve= 0 ,0
Exp/Cntr=0.3,0.1

Type RM Length L Ch R = 1 ,9393    ,620,620,620
BEGIN DESCRIPTION:
XS6899
END DESCRIPTION:
XS GIS Cut Line= 3
      2475953.07     13760722.27      2475718.87     13760360.32
      2474955.83     13760099.18
#Sta/Elev= 30
  4656.9  330.95  4725.1  328.76    4797  327.72  4806.2  328.07  4827.3  326.98
  4891.9  326.16    4915  325.07  4951.3  322.59  4972.4  318.05  4978.3  315.32
  4984.4  314.82  4984.8  314.32  4989.5  314.32    4990  314.82  4999.5  315.66
  5014.6  318.25  5086.7   319.9  5124.5  320.09  5155.8  321.78    5333  326.49
  5338.3  326.18  5458.2  330.16  5483.2  330.38  5546.6  332.85  5552.1  333.67
  5628.6  336.23    5672  337.79  5715.7   338.2  5833.7   341.2  5894.5  341.68
#Mann= 5 ,-1 , 0
  4656.9     .07       0  4984.4     .05       0    4990     .07       0
  5086.7     .05       0  5628.6     .07       0
Bank Sta=4984.4,4990
XS Rating Curve= 0 ,0
Exp/Cntr=0.3,0.1

Type RM Length L Ch R = 1 ,8773    ,705,705,705
BEGIN DESCRIPTION:
XS6898
END DESCRIPTION:
XS GIS Cut Line= 3
      2476116.46     13760440.51      2476018.94     13760060.18
      2474868.05     13759709.06
#Sta/Elev= 30
    4298  329.27  4408.3  327.11  4437.9  327.56  4530.8  325.38  4566.3  326.27
    4607  325.69  4715.7   325.7  4808.5  324.35  4864.9  322.75  4914.3  318.27
  4930.6   317.5  4935.8  316.44  4996.2  316.05  5012.6  314.87  5026.2  313.19
  5026.7  312.69  5031.8  313.19  5039.8  316.79  5067.1  318.66  5137.9  319.48
  5170.7  321.66  5208.8  321.67  5248.9  324.35  5274.4  324.78  5332.5  327.87
  5345.3   327.6  5426.6  330.82  5618.3  333.57  5729.8  333.47  5893.9  334.68
#Mann= 6 ,-1 , 0
    4298     .07       0    4607    .035       0  4808.5     .07       0
  5012.6     .05       0  5026.2     .05       0  5031.8     .05       0
Bank Sta=5026.2,5031.8
XS Rating Curve= 0 ,0
Exp/Cntr=0.3,0.1

Type RM Length L Ch R = 1 ,8068    ,488,488,488
BEGIN DESCRIPTION:
E21091
END DESCRIPTION:
XS GIS Cut Line= 3
      2476584.64     13760021.18      2475638.57     13759514.01
      2474731.55     13759426.23
#Sta/Elev= 30
  3712.2  332.84  4018.1  325.69  4131.6  324.31  4165.1   324.7  4291.1  323.96
  4360.2  324.78  4433.3  323.05  4470.2  323.11    4534  322.16  4580.3  322.39
  4630.8  322.34  4712.7  319.57  4784.8  313.13  4825.8  316.19  4839.5   316.3
  4975.5  313.74  4980.1  313.85  4987.3  311.43  4987.8  310.93    4993  311.43
  5020.3  316.45  5030.1  319.19  5035.1  319.55  5040.4  321.88  5060.5  325.15
  5100.7  327.28  5139.5  327.77  5472.4  329.43    5603  331.82  5696.9  331.98
#Mann= 10 ,-1 , 0
  3712.2     .07       0  4165.1     .05       0  4360.2    .035       0
  4470.2     .05       0    4534    .035       0  4580.3     .05       0
  4975.5     .07       0  4987.3     .05       0    4993     .07       0
  5139.5     .05       0
Bank Sta=4987.3,4993
XS Rating Curve= 0 ,0
Exp/Cntr=0.3,0.1

Type RM Length L Ch R = 1 ,7580    ,440,440,440
BEGIN DESCRIPTION:
E21090
END DESCRIPTION:
XS GIS Cut Line= 4
       2476779.7     13759787.11      2475853.14     13759114.13
      2475492.28     13759084.87      2474712.03     13759211.66
#Sta/Elev= 30
  3676.6   331.4  3703.3  331.32  3860.2  326.34  4056.3  323.37  4490.2   321.9
    4576  322.38    4733  321.22  4791.7  319.69  4812.5  320.29    4850   318.6
  4910.2   318.5  4940.3  316.59  4970.4  312.89  4990.5  311.63  4998.2  309.32
  4998.7  308.82  5003.9  309.32  5030.6   313.3  5155.6  313.18  5211.1  313.86
  5344.3  321.32  5444.5  321.72  5462.4  320.05  5467.5  321.15  5505.3  319.46
  5545.8  323.38  5641.2  324.92  5788.9   326.9  5809.2  327.95  5974.3   329.3
#Mann= 6 ,-1 , 0
  3676.6     .07       0  4056.3     .05       0  4998.2     .05       0
  5003.9     .05       0  5155.6     .07       0  5641.2     .05       0
Bank Sta=4998.2,5003.9
XS Rating Curve= 0 ,0
Exp/Cntr=0.3,0.1

Type RM Length L Ch R = 1 ,7140    ,757,757,757
BEGIN DESCRIPTION:
E21089
END DESCRIPTION:
XS GIS Cut Line= 3
      2476838.21     13759718.83      2475521.54     13758636.23
      2475248.47     13757856.03
#Sta/Elev= 30
    3396  331.36    3579   325.7    3771  323.18  4559.1  320.66  4658.1  319.69
  4772.5  317.18  4822.6  315.09    4864  313.07  4942.2  311.59  4970.9  312.06
  4978.8  311.62  4985.3  308.79  4988.6  308.36  4989.1  307.86  4996.5  308.36
  5013.9  311.91  5077.8  312.64  5084.3  313.57  5090.6  312.92  5122.8  313.11
    5163   316.1  5230.3  319.26  5261.4  321.89  5292.6  323.01    5530   327.4
  5586.8  329.41  5623.1  329.49    5674   331.7  5752.7  333.74  5927.2  339.43
#Mann= 8 ,-1 , 0
    3396     .07       0    3771     .05       0  4822.6     .07       0
  4988.6     .05       0  4996.5     .07       0  5090.6     .05       0
  5122.8     .07       0  5752.7     .05       0
Bank Sta=4988.6,4996.5
XS Rating Curve= 0 ,0
Exp/Cntr=0.3,0.1

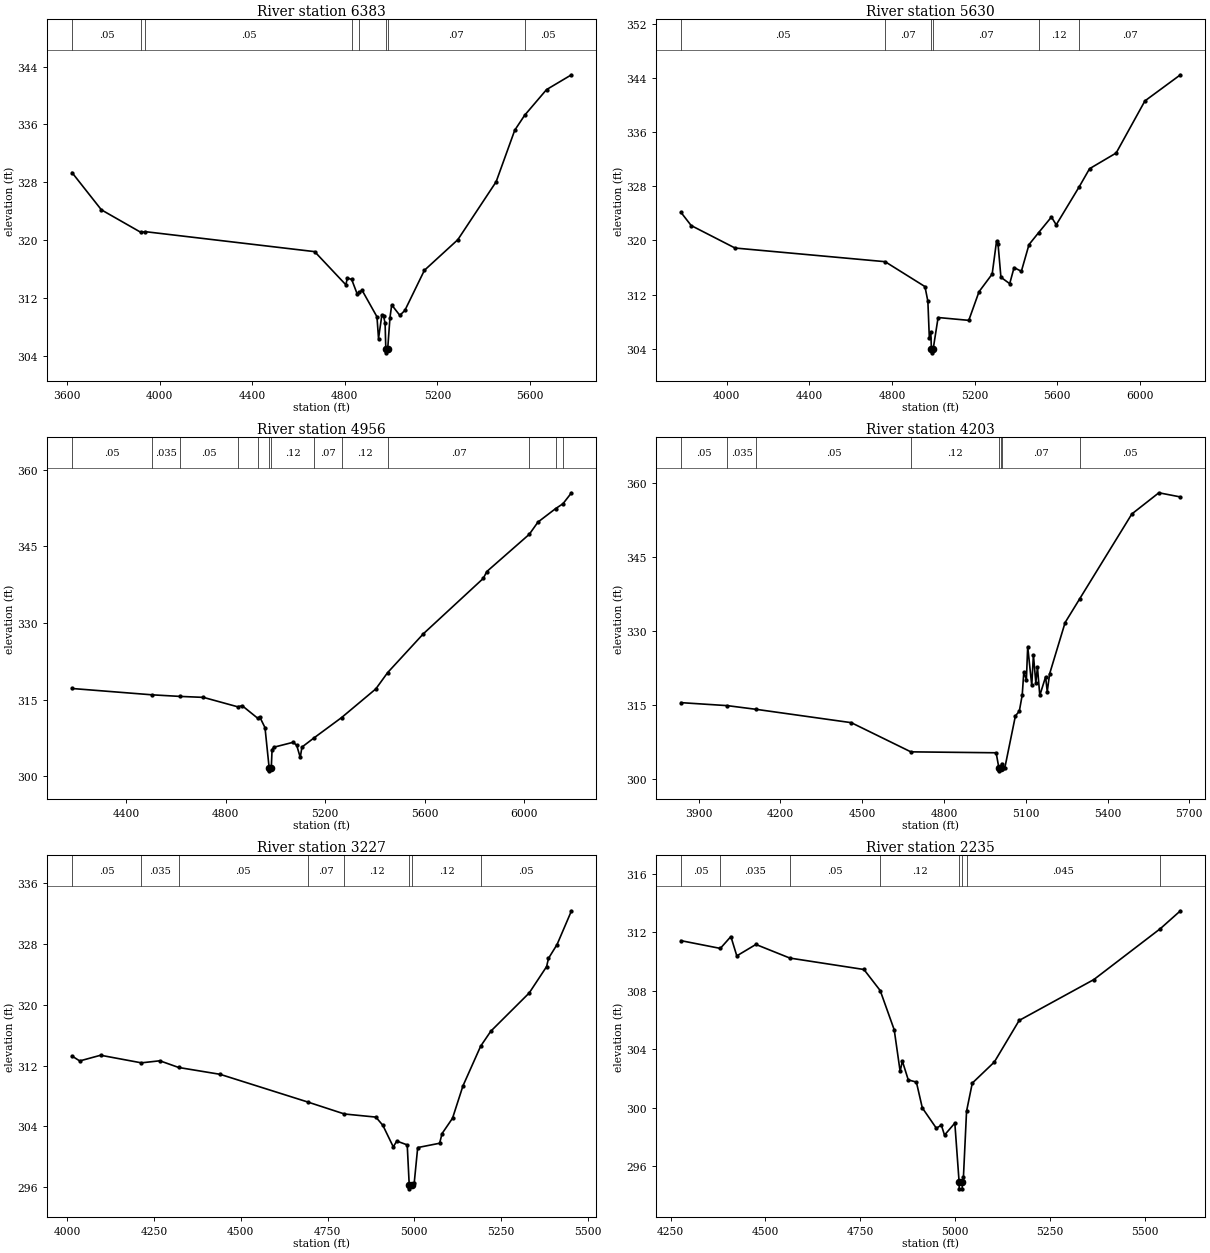
Type RM Length L Ch R = 1 ,6383    ,753,753,753
BEGIN DESCRIPTION:
E21088
END DESCRIPTION:
XS GIS Cut Line= 3
      2477043.02     13759406.73      2476018.94     13758265.62
      2475755.62     13757699.96
#Sta/Elev= 30
  3621.5  329.35  3748.6  324.19  3918.9  321.08  3938.5  321.17  4669.6  318.41
  4804.2  313.83  4810.9  314.75  4829.4  314.57  4853.5  312.54  4862.9   312.8
  4874.4  313.07  4938.7   309.4  4945.4   306.4  4959.6   309.6  4967.1  309.51
  4973.8  308.51  4976.9  304.92  4977.4  304.42  4984.9  304.92  4994.8  309.28
  5002.3  311.05  5037.4   309.6  5059.1  310.28  5143.5  315.83  5287.8  320.06
  5453.3  328.07  5533.7   335.2  5576.6  337.27  5670.9  340.81  5778.7  342.86
#Mann= 8 ,-1 , 0
  3621.5     .05       0  3918.9     .07       0  3938.5     .05       0
  4829.4    .035       0  4862.9     .07       0  4976.9     .05       0
  4984.9     .07       0  5576.6     .05       0
Bank Sta=4976.9,4984.9
XS Rating Curve= 0 ,0
Exp/Cntr=0.3,0.1

Type RM Length L Ch R = 1 ,5630    ,674,674,674
BEGIN DESCRIPTION:
E21087
END DESCRIPTION:
XS GIS Cut Line= 3
      2477540.39     13758880.04      2476370.05     13757719.45
      2475706.82     13757329.31
#Sta/Elev= 30
  3778.1  324.15  3827.9  322.19    4040  318.87  4766.4  316.85  4959.3  313.17
  4973.4     311  4980.5  305.58  4987.6  306.39  4990.6  303.88  4991.1  303.38
  4998.8  303.88  5022.9   308.6  5171.4  308.18  5220.9  312.41  5284.6  315.02
  5305.8   319.9  5312.8  319.53    5327  314.55  5369.4   313.6  5390.6  315.98
  5425.9  315.43  5462.9  319.38  5509.4  321.14  5571.4  323.45  5594.6   322.3
  5705.7  327.91  5755.9  330.59  5884.7  332.91  6023.9  340.61  6195.8  344.47
#Mann= 6 ,-1 , 0
  3778.1     .05       0  4766.4     .07       0  4990.6     .05       0
  4998.8     .07       0  5509.4     .12       0  5705.7     .07       0
Bank Sta=4990.6,4998.8
XS Rating Curve= 0 ,0
Exp/Cntr=0.3,0.1

Type RM Length L Ch R = 1 ,4956    ,753,753,753
BEGIN DESCRIPTION:
E21086
END DESCRIPTION:
XS GIS Cut Line= 3
       2477608.7      13758148.6       2476838.2     13757319.57
      2476252.99      13756666.1
#Sta/Elev= 30
  4181.5  317.16  4503.6  315.92  4615.6  315.61  4710.2  315.42  4847.8  313.58
  4866.1  313.79  4929.2  311.31  4936.9  311.57  4957.9  309.49  4974.7  301.54
  4975.2  301.04  4983.1  301.54  4986.3  305.19  4993.1  305.66  5071.3  306.63
  5085.5  306.02  5099.6  303.66  5106.5  305.69  5154.5  307.47  5265.7  311.46
  5403.6  317.08  5451.1  320.27    5595  327.88  5835.7  338.71  5849.9  340.05
  6020.7  347.34  6055.6  349.73  6126.3  352.36  6156.3  353.33  6190.5  355.47
#Mann= 13 ,-1 , 0
  4181.5     .05       0  4503.6    .035       0  4615.6     .05       0
  4847.8     .07       0  4929.2     .12       0  4974.7     .05       0
  4983.1     .12       0  5154.5     .07       0  5265.7     .12       0
  5451.1     .07       0  6020.7    .035       0  6126.3     .07       0
  6156.3     .05       0
Bank Sta=4974.7,4983.1
XS Rating Curve= 0 ,0
Exp/Cntr=0.3,0.1

Type RM Length L Ch R = 1 ,4203    ,976,976,976
BEGIN DESCRIPTION:
E21085
END DESCRIPTION:
XS GIS Cut Line= 3
      2477676.94     13757972.98      2477247.82     13756783.16
       2476779.8     13756461.39
#Sta/Elev= 30
  3834.6  315.43  4005.1  314.82  4110.8  314.07  4459.7  311.36  4678.3  305.43
  4991.2  305.24  5001.6  302.07  5002.1  301.57  5010.1  302.07  5011.4  303.05
  5023.1  302.19  5061.9  312.74  5076.2  313.69  5086.9  316.97  5092.6  321.57
  5102.2  320.12    5107  326.82  5121.9  318.92  5127.9  325.14  5136.8   319.5
  5142.8  322.62  5151.4  316.89  5172.6  320.67  5178.7  317.69  5187.5   321.3
  5244.3  331.71  5297.3  336.49  5489.2  353.78  5588.3  358.08  5667.4  357.23
#Mann= 8 ,-1 , 0
  3834.6     .05       0  4005.1    .035       0  4110.8     .05       0
  4678.3     .12       0  5001.6     .05       0  5010.1     .12       0
  5011.4     .07       0  5297.3     .05       0
Bank Sta=5001.6,5010.1
XS Rating Curve= 0 ,0
Exp/Cntr=0.3,0.1

Type RM Length L Ch R = 1 ,3227    ,992,992,992
BEGIN DESCRIPTION:
E21084
END DESCRIPTION:
XS GIS Cut Line= 2
      2477940.29     13757807.27      2477803.75     13756373.56
#Sta/Elev= 30
  4013.2  313.25  4035.6   312.6  4095.8  313.35  4213.2  312.35  4266.6  312.62
  4320.8  311.74  4440.3  310.84  4692.7   307.2  4798.7  305.62  4889.4  305.21
  4909.5  304.13  4939.6  301.29  4949.7  302.06  4979.8  301.55  4985.6  296.27
  4986.1  295.77  4994.2  296.27  4999.9  296.51    5010   301.2  5073.2  301.77
  5080.3  303.05  5110.4  305.06  5140.5  309.32  5191.6  314.55  5220.9  316.52
  5331.4  321.54  5381.6  325.01  5387.1   326.1  5411.8  327.92  5453.4  332.36
#Mann= 8 ,-1 , 0
  4013.2     .05       0  4213.2    .035       0  4320.8     .05       0
  4692.7     .07       0  4798.7     .12       0  4985.6     .05       0
  4994.2     .12       0  5191.6     .05       0
Bank Sta=4985.6,4994.2
XS Rating Curve= 0 ,0
Exp/Cntr=0.3,0.1

Type RM Length L Ch R = 1 ,2235    ,968,968,968
BEGIN DESCRIPTION:
E21083
END DESCRIPTION:
XS GIS Cut Line= 2
      2478886.31     13757504.85      2478213.39     13756373.56
#Sta/Elev= 30
  4277.4  311.42  4381.3  310.89  4409.1   311.7  4424.7  310.38    4475  311.16
  4564.5  310.23  4759.7  309.45  4802.6  308.01  4839.5  305.33  4855.1  302.49
  4860.9   303.2  4876.5  301.91  4897.9  301.76  4913.5     300  4950.5  298.61
  4963.7  298.82    4972  298.14  4999.2  298.96  5010.4  294.97  5010.9  294.47
  5018.6  294.47  5019.1  294.97  5021.9  295.28  5030.1  299.77  5045.2  301.69
  5103.3  303.13  5168.7  305.97  5365.4  308.76  5540.8  312.24  5593.7  313.46
#Mann= 8 ,-1 , 0
  4277.4     .05       0  4381.3    .035       0  4564.5     .05       0
  4802.6     .12       0  5010.4     .05       0  5019.1     .12       0
  5030.1    .045       0  5540.8     .05       0
Bank Sta=5010.4,5019.1
XS Rating Curve= 0 ,0
Exp/Cntr=0.3,0.1

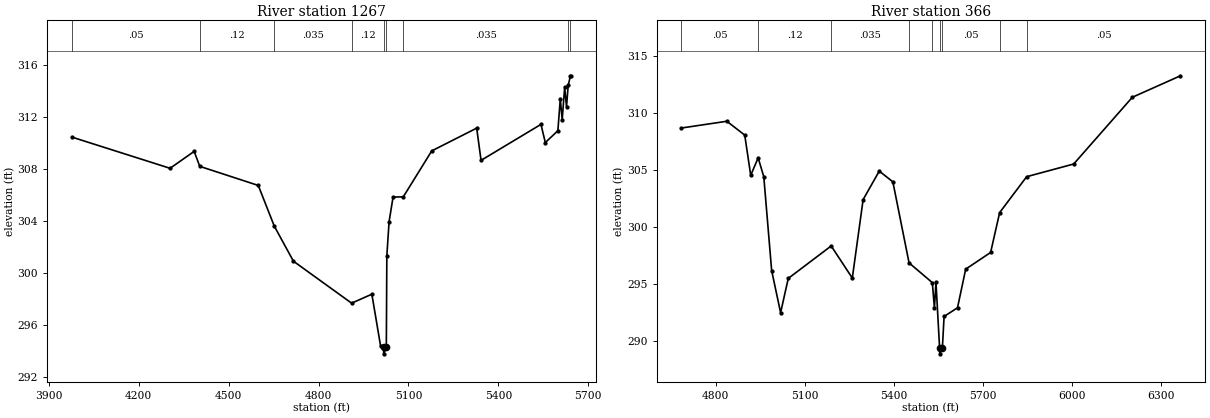
Type RM Length L Ch R = 1 ,1267    ,901,901,901
BEGIN DESCRIPTION:
E21082
END DESCRIPTION:
XS GIS Cut Line= 3
      2479237.46     13757173.31      2479042.38     13756627.11
      2478389.82     13755760.27
#Sta/Elev= 30
    3977  310.47  4304.4  308.07  4384.9  309.37  4403.5  308.22  4598.8  306.75
  4652.2  303.62  4716.1  300.92  4910.3  297.69  4977.8  298.38  5006.9   294.4
  5016.9  294.29  5017.4  293.79  5026.1  294.29  5027.8  301.33  5035.3  303.96
  5048.6  305.86  5082.6  305.87  5177.7  309.41  5327.6  311.16  5342.2  308.68
  5542.1  311.45  5556.6  310.05  5598.5  310.96  5606.6  313.41  5612.9   311.8
  5621.2  314.31  5627.4  312.81    5633  314.46  5640.6  315.19    5642  315.16
#Mann= 9 ,-1 , 0
    3977     .05       0  4403.5     .12       0  4652.2    .035       0
  4910.3     .12       0  5016.9     .05       0  5026.1     .12       0
  5082.6    .035       0    5633     .07       0  5640.6    .035       0
Bank Sta=5016.9,5026.1
XS Rating Curve= 0 ,0
Exp/Cntr=0.3,0.1

Type RM Length L Ch R = 1 ,366     ,0,0,0
BEGIN DESCRIPTION:
E21081
END DESCRIPTION:
XS GIS Cut Line= 3
      2479422.75     13757036.71      2479344.73     13756383.28
      2479062.15     13755399.12
#Sta/Elev= 30
  4684.5  308.66  4837.3  309.25  4897.7  308.04  4917.9  304.52  4942.9  306.05
  4961.9   304.4  4988.4  296.19  5018.6   292.5  5044.4   295.5  5189.1  298.34
  5260.3  295.53  5296.8   302.4  5351.2  304.89    5397  303.95  5451.6  296.86
  5530.1  295.13  5537.1  292.89  5542.3  295.16  5554.6   289.4  5555.1   288.9
  5563.9   289.4  5569.7  292.17  5614.9  292.93  5642.5  296.31  5726.5  297.77
    5757  301.26    5848   304.4  6006.6  305.51  6204.3  311.35  6366.5  313.23
#Mann= 9 ,-1 , 0
  4684.5     .05       0  4942.9     .12       0  5189.1    .035       0
  5451.6     .07       0  5530.1     .05       0  5554.6     .05       0
  5563.9     .05       0    5757     .12       0    5848     .05       0
Bank Sta=5554.6,5563.9
XS Rating Curve= 0 ,0
Exp/Cntr=0.3,0.1

Chan Stop Cuts=-1
Use User Specified Reach Order=0
Composite Channel Slope=5