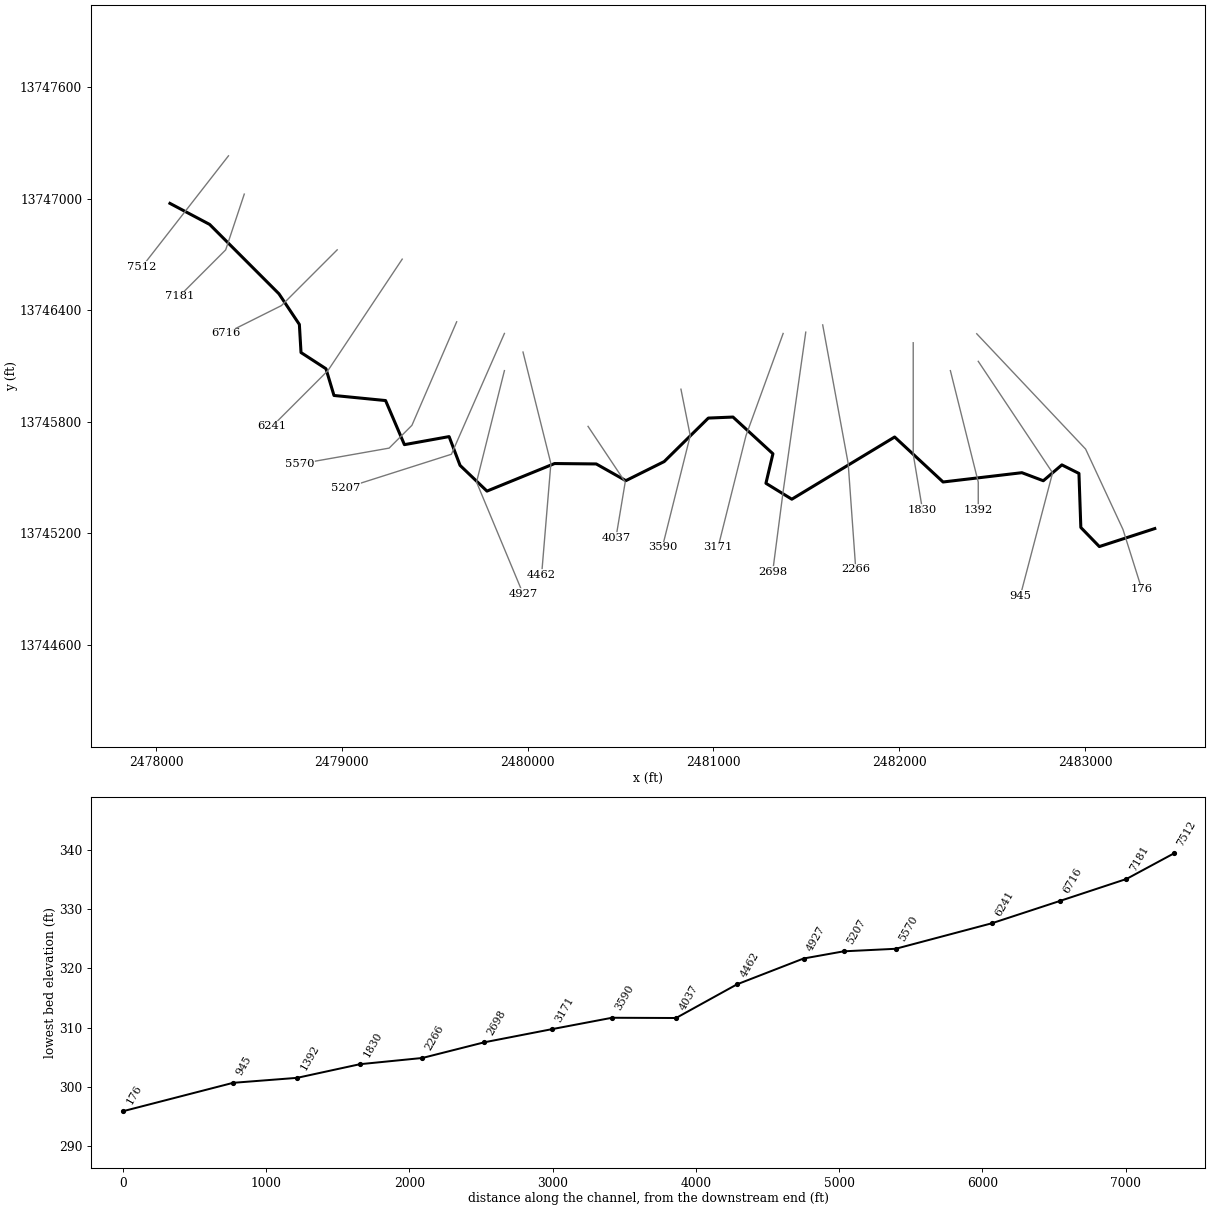
--- Stream0480.prj (project) ---

Proj Title=Stream0480 Base Level Engineering
Current Plan=p01
Default Exp/Contr=0.3,0.1
English Units
Geom File=g01
Flow File=f01
Plan File=p01
BEGIN DESCRIPTION:
Stream0480
END DESCRIPTION:

--- Stream0480.p01 (plan) ---

Plan Title=Multiple Run
Short Identifier=Multiple
Geom File=g01
Flow File=f01
Subcritical Flow
K Sum by GR= 0
Std Step Tol= 0.01
Critical Tol= 0.01
Num of Std Step Trials= 20
Max Error Tol= 0.3
Flow Tol Ratio= 0.001
Split Flow NTrial= 30
Split Flow Tol= 0.02
Split Flow Ratio= 0.02
Log Output Level= 0
Friction Slope Method= 1
Unsteady Friction Slope Method= 2
Unsteady Bridges Friction Slope Method= 1
Parabolic Critical Depth
Global Vel Dist=  1 , 1 , 1
Global Log Level= 0
CheckData=True
Encroach Param= -1, 0, 0, 0
BEGIN DESCRIPTION:
Multiple Run
END DESCRIPTION:

--- Stream0480.f01 (steady flow) ---

Flow Title=Multiple
Number of Profiles=7
Profile Names=10-year,25-year,50-year,1pct_min,100-year,1pct_plu,500-year
River Rch & RM= Stream0480,Reach-1,7512
     317     486     630     397     792    1581    1237
River Rch & RM= Stream0480,Reach-1,4462
     529     835    1106     709    1415    2824    2293
Boundary for River Rch & Prof#=Stream0480,Reach-1,1
Up Type=0
Dn Type=3
Dn Slope=0.005
Boundary for River Rch & Prof#=Stream0480,Reach-1,2
Up Type=0
Dn Type=3
Dn Slope=0.005
Boundary for River Rch & Prof#=Stream0480,Reach-1,3
Up Type=0
Dn Type=3
Dn Slope=0.005
Boundary for River Rch & Prof#=Stream0480,Reach-1,4
Up Type=0
Dn Type=3
Dn Slope=0.005
Boundary for River Rch & Prof#=Stream0480,Reach-1,5
Up Type=0
Dn Type=3
Dn Slope=0.005
Boundary for River Rch & Prof#=Stream0480,Reach-1,6
Up Type=0
Dn Type=3
Dn Slope=0.005
Boundary for River Rch & Prof#=Stream0480,Reach-1,7
Up Type=0
Dn Type=3
Dn Slope=0.005

--- Stream0480.g01 (geometry) ---

Geom Title=Existing Conditions

River Reach=Stream0480,Reach-1
Reach XY= 30
      2478075.00     13746975.00      2478288.65     13746861.74
      2478661.51     13746488.56      2478771.45     13746323.53
      2478780.37     13746172.30      2478914.61     13746085.10
      2478957.78     13745941.24      2479235.37     13745913.92
      2479336.81     13745676.60      2479577.33     13745719.91
      2479636.24     13745565.00      2479781.03     13745426.61
      2480145.03     13745574.93      2480369.07     13745572.76
      2480528.40     13745482.78      2480734.79     13745585.52
      2480972.32     13745819.61      2481105.11     13745825.11
      2481320.01     13745627.54      2481282.37     13745468.66
      2481421.69     13745383.02      2481975.09     13745717.71
      2482235.64     13745475.65      2482659.94     13745525.69
      2482775.10     13745482.34      2482874.94     13745567.70
      2482966.89     13745521.69      2482977.05     13745230.84
      2483076.62     13745128.12      2483375.00     13745225.00

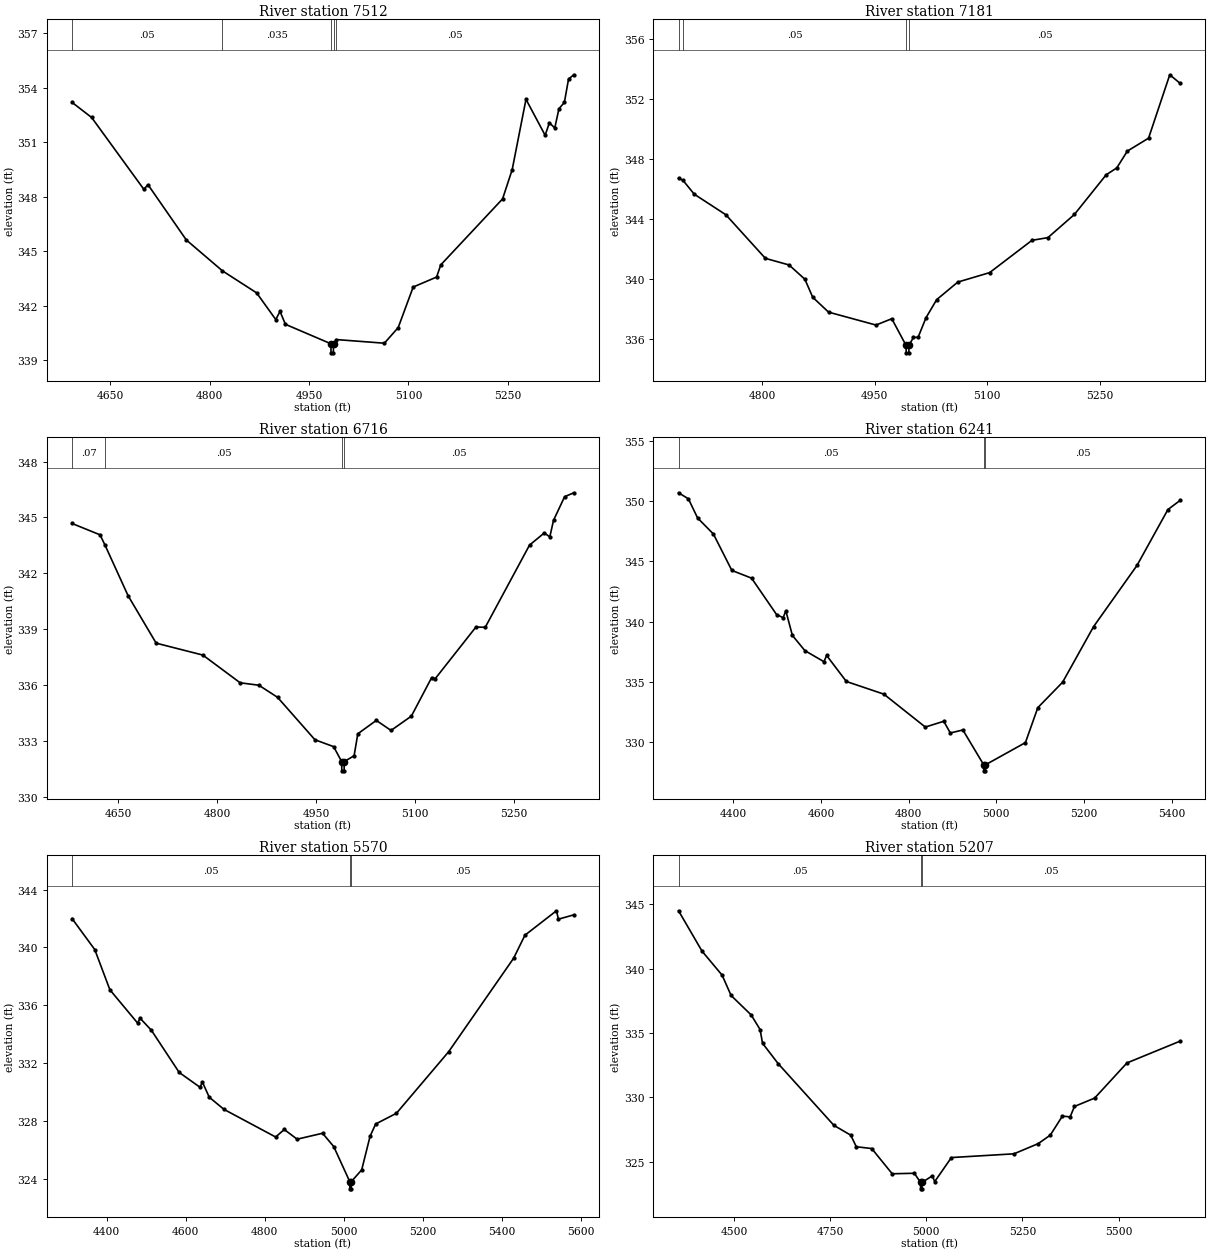
Type RM Length L Ch R = 1,7512,331,331,331
BEGIN DESCRIPTION:
XS6912
END DESCRIPTION:
XS GIS Cut Line= 2
      2478389.96     13747230.90      2477924.86     13746634.01
#Sta/Elev= 30
  4592.7  353.18  4622.2  352.35  4700.9  348.40  4707.2  348.65  4765.0  345.61
  4819.5  343.91  4871.0  342.70  4899.9  341.23  4906.3  341.68  4914.4  340.97
  4983.0  339.90  4983.2  339.40  4986.7  339.40  4987.0  339.90  4991.2  340.13
  5063.7  339.93  5084.5  340.79  5107.1  343.02  5142.4  343.57  5148.7  344.24
  5241.9  347.87  5256.4  349.48  5277.2  353.35  5306.1  351.37  5312.5  352.06
  5320.6  351.77  5326.9  352.83  5335.1  353.18  5341.4  354.47  5349.4  354.70
#Mann=5,-1,0
  4592.7    0.05       0  4819.5   0.035       0  4983.0    0.05       0
  4987.0   0.035       0  4991.2    0.05       0
Bank Sta=4983,4987
Exp/Cntr=0.3,0.1

Type RM Length L Ch R = 1,7181,465,465,465
BEGIN DESCRIPTION:
Stream0480 14.0
END DESCRIPTION:
XS GIS Cut Line= 3
      2478474.99     13747024.96      2478375.00     13746725.00
      2478125.02     13746475.02
#Sta/Elev= 30
  4688.0  346.71  4693.8  346.58  4709.0  345.65  4751.2  344.28  4803.9  341.38
  4835.5  340.94  4856.6  339.99  4867.1  338.79  4888.2  337.80  4951.5  336.94
  4972.6  337.36  4991.6  335.59  4991.9  335.09  4995.4  335.09  4995.6  335.59
  5001.5  336.12  5007.7  336.12  5018.3  337.43  5032.5  338.63  5060.7  339.80
  5103.2  340.43  5159.7  342.58  5181.0  342.76  5216.3  344.30  5258.7  346.94
  5272.9  347.40  5287.0  348.52  5315.3  349.38  5343.6  353.60  5357.7  353.02
#Mann=4,-1,0
  4688.0   0.035       0  4693.8    0.05       0  4991.6    0.05       0
  4995.6    0.05       0
Bank Sta=4991.6,4995.6
Exp/Cntr=0.3,0.1

Type RM Length L Ch R = 1,6716,475,475,475
BEGIN DESCRIPTION:
Stream0480 13.0
END DESCRIPTION:
XS GIS Cut Line= 3
      2478974.99     13746724.99      2478675.00     13746425.00
      2478374.96     13746274.98
#Sta/Elev= 30
  4580.6  344.67  4623.0  344.06  4630.7  343.49  4665.4  340.79  4707.9  338.24
  4778.6  337.60  4835.1  336.11  4863.4  335.98  4891.7  335.33  4948.3  333.05
  4976.6  332.68  4988.7  331.88  4989.0  331.38  4992.5  331.38  4992.7  331.88
  5007.6  332.19  5013.2  333.37  5041.2  334.09  5063.5  333.55  5094.3  334.32
  5125.0  336.39  5130.6  336.34  5192.1  339.11  5206.1  339.09  5273.2  343.51
  5295.5  344.16  5303.9  343.95  5309.5  344.84  5326.3  346.11  5340.3  346.32
#Mann=4,-1,0
  4580.6    0.07       0  4630.7    0.05       0  4988.7    0.05       0
  4992.7    0.05       0
Bank Sta=4988.7,4992.7
Exp/Cntr=0.3,0.1

Type RM Length L Ch R = 1,6241,671,671,671
BEGIN DESCRIPTION:
Stream0480 12.0
END DESCRIPTION:
XS GIS Cut Line= 3
      2479324.99     13746674.98      2478925.00     13746075.00
      2478624.97     13745774.97
#Sta/Elev= 30
  4274.7  350.68  4297.2  350.18  4318.2  348.59  4354.3  347.26  4396.4  344.24
  4441.4  343.60  4498.5  340.58  4513.5  340.32  4519.6  340.89  4534.6  338.85
  4563.1  337.59  4606.7  336.67  4612.7  337.19  4657.8  335.03  4743.4  333.98
  4838.0  331.25  4880.1  331.73  4895.1  330.76  4923.7  331.01  4971.3  328.12
  4971.5  327.62  4975.0  327.62  4975.3  328.12  5066.5  329.96  5094.8  332.86
  5151.4  334.97  5222.1  339.58  5321.1  344.65  5391.8  349.29  5420.1  350.06
#Mann=3,-1,0
  4274.7    0.05       0  4971.3    0.05       0  4975.3    0.05       0
Bank Sta=4971.3,4975.3
Exp/Cntr=0.3,0.1

Type RM Length L Ch R = 1,5570,363,363,363
BEGIN DESCRIPTION:
E21099
END DESCRIPTION:
XS GIS Cut Line= 4
      2479618.00     13746337.70      2479377.26     13745780.67
      2479254.52     13745657.94      2478773.06     13745572.97
#Sta/Elev= 30
  4312.5  341.99  4369.9  339.85  4408.2  337.07  4478.7  334.76  4484.1  335.12
  4513.0  334.28  4583.5  331.36  4636.0  330.34  4642.3  330.69  4659.5  329.65
  4696.7  328.81  4827.5  326.90  4849.2  327.42  4881.8  326.75  4946.1  327.16
  4974.4  326.24  5014.9  323.82  5015.1  323.32  5018.6  323.32  5018.9  323.82
  5045.1  324.63  5066.4  326.96  5080.5  327.80  5133.0  328.54  5265.0  332.79
  5429.4  339.25  5458.0  340.84  5537.7  342.53  5542.8  341.95  5581.8  342.25
#Mann=3,-1,0
  4312.5    0.05       0  5014.9    0.05       0  5018.9    0.05       0
Bank Sta=5014.9,5018.9
Exp/Cntr=0.3,0.1

Type RM Length L Ch R = 1,5207,280,280,280
BEGIN DESCRIPTION:
Stream0480 11.0
END DESCRIPTION:
XS GIS Cut Line= 3
      2479875.01     13746275.02      2479589.68     13745624.89
      2479022.72     13745444.35
#Sta/Elev= 30
  4355.5  344.49  4416.7  341.35  4468.8  339.49  4492.2  337.91  4544.4  336.40
  4567.7  335.26  4573.9  334.20  4614.5  332.62  4759.6  327.82  4803.3  327.06
  4817.8  326.16  4857.9  326.02  4911.2  324.06  4968.8  324.10  4984.8  323.39
  4985.0  322.89  4988.5  322.89  4988.8  323.39  5015.6  323.90  5021.7  323.45
  5065.1  325.32  5227.8  325.61  5290.8  326.40  5322.3  327.06  5353.8  328.54
  5373.9  328.48  5385.2  329.29  5437.7  329.94  5521.7  332.67  5660.5  334.37
#Mann=3,-1,0
  4355.5    0.05       0  4984.8    0.05       0  4988.8    0.05       0
Bank Sta=4984.8,4988.8
Exp/Cntr=0.3,0.1

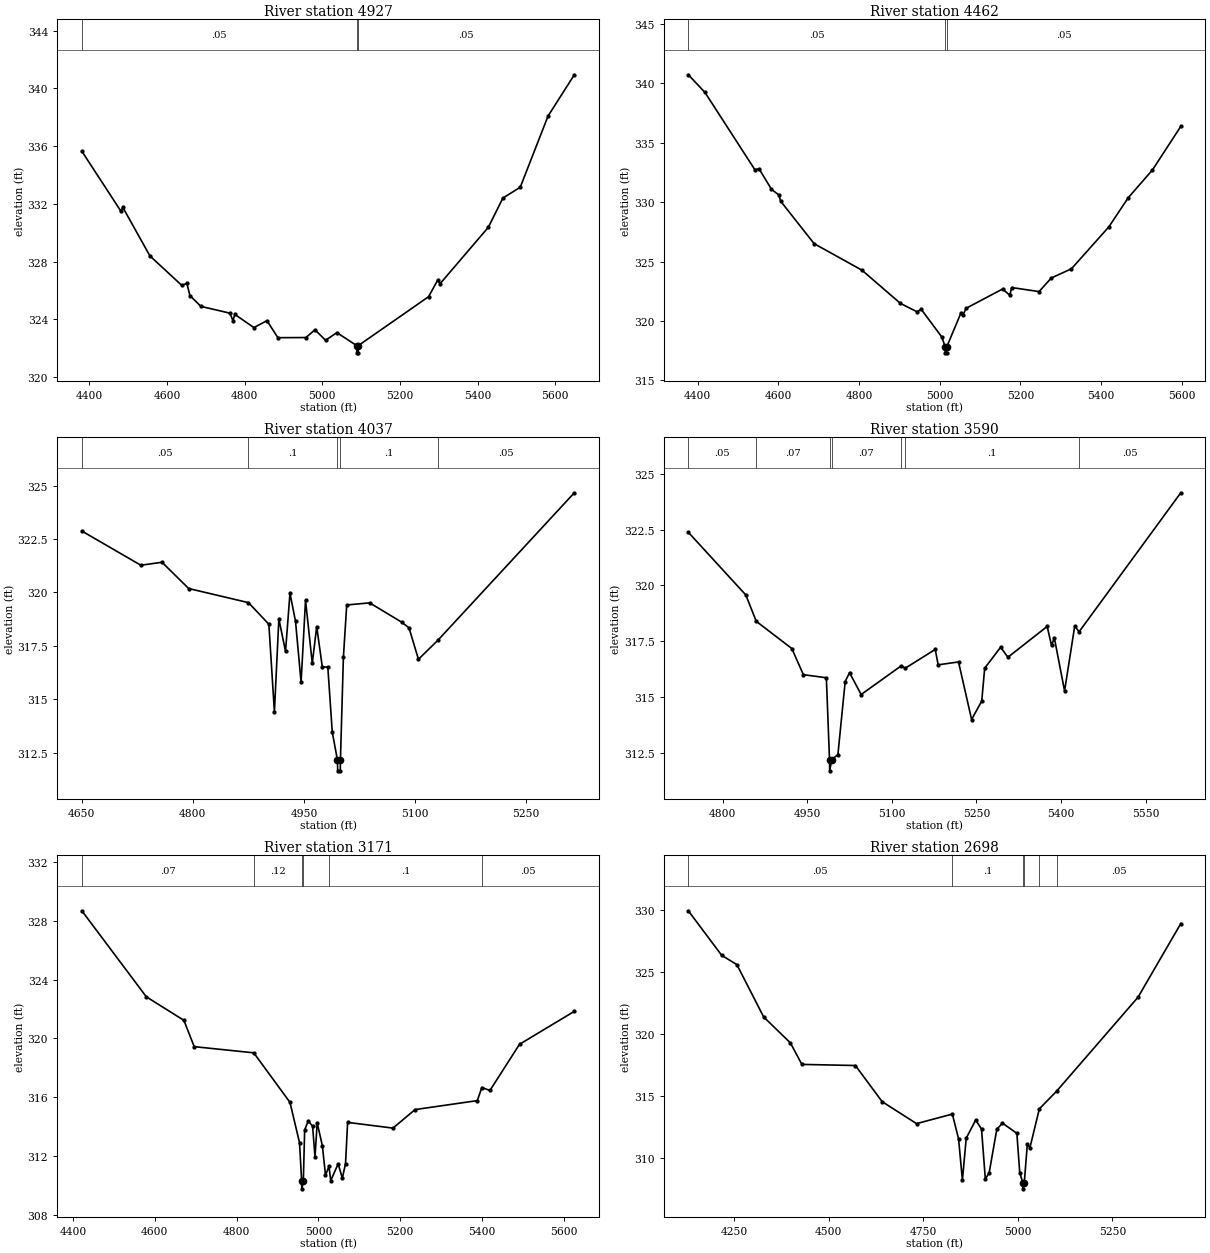
Type RM Length L Ch R = 1,4927,465,465,465
BEGIN DESCRIPTION:
Stream0480 10.0
END DESCRIPTION:
XS GIS Cut Line= 3
      2479874.99     13746074.96      2479725.00     13745475.00
      2479974.99     13744875.02
#Sta/Elev= 30
  4380.8  335.65  4481.3  331.50  4486.4  331.76  4556.0  328.40  4638.4  326.35
  4651.3  326.50  4659.1  325.65  4687.4  324.90  4762.1  324.43  4769.9  323.92
  4775.0  324.34  4824.0  323.43  4857.5  323.91  4885.8  322.73  4958.0  322.74
  4981.2  323.28  5008.4  322.55  5037.7  323.08  5088.8  322.18  5089.0  321.68
  5092.5  321.68  5092.8  322.18  5273.8  325.57  5297.7  326.74  5303.1  326.46
  5427.7  330.38  5465.1  332.40  5510.0  333.16  5581.5  338.09  5649.2  340.95
#Mann=3,-1,0
  4380.8    0.05       0  5088.8    0.05       0  5092.8    0.05       0
Bank Sta=5088.8,5092.8
Exp/Cntr=0.3,0.1

Type RM Length L Ch R = 1,4462,425,425,425
BEGIN DESCRIPTION:
Stream0480 9.0
END DESCRIPTION:
XS GIS Cut Line= 3
      2479975.01     13746174.95      2480125.00     13745575.00
      2480075.00     13744975.00
#Sta/Elev= 30
  4376.8  340.70  4418.0  339.22  4541.7  332.72  4552.0  332.80  4582.9  331.07
  4600.9  330.60  4606.1  330.05  4688.6  326.50  4807.1  324.27  4902.4  321.48
  4943.7  320.77  4954.0  320.98  5005.3  318.64  5013.3  317.82  5013.5  317.32
  5017.0  317.32  5017.3  317.82  5052.9  320.71  5057.9  320.54  5065.5  321.07
  5155.8  322.69  5173.3  322.16  5178.3  322.81  5246.1  322.47  5276.2  323.61
  5326.4  324.39  5419.2  327.92  5466.8  330.35  5527.1  332.70  5597.3  336.36
#Mann=3,-1,0
  4376.8    0.05       0  5013.3    0.05       0  5017.3    0.05       0
Bank Sta=5013.3,5017.3
Exp/Cntr=0.3,0.1

Type RM Length L Ch R = 1,4037,447,447,447
BEGIN DESCRIPTION:
Stream0480 8.0
END DESCRIPTION:
XS GIS Cut Line= 3
      2480325.01     13745774.99      2480525.00     13745475.00
      2480475.00     13745174.98
#Sta/Elev= 30
  4650.3  322.87  4729.9  321.27  4758.5  321.41  4794.5  320.18  4875.2  319.52
  4902.7  318.51  4910.2  314.41  4916.2  318.76  4925.2  317.24  4931.2  319.96
  4938.7  318.64  4946.2  315.79  4952.2  319.63  4961.3  316.68  4967.3  318.40
  4974.8  316.52  4982.3  316.50  4988.3  313.46  4995.3  312.15  4995.6  311.65
  4999.1  311.65  4999.3  312.15  5003.3  316.96  5007.8  319.41  5038.7  319.51
  5081.8  318.61  5091.9  318.34  5104.6  316.87  5130.6  317.75  5315.0  324.66
#Mann=5,-1,0
  4650.3    0.05       0  4875.2     0.1       0  4995.3    0.05       0
  4999.3     0.1       0  5130.6    0.05       0
Bank Sta=4995.3,4999.3
Exp/Cntr=0.3,0.1

Type RM Length L Ch R = 1,3590,419,419,419
BEGIN DESCRIPTION:
Stream0480 7.0
END DESCRIPTION:
XS GIS Cut Line= 3
      2480824.99     13745975.03      2480875.00     13745725.00
      2480725.01     13745125.04
#Sta/Elev= 30
  4739.1  322.38  4841.1  319.57  4859.6  318.39  4922.7  317.17  4943.1  316.00
  4983.9  315.86  4989.5  312.19  4989.8  311.69  4993.5  312.19  5004.4  312.42
  5017.3  315.69  5025.0  316.09  5045.6  315.11  5116.4  316.39  5123.9  316.29
  5177.0  317.13  5182.2  316.44  5218.3  316.57  5241.5  313.99  5259.5  314.82
  5264.7  316.29  5293.0  317.23  5305.9  316.78  5375.5  318.16  5383.2  317.32
  5388.3  317.64  5406.4  315.27  5424.4  318.18  5432.1  317.92  5612.5  324.15
#Mann=7,-1,0
  4739.1    0.05       0  4859.6    0.07       0  4989.5    0.05       0
  4993.5    0.07       0  5116.4    0.12       0  5123.9     0.1       0
  5432.1    0.05       0
Bank Sta=4989.5,4993.5
Exp/Cntr=0.3,0.1

Type RM Length L Ch R = 1,3171,473,473,473
BEGIN DESCRIPTION:
Stream0480 6.0
END DESCRIPTION:
XS GIS Cut Line= 3
      2481374.99     13746274.97      2481175.00     13745725.00
      2481024.99     13745124.96
#Sta/Elev= 30
  4421.7  328.68  4579.3  322.83  4671.1  321.23  4696.3  319.44  4841.9  319.02
  4930.4  315.65  4953.7  312.91  4959.0  310.27  4959.3  309.77  4963.0  310.27
  4966.3  313.78  4975.0  314.38  4985.6  314.04  4991.6  311.93  4996.9  314.26
  5009.5  312.71  5017.2  310.70  5025.7  311.29  5030.1  310.33  5048.1  311.47
  5058.4  310.50  5066.2  311.49  5071.3  314.29  5182.1  313.90  5236.2  315.16
  5388.3  315.77  5399.3  316.66  5419.2  316.46  5491.4  319.60  5625.4  321.84
#Mann=6,-1,0
  4421.7    0.07       0  4841.9    0.12       0  4959.0    0.05       0
  4963.0    0.12       0  5025.7     0.1       0  5399.3    0.05       0
Bank Sta=4959,4963
Exp/Cntr=0.3,0.1

Type RM Length L Ch R = 1,2698,432,432,432
BEGIN DESCRIPTION:
Stream0480 5.0
END DESCRIPTION:
XS GIS Cut Line= 3
      2481496.71     13746282.08      2481375.00     13745425.00
      2481318.74     13744992.92
#Sta/Elev= 30
  4129.3  329.94  4217.3  326.36  4257.7  325.60  4328.4  321.39  4399.1  319.30
  4429.4  317.57  4570.8  317.48  4641.5  314.57  4732.4  312.80  4827.0  313.57
  4843.5  311.57  4853.6  308.25  4863.7  311.63  4888.6  313.09  4904.1  312.37
  4914.2  308.34  4924.3  308.84  4944.5  312.35  4959.5  312.84  4997.5  312.02
  5005.1  308.85  5013.1  308.05  5013.4  307.55  5017.1  308.05  5025.2  311.15
  5032.0  310.86  5056.9  313.99  5102.4  315.41  5317.7  322.98  5430.7  328.91
#Mann=6,-1,0
  4129.3    0.05       0  4827.0     0.1       0  5013.1    0.05       0
  5017.1     0.1       0  5056.9    0.12       0  5102.4    0.05       0
Bank Sta=5013.1,5017.1
Exp/Cntr=0.3,0.1

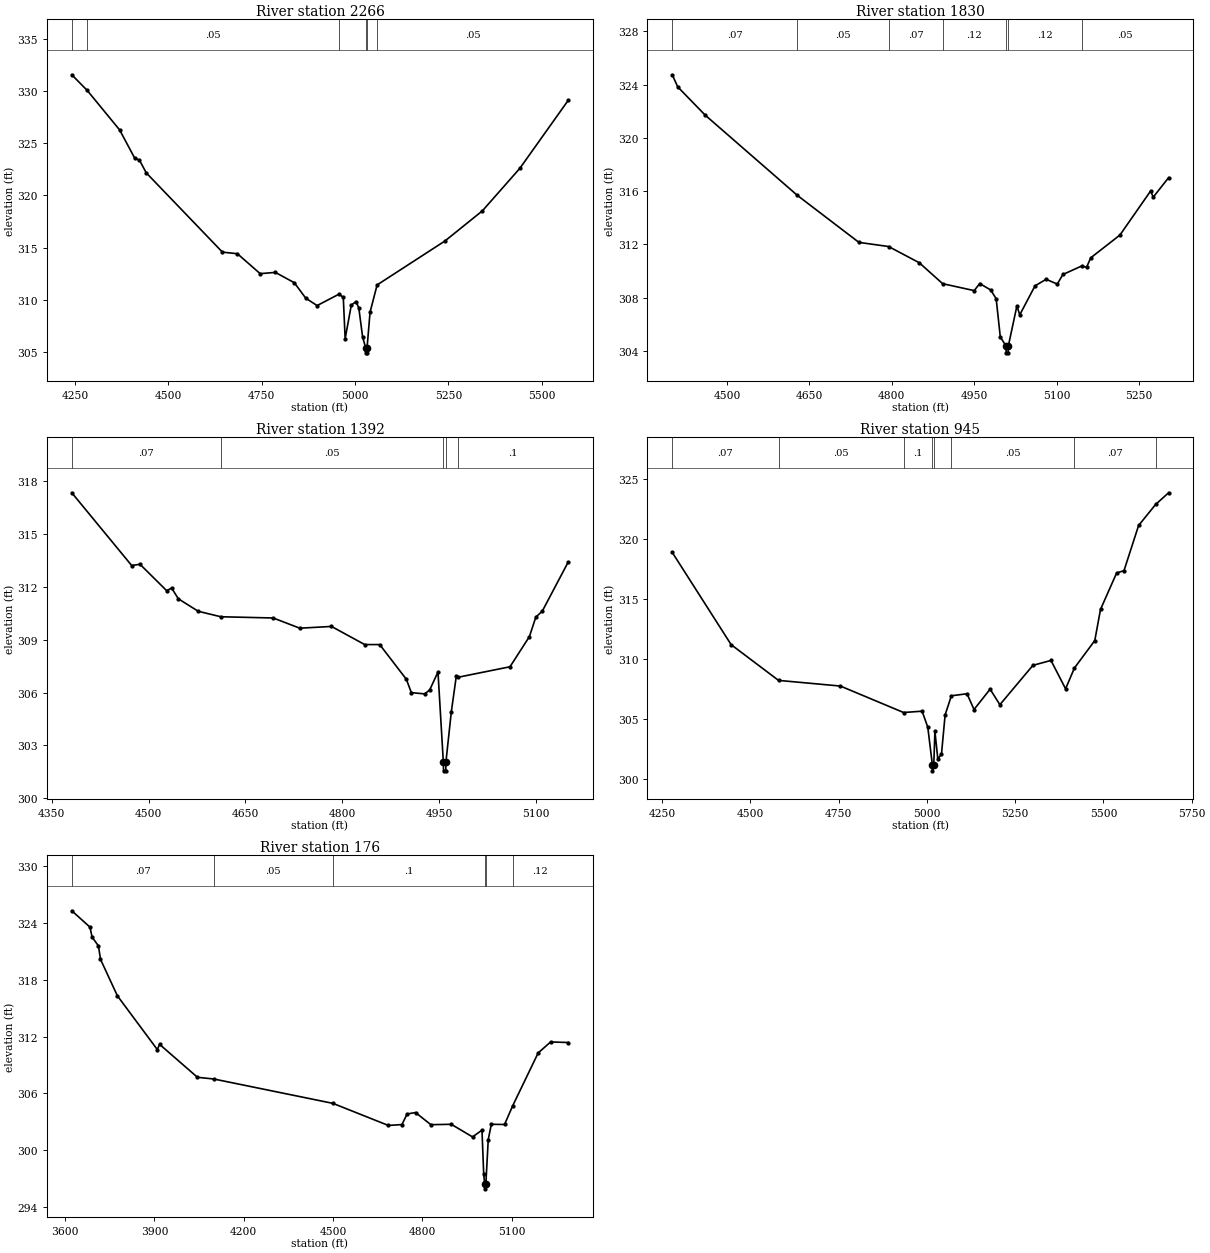
Type RM Length L Ch R = 1,2266,436,436,436
BEGIN DESCRIPTION:
Stream0480 4.0
END DESCRIPTION:
XS GIS Cut Line= 3
      2481587.85     13746321.08      2481725.00     13745575.00
      2481765.80     13745005.94
#Sta/Elev= 30
  4241.4  331.56  4282.7  330.06  4369.6  326.27  4410.3  323.54  4422.4  323.39
  4440.8  322.16  4644.8  314.56  4684.8  314.41  4745.8  312.50  4786.5  312.62
  4837.3  311.63  4867.8  310.15  4898.3  309.44  4957.3  310.54  4968.4  310.22
  4973.4  306.26  4989.8  309.48  5002.5  309.83  5010.0  309.21  5020.0  306.46
  5028.1  305.41  5028.3  304.91  5031.8  304.91  5032.1  305.41  5040.1  308.81
  5059.0  311.42  5240.6  315.63  5340.9  318.52  5441.1  322.59  5570.5  329.10
#Mann=6,-1,0
  4241.4    0.07       0  4282.7    0.05       0  4957.3    0.12       0
  5028.1    0.05       0  5032.1    0.12       0  5059.0    0.05       0
Bank Sta=5028.1,5032.1
Exp/Cntr=0.3,0.1

Type RM Length L Ch R = 1,1830,438,438,438
BEGIN DESCRIPTION:
Stream0480 3.0
END DESCRIPTION:
XS GIS Cut Line= 3
      2482075.00     13746224.96      2482075.00     13745625.00
      2482125.00     13745325.00
#Sta/Elev= 30
  4400.1  324.73  4410.1  323.82  4460.1  321.70  4628.2  315.67  4740.1  312.15
  4794.1  311.84  4850.1  310.62  4892.6  309.05  4950.1  308.53  4960.1  309.06
  4980.1  308.58  4990.1  307.92  4997.6  305.06  5008.2  304.36  5008.4  303.86
  5011.9  303.86  5012.2  304.36  5027.9  307.39  5033.0  306.71  5060.9  308.89
  5081.2  309.38  5101.4  309.02  5111.6  309.74  5146.0  310.38  5154.7  310.27
  5162.3  310.99  5215.5  312.70  5271.3  316.00  5276.3  315.55  5304.2  317.01
#Mann=7,-1,0
  4400.1    0.07       0  4628.2    0.05       0  4794.1    0.07       0
  4892.6    0.12       0  5008.2    0.05       0  5012.2    0.12       0
  5146.0    0.05       0
Bank Sta=5008.2,5012.2
Exp/Cntr=0.3,0.1

Type RM Length L Ch R = 1,1392,447,447,447
BEGIN DESCRIPTION:
Stream0480 2.0
END DESCRIPTION:
XS GIS Cut Line= 3
      2482275.01     13746074.97      2482425.00     13745475.00
      2482425.00     13745325.04
#Sta/Elev= 30
  4381.2  317.35  4473.9  313.22  4486.8  313.29  4528.1  311.79  4535.8  311.94
  4546.1  311.33  4577.0  310.62  4611.9  310.31  4693.0  310.24  4734.2  309.66
  4783.2  309.76  4834.7  308.73  4857.9  308.73  4899.1  306.76  4906.9  306.00
  4927.5  305.93  4935.2  306.15  4948.1  307.17  4956.4  302.06  4956.7  301.56
  4960.2  301.56  4960.4  302.06  4968.7  304.90  4976.4  306.92  4978.6  306.87
  5059.6  307.47  5089.6  309.18  5099.6  310.29  5109.6  310.63  5149.6  313.41
#Mann=5,-1,0
  4381.2    0.07       0  4611.9    0.05       0  4956.4    0.05       0
  4960.4    0.05       0  4978.6     0.1       0
Bank Sta=4956.4,4960.4
Exp/Cntr=0.3,0.1

Type RM Length L Ch R = 1,945,769,769,769
BEGIN DESCRIPTION:
Stream0480 1.0
END DESCRIPTION:
XS GIS Cut Line= 3
      2482425.00     13746125.01      2482825.00     13745525.00
      2482651.21     13744862.74
#Sta/Elev= 30
  4278.9  318.88  4445.7  311.21  4579.9  308.24  4755.1  307.77  4934.0  305.57
  4986.5  305.68  5002.6  304.35  5015.6  301.22  5015.9  300.72  5019.6  301.22
  5022.8  304.01  5031.0  301.71  5041.4  302.11  5051.7  305.37  5069.4  306.96
  5113.7  307.13  5133.6  305.82  5179.1  307.51  5206.8  306.22  5300.3  309.49
  5351.5  309.90  5392.9  307.54  5417.9  309.27  5475.6  311.55  5491.8  314.14
  5537.6  317.18  5558.3  317.36  5599.7  321.12  5647.9  322.87  5684.7  323.84
#Mann=8,-1,0
  4278.9    0.07       0  4579.9    0.05       0  4934.0     0.1       0
  5015.6    0.05       0  5019.6     0.1       0  5069.4    0.05       0
  5417.9    0.07       0  5647.9    0.05       0
Bank Sta=5015.6,5019.6
Exp/Cntr=0.3,0.1

Type RM Length L Ch R = 1,176,0,0,0
BEGIN DESCRIPTION:
XS6913
END DESCRIPTION:
XS GIS Cut Line= 4
      2482416.84     13746273.35      2483002.78     13745652.69
      2483203.93     13745219.95      2483305.07     13744898.96
#Sta/Elev= 30
  3622.5  325.27  3683.7  323.54  3690.6  322.50  3712.1  321.56  3718.9  320.15
  3775.6  316.30  3909.9  310.62  3917.2  311.18  4044.6  307.70  4099.5  307.52
  4499.5  304.95  4685.8  302.62  4731.5  302.71  4748.9  303.83  4777.3  303.98
  4828.6  302.70  4897.3  302.74  4968.6  301.41  5000.4  302.12  5006.2  297.47
  5009.4  296.43  5009.7  295.93  5013.4  296.43  5021.4  301.12  5031.8  302.74
  5076.2  302.72  5103.5  304.69  5189.1  310.27  5231.0  311.43  5289.8  311.37
#Mann=6,-1,0
  3622.5    0.07       0  4099.5    0.05       0  4499.5     0.1       0
  5009.4    0.05       0  5013.4     0.1       0  5103.5    0.12       0
Bank Sta=5009.4,5013.4
Exp/Cntr=0.3,0.1

Chan Stop Cuts=-1