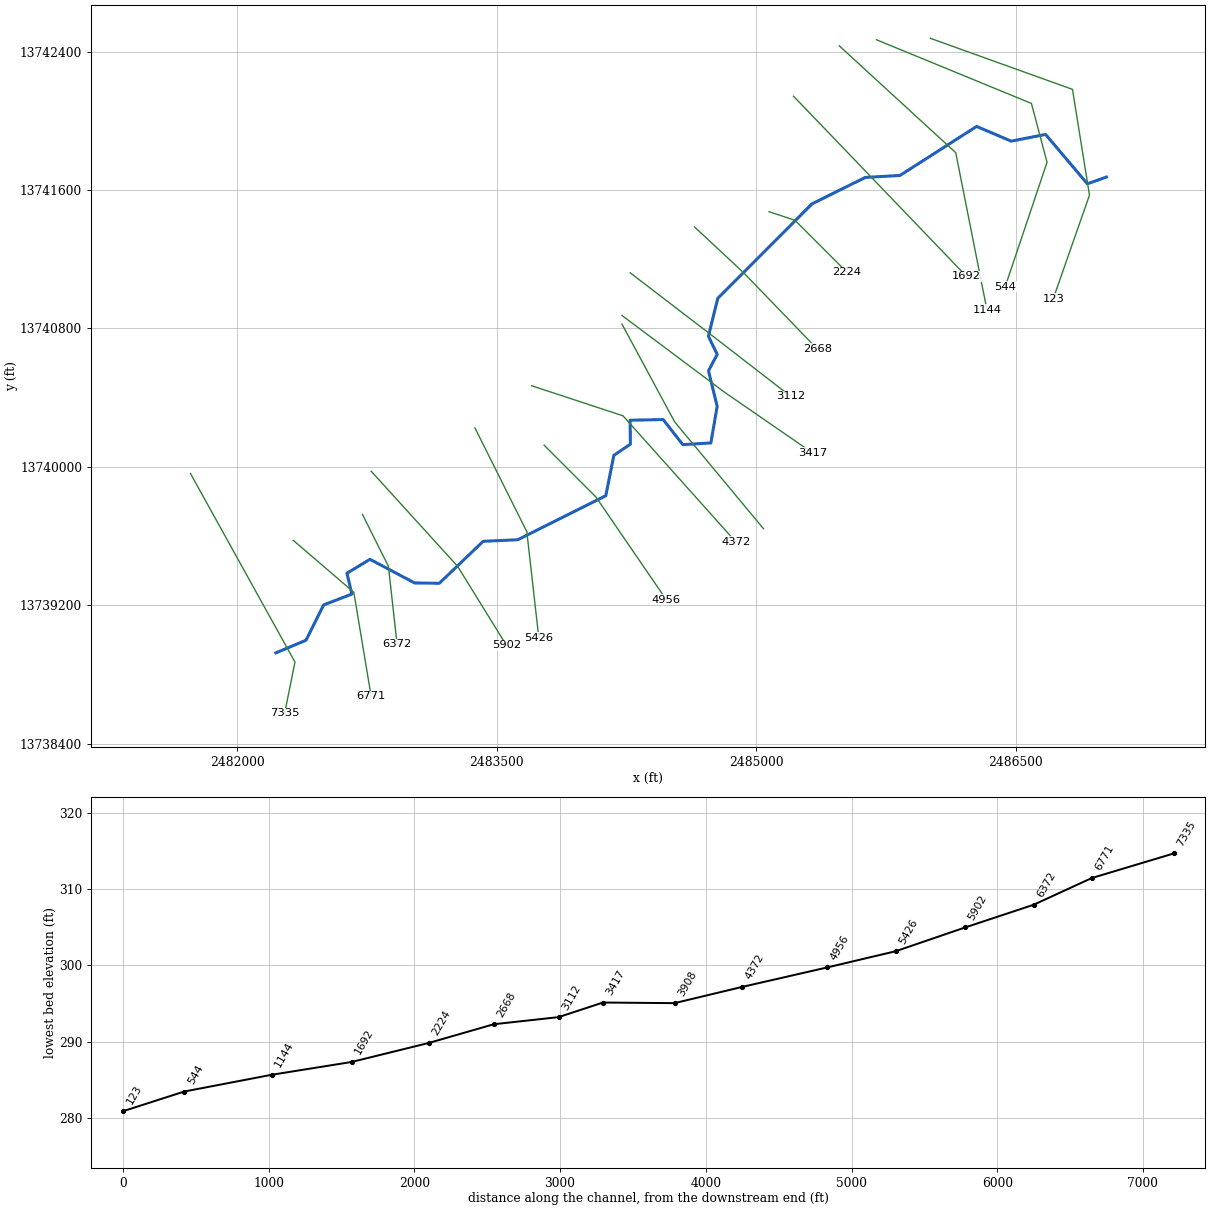
--- Stream0481.prj (project) ---

Proj Title=Stream0481 Base Level Engineering
Current Plan=p01
Default Exp/Contr=0.3,0.1
English Units
Geom File=g01
Flow File=f01
Plan File=p01
BEGIN DESCRIPTION:
Stream0481
END DESCRIPTION:

--- Stream0481.p01 (plan) ---

Plan Title=Multiple Run
Short Identifier=Multiple
Geom File=g01
Flow File=f01
Subcritical Flow
K Sum by GR= 0
Std Step Tol= 0.01
Critical Tol= 0.01
Num of Std Step Trials= 20
Max Error Tol= 0.3
Flow Tol Ratio= 0.001
Split Flow NTrial= 30
Split Flow Tol= 0.02
Split Flow Ratio= 0.02
Log Output Level= 0
Friction Slope Method= 1
Unsteady Friction Slope Method= 2
Unsteady Bridges Friction Slope Method= 1
Parabolic Critical Depth
Global Vel Dist=  1 , 1 , 1
Global Log Level= 0
CheckData=True
Encroach Param= -1, 0, 0, 0
BEGIN DESCRIPTION:
Multiple Run
END DESCRIPTION:

--- Stream0481.f01 (steady flow) ---

Flow Title=Multiple
Number of Profiles=7
Profile Names=10-year,25-year,50-year,1pct_min,100-year,1pct_plu,500-year
River Rch & RM= Stream0481,Reach-1,7335
     455     716     945     605    1208    2410    1952
River Rch & RM= Stream0481,Reach-1,3417
     616     982    1308     844    1685    3361    2765
Boundary for River Rch & Prof#=Stream0481,Reach-1,1
Up Type=0
Dn Type=3
Dn Slope=0.005
Boundary for River Rch & Prof#=Stream0481,Reach-1,2
Up Type=0
Dn Type=3
Dn Slope=0.005
Boundary for River Rch & Prof#=Stream0481,Reach-1,3
Up Type=0
Dn Type=3
Dn Slope=0.005
Boundary for River Rch & Prof#=Stream0481,Reach-1,4
Up Type=0
Dn Type=3
Dn Slope=0.005
Boundary for River Rch & Prof#=Stream0481,Reach-1,5
Up Type=0
Dn Type=3
Dn Slope=0.005
Boundary for River Rch & Prof#=Stream0481,Reach-1,6
Up Type=0
Dn Type=3
Dn Slope=0.005
Boundary for River Rch & Prof#=Stream0481,Reach-1,7
Up Type=0
Dn Type=3
Dn Slope=0.005

--- Stream0481.g01 (geometry) ---

Geom Title=Existing Conditions

River Reach=Stream0481,Reach-1
Reach XY= 30
      2482225.00     13738925.00      2482398.85     13738997.85
      2482501.10     13739202.28      2482664.04     13739264.58
      2482635.07     13739385.00      2482768.38     13739465.61
      2483026.56     13739328.74      2483169.14     13739327.05
      2483422.55     13739569.54      2483623.45     13739578.75
      2484131.39     13739833.00      2484178.10     13740066.69
      2484273.39     13740130.88      2484271.99     13740269.55
      2484463.17     13740273.38      2484576.46     13740128.52
      2484738.74     13740138.19      2484775.20     13740350.08
      2484725.07     13740554.97      2484775.39     13740650.00
      2484724.72     13740754.82      2484778.48     13740973.73
      2485322.57     13741519.48      2485630.90     13741672.85
      2485831.66     13741684.31      2486274.90     13741967.69
      2486475.00     13741882.56      2486673.53     13741921.47
      2486914.94     13741635.98      2487025.00     13741675.00

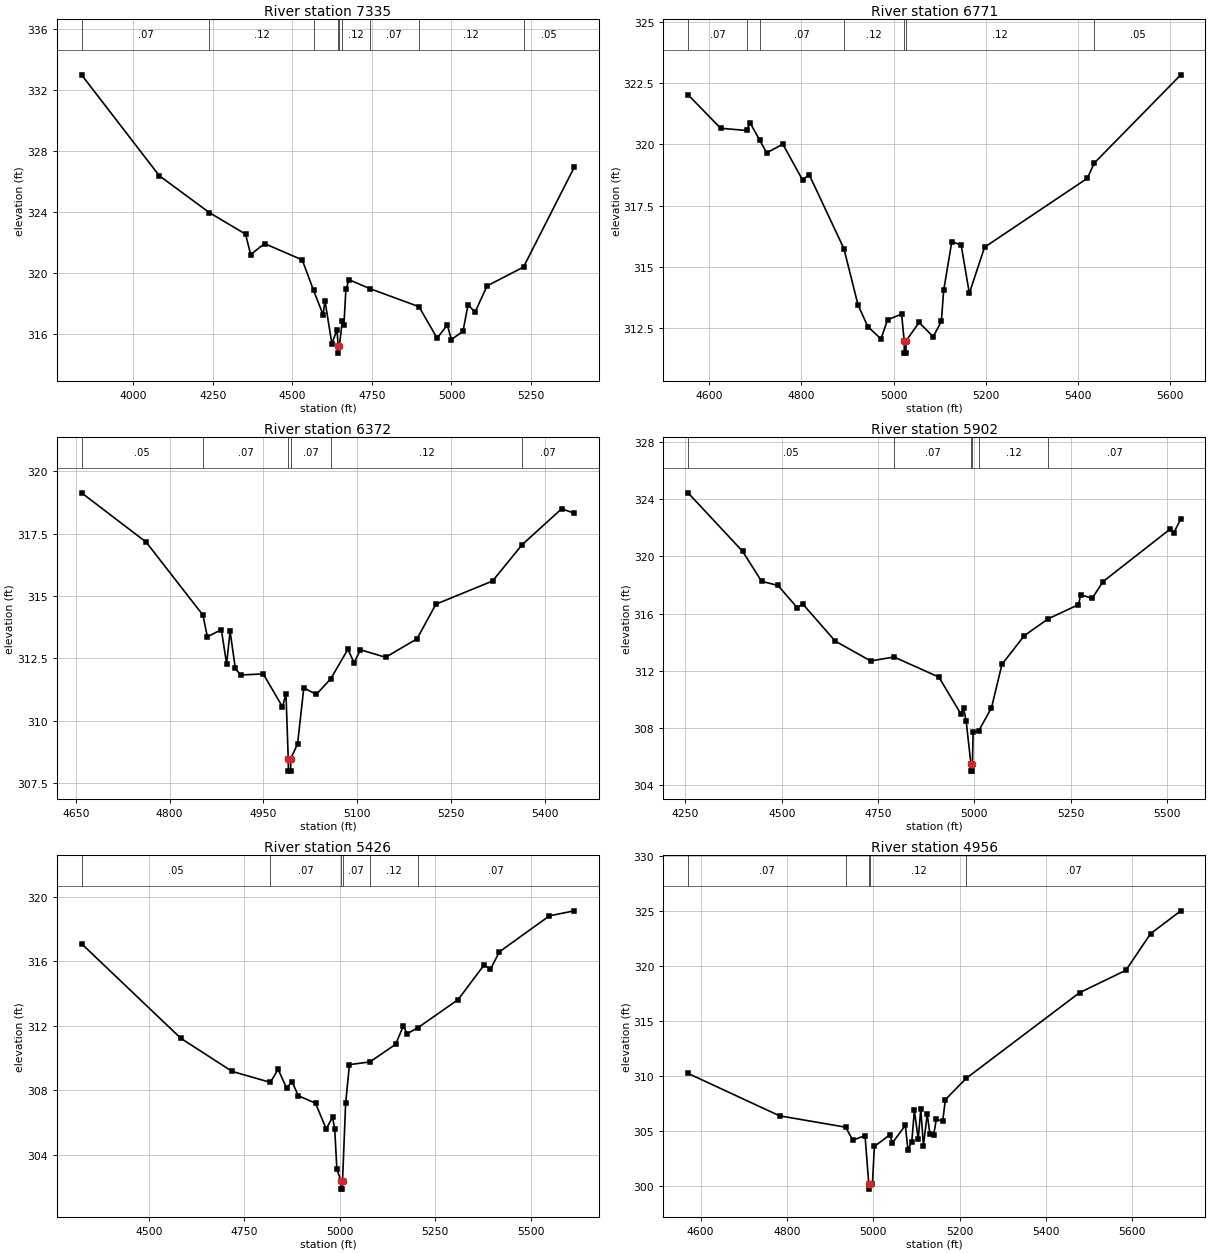
Type RM Length L Ch R = 1,7335,564,564,564
BEGIN DESCRIPTION:
Stream0481 15.0
END DESCRIPTION:
XS GIS Cut Line= 3
      2481730.58     13739961.77      2482334.72     13738871.53
      2482275.00     13738575.02
#Sta/Elev= 30
  3837.2  332.99  4081.4  326.37  4238.6  323.95  4352.7  322.53  4368.8  321.19
  4412.3  321.91  4530.9  320.84  4566.3  318.85  4596.6  317.23  4602.3  318.17
  4624.0  315.34  4640.1  316.25  4643.8  315.22  4644.0  314.72  4647.8  315.22
  4656.7  316.80  4661.8  316.54  4668.1  318.90  4677.9  319.54  4742.7  318.96
  4897.8  317.77  4954.9  315.70  4986.9  316.57  4999.6  315.61  5036.1  316.15
  5052.2  317.91  5073.9  317.40  5111.7  319.13  5226.4  320.37  5386.1  326.93
#Mann=9,-1,0
  3837.2    0.07       0  4238.6    0.12       0  4566.3    0.07       0
  4643.8    0.05       0  4647.8    0.07       0  4656.7    0.12       0
  4742.7    0.07       0  4897.8    0.12       0  5226.4    0.05       0
Bank Sta=4643.8,4647.8
Exp/Cntr=0.3,0.1

Type RM Length L Ch R = 1,6771,399,399,399
BEGIN DESCRIPTION:
Stream0481 14.0
END DESCRIPTION:
XS GIS Cut Line= 3
      2482324.99     13739575.01      2482675.00     13739275.00
      2482775.00     13738674.97
#Sta/Elev= 30
  4553.9  322.02  4624.7  320.65  4681.4  320.56  4688.4  320.88  4709.2  320.17
  4724.6  319.65  4759.7  320.00  4802.5  318.54  4816.8  318.76  4892.2  315.74
  4922.7  313.45  4944.1  312.56  4972.6  312.06  4986.9  312.84  5017.4  313.07
  5023.0  311.98  5023.3  311.48  5026.8  311.48  5027.0  311.98  5055.4  312.73
  5085.9  312.15  5103.6  312.77  5108.7  314.04  5126.4  316.03  5146.7  315.88
  5164.4  313.92  5197.4  315.80  5420.4  318.61  5435.4  319.23  5623.2  322.83
#Mann=7,-1,0
  4553.9    0.07       0  4681.4    0.05       0  4709.2    0.07       0
  4892.2    0.12       0  5023.0    0.05       0  5027.0    0.12       0
  5435.4    0.05       0
Bank Sta=5023,5027
Exp/Cntr=0.3,0.1

Type RM Length L Ch R = 1,6372,470,470,470
BEGIN DESCRIPTION:
Stream0481 13.0
END DESCRIPTION:
XS GIS Cut Line= 3
      2482725.00     13739724.99      2482875.00     13739425.00
      2482925.00     13738974.97
#Sta/Elev= 30
  4659.3  319.14  4762.7  317.16  4853.5  314.23  4860.5  313.36  4882.9  313.65
  4891.3  312.28  4896.9  313.58  4905.3  312.09  4913.6  311.83  4950.0  311.87
  4980.7  310.55  4986.3  311.08  4989.9  308.47  4990.2  307.97  4993.7  307.97
  4993.9  308.47  5004.8  309.06  5014.8  311.31  5034.9  311.05  5058.0  311.68
  5085.3  312.86  5095.3  312.32  5105.4  312.84  5145.6  312.54  5195.9  313.28
  5226.1  314.67  5316.7  315.60  5364.1  317.06  5427.3  318.50  5447.5  318.32
#Mann=6,-1,0
  4659.3    0.05       0  4853.5    0.07       0  4989.9    0.05       0
  4993.9    0.07       0  5058.0    0.12       0  5364.1    0.07       0
Bank Sta=4989.9,4993.9
Exp/Cntr=0.3,0.1

Type RM Length L Ch R = 1,5902,476,476,476
BEGIN DESCRIPTION:
Stream0481 12.0
END DESCRIPTION:
XS GIS Cut Line= 3
      2482775.02     13739974.98      2483275.00     13739425.00
      2483556.57     13738969.36
#Sta/Elev= 30
  4256.7  324.43  4398.2  320.35  4447.6  318.25  4490.1  317.96  4540.1  316.41
  4554.0  316.68  4638.8  314.07  4730.7  312.69  4791.5  312.96  4907.7  311.56
  4964.5  309.00  4971.9  309.38  4978.7  308.47  4990.9  305.49  4991.1  304.99
  4994.6  304.99  4994.9  305.49  4996.6  307.70  5011.2  307.81  5044.3  309.41
  5071.5  312.45  5129.4  314.45  5191.5  315.63  5270.1  316.62  5276.0  317.31
  5305.6  317.06  5333.9  318.23  5507.7  321.89  5517.2  321.63  5535.6  322.60
#Mann=6,-1,0
  4256.7    0.05       0  4791.5    0.07       0  4990.9    0.05       0
  4994.9    0.07       0  5011.2    0.12       0  5191.5    0.07       0
Bank Sta=4990.9,4994.9
Exp/Cntr=0.3,0.1

Type RM Length L Ch R = 1,5426,470,470,470
BEGIN DESCRIPTION:
Stream0481 11.0
END DESCRIPTION:
XS GIS Cut Line= 3
      2483374.98     13740225.03      2483675.00     13739625.00
      2483744.45     13739010.37
#Sta/Elev= 30
  4324.3  317.09  4584.3  311.22  4718.4  309.17  4818.5  308.49  4838.6  309.30
  4861.0  308.13  4875.0  308.54  4891.7  307.66  4936.5  307.20  4964.4  305.61
  4981.2  306.33  4986.8  305.59  4992.4  303.11  5003.2  302.37  5003.5  301.87
  5007.0  301.87  5007.2  302.37  5015.3  307.19  5025.3  309.59  5078.8  309.76
  5146.1  310.85  5166.2  311.98  5176.3  311.51  5204.4  311.88  5309.5  313.62
  5377.6  315.77  5394.3  315.51  5417.8  316.59  5548.7  318.82  5613.7  319.13
#Mann=6,-1,0
  4324.3    0.05       0  4818.5    0.07       0  5003.2    0.05       0
  5007.2    0.07       0  5078.8    0.12       0  5204.4    0.07       0
Bank Sta=5003.2,5007.2
Exp/Cntr=0.3,0.1

Type RM Length L Ch R = 1,4956,584,584,584
BEGIN DESCRIPTION:
Stream0481 10.0
END DESCRIPTION:
XS GIS Cut Line= 3
      2483775.02     13740124.98      2484075.00     13739825.00
      2484480.25     13739233.08
#Sta/Elev= 30
  4571.0  310.24  4783.1  306.39  4936.3  305.36  4952.8  304.18  4981.1  304.60
  4989.7  300.24  4990.0  299.74  4993.7  300.24  4998.3  300.24  5002.7  303.61
  5038.6  304.67  5044.6  303.94  5074.5  305.53  5080.5  303.31  5089.4  304.03
  5095.4  306.89  5104.3  304.28  5110.3  306.99  5116.4  303.69  5125.2  306.55
  5131.3  304.77  5140.2  304.67  5146.2  306.08  5161.1  305.92  5167.2  307.86
  5216.0  309.81  5478.0  317.56  5585.6  319.60  5642.5  322.91  5712.6  324.99
#Mann=5,-1,0
  4571.0    0.07       0  4936.3    0.12       0  4989.7    0.05       0
  4993.7    0.12       0  5216.0    0.07       0
Bank Sta=4989.7,4993.7
Exp/Cntr=0.3,0.1

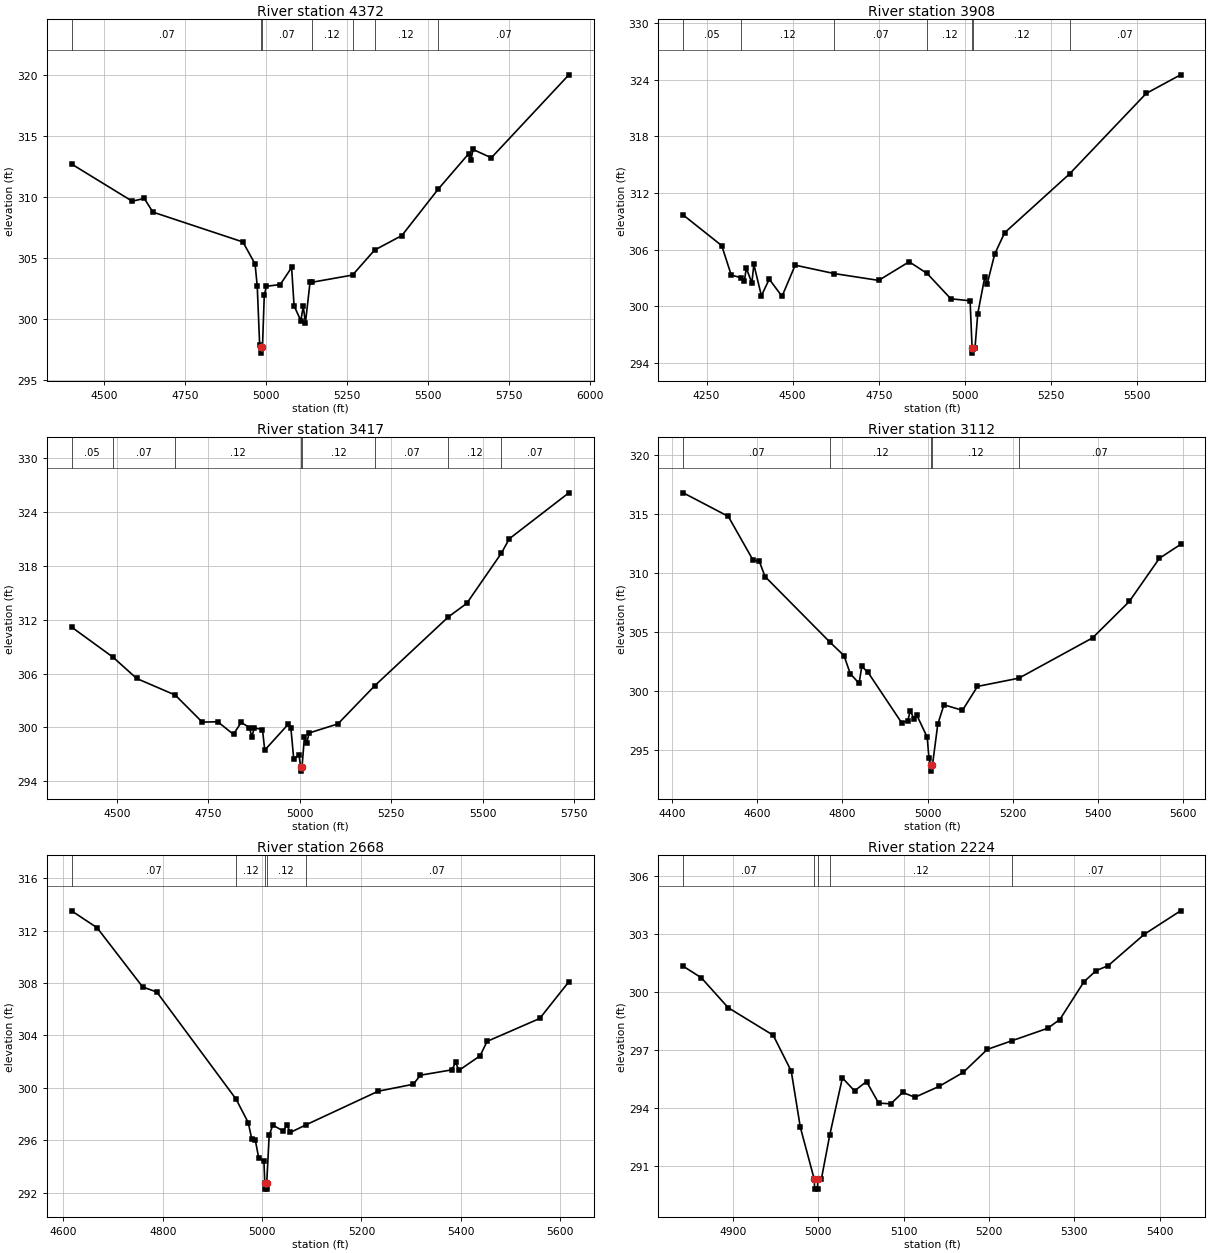
Type RM Length L Ch R = 1,4372,464,464,464
BEGIN DESCRIPTION:
Stream0481 9.0
END DESCRIPTION:
XS GIS Cut Line= 3
      2483702.75     13740468.76      2484230.56     13740295.14
      2484883.33     13739565.97
#Sta/Elev= 30
  4399.2  312.68  4586.5  309.63  4623.6  309.86  4650.1  308.74  4927.9  306.29
  4965.4  304.49  4972.1  302.68  4979.6  297.84  4984.3  297.68  4984.5  297.18
  4988.3  297.68  4993.8  301.93  5000.5  302.66  5043.1  302.80  5078.2  304.20
  5085.7  301.06  5106.6  299.84  5114.1  301.02  5120.8  299.66  5135.1  303.01
  5141.4  302.99  5266.2  303.58  5333.9  305.62  5418.4  306.82  5530.4  310.62
  5624.0  313.51  5630.7  312.97  5638.2  313.87  5694.3  313.19  5933.5  319.99
#Mann=7,-1,0
  4399.2    0.07       0  4984.3    0.05       0  4988.3    0.07       0
  5141.4    0.12       0  5266.2    0.07       0  5333.9    0.12       0
  5530.4    0.07       0
Bank Sta=4984.3,4988.3
Exp/Cntr=0.3,0.1

Type RM Length L Ch R = 1,3908,491,491,491
BEGIN DESCRIPTION:
Stream0481 8.0
END DESCRIPTION:
XS GIS Cut Line= 3
      2484225.00     13740824.99      2484529.17     13740260.42
      2485043.06     13739642.35
#Sta/Elev= 30
  4182.0  309.67  4293.9  306.43  4321.5  303.32  4350.6  303.02  4359.6  302.67
  4365.3  304.05  4381.5  302.48  4387.2  304.44  4409.2  301.12  4431.9  302.88
  4469.1  301.06  4507.3  304.36  4621.1  303.47  4749.9  302.75  4838.5  304.72
  4890.8  303.48  4959.6  300.80  5015.6  300.59  5021.4  295.55  5021.7  295.05
  5025.4  295.55  5029.9  295.62  5037.8  299.23  5058.6  303.16  5065.1  302.35
  5087.2  305.55  5115.9  307.79  5304.5  314.02  5527.3  322.54  5627.1  324.51
#Mann=7,-1,0
  4182.0    0.05       0  4350.6    0.12       0  4621.1    0.07       0
  4890.8    0.12       0  5021.4    0.05       0  5025.4    0.12       0
  5304.5    0.07       0
Bank Sta=5021.4,5025.4
Exp/Cntr=0.3,0.1

Type RM Length L Ch R = 1,3417,305,305,305
BEGIN DESCRIPTION:
Stream0481 7.0
END DESCRIPTION:
XS GIS Cut Line= 3
      2484225.03     13740874.97      2484813.89     13740434.03
      2485327.64     13740079.95
#Sta/Elev= 30
  4375.9  311.18  4489.3  307.82  4554.0  305.45  4659.5  303.60  4733.2  300.59
  4775.6  300.63  4818.7  299.22  4839.5  300.56  4862.4  299.98  4868.7  298.93
  4875.6  299.95  4897.9  299.76  4904.1  297.47  4968.7  300.37  4975.5  299.96
  4983.3  296.50  4997.9  296.92  5002.1  295.63  5002.4  295.13  5006.1  295.63
  5012.5  298.90  5018.7  298.27  5025.5  299.38  5104.1  300.39  5204.8  304.64
  5406.4  312.32  5456.2  313.81  5551.1  319.41  5572.6  321.01  5735.5  326.13
#Mann=8,-1,0
  4375.9    0.05       0  4489.3    0.07       0  4659.5    0.12       0
  5002.1    0.05       0  5006.1    0.12       0  5204.8    0.07       0
  5406.4    0.12       0  5551.1    0.07       0
Bank Sta=5002.1,5006.1
Exp/Cntr=0.3,0.1

Type RM Length L Ch R = 1,3112,444,444,444
BEGIN DESCRIPTION:
Stream0481 6.0
END DESCRIPTION:
XS GIS Cut Line= 3
      2484272.32     13741121.61      2484725.00     13740775.00
      2485198.50     13740408.84
#Sta/Elev= 30
  4425.9  316.83  4531.8  314.83  4589.9  311.12  4604.4  311.05  4618.2  309.72
  4771.1  304.14  4803.8  303.01  4818.4  301.48  4839.2  300.66  4845.5  302.10
  4860.0  301.60  4938.9  297.33  4953.4  297.47  4959.7  298.35  4968.0  297.63
  4974.3  298.00  4999.2  296.09  5003.3  294.35  5007.6  293.71  5007.9  293.21
  5011.6  293.71  5024.1  297.19  5038.6  298.84  5082.1  298.37  5117.4  300.40
  5214.7  301.10  5387.9  304.52  5474.2  307.61  5544.8  311.27  5594.6  312.45
#Mann=5,-1,0
  4425.9    0.07       0  4771.1    0.12       0  5007.6    0.05       0
  5011.6    0.12       0  5214.7    0.07       0
Bank Sta=5007.6,5011.6
Exp/Cntr=0.3,0.1

Type RM Length L Ch R = 1,2668,444,444,444
BEGIN DESCRIPTION:
Stream0481 5.0
END DESCRIPTION:
XS GIS Cut Line= 3
      2484644.24     13741386.70      2484925.00     13741125.00
      2485353.96     13740681.25
#Sta/Elev= 30
  4616.4  313.51  4667.8  312.22  4759.6  307.70  4787.9  307.32  4947.7  299.14
  4972.1  297.35  4979.0  296.13  4986.3  296.01  4993.1  294.68  5003.7  294.39
  5005.3  292.78  5005.5  292.28  5009.0  292.28  5009.3  292.78  5014.2  296.38
  5021.4  297.16  5042.5  296.72  5049.7  297.18  5056.7  296.60  5087.5  297.17
  5233.7  299.75  5304.4  300.28  5318.5  300.97  5382.1  301.38  5389.3  301.95
  5396.2  301.34  5438.7  302.45  5452.8  303.55  5558.8  305.30  5617.4  308.10
#Mann=5,-1,0
  4616.4    0.07       0  4947.7    0.12       0  5005.3    0.05       0
  5009.3    0.12       0  5087.5    0.07       0
Bank Sta=5005.3,5009.3
Exp/Cntr=0.3,0.1

Type RM Length L Ch R = 1,2224,532,532,532
BEGIN DESCRIPTION:
Stream0481 4.0
END DESCRIPTION:
XS GIS Cut Line= 3
      2485074.98     13741475.01      2485225.00     13741425.00
      2485525.00     13741125.00
#Sta/Elev= 30
  4841.9  301.33  4863.0  300.74  4894.6  299.19  4947.3  297.77  4968.4  295.92
  4979.0  293.03  4995.4  290.33  4995.7  289.83  4999.2  289.83  4999.4  290.33
  5003.6  290.33  5013.5  292.62  5028.3  295.57  5042.5  294.90  5056.6  295.38
  5070.7  294.27  5084.9  294.23  5099.0  294.82  5113.2  294.57  5141.5  295.13
  5169.7  295.85  5198.0  297.04  5226.4  297.48  5268.7  298.13  5282.9  298.58
  5311.2  300.53  5325.3  301.10  5339.5  301.36  5381.9  302.98  5424.3  304.19
#Mann=5,-1,0
  4841.9    0.07       0  4995.4    0.05       0  4999.4    0.07       0
  5013.5    0.12       0  5226.4    0.07       0
Bank Sta=4995.4,4999.4
Exp/Cntr=0.3,0.1

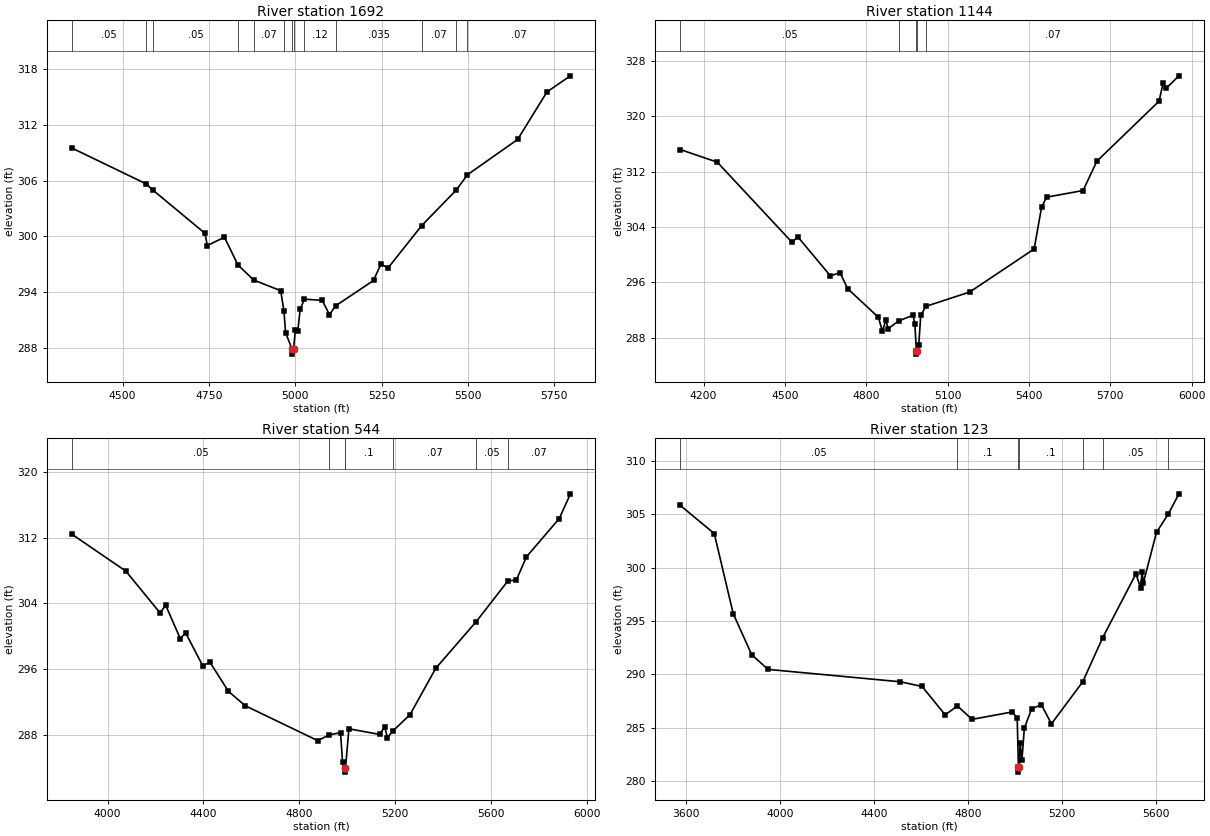
Type RM Length L Ch R = 1,1692,548,548,548
BEGIN DESCRIPTION:
XS6916
END DESCRIPTION:
XS GIS Cut Line= 2
      2485216.68     13742142.34      2486216.70     13741100.66
#Sta/Elev= 30
  4352.4  309.53  4568.4  305.65  4586.9  305.01  4738.2  300.34  4745.4  299.01
  4794.8  299.91  4834.1  296.91  4879.9  295.29  4957.7  294.15  4967.0  291.97
  4971.8  289.63  4990.9  287.82  4991.2  287.32  4994.9  287.82  5000.1  289.92
  5007.1  289.80  5014.1  292.17  5026.4  293.24  5077.8  293.11  5098.9  291.57
  5116.3  292.51  5226.3  295.25  5247.6  297.00  5268.7  296.61  5365.5  301.15
  5465.9  304.99  5498.4  306.64  5643.6  310.44  5728.5  315.56  5796.4  317.29
#Mann=13,-1,0
  4352.4    0.05       0  4568.4   0.035       0  4586.9    0.05       0
  4834.1   0.035       0  4879.9    0.07       0  4967.0   0.035       0
  4990.9   0.035       0  4994.9   0.035       0  5026.4    0.12       0
  5116.3   0.035       0  5365.5    0.07       0  5465.9   0.035       0
  5498.4    0.07       0
Bank Sta=4990.9,4994.9
Exp/Cntr=0.3,0.1

Type RM Length L Ch R = 1,1144,600,600,600
BEGIN DESCRIPTION:
XS6915
END DESCRIPTION:
XS GIS Cut Line= 3
      2485480.58     13742434.00      2486154.17     13741815.97
      2486334.35     13740908.13
#Sta/Elev= 30
  4113.6  315.22  4250.6  313.39  4526.7  301.79  4547.1  302.62  4668.0  296.95
  4703.2  297.43  4731.5  295.10  4845.0  290.96  4859.2  288.99  4873.3  290.59
  4880.1  289.30  4919.6  290.44  4972.6  291.26  4979.4  290.01  4984.8  286.14
  4985.0  285.64  4988.8  286.14  4993.6  286.92  5001.0  291.24  5019.7  292.54
  5181.7  294.62  5419.3  300.84  5446.7  306.90  5465.3  308.33  5599.7  309.29
  5650.6  313.53  5879.8  322.20  5895.3  324.88  5905.5  324.04  5953.3  325.87
#Mann=5,-1,0
  4113.6    0.05       0  4919.6    0.12       0  4984.8    0.05       0
  4988.8    0.12       0  5019.7    0.07       0
Bank Sta=4984.8,4988.8
Exp/Cntr=0.3,0.1

Type RM Length L Ch R = 1,544,421,421,421
BEGIN DESCRIPTION:
XS6914
END DESCRIPTION:
XS GIS Cut Line= 4
      2485695.86     13742468.74      2486591.67     13742100.69
      2486681.94     13741760.42      2486439.76     13741040.79
#Sta/Elev= 30
  3850.3  312.46  4076.4  307.94  4218.9  302.85  4242.8  303.77  4303.4  299.71
  4325.5  300.42  4397.5  296.38  4426.8  296.85  4504.1  293.29  4573.7  291.54
  4876.4  287.28  4925.5  287.99  4971.5  288.25  4979.8  284.73  4988.2  283.94
  4988.4  283.44  4992.2  283.94  5006.5  288.72  5135.0  288.03  5155.7  288.97
  5167.0  287.63  5189.5  288.45  5260.9  290.43  5368.4  296.09  5536.9  301.77
  5670.3  306.78  5704.1  306.82  5746.4  309.67  5883.5  314.35  5930.1  317.36
#Mann=7,-1,0
  3850.3    0.05       0  4925.5     0.1       0  4988.2    0.05       0
  4992.2     0.1       0  5189.5    0.07       0  5536.9    0.05       0
  5670.3    0.07       0
Bank Sta=4988.2,4992.2
Exp/Cntr=0.3,0.1

Type RM Length L Ch R = 1,123,0,0,0
BEGIN DESCRIPTION:
E21100
END DESCRIPTION:
XS GIS Cut Line= 4
      2486008.07     13742476.90      2486828.92     13742181.91
      2486927.25     13741570.54      2486717.77     13740972.01
#Sta/Elev= 30
  3573.6  305.84  3719.1  303.19  3799.9  295.69  3878.5  291.85  3948.2  290.47
  4512.1  289.31  4604.8  288.87  4702.8  286.22  4755.5  287.04  4817.5  285.79
  4989.7  286.49  5009.9  285.89  5015.2  281.35  5015.4  280.85  5019.2  281.35
  5022.3  283.62  5030.2  282.00  5040.3  284.95  5070.9  286.75  5112.7  287.18
  5155.7  285.37  5289.0  289.30  5373.8  293.42  5516.0  299.42  5536.4  298.05
  5541.7  299.60  5547.7  298.59  5603.8  303.32  5653.3  305.00  5699.2  306.91
#Mann=7,-1,0
  3573.6    0.05       0  4755.5     0.1       0  5015.2    0.05       0
  5019.2     0.1       0  5289.0    0.07       0  5373.8    0.05       0
  5653.3    0.07       0
Bank Sta=5015.2,5019.2
Exp/Cntr=0.3,0.1

Chan Stop Cuts=-1