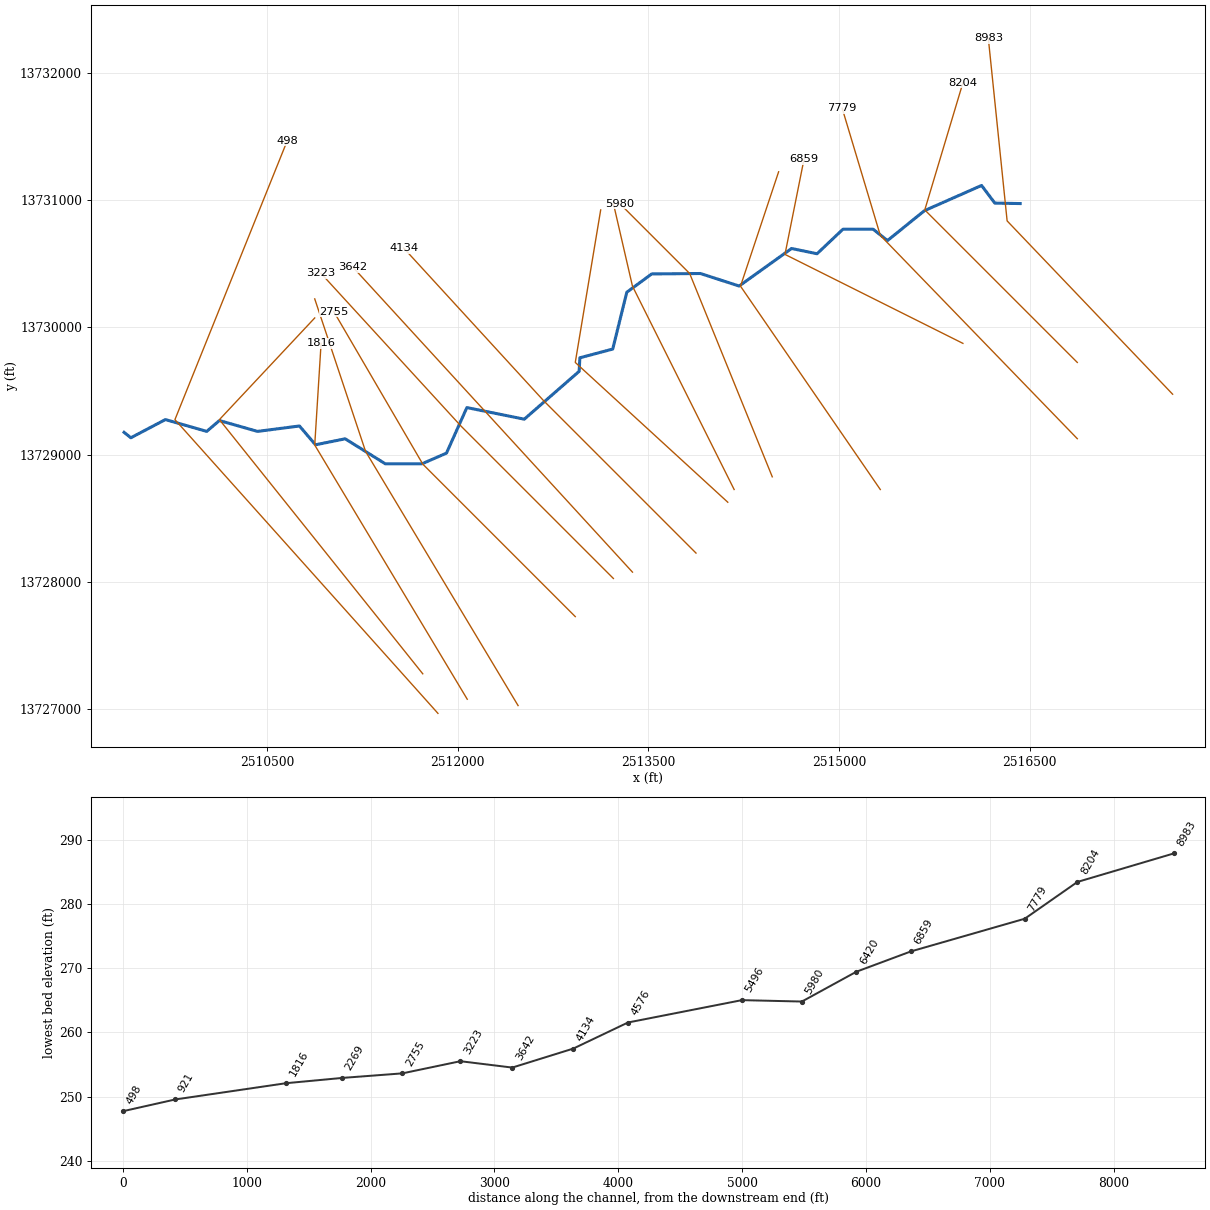
--- Stream0484.prj (project) ---

Proj Title=Stream0484 Base Level Engineering
Current Plan=p01
Default Exp/Contr=0.3,0.1
English Units
Geom File=g01
Flow File=f01
Plan File=p01
BEGIN DESCRIPTION:
Stream0484
END DESCRIPTION:

--- Stream0484.p01 (plan) ---

Plan Title=Multiple Run
Short Identifier=Multiple
Geom File=g01
Flow File=f01
Subcritical Flow
K Sum by GR= 0
Std Step Tol= 0.01
Critical Tol= 0.01
Num of Std Step Trials= 20
Max Error Tol= 0.3
Flow Tol Ratio= 0.001
Split Flow NTrial= 30
Split Flow Tol= 0.02
Split Flow Ratio= 0.02
Log Output Level= 0
Friction Slope Method= 1
Unsteady Friction Slope Method= 2
Unsteady Bridges Friction Slope Method= 1
Parabolic Critical Depth
Global Vel Dist=  1 , 1 , 1
Global Log Level= 0
CheckData=True
Encroach Param= -1, 0, 0, 0
BEGIN DESCRIPTION:
Multiple Run
END DESCRIPTION:

--- Stream0484.f01 (steady flow) ---

Flow Title=Multiple
Number of Profiles=7
Profile Names=10-year,25-year,50-year,1pct_min,100-year,1pct_plu,500-year
River Rch & RM= Stream0484,Reach-1,8983
     833    1363    1850    1217    2428    4844    4137
River Rch & RM= Stream0484,Reach-1,6859
    1207    2007    2752    1825    3641    7265    6314
Boundary for River Rch & Prof#=Stream0484,Reach-1,1
Up Type=0
Dn Type=3
Dn Slope=0.005
Boundary for River Rch & Prof#=Stream0484,Reach-1,2
Up Type=0
Dn Type=3
Dn Slope=0.005
Boundary for River Rch & Prof#=Stream0484,Reach-1,3
Up Type=0
Dn Type=3
Dn Slope=0.005
Boundary for River Rch & Prof#=Stream0484,Reach-1,4
Up Type=0
Dn Type=3
Dn Slope=0.005
Boundary for River Rch & Prof#=Stream0484,Reach-1,5
Up Type=0
Dn Type=3
Dn Slope=0.005
Boundary for River Rch & Prof#=Stream0484,Reach-1,6
Up Type=0
Dn Type=3
Dn Slope=0.005
Boundary for River Rch & Prof#=Stream0484,Reach-1,7
Up Type=0
Dn Type=3
Dn Slope=0.005

--- Stream0484.g01 (geometry) ---

Geom Title=Existing Conditions

River Reach=Stream0484,Reach-1
Reach XY= 30
      2516425.00     13730975.00      2516226.25     13730978.44
      2516121.85     13731117.47      2515672.70     13730919.17
      2515381.66     13730683.98      2515269.15     13730772.92
      2515030.85     13730772.94      2514827.30     13730580.09
      2514626.50     13730621.53      2514214.56     13730326.05
      2513909.84     13730424.61      2513526.55     13730421.25
      2513330.52     13730277.44      2513219.62     13729830.19
      2512961.00     13729761.38      2512955.63     13729655.00
      2512523.75     13729278.45      2512072.03     13729369.60
      2511911.55     13729011.37      2511719.06     13728927.26
      2511430.86     13728927.07      2511114.52     13729124.06
      2510880.88     13729076.96      2510754.81     13729224.96
      2510424.90     13729182.34      2510124.90     13729267.66
      2510025.10     13729182.34      2509699.89     13729275.31
      2509428.33     13729132.29      2509375.00     13729175.00

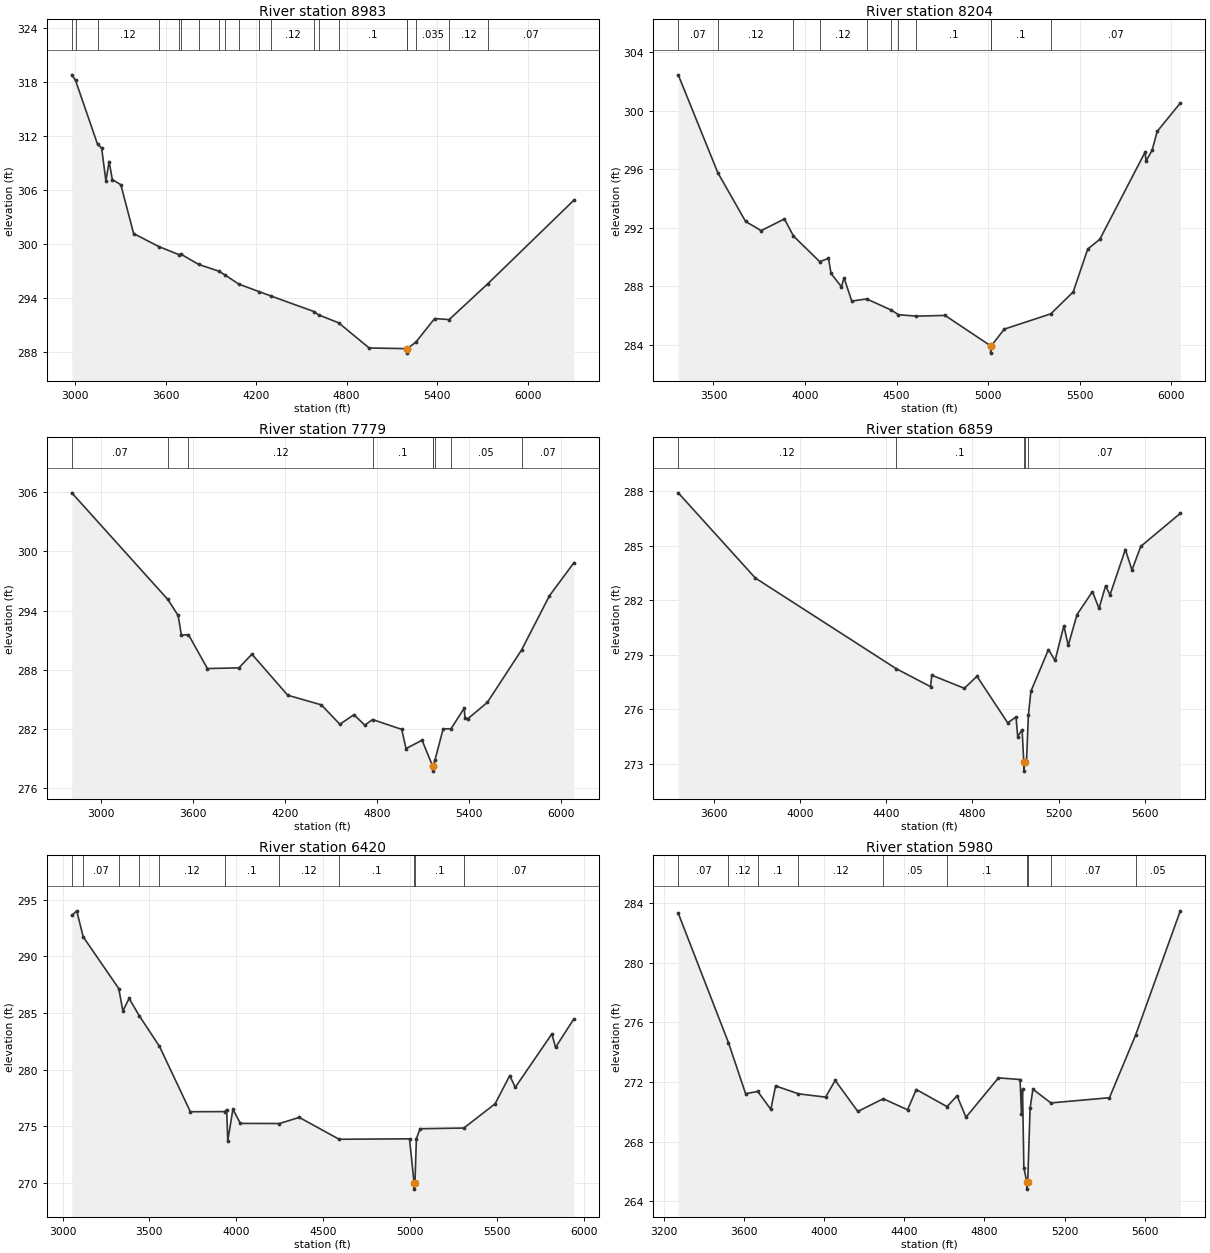
Type RM Length L Ch R = 1,8983,779,779,779
BEGIN DESCRIPTION:
Stream0484 16.0
END DESCRIPTION:
XS GIS Cut Line= 3
      2517625.03     13729474.97      2516322.97     13730838.53
      2516175.00     13732275.04
#Sta/Elev= 30
  2977.6  318.79  3002.6  318.17  3149.0  311.05  3175.6  310.65  3203.9  307.00
  3225.3  309.15  3246.4  307.15  3303.0  306.57  3387.9  301.14  3556.0  299.69
  3686.7  298.81  3702.9  298.84  3819.2  297.71  3951.8  296.97  3996.7  296.51
  4084.4  295.53  4219.2  294.69  4297.2  294.21  4584.3  292.47  4614.6  292.10
  4747.2  291.22  4949.9  288.42  5199.2  288.35  5199.5  287.85  5203.2  288.35
  5260.4  289.09  5383.6  291.69  5480.3  291.58  5736.3  295.56  6307.1  304.85
#Mann=20,-1,0
  2977.6    0.12       0  3002.6    0.07       0  3149.0    0.12       0
  3556.0    0.12       0  3686.7   0.035       0  3702.9    0.07       0
  3819.2   0.035       0  3951.8    0.12       0  3996.7   0.035       0
  4084.4    0.12       0  4219.2   0.035       0  4297.2    0.12       0
  4584.3     0.1       0  4614.6    0.12       0  4747.2     0.1       0
  5199.2    0.05       0  5203.2     0.1       0  5260.4   0.035       0
  5480.3    0.12       0  5736.3    0.07       0
Bank Sta=5199.2,5203.2
Exp/Cntr=0.3,0.1

Type RM Length L Ch R = 1,8204,425,425,425
BEGIN DESCRIPTION:
Stream0484 15.0
END DESCRIPTION:
XS GIS Cut Line= 3
      2516875.01     13729724.99      2515675.00     13730925.00
      2515975.00     13731925.00
#Sta/Elev= 30
  3307.7  302.45  3523.6  295.76  3675.4  292.42  3760.3  291.79  3887.5  292.59
  3936.8  291.42  4080.1  289.67  4128.0  289.89  4142.1  288.86  4198.7  287.95
  4212.8  288.56  4255.2  286.97  4336.2  287.12  4471.6  286.35  4509.9  286.04
  4607.0  285.94  4764.4  285.99  5013.2  283.91  5013.5  283.41  5017.2  283.91
  5087.4  285.05  5342.0  286.10  5464.1  287.60  5543.3  290.53  5609.4  291.20
  5856.5  297.16  5861.7  296.55  5894.8  297.29  5922.6  298.58  6048.8  300.52
#Mann=11,-1,0
  3307.7    0.07       0  3523.6    0.12       0  3936.8   0.035       0
  4080.1    0.12       0  4336.2    0.07       0  4471.6    0.12       0
  4509.9    0.07       0  4607.0     0.1       0  5013.2    0.05       0
  5017.2     0.1       0  5342.0    0.07       0
Bank Sta=5013.2,5017.2
Exp/Cntr=0.3,0.1

Type RM Length L Ch R = 1,7779,920,920,920
BEGIN DESCRIPTION:
Stream0484 14.0
END DESCRIPTION:
XS GIS Cut Line= 3
      2516875.01     13729124.99      2515325.00     13730725.00
      2515025.00     13731724.99
#Sta/Elev= 30
  2809.6  305.96  3435.3  295.13  3502.7  293.50  3523.8  291.51  3570.2  291.55
  3693.6  288.11  3898.6  288.18  3983.5  289.57  4216.8  285.40  4436.2  284.42
  4556.4  282.45  4648.2  283.42  4719.0  282.36  4769.6  282.93  4959.5  281.93
  4987.8  279.98  5092.1  280.83  5161.4  278.19  5161.7  277.69  5165.5  278.19
  5176.3  278.82  5229.6  281.97  5281.1  282.00  5367.0  284.09  5372.2  283.06
  5392.2  283.03  5517.5  284.67  5740.4  289.99  5922.1  295.50  6081.3  298.85
#Mann=9,-1,0
  2809.6    0.07       0  3435.3   0.035       0  3570.2    0.12       0
  4769.6     0.1       0  5161.4    0.05       0  5165.5     0.1       0
  5176.3    0.07       0  5281.1    0.05       0  5740.4    0.07       0
Bank Sta=5161.4,5165.5
Exp/Cntr=0.3,0.1

Type RM Length L Ch R = 1,6859,439,439,439
BEGIN DESCRIPTION:
Stream0484 13.0
END DESCRIPTION:
XS GIS Cut Line= 3
      2515974.99     13729875.00      2514575.00     13730575.00
      2514725.00     13731325.01
#Sta/Elev= 30
  3434.7  287.92  3792.5  283.23  4446.2  278.24  4605.8  277.25  4611.4  277.88
  4762.4  277.16  4821.1  277.82  4963.6  275.26  5002.5  275.58  5010.1  274.50
  5030.5  274.89  5038.4  273.10  5038.7  272.60  5043.1  273.10  5050.9  273.12
  5059.7  275.67  5071.3  276.99  5152.9  279.29  5183.5  278.69  5224.3  280.60
  5244.7  279.52  5285.5  281.22  5356.9  282.48  5387.5  281.56  5418.1  282.80
  5438.5  282.30  5509.8  284.80  5540.4  283.67  5581.2  284.97  5764.8  286.79
#Mann=5,-1,0
  3434.7    0.12       0  4446.2     0.1       0  5038.4    0.05       0
  5043.1     0.1       0  5059.7    0.07       0
Bank Sta=5038.4,5043.1
Exp/Cntr=0.3,0.1

Type RM Length L Ch R = 1,6420,440,440,440
BEGIN DESCRIPTION:
Stream0484 12.0
END DESCRIPTION:
XS GIS Cut Line= 3
      2515324.98     13728725.03      2514225.00     13730325.00
      2514525.00     13731225.00
#Sta/Elev= 30
  3053.0  293.60  3081.4  294.01  3119.0  291.71  3323.5  287.15  3347.2  285.17
  3383.1  286.28  3440.7  284.77  3557.9  282.05  3735.6  276.28  3933.0  276.29
  3944.6  276.47  3951.0  273.72  3980.5  276.49  4023.8  275.25  4248.5  275.24
  4362.8  275.78  4592.2  273.85  4997.3  273.89  5023.8  269.95  5024.2  269.45
  5028.6  269.95  5036.8  273.89  5057.9  274.78  5309.9  274.84  5490.0  276.98
  5574.4  279.47  5606.0  278.43  5816.8  283.15  5837.9  281.96  5943.3  284.47
#Mann=11,-1,0
  3053.0    0.05       0  3119.0    0.07       0  3323.5   0.035       0
  3440.7    0.07       0  3557.9    0.12       0  3933.0     0.1       0
  4248.5    0.12       0  4592.2     0.1       0  5023.8    0.05       0
  5028.6     0.1       0  5309.9    0.07       0
Bank Sta=5023.8,5028.6
Exp/Cntr=0.3,0.1

Type RM Length L Ch R = 1,5980,484,484,484
BEGIN DESCRIPTION:
Stream0484 11.0
END DESCRIPTION:
XS GIS Cut Line= 3
      2514475.00     13728825.00      2513825.00     13730425.00
      2513275.00     13730975.00
#Sta/Elev= 30
  3272.9  283.31  3523.5  274.63  3609.0  271.21  3669.5  271.36  3734.7  270.16
  3758.6  271.73  3872.8  271.20  4007.9  270.98  4056.1  272.10  4168.8  270.02
  4295.7  270.87  4417.0  270.13  4460.4  271.49  4614.1  270.34  4663.8  271.07
  4708.5  269.63  4870.4  272.27  4978.3  272.16  4985.2  269.88  4990.5  271.53
  4997.2  266.24  5011.6  265.31  5011.9  264.81  5016.5  265.31  5028.2  270.23
  5042.3  271.51  5132.0  270.59  5424.2  270.94  5554.4  275.13  5777.7  283.47
#Mann=10,-1,0
  3272.9    0.07       0  3523.5    0.12       0  3669.5     0.1       0
  3872.8    0.12       0  4295.7    0.05       0  4614.1     0.1       0
  5011.6    0.05       0  5016.5     0.1       0  5132.0    0.07       0
  5554.4    0.05       0
Bank Sta=5011.6,5016.5
Exp/Cntr=0.3,0.1

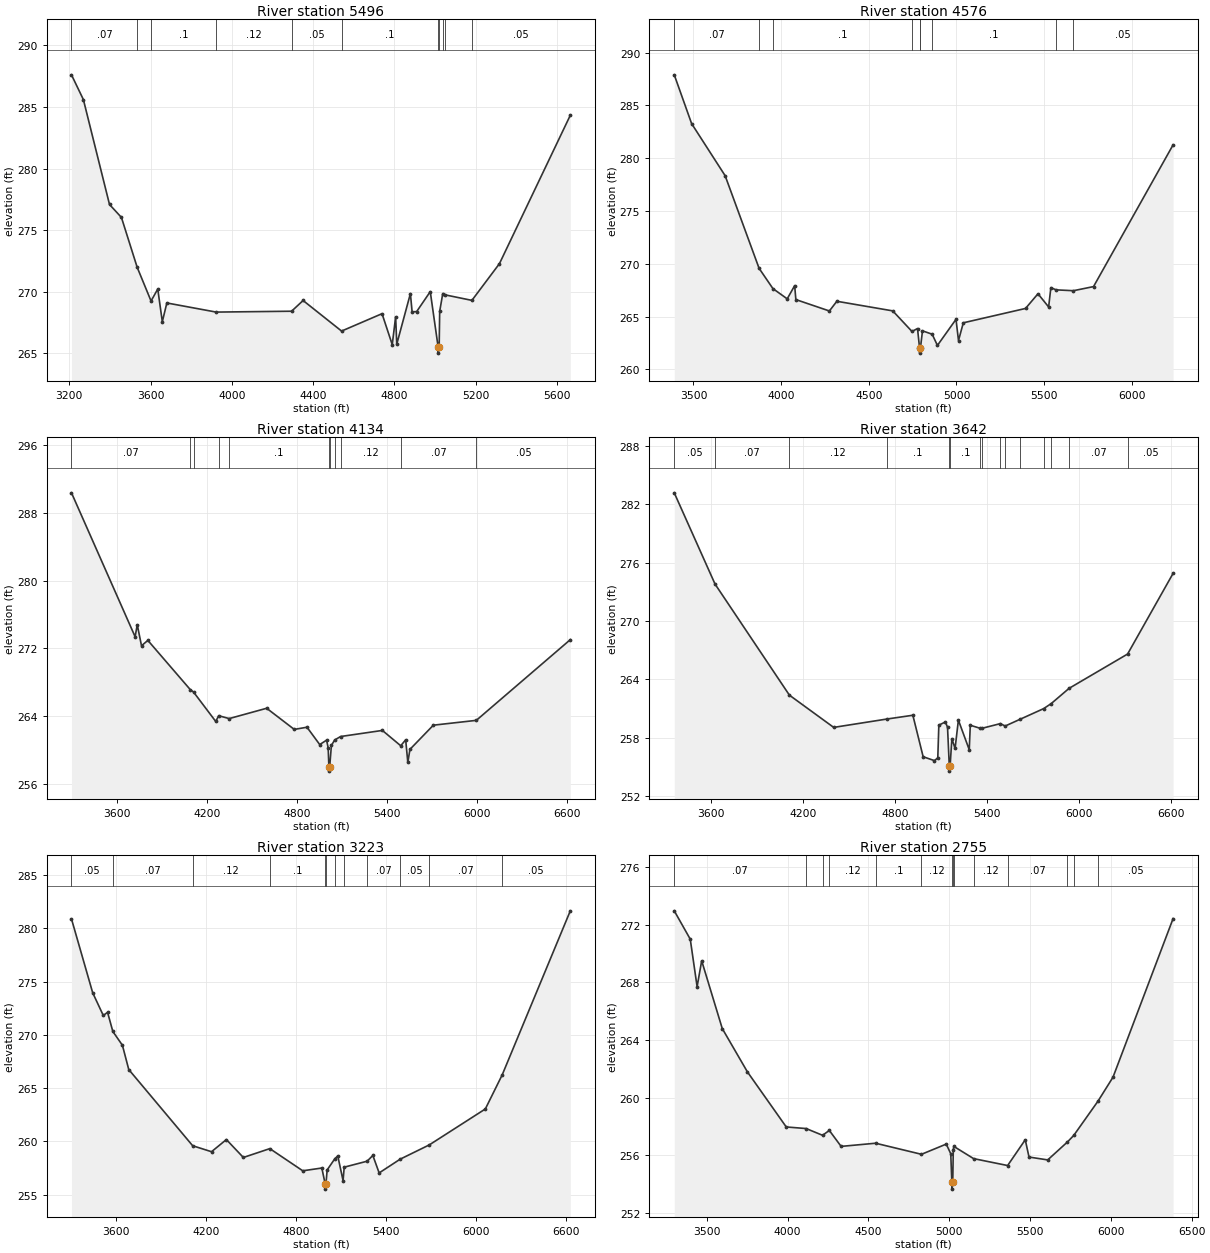
Type RM Length L Ch R = 1,5496,920,920,920
BEGIN DESCRIPTION:
Stream0484 10.0
END DESCRIPTION:
XS GIS Cut Line= 3
      2514174.98     13728725.04      2513375.00     13730325.00
      2513225.00     13730975.01
#Sta/Elev= 30
  3210.6  287.61  3269.2  285.60  3397.8  277.09  3456.5  276.04  3533.9  272.00
  3602.3  269.26  3635.4  270.23  3657.8  267.58  3680.1  269.10  3922.9  268.36
  4294.3  268.43  4350.9  269.30  4540.4  266.82  4739.5  268.23  4789.8  265.72
  4806.5  267.97  4812.1  265.76  4879.2  269.86  4887.6  268.38  4910.0  268.40
  4977.0  270.02  5015.7  265.53  5016.1  265.03  5020.8  265.53  5023.4  268.42
  5038.5  269.86  5049.4  269.76  5182.0  269.31  5317.6  272.29  5666.5  284.33
#Mann=11,-1,0
  3210.6    0.07       0  3533.9    0.12       0  3602.3     0.1       0
  3922.9    0.12       0  4294.3    0.05       0  4540.4     0.1       0
  5015.7    0.05       0  5020.8     0.1       0  5038.5    0.12       0
  5049.4    0.07       0  5182.0    0.05       0
Bank Sta=5015.7,5020.8
Exp/Cntr=0.3,0.1

Type RM Length L Ch R = 1,4576,442,442,442
BEGIN DESCRIPTION:
Stream0484 9.0
END DESCRIPTION:
XS GIS Cut Line= 3
      2514125.01     13728624.99      2512925.00     13729725.00
      2513124.99     13730924.96
#Sta/Elev= 30
  3390.7  287.90  3489.7  283.28  3680.8  278.35  3874.4  269.58  3953.3  267.66
  4034.8  266.69  4077.3  267.94  4084.1  266.62  4275.3  265.54  4317.8  266.46
  4636.6  265.55  4746.3  263.60  4777.8  263.88  4789.4  262.05  4789.8  261.55
  4794.5  262.05  4806.2  263.66  4861.4  263.34  4891.3  262.28  4997.3  264.75
  5011.5  262.74  5038.9  264.42  5393.7  265.78  5464.7  267.17  5525.5  265.92
  5538.2  267.75  5568.2  267.54  5666.8  267.46  5781.5  267.85  6235.1  281.27
#Mann=9,-1,0
  3390.7    0.07       0  3874.4    0.12       0  3953.3     0.1       0
  4746.3    0.05       0  4789.4    0.05       0  4794.5    0.05       0
  4861.4     0.1       0  5568.2    0.12       0  5666.8    0.05       0
Bank Sta=4789.4,4794.5
Exp/Cntr=0.3,0.1

Type RM Length L Ch R = 1,4134,492,492,492
BEGIN DESCRIPTION:
Stream0484 8.0
END DESCRIPTION:
XS GIS Cut Line= 3
      2513874.98     13728225.02      2512675.00     13729425.00
      2511575.01     13730624.99
#Sta/Elev= 30
  3298.0  290.38  3722.2  273.37  3736.4  274.79  3764.7  272.31  3807.1  272.94
  4089.5  267.13  4111.8  266.83  4259.6  263.36  4279.2  264.04  4349.2  263.70
  4599.0  264.92  4782.9  262.42  4867.7  262.68  4952.6  260.63  4998.4  261.15
  5008.9  260.26  5013.7  257.99  5014.1  257.49  5018.9  257.99  5030.5  260.53
  5052.2  261.17  5091.7  261.58  5370.2  262.30  5492.5  260.49  5525.6  261.19
  5539.8  258.52  5554.0  260.06  5710.0  262.92  5996.4  263.49  6622.9  273.03
#Mann=11,-1,0
  3298.0    0.07       0  4089.5    0.12       0  4111.8    0.07       0
  4279.2    0.12       0  4349.2     0.1       0  5013.7    0.05       0
  5018.9     0.1       0  5052.2    0.07       0  5091.7    0.12       0
  5492.5    0.07       0  5996.4    0.05       0
Bank Sta=5013.7,5018.9
Exp/Cntr=0.3,0.1

Type RM Length L Ch R = 1,3642,419,419,419
BEGIN DESCRIPTION:
Stream0484 7.0
END DESCRIPTION:
XS GIS Cut Line= 3
      2513375.00     13728075.00      2512275.00     13729275.00
      2511174.98     13730475.03
#Sta/Elev= 30
  3358.4  283.18  3624.6  273.79  4109.9  262.36  4399.0  259.04  4746.0  259.90
  4915.7  260.29  4982.9  256.02  5056.9  255.62  5078.5  255.91  5085.3  259.27
  5127.8  259.60  5142.0  259.06  5153.6  255.04  5154.0  254.54  5158.8  255.04
  5170.3  257.88  5191.3  256.87  5212.9  259.79  5283.8  256.74  5290.6  259.26
  5357.1  258.94  5367.7  258.95  5487.3  259.43  5518.0  259.18  5617.5  259.89
  5769.0  260.97  5818.7  261.49  5935.5  263.06  6317.3  266.59  6614.2  274.89
#Mann=15,-1,0
  3358.4    0.05       0  3624.6    0.07       0  4109.9    0.12       0
  4746.0     0.1       0  5153.6    0.05       0  5158.8     0.1       0
  5357.1    0.07       0  5367.7     0.1       0  5487.3    0.05       0
  5518.0    0.07       0  5617.5    0.05       0  5769.0    0.07       0
  5818.7    0.05       0  5935.5    0.07       0  6317.3    0.05       0
Bank Sta=5153.6,5158.8
Exp/Cntr=0.3,0.1

Type RM Length L Ch R = 1,3223,468,468,468
BEGIN DESCRIPTION:
Stream0484 6.0
END DESCRIPTION:
XS GIS Cut Line= 3
      2513224.98     13728025.02      2512025.00     13729225.00
      2510925.01     13730424.99
#Sta/Elev= 30
  3303.1  280.88  3444.5  273.95  3515.2  271.82  3543.5  272.12  3578.8  270.32
  3642.5  269.03  3684.9  266.75  4110.9  259.60  4236.5  259.04  4335.5  260.18
  4448.6  258.50  4625.1  259.33  4844.6  257.25  4971.8  257.51  4993.8  256.03
  4994.2  255.53  4999.4  256.03  5007.2  257.33  5058.8  258.39  5078.1  258.64
  5113.3  256.33  5120.9  257.59  5273.6  258.15  5311.8  258.69  5353.8  257.05
  5493.9  258.34  5688.1  259.68  6061.6  263.05  6174.0  266.25  6628.0  281.64
#Mann=12,-1,0
  3303.1    0.05       0  3578.8    0.07       0  4110.9    0.12       0
  4625.1     0.1       0  4993.8    0.05       0  4999.4     0.1       0
  5058.8    0.12       0  5120.9     0.1       0  5273.6    0.07       0
  5493.9    0.05       0  5688.1    0.07       0  6174.0    0.05       0
Bank Sta=4993.8,4999.4
Exp/Cntr=0.3,0.1

Type RM Length L Ch R = 1,2755,486,486,486
BEGIN DESCRIPTION:
Stream0484 5.0
END DESCRIPTION:
XS GIS Cut Line= 3
      2512924.99     13727725.01      2511725.00     13728925.00
      2511024.99     13730125.01
#Sta/Elev= 30
  3298.8  272.98  3397.8  271.01  3440.2  267.71  3468.5  269.51  3595.8  264.80
  3751.3  261.79  3991.7  257.96  4114.8  257.85  4216.6  257.38  4258.1  257.72
  4331.2  256.61  4544.6  256.83  4828.4  256.06  4981.7  256.77  5009.5  256.10
  5016.2  254.14  5016.6  253.64  5021.8  254.14  5025.2  256.37  5028.4  256.61
  5151.0  255.76  5361.4  255.28  5470.5  257.07  5493.7  255.87  5609.4  255.67
  5731.8  256.92  5770.3  257.37  5920.9  259.76  6013.4  261.42  6385.1  272.44
#Mann=14,-1,0
  3298.8    0.07       0  4114.8    0.12       0  4216.6    0.07       0
  4258.1    0.12       0  4544.6     0.1       0  4828.4    0.12       0
  5016.2    0.05       0  5021.8    0.12       0  5028.4     0.1       0
  5151.0    0.12       0  5361.4    0.07       0  5731.8    0.05       0
  5770.3    0.07       0  5920.9    0.05       0
Bank Sta=5016.2,5021.8
Exp/Cntr=0.3,0.1

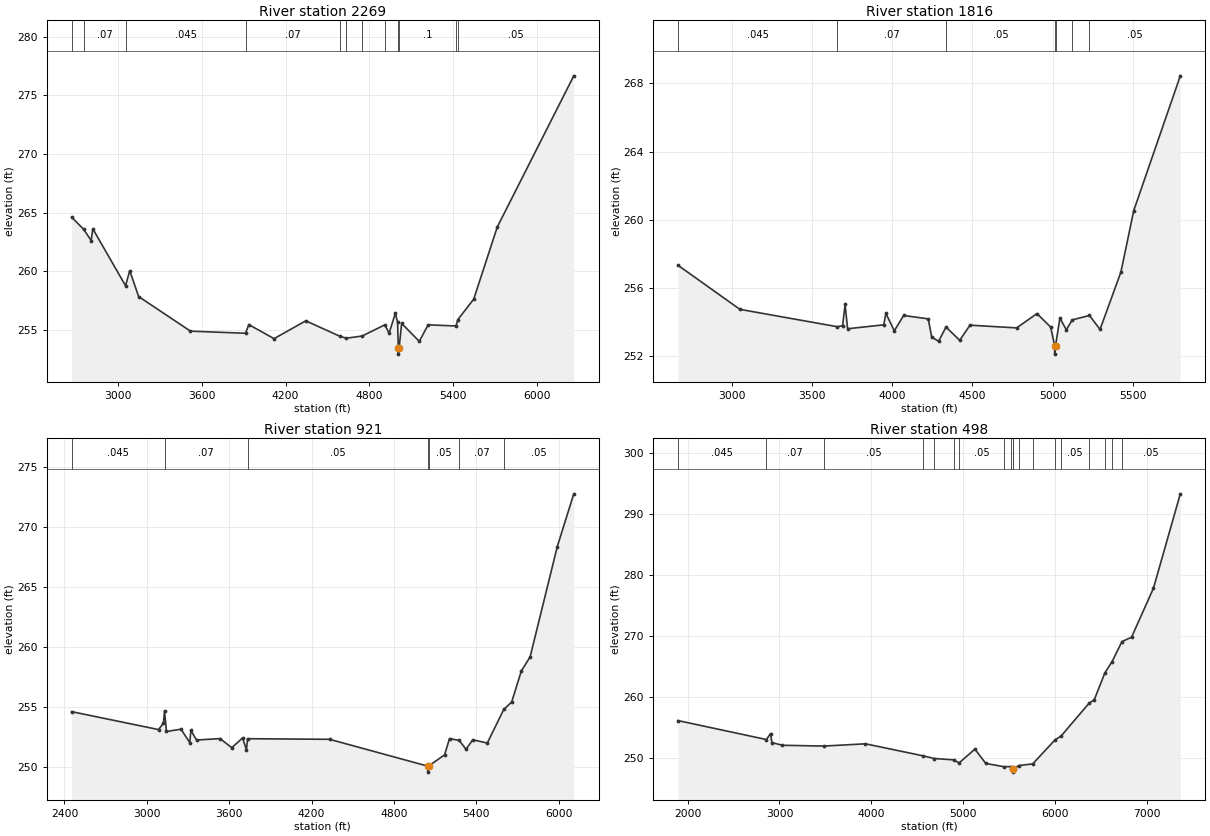
Type RM Length L Ch R = 1,2269,453,453,453
BEGIN DESCRIPTION:
Stream0484 4.0
END DESCRIPTION:
XS GIS Cut Line= 3
      2512475.02     13727024.97      2511275.00     13729025.00
      2510875.01     13730224.97
#Sta/Elev= 30
  2667.6  264.61  2753.3  263.58  2807.6  262.62  2819.2  263.62  3054.0  258.76
  3083.6  260.05  3147.7  257.84  3519.0  254.89  3913.2  254.71  3936.8  255.45
  4117.6  254.25  4345.0  255.77  4588.0  254.46  4634.3  254.29  4747.7  254.47
  4911.5  255.43  4941.7  254.71  4986.4  256.41  5002.7  255.67  5007.8  253.43
  5008.2  252.93  5013.4  253.43  5031.6  255.55  5158.1  254.02  5221.4  255.43
  5420.7  255.33  5434.6  255.88  5548.1  257.62  5716.8  263.77  6264.9  276.67
#Mann=12,-1,0
  2667.6   0.035       0  2753.3    0.07       0  3054.0   0.045       0
  3913.2    0.07       0  4588.0    0.12       0  4634.3    0.07       0
  4747.7    0.05       0  4911.5     0.1       0  5007.8    0.05       0
  5013.4     0.1       0  5420.7    0.07       0  5434.6    0.05       0
Bank Sta=5007.8,5013.4
Exp/Cntr=0.3,0.1

Type RM Length L Ch R = 1,1816,895,895,895
BEGIN DESCRIPTION:
Stream0484 3.0
END DESCRIPTION:
XS GIS Cut Line= 3
      2512075.02     13727074.96      2510875.00     13729075.00
      2510925.00     13729875.01
#Sta/Elev= 30
  2663.5  257.32  3048.4  254.74  3656.3  253.72  3689.8  253.78  3705.3  255.03
  3720.9  253.60  3946.4  253.83  3960.0  254.50  4012.4  253.48  4070.8  254.38
  4224.3  254.18  4245.7  253.12  4288.4  252.86  4335.2  253.70  4420.6  252.92
  4484.7  253.81  4776.3  253.65  4902.6  254.49  4988.2  253.70  5013.1  252.61
  5013.5  252.11  5018.9  252.61  5046.0  254.22  5086.1  253.54  5123.2  254.12
  5230.4  254.38  5296.5  253.56  5426.8  256.93  5506.9  260.54  5797.5  268.45
#Mann=7,-1,0
  2663.5   0.045       0  3656.3    0.07       0  4335.2    0.05       0
  5013.1    0.05       0  5018.9    0.05       0  5123.2     0.1       0
  5230.4    0.05       0
Bank Sta=5013.1,5018.9
Exp/Cntr=0.3,0.1

Type RM Length L Ch R = 1,921,423,423,423
BEGIN DESCRIPTION:
Stream0484 2.0
END DESCRIPTION:
XS GIS Cut Line= 3
      2511724.99     13727275.01      2510125.00     13729275.00
      2510874.99     13730074.98
#Sta/Elev= 30
  2452.1  254.61  3085.2  253.12  3120.4  253.65  3128.7  254.67  3142.8  252.96
  3248.5  253.15  3312.5  252.04  3320.5  253.05  3362.1  252.25  3533.4  252.37
  3618.3  251.61  3696.7  252.42  3725.5  251.45  3733.9  252.36  4330.6  252.31
  5045.8  250.08  5046.3  249.58  5051.6  250.08  5168.9  251.02  5204.6  252.37
  5275.5  252.22  5324.7  251.48  5374.1  252.27  5480.1  252.00  5600.0  254.80
  5657.4  255.41  5727.7  257.99  5791.7  259.16  5989.5  268.33  6109.9  272.73
#Mann=7,-1,0
  2452.1   0.045       0  3128.7    0.07       0  3733.9    0.05       0
  5045.8    0.05       0  5051.6    0.05       0  5275.5    0.07       0
  5600.0    0.05       0
Bank Sta=5045.8,5051.6
Exp/Cntr=0.3,0.1

Type RM Length L Ch R = 1,498,0,0,0
BEGIN DESCRIPTION:
Stream0484 1.0
END DESCRIPTION:
XS GIS Cut Line= 3
      2511844.58     13726963.66      2509775.00     13729275.00
      2510659.34     13731470.93
#Sta/Elev= 30
  1897.0  256.19  2858.0  253.09  2903.5  254.07  2917.7  252.60  3030.6  252.15
  3484.2  252.02  3937.5  252.39  4565.0  250.42  4684.9  249.98  4898.2  249.76
  4957.5  249.26  5128.9  251.52  5247.4  249.18  5444.4  248.64  5524.1  248.65
  5543.2  248.25  5543.6  247.75  5549.0  248.25  5607.8  248.83  5759.1  249.10
  6002.9  253.05  6067.4  253.65  6371.1  259.01  6429.8  259.62  6545.1  264.01
  6624.0  265.87  6731.3  269.14  6835.4  269.85  7074.4  277.89  7366.8  293.35
#Mann=19,-1,0
  1897.0   0.045       0  2858.0    0.07       0  3484.2    0.05       0
  4565.0    0.07       0  4684.9    0.05       0  4898.2    0.07       0
  4957.5    0.05       0  5444.4    0.07       0  5524.1    0.05       0
  5543.2    0.05       0  5549.0    0.05       0  5607.8    0.07       0
  5759.1    0.05       0  6002.9    0.07       0  6067.4    0.05       0
  6371.1    0.07       0  6545.1    0.05       0  6624.0   0.035       0
  6731.3    0.05       0
Bank Sta=5543.2,5549
Exp/Cntr=0.3,0.1

Chan Stop Cuts=-1