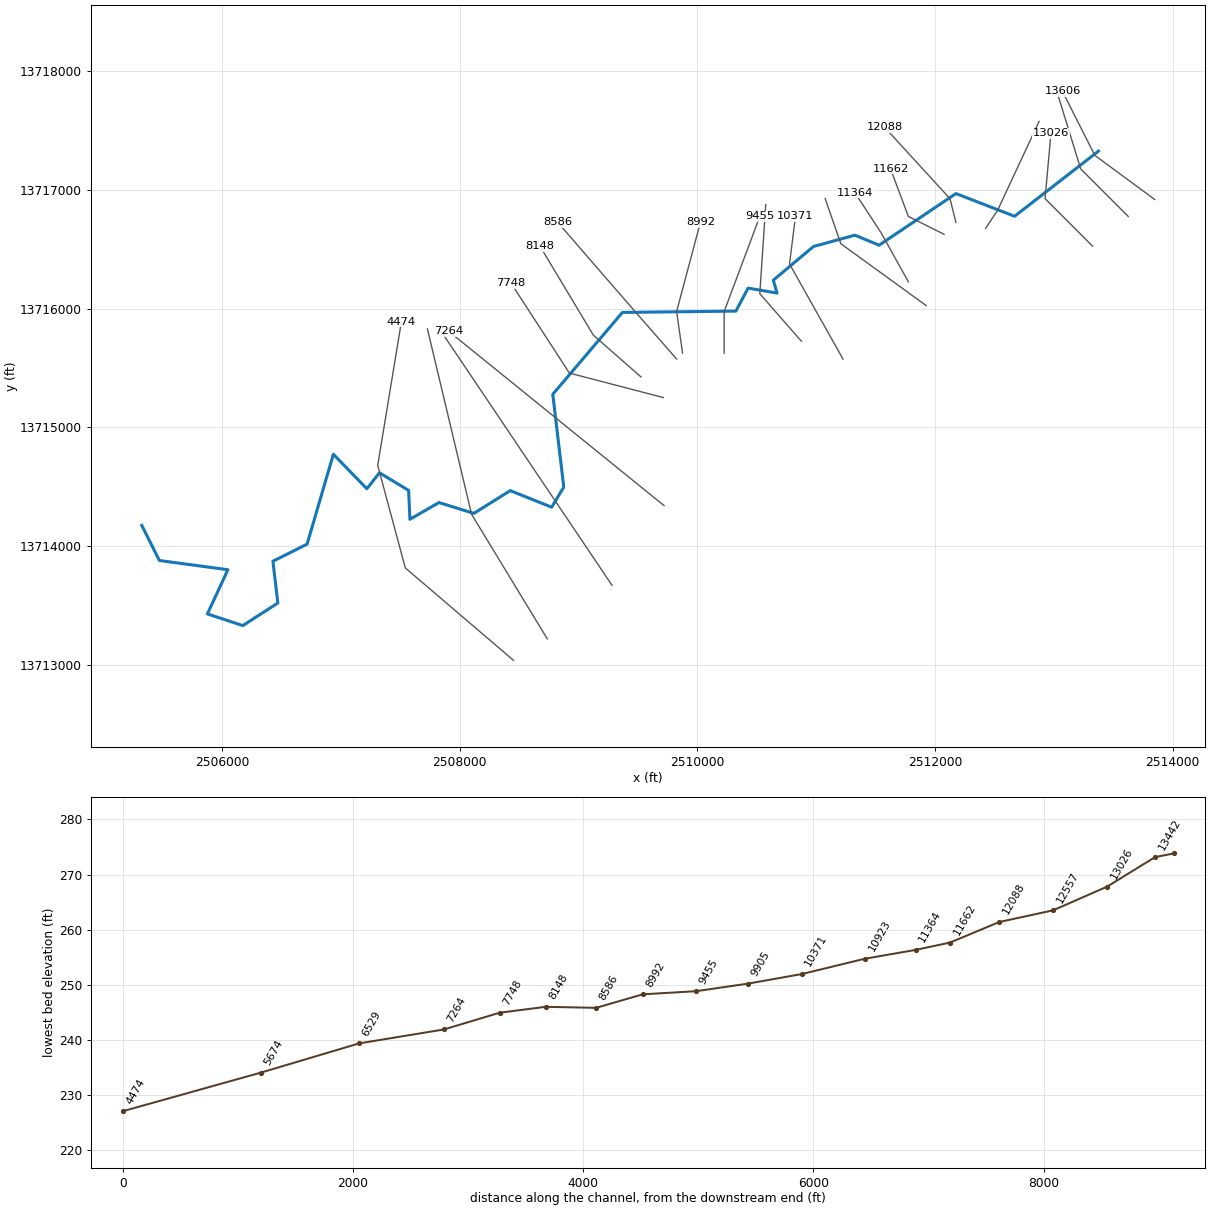
--- Stream0487.prj (project) ---

Proj Title=Stream0487 Base Level Engineering
Current Plan=p01
Default Exp/Contr=0.3,0.1
English Units
Geom File=g01
Flow File=f01
Plan File=p01
Y Axis Title=Elevation
X Axis Title(PF)=Main Channel Distance
X Axis Title(XS)=Station
BEGIN DESCRIPTION:
Stream0487
END DESCRIPTION:
DSS Export Rating Curves= 0
DSS Export Rating Curve Sorted= 0
DSS Export Volume Flow Curves= 0
DXF OffsetX= 0
DXF OffsetY= 0
DXF ScaleX= 1
DXF ScaleY= 10

--- Stream0487.p01 (plan) ---

Plan Title=Multiple Run
Short Identifier=Multiple
Geom File=g01
Flow File=f01
Subcritical Flow
K Sum by GR= 0
Std Step Tol= 0.01
Critical Tol= 0.01
Num of Std Step Trials= 20
Max Error Tol= 0.3
Flow Tol Ratio= 0.001
Split Flow NTrial= 30
Split Flow Tol= 0.02
Split Flow Ratio= 0.02
Log Output Level= 0
Friction Slope Method= 1
Unsteady Friction Slope Method= 2
Unsteady Bridges Friction Slope Method= 1
Parabolic Critical Depth
Global Vel Dist=  1 , 1 , 1
Global Log Level= 0
CheckData=True
Encroach Param= -1, 0, 0, 0
BEGIN DESCRIPTION:
Multiple Run
END DESCRIPTION:

--- Stream0487.f01 (steady flow) ---

Flow Title=Multiple
Number of Profiles=7
Profile Names=10-year,25-year,50-year,1pct_min,100-year,1pct_plu,500-year
River Rch & RM= Stream0487,Reach-1,13606
    1050    1739    2378    1574    3141    6268    5426
River Rch & RM= Stream0487,Reach-1,12557
    1275    2118    2903    1923    3838    7657    6642
Boundary for River Rch & Prof#=Stream0487,Reach-1,1
Up Type=0
Dn Type=3
Dn Slope=0.005
Boundary for River Rch & Prof#=Stream0487,Reach-1,2
Up Type=0
Dn Type=3
Dn Slope=0.005
Boundary for River Rch & Prof#=Stream0487,Reach-1,3
Up Type=0
Dn Type=3
Dn Slope=0.005
Boundary for River Rch & Prof#=Stream0487,Reach-1,4
Up Type=0
Dn Type=3
Dn Slope=0.005
Boundary for River Rch & Prof#=Stream0487,Reach-1,5
Up Type=0
Dn Type=3
Dn Slope=0.005
Boundary for River Rch & Prof#=Stream0487,Reach-1,6
Up Type=0
Dn Type=3
Dn Slope=0.005
Boundary for River Rch & Prof#=Stream0487,Reach-1,7
Up Type=0
Dn Type=3
Dn Slope=0.005

--- Stream0487.g01 (geometry) ---

Geom Title=Existing Conditions
Program Version=4.10

River Reach=Stream0487      ,Reach-1
Reach XY= 30
        2513375.       13717325.      2512668.96     13716776.62
      2512174.99     13716967.47      2511528.41     13716532.81
      2511324.99     13716617.47      2510976.43     13716521.93
      2510638.55     13716238.36      2510670.37     13716130.17
      2510426.39     13716171.97      2510323.77     13715978.44
      2509368.83     13715967.24      2508782.98     13715278.33
      2508875.39      13714497.8      2508773.75     13714328.44
        2508425.     13714467.91      2508118.96     13714276.63
      2507824.99     13714367.47      2507580.82      13714226.5
      2507570.04     13714469.89      2507324.73     13714617.81
      2507218.47     13714483.88      2506936.69     13714774.02
      2506715.99     13714017.94      2506428.04     13713873.58
      2506469.64      13713522.3      2506174.91     13713332.31
      2505876.87     13713430.69      2506049.16      13713802.3
      2505472.41     13713879.97        2505325.       13714175.

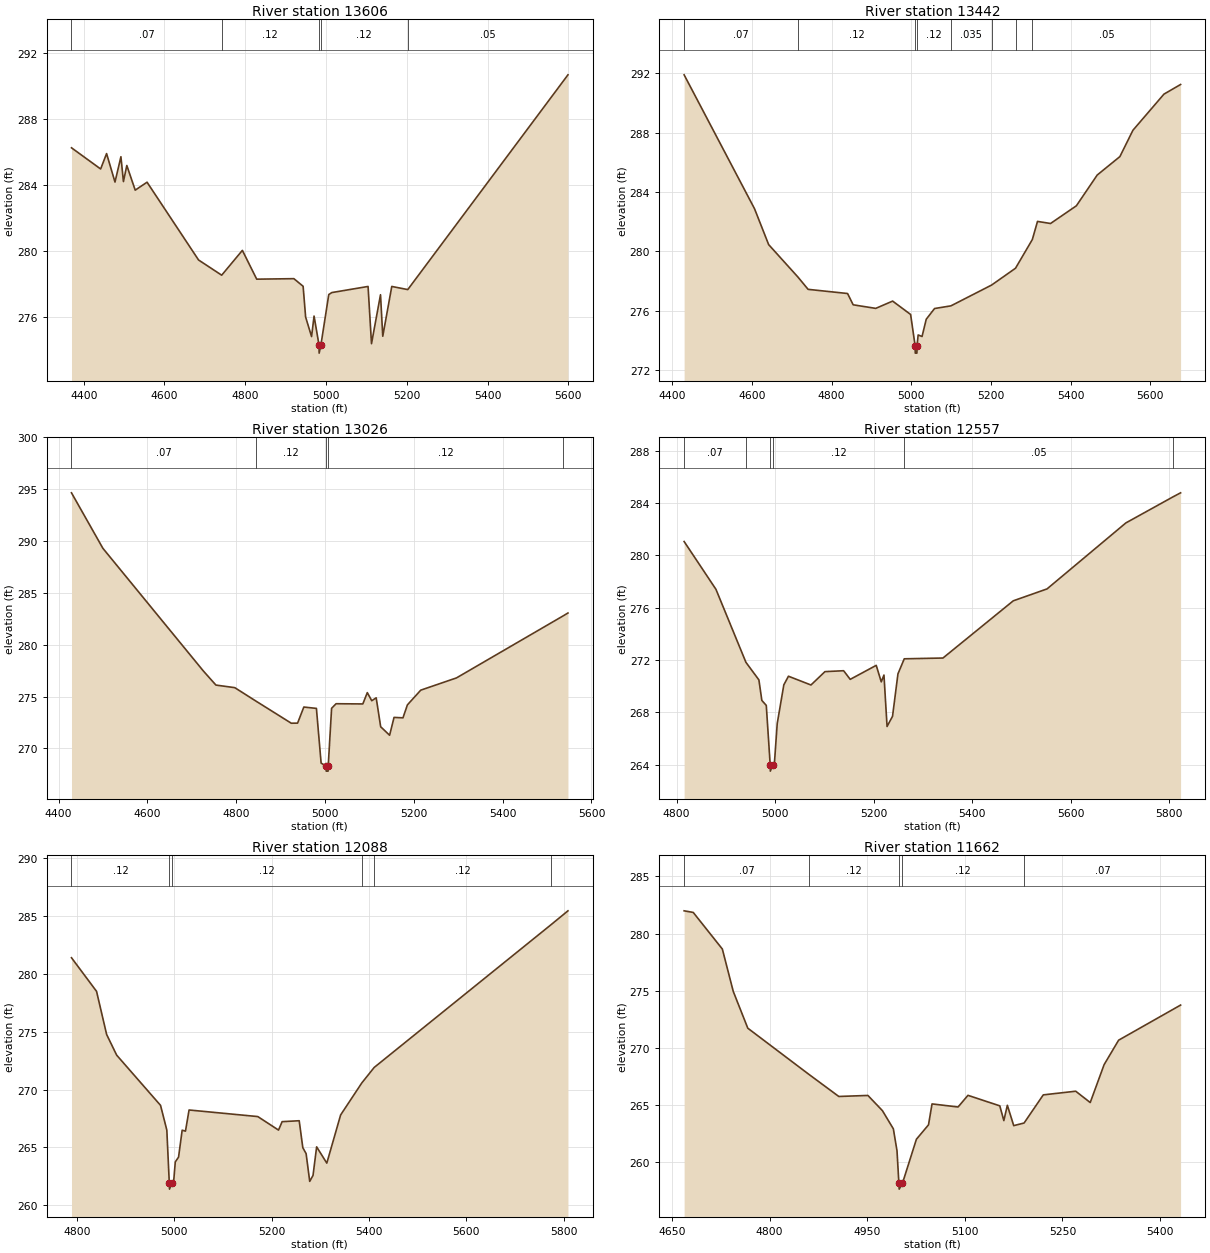
Type RM Length L Ch R = 1 ,13606   ,164,164,164
BEGIN DESCRIPTION:
XS6923
END DESCRIPTION:
XS GIS Cut Line= 3
      2513848.24     13716917.22      2513343.79     13717288.92
      2513071.65     13717826.57
#Sta/Elev= 30
  4369.8  286.25    4442  284.97  4456.7   285.9  4477.5  284.18  4492.2  285.71
  4498.4  284.21  4506.8  285.18  4527.6  283.69  4556.9  284.17  4684.4  279.47
  4741.7  278.55  4792.9  280.05  4828.4  278.31  4920.4  278.34  4943.3  277.88
  4949.5  276.02  4964.2  274.84  4970.4  276.08  4982.6  274.34    4983  273.84
  4987.4  274.34  5006.8  277.38  5014.4   277.5  5104.1  277.87  5112.6  274.41
  5134.9  277.37  5140.5  274.86  5162.8  277.87  5202.4  277.68    5599  290.66
#Mann= 5 ,-1 , 0
  4369.8     .07       0  4741.7     .12       0  4982.6     .05       0
  4987.4     .12       0  5202.4     .05       0
Bank Sta=4982.6,4987.4
XS Rating Curve= 0 ,0
Exp/Cntr=0.3,0.1

Type RM Length L Ch R = 1 ,13442   ,416,416,416
BEGIN DESCRIPTION:
Stream0487 25.0
END DESCRIPTION:
XS GIS Cut Line= 3
      2513624.98     13716775.02        2513225.       13717175.
      2513025.01     13717824.97
#Sta/Elev= 30
    4430  291.88  4606.7  282.87  4642.1  280.46  4715.8  278.27  4741.1  277.45
  4840.1  277.17  4854.2  276.41  4910.8  276.17  4953.2  276.66  4998.3  275.76
  5009.6  273.66    5010  273.16  5014.1  273.16  5014.5  273.66  5017.2  274.38
    5027  274.28  5037.5  275.44  5058.4  276.16  5099.5  276.34  5201.6  277.74
  5261.5  278.87  5303.7   280.8  5316.7  282.02  5349.4  281.88  5414.2  283.07
  5466.5  285.14  5523.4  286.38  5556.1  288.15  5633.9  290.58  5675.7  291.23
#Mann= 8 ,-1 , 0
    4430     .07       0  4715.8     .12       0  5009.6     .05       0
  5014.5     .12       0  5099.5    .035       0  5201.6     .12       0
  5261.5    .035       0  5303.7     .05       0
Bank Sta=5009.6,5014.5
XS Rating Curve= 0 ,0
Exp/Cntr=0.3,0.1

Type RM Length L Ch R = 1 ,13026   ,469,469,469
BEGIN DESCRIPTION:
Stream0487 24.0
END DESCRIPTION:
XS GIS Cut Line= 3
      2513324.97     13716525.03        2512925.       13716925.
        2512975.     13717474.99
#Sta/Elev= 30
  4429.1  294.65  4499.8   289.3    4726  277.47  4754.3  276.11  4796.8  275.86
  4844.6  274.56    4924  272.43  4938.2  272.44  4952.3  273.99  4980.6  273.86
  4991.2  268.58  5002.3  268.31  5002.7  267.81  5006.9  267.81  5007.2  268.31
  5014.8  273.87  5024.9  274.31  5085.1  274.29  5095.2  275.38  5105.2   274.6
  5115.2  274.88  5125.3  272.09  5145.4  271.27  5155.4  272.99  5175.5  272.95
  5185.5   274.2  5215.6  275.62    5296   276.8  5536.9   282.8    5547  283.06
#Mann= 5 ,-1 , 0
  4429.1     .07       0  4844.6     .12       0  5002.3     .05       0
  5007.2     .12       0  5536.9    .035       0
Bank Sta=5002.3,5007.2
XS Rating Curve= 0 ,0
Exp/Cntr=0.3,0.1

Type RM Length L Ch R = 1 ,12557   ,469,469,469
BEGIN DESCRIPTION:
Stream0487 23.0
END DESCRIPTION:
XS GIS Cut Line= 3
      2512424.99     13716674.98        2512525.       13716825.
      2512874.98     13717574.95
#Sta/Elev= 30
  4815.4  281.05    4880   277.4  4940.9  271.82  4967.2  270.48  4973.2  268.91
  4982.2  268.53  4990.1  264.01  4990.5  263.51  4995.2  264.01  4998.5  264.01
  5004.4  267.14  5017.8   270.1  5027.2  270.76  5072.9  270.09  5101.3  271.11
  5139.2  271.18  5152.6  270.52  5205.4  271.59  5215.6  270.33  5221.1  270.85
  5227.4  266.92  5238.5   267.7  5249.5  270.94  5262.3  272.09  5340.9  272.15
  5483.6  276.52  5552.2  277.43  5712.2  282.47  5807.3  284.45  5823.3  284.77
#Mann= 6 ,-1 , 0
  4815.4     .07       0  4940.9     .12       0  4990.1     .05       0
  4995.2     .12       0  5262.3     .05       0  5807.3    .035       0
Bank Sta=4990.1,4995.2
XS Rating Curve= 0 ,0
Exp/Cntr=0.3,0.1

Type RM Length L Ch R = 1 ,12088   ,426,426,426
BEGIN DESCRIPTION:
Stream0487 22.0
END DESCRIPTION:
XS GIS Cut Line= 3
        2512175.       13716725.        2512125.       13716925.
        2511575.       13717525.
#Sta/Elev= 30
  4788.7  281.41  4840.2   278.5  4860.9  274.77  4881.5  272.98  4971.7  268.63
  4984.6  266.49  4989.7  261.88  4990.1  261.38  4994.8  261.88  4998.3  261.88
    5002  263.74  5008.7  264.15  5016.1  266.48  5022.9   266.4  5030.3  268.23
  5171.5  267.66  5214.1  266.49  5221.5  267.22  5256.6   267.3    5264  264.97
  5270.8  264.45  5278.2  262.05    5285  262.57  5292.4  265.04  5313.3  263.63
  5341.7   267.8  5385.2  270.57  5410.6  271.91  5774.1  284.27  5808.8  285.47
#Mann= 6 ,-1 , 0
  4788.7     .12       0  4989.7     .05       0  4994.8     .12       0
  5385.2     .07       0  5410.6     .12       0  5774.1     .07       0
Bank Sta=4989.7,4994.8
XS Rating Curve= 0 ,0
Exp/Cntr=0.3,0.1

Type RM Length L Ch R = 1 ,11662   ,298,298,298
BEGIN DESCRIPTION:
Stream0487 21.0
END DESCRIPTION:
XS GIS Cut Line= 3
      2512074.99     13716625.01        2511775.       13716775.
        2511625.       13717175.
#Sta/Elev= 30
  4668.8  281.99  4682.8  281.85  4727.5  278.65  4744.3  274.94  4766.6  271.73
  4860.3   267.7  4906.4  265.76  4951.1  265.85  4973.4  264.52  4990.2  262.93
  4995.8  261.01  4998.7  258.16  4999.2  257.66  5004.1  258.16  5025.6  262.02
  5044.2  263.28  5049.6  265.11  5089.6  264.84  5104.8  265.86  5153.7  264.94
  5159.9  263.65  5165.3  264.99  5175.1  263.21    5191  263.44  5220.5   265.9
  5270.3  266.22  5292.6  265.23  5313.9  268.54  5336.2  270.68  5431.4  273.75
#Mann= 5 ,-1 , 0
  4668.8     .07       0  4860.3     .12       0  4998.7     .05       0
  5004.1     .12       0    5191     .07       0
Bank Sta=4998.7,5004.1
XS Rating Curve= 0 ,0
Exp/Cntr=0.3,0.1

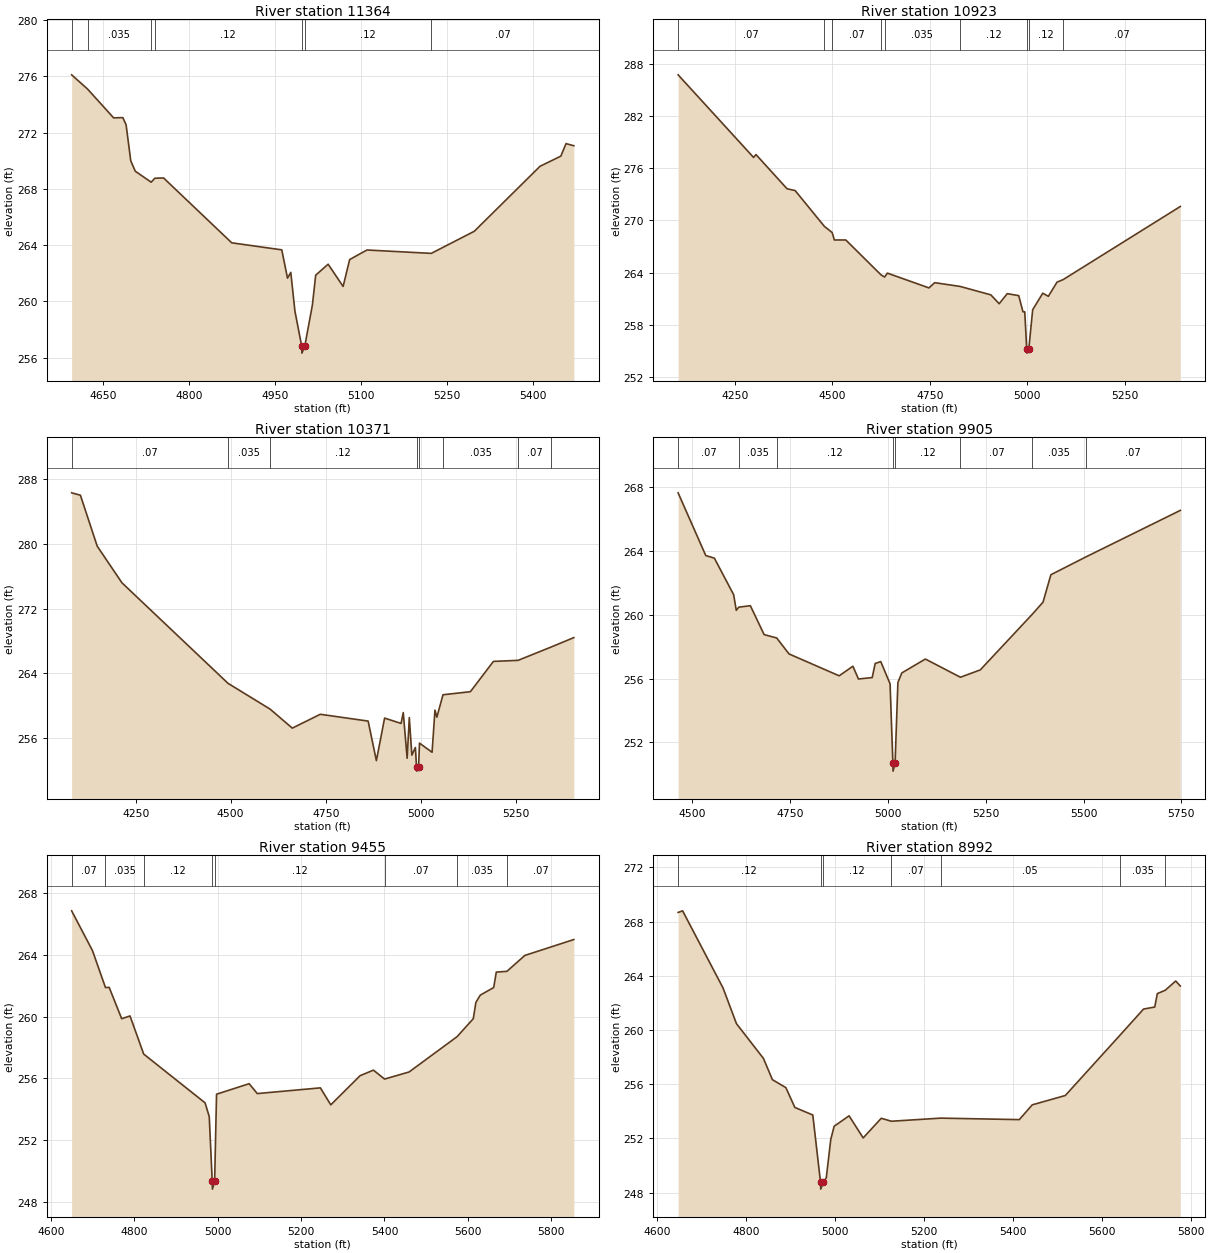
Type RM Length L Ch R = 1 ,11364   ,441,441,441
BEGIN DESCRIPTION:
Stream0487 20.0
END DESCRIPTION:
XS GIS Cut Line= 3
      2511774.99     13716225.03      2511544.91     13716638.41
      2511324.98     13716975.03
#Sta/Elev= 30
  4595.7  276.11  4623.4   275.1  4668.9  273.05  4684.9  273.07  4690.6  272.56
  4698.7     270  4706.6  269.26  4734.3  268.48  4740.7  268.76  4755.9  268.78
  4874.7  264.17  4961.9  263.67  4971.9  261.66  4977.6  262.07  4984.8  259.32
  4996.6  256.83    4997  256.33    5002  256.83  5015.3  259.76    5021  261.87
  5042.7  262.65  5068.8  261.07  5080.2  262.98  5110.4  263.66  5222.5  263.42
  5297.4  264.99    5412  269.61  5448.2  270.33  5457.3  271.22  5470.9  271.07
#Mann= 7 ,-1 , 0
  4595.7     .07       0  4623.4    .035       0  4734.3     .07       0
  4740.7     .12       0  4996.6     .05       0    5002     .12       0
  5222.5     .07       0
Bank Sta=4996.6,5002
XS Rating Curve= 0 ,0
Exp/Cntr=0.3,0.1

Type RM Length L Ch R = 1 ,10923   ,552,552,552
BEGIN DESCRIPTION:
Stream0487 19.0
END DESCRIPTION:
XS GIS Cut Line= 3
      2511925.01     13716024.99      2511206.38     13716545.47
      2511075.01     13716924.96
#Sta/Elev= 30
  4103.9  286.73  4297.6  277.23  4303.8  277.56  4383.5  273.63  4404.3  273.42
  4479.4   269.3  4499.2   268.6  4504.9  267.74  4534.3  267.74  4624.9  263.72
  4633.9  263.48    4641  263.93  4747.7  262.23  4762.4  262.83  4827.6   262.4
  4906.5  261.43  4927.9  260.41  4948.7  261.57  4978.1  261.34    4989  259.48
  4993.6  259.48  4998.6  255.23    4999  254.73    5004  255.23  5013.9  259.72
  5039.8  261.62  5054.2  261.26  5076.3  262.89    5092  263.18  5392.8  271.59
#Mann= 9 ,-1 , 0
  4103.9     .07       0  4479.4    .035       0  4499.2     .07       0
  4624.9     .12       0  4633.9    .035       0  4827.6     .12       0
  4998.6     .05       0    5004     .12       0    5092     .07       0
Bank Sta=4998.6,5004
XS Rating Curve= 0 ,0
Exp/Cntr=0.3,0.1

Type RM Length L Ch R = 1 ,10371   ,466,466,466
BEGIN DESCRIPTION:
Stream0487 18.0
END DESCRIPTION:
XS GIS Cut Line= 3
        2511225.       13715575.        2510775.       13716375.
        2510825.     13716775.01
#Sta/Elev= 30
  4081.7   286.3  4104.7  286.01    4149  279.71    4214  275.19  4493.1  262.77
  4603.7  259.59  4662.1  257.24  4735.7  258.95  4861.6  258.11  4883.3  253.23
  4904.9  258.48  4948.3  257.82    4954  259.16  4964.2  253.52  4969.9  258.54
  4976.6  253.91  4985.9  254.85  4988.9  252.43  4989.3  251.93  4994.3  252.43
  4996.7  255.39  5029.8  254.26  5037.4  259.46  5042.4  258.59  5058.5  261.36
  5130.6  261.74  5191.1  265.48    5256  265.61  5342.1  267.24  5402.7  268.42
#Mann= 8 ,-1 , 0
  4081.7     .07       0  4493.1    .035       0  4603.7     .12       0
  4988.9     .05       0  4994.3     .12       0  5058.5    .035       0
    5256     .07       0  5342.1    .035       0
Bank Sta=4988.9,4994.3
XS Rating Curve= 0 ,0
Exp/Cntr=0.3,0.1

Type RM Length L Ch R = 1 ,9905    ,450,450,450
BEGIN DESCRIPTION:
Stream0487 17.0
END DESCRIPTION:
XS GIS Cut Line= 3
      2510875.03     13715724.97        2510525.       13716125.
        2510575.     13716874.99
#Sta/Elev= 30
    4464  267.63  4534.7   263.7  4556.6  263.54  4605.9  261.25  4612.6  260.27
  4619.1  260.47  4648.6  260.56  4683.8  258.75  4715.9  258.54  4747.4  257.54
  4875.5  256.17  4910.6  256.77  4924.8  255.97    4960  256.06  4967.5  256.94
  4981.8  257.06  5005.6  255.67  5012.8   250.7  5013.2   250.2  5018.4   250.7
  5025.6  255.75  5035.6  256.35  5095.8  257.22  5185.4  256.08  5236.1  256.54
  5368.8  260.02  5396.4  260.78  5416.5   262.5  5505.5  263.61  5747.2  266.53
#Mann= 8 ,-1 , 0
    4464     .07       0  4619.1    .035       0  4715.9     .12       0
  5012.8     .05       0  5018.4     .12       0  5185.4     .07       0
  5368.8    .035       0  5505.5     .07       0
Bank Sta=5012.8,5018.4
XS Rating Curve= 0 ,0
Exp/Cntr=0.3,0.1

Type RM Length L Ch R = 1 ,9455    ,463,463,463
BEGIN DESCRIPTION:
Stream0487 16.0
END DESCRIPTION:
XS GIS Cut Line= 3
        2510225.     13715624.99        2510225.       13715975.
        2510525.     13716774.99
#Sta/Elev= 30
  4649.7  266.86  4699.7  264.28  4730.8  261.89  4739.7   261.9  4769.7  259.87
  4789.7  260.05  4822.5  257.58  4969.7  254.42  4979.7  253.53  4986.9  249.33
  4987.3  248.83  4992.6  249.33  4997.2  254.98  5075.4  255.66  5094.9  255.02
  5246.2  255.39  5271.2  254.29  5341.5  256.18  5373.5  256.54  5400.2  255.96
    5459  256.42  5574.2  258.71  5612.9  259.87  5619.2  260.93  5629.8   261.4
  5661.9  261.89  5668.1  262.89  5693.6  262.94  5736.6  263.97  5854.1     265
#Mann= 8 ,-1 , 0
  4649.7     .07       0  4730.8    .035       0  4822.5     .12       0
  4986.9     .05       0  4992.6     .12       0  5400.2     .07       0
  5574.2    .035       0  5693.6     .07       0
Bank Sta=4986.9,4992.6
XS Rating Curve= 0 ,0
Exp/Cntr=0.3,0.1

Type RM Length L Ch R = 1 ,8992    ,406,406,406
BEGIN DESCRIPTION:
Stream0487 15.0
END DESCRIPTION:
XS GIS Cut Line= 3
        2509875.     13715625.01        2509825.       13715975.
      2510024.99     13716724.95
#Sta/Elev= 30
  4646.5  268.68  4656.6   268.8  4747.5  263.11  4777.8  260.47  4838.4  257.91
  4858.6  256.34  4888.9  255.75  4909.1  254.29  4949.5  253.73  4966.9  248.76
  4967.3  248.26  4972.6  248.76  4979.8  249.09  4989.9  251.93  4997.5   252.9
  5031.1  253.67  5062.8  252.04  5103.5  253.49  5126.3  253.27    5237   253.5
    5414  253.39  5443.1  254.48  5517.5  255.17  5639.7  259.59  5693.5  261.55
  5718.7   261.7  5724.5  262.69  5742.4  262.94  5765.9  263.62  5776.2  263.25
#Mann= 7 ,-1 , 0
  4646.5     .12       0  4966.9     .05       0  4972.6     .12       0
  5126.3     .07       0    5237     .05       0  5639.7    .035       0
  5742.4     .07       0
Bank Sta=4966.9,4972.6
XS Rating Curve= 0 ,0
Exp/Cntr=0.3,0.1

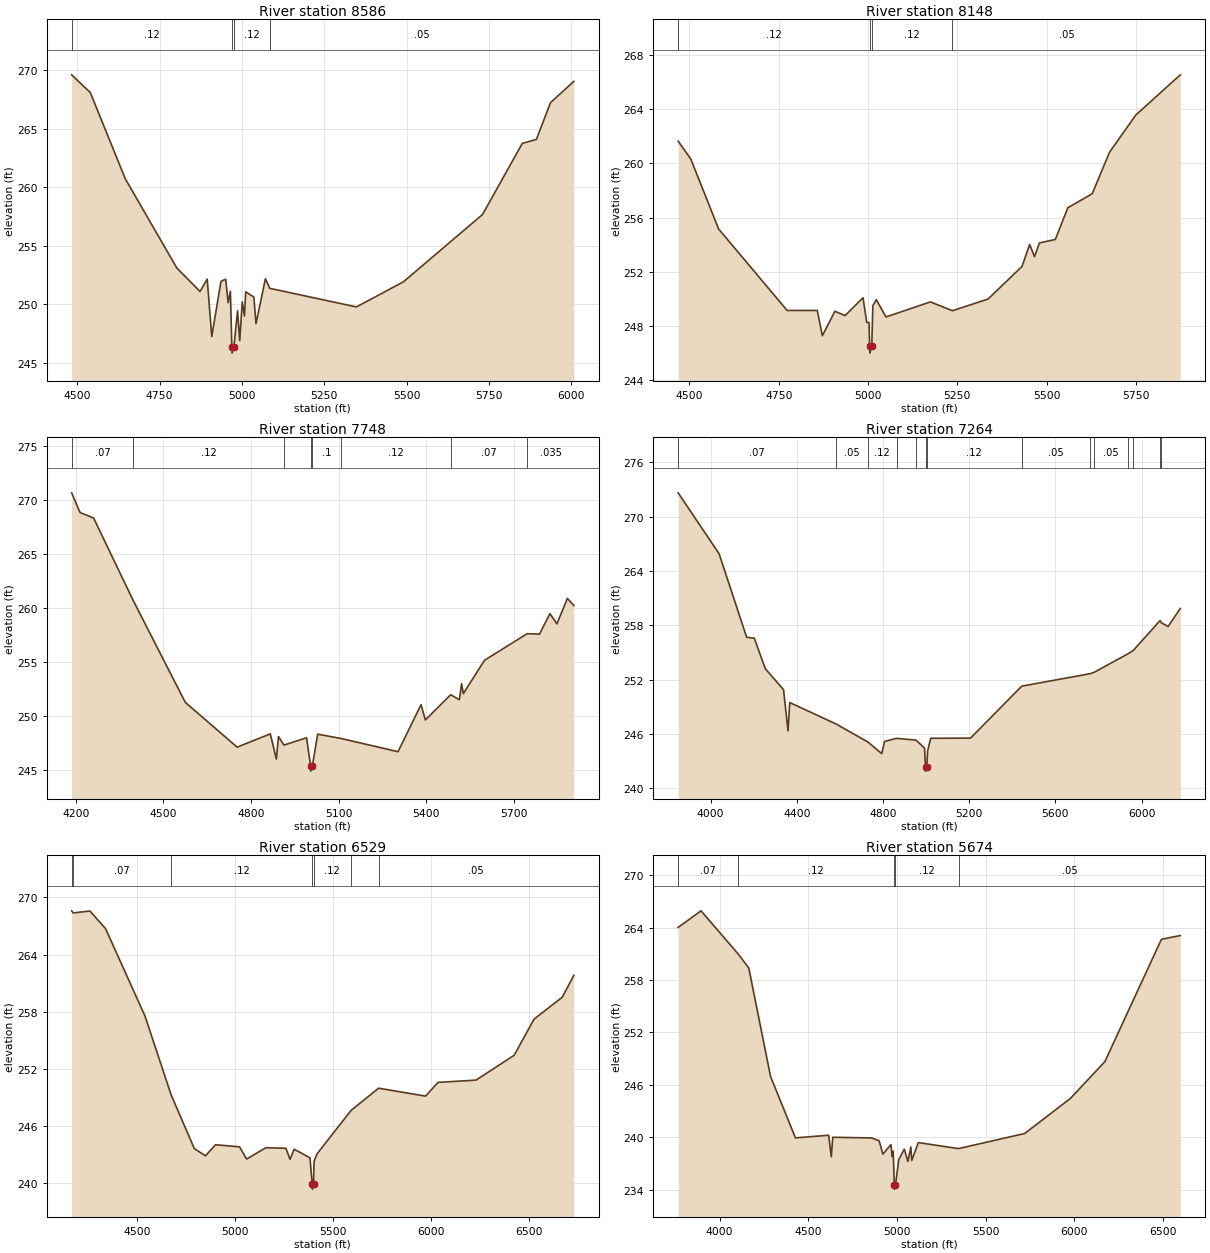
Type RM Length L Ch R = 1 ,8586    ,438,438,438
BEGIN DESCRIPTION:
Stream0487 14.0
END DESCRIPTION:
XS GIS Cut Line= 3
      2509824.99     13715575.02        2509475.       13715975.
      2508824.97     13716725.03
#Sta/Elev= 30
  4483.4  269.61  4539.9   268.1  4646.2  260.72  4802.3   253.1    4873  251.08
  4894.8  252.14  4908.6  247.23  4936.6  251.95  4950.8  252.13  4958.4  250.13
  4965.1  251.11  4969.6  246.31  4970.1  245.81  4975.6  246.31  4986.9  249.44
  4993.5  246.88  5001.1  250.19  5007.8  248.99  5011.6  251.05  5036.3  250.61
  5042.9  248.33  5071.4  252.17  5084.8  251.35  5347.7  249.76  5490.3  251.91
  5730.5  257.67  5851.1  263.75  5893.9  264.09  5936.6  267.23  6007.4  269.05
#Mann= 4 ,-1 , 0
  4483.4     .12       0  4969.6     .05       0  4975.6     .12       0
  5084.8     .05       0
Bank Sta=4969.6,4975.6
XS Rating Curve= 0 ,0
Exp/Cntr=0.3,0.1

Type RM Length L Ch R = 1 ,8148    ,400,400,400
BEGIN DESCRIPTION:
Stream0487 13.0
END DESCRIPTION:
XS GIS Cut Line= 3
      2509525.03     13715424.97        2509125.       13715775.
        2508675.       13716525.
#Sta/Elev= 30
  4468.2  261.64  4503.8  260.31  4581.7  255.15  4773.4  249.14  4857.9  249.14
  4872.1  247.27  4907.2  249.08  4935.7  248.76    4986  250.08  4996.4  248.25
  5002.7  248.25  5004.5  246.49    5005  245.99  5010.5  246.49  5013.4  249.48
  5023.1  249.94  5050.3  248.66  5174.7  249.77  5236.4  249.12    5336  249.98
  5431.2  252.39  5452.6  254.01  5466.2  253.11  5479.8  254.12  5524.5  254.38
  5559.5  256.72  5627.6  257.75  5676.1  260.81    5750  263.57  5874.4  266.53
#Mann= 4 ,-1 , 0
  4468.2     .12       0  5004.5     .05       0  5010.5     .12       0
  5236.4     .05       0
Bank Sta=5004.5,5010.5
XS Rating Curve= 0 ,0
Exp/Cntr=0.3,0.1

Type RM Length L Ch R = 1 ,7748    ,484,484,484
BEGIN DESCRIPTION:
XS6928
END DESCRIPTION:
XS GIS Cut Line= 3
      2509712.81     13715251.09      2508922.93     13715456.85
      2508431.73     13716213.57
#Sta/Elev= 30
  4186.3  270.68    4215  268.86  4261.4  268.35  4396.6  260.73  4575.1  251.29
  4752.4  247.14  4866.1  248.37  4886.7  246.04    4894  248.12  4912.7  247.33
  4990.1  248.01  5004.1  245.42  5004.6  244.92  5010.1  245.42  5028.2  248.34
  5106.5  247.95  5303.1  246.72  5381.8  251.07  5396.7  249.66  5483.2  251.99
    5513  251.53  5520.6  253.01  5526.5  252.09    5599  255.18    5745  257.64
  5787.2   257.6  5822.9   259.5  5846.8  258.55  5882.6  260.91  5904.7  260.25
#Mann= 8 ,-1 , 0
  4186.3     .07       0  4396.6     .12       0  4912.7      .1       0
  5004.1     .05       0  5010.1      .1       0  5106.5     .12       0
  5483.2     .07       0    5745    .035       0
Bank Sta=5004.1,5010.1
XS Rating Curve= 0 ,0
Exp/Cntr=0.3,0.1

Type RM Length L Ch R = 1 ,7264    ,735,735,735
BEGIN DESCRIPTION:
XS6927
END DESCRIPTION:
XS GIS Cut Line= 2
      2509719.45     13714341.71       2507908.7     13715807.55
#Sta/Elev= 30
  3849.6  272.64  4039.7  265.91  4167.6  256.67  4202.8  256.58  4253.9  253.21
  4338.7  250.88  4359.5  246.33  4367.4  249.46  4582.5  247.09  4729.3  245.11
  4794.3  243.82  4807.4  245.16  4862.8   245.5  4953.1  245.31  4992.6  244.44
  4997.3  242.38  4997.8  241.88  5003.4  242.38    5007  244.09  5021.3  245.51
  5206.2  245.53  5443.6  251.27    5761  252.65  5781.2  252.82  5934.5  254.82
  5962.1  255.24  6085.7  258.53  6091.7  258.27  6122.9  257.87  6179.3  259.86
#Mann= 14 ,-1 , 0
  3849.6     .07       0  4582.5     .05       0  4729.3     .12       0
  4862.8      .1       0  4953.1     .12       0  4997.3     .05       0
  5003.4     .12       0  5443.6     .05       0    5761     .07       0
  5781.2     .05       0  5934.5     .07       0  5962.1     .05       0
  6085.7    .035       0  6091.7     .07       0
Bank Sta=4997.3,5003.4
XS Rating Curve= 0 ,0
Exp/Cntr=0.3,0.1

Type RM Length L Ch R = 1 ,6529    ,855,855,855
BEGIN DESCRIPTION:
XS6926
END DESCRIPTION:
XS GIS Cut Line= 2
      2509281.38     13713671.24      2507848.29     13715800.97
#Sta/Elev= 30
  4163.7  268.59  4171.3  268.37  4257.2  268.57    4337  266.72  4539.1  257.51
  4672.1  249.26    4791  243.61    4848  242.86    4899  244.02    5022   243.8
    5058  242.52    5157  243.71  5258.9  243.65  5279.9  242.49  5301.2  243.55
  5381.9  242.65  5393.7  239.86  5394.2  239.36  5400.1  239.86  5402.9  242.28
  5417.9  243.06  5592.5  247.64  5732.7  249.96  5972.8  249.13  6036.5  250.57
  6230.7  250.81  6425.7  253.42  6527.6  257.22  6671.6  259.52  6730.7  261.81
#Mann= 7 ,-1 , 0
  4163.7     .05       0  4171.3     .07       0  4672.1     .12       0
  5393.7     .05       0  5400.1     .12       0  5592.5     .07       0
  5732.7     .05       0
Bank Sta=5393.7,5400.1
XS Rating Curve= 0 ,0
Exp/Cntr=0.3,0.1

Type RM Length L Ch R = 1 ,5674    ,1200,1200,1200
BEGIN DESCRIPTION:
XS6925
END DESCRIPTION:
XS GIS Cut Line= 3
      2508737.09     13713219.84      2508099.83     13714268.66
      2507728.11     13715828.54
#Sta/Elev= 30
  3766.7  264.02  3895.8  265.92    4106  260.96  4165.1  259.37  4287.6  246.96
    4428  239.92  4615.2  240.22  4630.2  237.76  4638.6  239.99    4857  239.91
  4899.6   239.6  4920.9  238.05  4966.3  239.15  4973.2  237.79  4979.1   238.4
  4985.5  234.55    4986  234.05  4991.9  234.55  5010.7  237.44  5041.6  238.63
  5062.1  237.22  5078.5  238.88  5083.7  237.33  5120.7  239.38  5347.5  238.69
  5720.1  240.42  5977.1  244.42  6172.4  248.65  6491.1  262.66  6597.5  263.09
#Mann= 5 ,-1 , 0
  3766.7     .07       0    4106     .12       0  4985.5     .05       0
  4991.9     .12       0  5347.5     .05       0
Bank Sta=4985.5,4991.9
XS Rating Curve= 0 ,0
Exp/Cntr=0.3,0.1

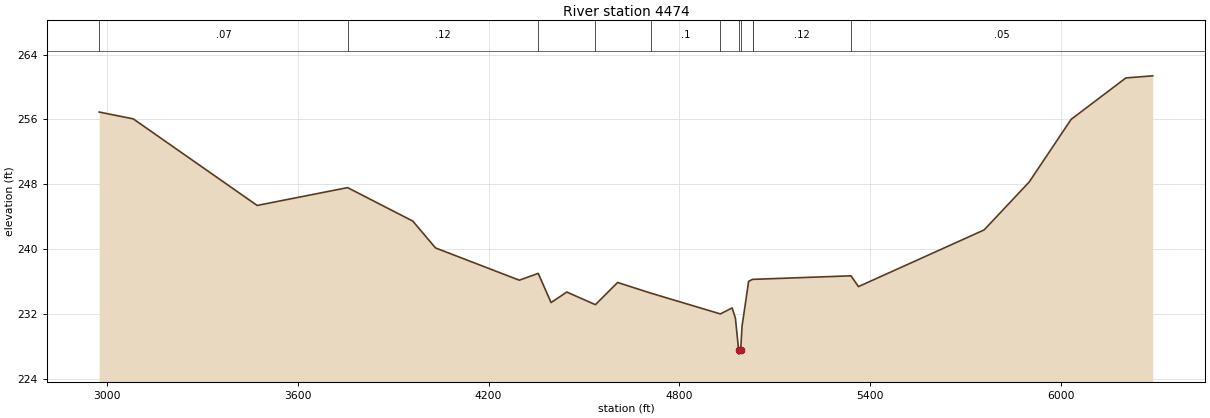
Type RM Length L Ch R = 1 ,4474    ,0,0,0
BEGIN DESCRIPTION:
XS6924
END DESCRIPTION:
XS GIS Cut Line= 4
      2508451.66     13713040.63      2507542.24     13713817.28
      2507309.91     13714680.22      2507509.05     13715888.33
#Sta/Elev= 30
  2975.4   256.9  3082.5  256.06  3472.2  245.38  3756.7  247.58  3961.9  243.45
  4033.3  240.14  4296.9  236.16  4356.4     237  4396.8   233.4  4446.3   234.7
  4536.2  233.14  4606.1  235.88  4709.9  234.57  4929.3     232  4966.4  232.74
  4976.7  231.46  4986.7  227.54  4987.2  227.04  4993.3  227.54  4997.4  230.45
  5018.2  236.02  5030.4  236.26  5030.5  236.26  5340.2   236.7  5363.7  235.37
    5759  242.36  5900.9  248.28  6032.7     256  6204.9  261.11  6289.4  261.37
#Mann= 11 ,-1 , 0
  2975.4     .07       0  3756.7     .12       0  4356.4      .1       0
  4536.2     .12       0  4709.9      .1       0  4929.3     .12       0
  4986.7     .05       0  4993.3     .12       0  5030.4     .07       0
  5030.5     .12       0  5340.2     .05       0
Bank Sta=4986.7,4993.3
XS Rating Curve= 0 ,0
Exp/Cntr=0.3,0.1

Chan Stop Cuts=-1
Use User Specified Reach Order=0
Composite Channel Slope=5