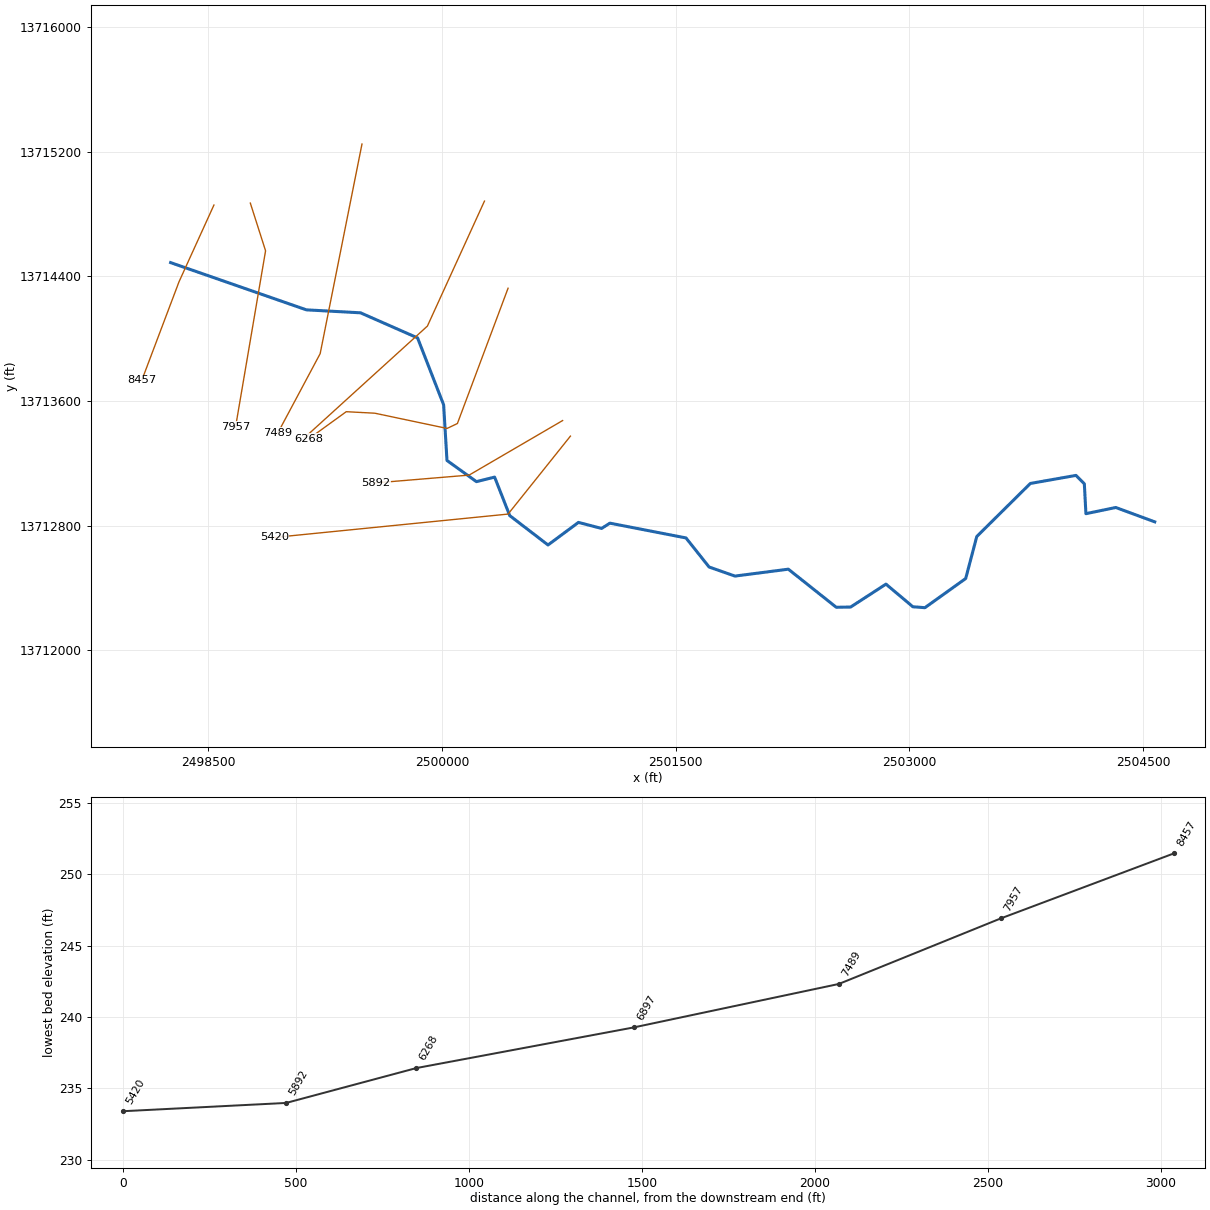
--- Stream0488.prj (project) ---

Proj Title=Stream0488 Base Level Engineering
Current Plan=p01
Default Exp/Contr=0.3,0.1
English Units
Geom File=g01
Flow File=f01
Plan File=p01
BEGIN DESCRIPTION:
Stream0488
END DESCRIPTION:

--- Stream0488.p01 (plan) ---

Plan Title=Multiple Run
Short Identifier=Multiple
Geom File=g01
Flow File=f01
Subcritical Flow
K Sum by GR= 0
Std Step Tol= 0.01
Critical Tol= 0.01
Num of Std Step Trials= 20
Max Error Tol= 0.3
Flow Tol Ratio= 0.001
Split Flow NTrial= 30
Split Flow Tol= 0.02
Split Flow Ratio= 0.02
Log Output Level= 0
Friction Slope Method= 1
Unsteady Friction Slope Method= 2
Unsteady Bridges Friction Slope Method= 1
Parabolic Critical Depth
Global Vel Dist=  1 , 1 , 1
Global Log Level= 0
CheckData=True
Encroach Param= -1, 0, 0, 0
BEGIN DESCRIPTION:
Multiple Run
END DESCRIPTION:

--- Stream0488.f01 (steady flow) ---

Flow Title=Multiple
Number of Profiles=7
Profile Names=10-year,25-year,50-year,1pct_min,100-year,1pct_plu,500-year
River Rch & RM= Stream0488,Reach-1,8457
     733    1182    1587    1033    2060    4111    3435
Boundary for River Rch & Prof#=Stream0488,Reach-1,1
Up Type=0
Dn Type=3
Dn Slope=0.005
Boundary for River Rch & Prof#=Stream0488,Reach-1,2
Up Type=0
Dn Type=3
Dn Slope=0.005
Boundary for River Rch & Prof#=Stream0488,Reach-1,3
Up Type=0
Dn Type=3
Dn Slope=0.005
Boundary for River Rch & Prof#=Stream0488,Reach-1,4
Up Type=0
Dn Type=3
Dn Slope=0.005
Boundary for River Rch & Prof#=Stream0488,Reach-1,5
Up Type=0
Dn Type=3
Dn Slope=0.005
Boundary for River Rch & Prof#=Stream0488,Reach-1,6
Up Type=0
Dn Type=3
Dn Slope=0.005
Boundary for River Rch & Prof#=Stream0488,Reach-1,7
Up Type=0
Dn Type=3
Dn Slope=0.005

--- Stream0488.g01 (geometry) ---

Geom Title=Existing Conditions

River Reach=Stream0488,Reach-1
Reach XY= 30
      2498259.41     13714488.09      2499130.63     13714185.06
      2499477.85     13714166.12      2499844.01     13714005.13
      2500011.31     13713575.84      2500032.81     13713218.79
      2500221.69     13713083.07      2500338.56     13713112.01
      2500435.52     13712865.21      2500681.12     13712676.76
      2500876.50     13712821.54      2501025.10     13712782.80
      2501078.22     13712816.72      2501566.69     13712721.91
      2501714.92     13712535.44      2501880.94     13712477.25
      2502223.53     13712521.47      2502530.97     13712277.14
      2502623.42     13712278.67      2502850.00     13712425.59
      2503022.57     13712280.40      2503100.04     13712274.49
      2503361.53     13712461.43      2503432.82     13712731.19
      2503776.50     13713071.39      2504069.35     13713123.04
      2504123.03     13713069.35      2504133.11     13712877.51
      2504324.90     13712917.22      2504575.00     13712825.00

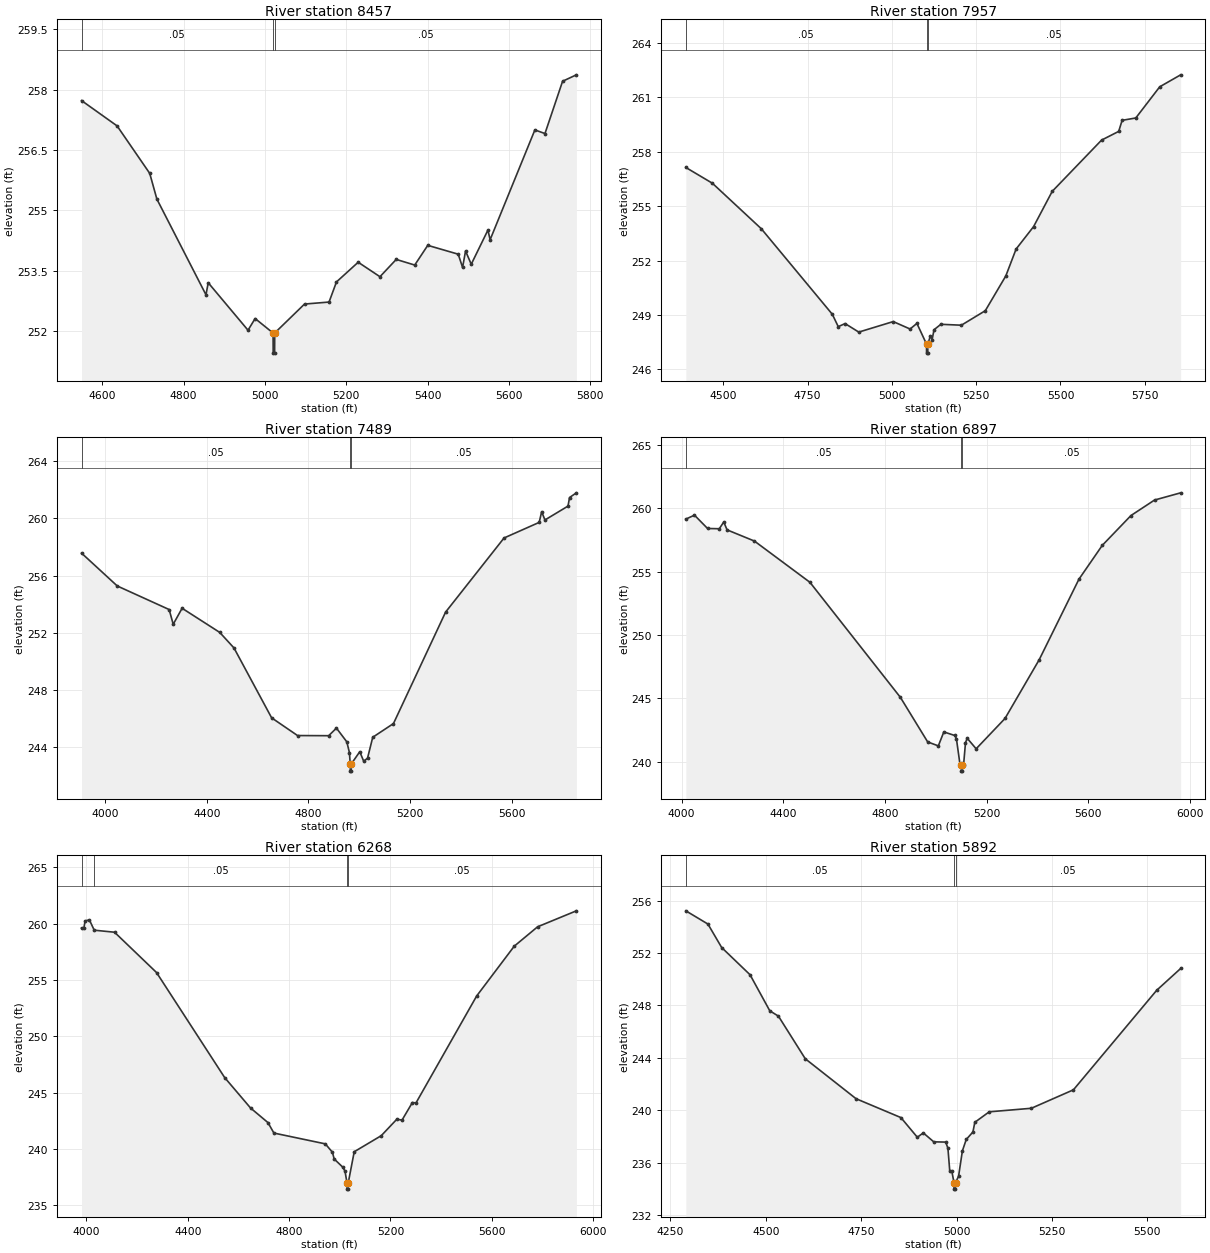
Type RM Length L Ch R = 1,8457,500,500,500
BEGIN DESCRIPTION:
Stream0488 17.0
END DESCRIPTION:
XS GIS Cut Line= 3
      2498537.20     13714857.43      2498313.08     13714364.98
      2498074.43     13713733.32
#Sta/Elev= 30
  4549.2  257.73  4636.6  257.10  4716.8  255.92  4734.4  255.28  4855.1  252.90
  4860.6  253.20  4958.4  252.02  4975.9  252.31  5020.0  251.95  5020.3  251.45
  5023.8  251.45  5024.0  251.95  5097.3  252.67  5157.6  252.72  5175.8  253.22
  5229.2  253.71  5282.7  253.35  5322.7  253.78  5368.2  253.64  5400.2  254.13
  5475.1  253.91  5485.8  253.58  5493.1  253.99  5507.1  253.66  5548.1  254.51
  5553.5  254.27  5663.5  257.00  5688.3  256.91  5731.6  258.21  5765.5  258.37
#Mann=3,-1,0
  4549.2    0.05       0  5020.0    0.05       0  5024.0    0.05       0
Bank Sta=5020,5024
Exp/Cntr=0.3,0.1

Type RM Length L Ch R = 1,7957,468,468,468
BEGIN DESCRIPTION:
E21102
END DESCRIPTION:
XS GIS Cut Line= 3
      2498770.78     13714870.02      2498868.63     13714563.84
      2498676.08     13713433.76
#Sta/Elev= 30
  4388.7  257.14  4467.5  256.27  4612.6  253.76  4823.3  249.04  4840.8  248.36
  4861.1  248.53  4901.7  248.06  5003.9  248.64  5053.9  248.23  5074.1  248.54
  5102.6  247.40  5102.8  246.90  5106.3  246.90  5106.6  247.40  5114.2  247.86
  5119.3  247.65  5124.9  248.19  5145.2  248.49  5206.0  248.44  5277.0  249.24
  5337.9  251.16  5368.3  252.64  5420.3  253.88  5475.4  255.82  5621.9  258.65
  5672.7  259.13  5682.8  259.74  5723.4  259.87  5794.4  261.59  5856.5  262.25
#Mann=3,-1,0
  4388.7    0.05       0  5102.6    0.05       0  5106.6    0.05       0
Bank Sta=5102.6,5106.6
Exp/Cntr=0.3,0.1

Type RM Length L Ch R = 1,7489,592,592,592
BEGIN DESCRIPTION:
Stream0488 16.0
END DESCRIPTION:
XS GIS Cut Line= 3
      2499487.32     13715248.84      2499219.01     13713904.12
      2498947.54     13713395.91
#Sta/Elev= 30
  3907.3  257.57  4047.9  255.27  4252.1  253.62  4268.1  252.59  4303.1  253.71
  4451.2  252.02  4507.3  250.93  4655.4  246.04  4757.4  244.80  4879.9  244.79
  4910.5  245.32  4951.3  244.36  4961.5  243.61  4964.7  242.81  4965.0  242.31
  4968.5  242.31  4968.7  242.81  5002.3  243.67  5017.8  243.00  5032.9  243.22
  5053.3  244.68  5134.9  245.64  5340.0  253.44  5570.1  258.63  5708.3  259.72
  5718.1  260.47  5731.0  259.89  5821.7  260.86  5827.8  261.46  5854.7  261.79
#Mann=3,-1,0
  3907.3    0.05       0  4964.7    0.05       0  4968.7    0.05       0
Bank Sta=4964.7,4968.7
Exp/Cntr=0.3,0.1

Type RM Length L Ch R = 1,6897,629,629,629
BEGIN DESCRIPTION:
Stream0488 15.0
END DESCRIPTION:
XS GIS Cut Line= 3
      2500273.30     13714882.65      2499907.14     13714080.89
      2499118.99     13713365.24
#Sta/Elev= 30
  4016.8  259.13  4050.8  259.44  4102.3  258.39  4148.4  258.37  4165.9  258.90
  4179.1  258.28  4286.5  257.40  4504.8  254.15  4860.7  245.08  4967.9  241.57
  5009.8  241.26  5031.4  242.36  5074.0  242.08  5080.8  241.84  5094.9  239.81
  5100.4  239.77  5100.6  239.27  5104.1  239.27  5104.4  239.77  5109.1  239.77
  5116.6  241.51  5123.3  241.86  5158.5  241.03  5272.0  243.42  5406.5  248.05
  5562.6  254.39  5654.5  257.06  5767.3  259.41  5859.9  260.63  5962.8  261.20
#Mann=3,-1,0
  4016.8    0.05       0  5100.4    0.05       0  5104.4    0.05       0
Bank Sta=5100.4,5104.4
Exp/Cntr=0.3,0.1

Type RM Length L Ch R = 1,6268,376,376,376
BEGIN DESCRIPTION:
Stream0488 14.0
END DESCRIPTION:
XS GIS Cut Line= 6
      2500424.82     13714323.94      2500099.69     13713455.89
      2500033.40     13713424.32      2499569.39     13713522.18
      2499386.31     13713531.65      2499147.74     13713359.00
#Sta/Elev= 30
  3981.0  259.61  3990.0  259.60  3995.3  260.24  4011.9  260.34  4031.1  259.42
  4111.2  259.24  4276.9  255.66  4545.7  246.33  4647.7  243.63  4716.5  242.33
  4740.0  241.40  4942.9  240.44  4971.1  239.69  4977.7  239.10  5012.2  238.36
  5020.6  238.01  5028.8  236.92  5029.1  236.42  5032.6  236.42  5032.8  236.92
  5056.9  239.74  5163.7  241.17  5225.0  242.63  5245.5  242.55  5286.3  244.11
  5300.7  244.08  5540.1  253.58  5688.3  258.00  5780.3  259.72  5933.4  261.14
#Mann=4,-1,0
  3981.0   0.035       0  4031.1    0.05       0  5028.8    0.05       0
  5032.8    0.05       0
Bank Sta=5028.8,5032.8
Exp/Cntr=0.3,0.1

Type RM Length L Ch R = 1,5892,472,472,472
BEGIN DESCRIPTION:
Stream0488 13.0
END DESCRIPTION:
XS GIS Cut Line= 3
      2500775.01     13713475.01      2500175.00     13713125.00
      2499575.01     13713075.00
#Sta/Elev= 30
  4290.5  255.22  4348.4  254.21  4384.4  252.42  4458.8  250.34  4510.5  247.59
  4533.2  247.18  4603.5  243.93  4736.6  240.88  4854.1  239.44  4897.1  237.94
  4912.8  238.27  4940.1  237.59  4971.5  237.57  4977.3  237.10  4982.2  235.33
  4987.6  235.33  4993.2  234.48  4993.4  233.98  4996.9  233.98  4997.2  234.48
  5005.2  234.96  5015.2  236.90  5025.3  237.77  5042.8  238.34  5047.8  239.08
  5085.5  239.88  5195.9  240.15  5306.2  241.56  5524.5  249.16  5587.2  250.82
#Mann=3,-1,0
  4290.5    0.05       0  4993.2    0.05       0  4997.2    0.05       0
Bank Sta=4993.2,4997.2
Exp/Cntr=0.3,0.1

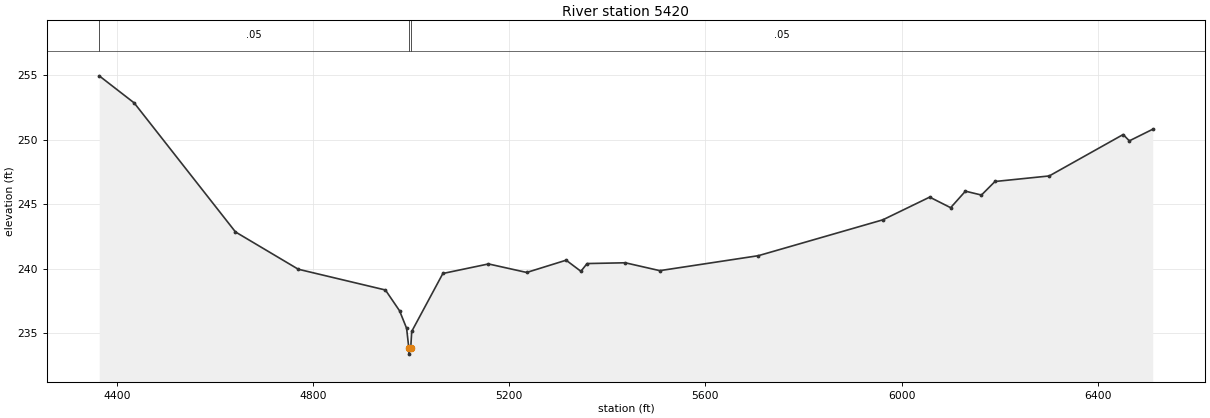
Type RM Length L Ch R = 1,5420,0,0,0
BEGIN DESCRIPTION:
Stream0488 12.0
END DESCRIPTION:
XS GIS Cut Line= 3
      2500825.02     13713375.03      2500425.00     13712875.00
      2498925.03     13712725.00
#Sta/Elev= 30
  4364.3  254.97  4435.6  252.87  4642.1  242.87  4770.1  239.98  4947.8  238.37
  4976.6  236.76  4991.0  235.40  4995.4  233.90  4995.7  233.40  4999.4  233.90
  5001.4  235.16  5064.9  239.65  5157.9  240.39  5235.8  239.73  5316.2  240.68
  5346.3  239.82  5358.9  240.42  5436.8  240.48  5507.1  239.87  5708.1  241.03
  5961.9  243.81  6057.4  245.57  6100.1  244.75  6130.2  246.03  6162.9  245.73
  6190.5  246.78  6301.1  247.21  6451.8  250.42  6464.4  249.93  6512.1  250.83
#Mann=3,-1,0
  4364.3    0.05       0  4995.4    0.05       0  4999.4    0.05       0
Bank Sta=4995.4,4999.4
Exp/Cntr=0.3,0.1

Chan Stop Cuts=-1