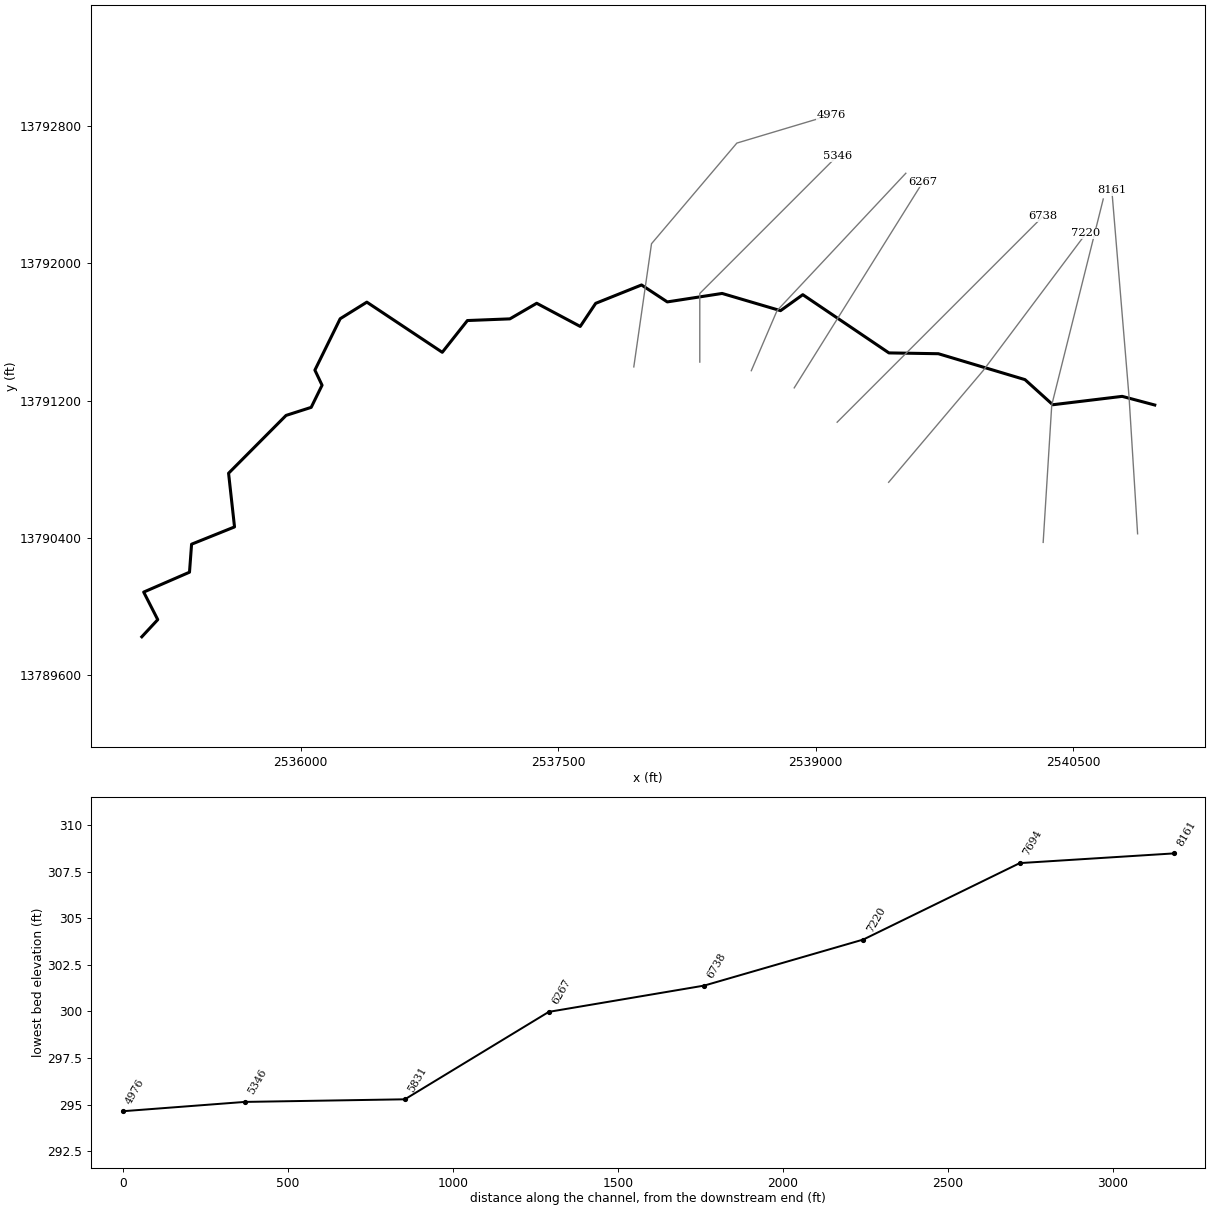
--- StreamM00.prj (project) ---

Proj Title=StreamM00 Base Level Engineering
Current Plan=p01
Default Exp/Contr=0.3,0.1
English Units
Geom File=g01
Flow File=f01
Plan File=p01
BEGIN DESCRIPTION:
StreamM00
END DESCRIPTION:

--- StreamM00.p01 (plan) ---

Plan Title=Multiple Run
Short Identifier=Multiple
Geom File=g01
Flow File=f01
Subcritical Flow
K Sum by GR= 0
Std Step Tol= 0.01
Critical Tol= 0.01
Num of Std Step Trials= 20
Max Error Tol= 0.3
Flow Tol Ratio= 0.001
Split Flow NTrial= 30
Split Flow Tol= 0.02
Split Flow Ratio= 0.02
Log Output Level= 0
Friction Slope Method= 1
Unsteady Friction Slope Method= 2
Unsteady Bridges Friction Slope Method= 1
Parabolic Critical Depth
Global Vel Dist=  1 , 1 , 1
Global Log Level= 0
CheckData=True
Encroach Param= -1, 0, 0, 0
BEGIN DESCRIPTION:
Multiple Run
END DESCRIPTION:

--- StreamM00.f01 (steady flow) ---

Flow Title=Multiple
Number of Profiles=7
Profile Names=10-year,25-year,50-year,1pct_min,100-year,1pct_plu,500-year
River Rch & RM= StreamM00,Reach-1,8161
     806    1297    1740    1130    2255    4499    3746
River Rch & RM= StreamM00,Reach-1,7694
     948    1533    2064    1343    2680    5348    4474
Boundary for River Rch & Prof#=StreamM00,Reach-1,1
Up Type=0
Dn Type=3
Dn Slope=0.005
Boundary for River Rch & Prof#=StreamM00,Reach-1,2
Up Type=0
Dn Type=3
Dn Slope=0.005
Boundary for River Rch & Prof#=StreamM00,Reach-1,3
Up Type=0
Dn Type=3
Dn Slope=0.005
Boundary for River Rch & Prof#=StreamM00,Reach-1,4
Up Type=0
Dn Type=3
Dn Slope=0.005
Boundary for River Rch & Prof#=StreamM00,Reach-1,5
Up Type=0
Dn Type=3
Dn Slope=0.005
Boundary for River Rch & Prof#=StreamM00,Reach-1,6
Up Type=0
Dn Type=3
Dn Slope=0.005
Boundary for River Rch & Prof#=StreamM00,Reach-1,7
Up Type=0
Dn Type=3
Dn Slope=0.005

--- StreamM00.g01 (geometry) ---

Geom Title=Existing Conditions

River Reach=StreamM00,Reach-1
Reach XY= 30
      2540975.00     13791175.00      2540785.19     13791225.45
      2540381.03     13791176.62      2540219.14     13791322.93
      2539714.50     13791473.80      2539426.47     13791478.55
      2538924.92     13791817.70      2538795.21     13791724.65
      2538454.97     13791824.93      2538135.62     13791775.61
      2537985.70     13791874.30      2537718.55     13791767.25
      2537628.67     13791632.69      2537375.08     13791767.70
      2537218.88     13791676.84      2536971.42     13791667.10
      2536825.01     13791482.07      2536385.68     13791774.26
      2536230.42     13791677.67      2536083.07     13791378.31
      2536124.86     13791290.41      2536061.56     13791161.37
      2535915.22     13791114.48      2535580.36     13790777.70
      2535614.97     13790464.94      2535364.88     13790364.37
      2535352.70     13790201.27      2535085.93     13790085.43
      2535167.81     13789924.91      2535075.00     13789825.00

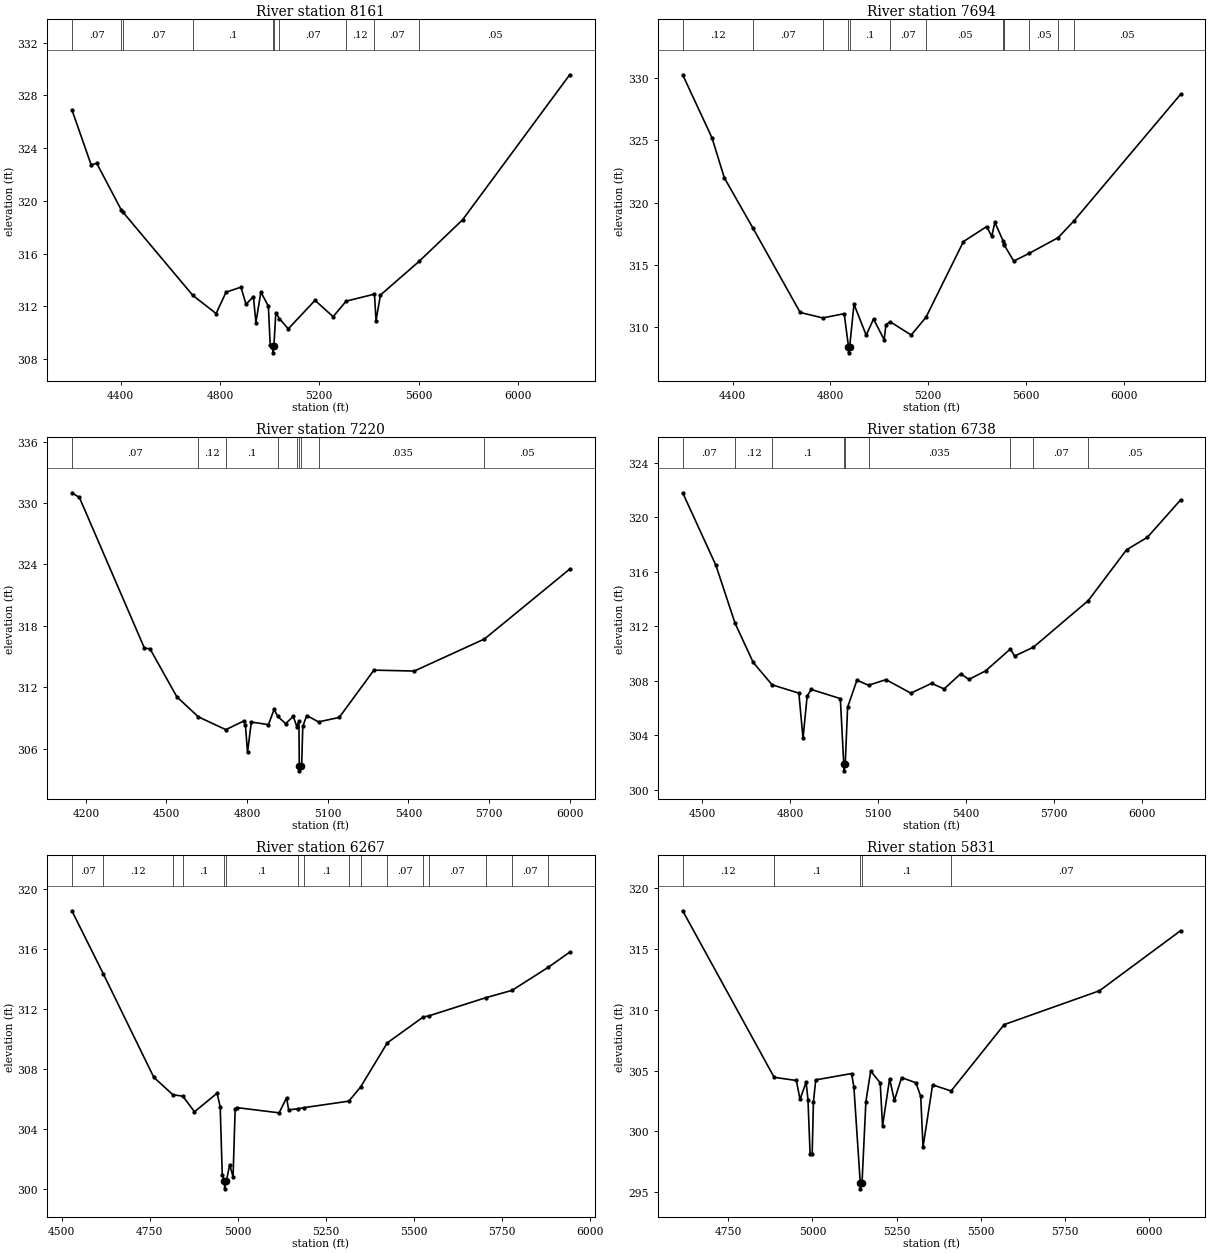
Type RM Length L Ch R = 1,8161,467,467,467
BEGIN DESCRIPTION:
StreamM00 13.0
END DESCRIPTION:
XS GIS Cut Line= 3
      2540875.00     13790424.98      2540825.00     13791225.00
      2540725.00     13792424.96
#Sta/Elev= 30
  4203.1  326.91  4280.8  322.73  4303.3  322.85  4402.2  319.31  4409.2  319.14
  4690.6  312.83  4784.3  311.46  4824.3  313.08  4884.4  313.46  4904.5  312.16
  4934.5  312.74  4944.6  310.78  4964.6  313.09  4994.7  312.02  5002.2  309.06
  5012.5  308.98  5012.8  308.48  5017.0  308.98  5024.8  311.52  5039.5  311.07
  5074.9  310.30  5182.8  312.46  5255.6  311.22  5308.3  312.40  5422.2  312.93
  5428.6  310.92  5446.2  312.86  5603.0  315.43  5777.4  318.57  6208.8  329.56
#Mann=10,-1,0
  4203.1    0.07       0  4402.2    0.12       0  4409.2    0.07       0
  4690.6     0.1       0  5012.5    0.05       0  5017.0     0.1       0
  5039.5    0.07       0  5308.3    0.12       0  5422.2    0.07       0
  5603.0    0.05       0
Bank Sta=5012.5,5017
Exp/Cntr=0.3,0.1

Type RM Length L Ch R = 1,7694,474,474,474
BEGIN DESCRIPTION:
StreamM00 12.0
END DESCRIPTION:
XS GIS Cut Line= 3
      2540325.00     13790374.97      2540375.00     13791175.00
      2540675.00     13792374.98
#Sta/Elev= 30
  4194.8  330.26  4315.1  325.19  4365.2  322.00  4481.1  318.01  4675.8  311.20
  4768.2  310.76  4856.1  311.10  4873.7  308.46  4874.1  307.96  4878.6  308.46
  4896.2  311.86  4946.3  309.37  4976.3  310.68  5019.6  309.01  5027.3  310.23
  5044.6  310.45  5130.4  309.39  5191.0  310.81  5344.3  316.88  5439.6  318.09
  5460.2  317.30  5473.1  318.42  5507.5  316.91  5510.7  316.72  5512.0  316.59
  5550.4  315.32  5612.9  315.93  5732.3  317.20  5795.3  318.51  6233.3  328.69
#Mann=13,-1,0
  4194.8    0.12       0  4481.1    0.07       0  4768.2     0.1       0
  4873.7    0.05       0  4878.6     0.1       0  5044.6    0.07       0
  5191.0    0.05       0  5507.5   0.035       0  5510.7    0.05       0
  5512.0   0.035       0  5612.9    0.05       0  5732.3   0.035       0
  5795.3    0.05       0
Bank Sta=4873.7,4878.6
Exp/Cntr=0.3,0.1

Type RM Length L Ch R = 1,7220,482,482,482
BEGIN DESCRIPTION:
StreamM00 11.0
END DESCRIPTION:
XS GIS Cut Line= 3
      2539424.98     13790724.97      2539975.00     13791375.00
      2540575.00     13792174.99
#Sta/Elev= 30
  4148.1  331.00  4176.1  330.54  4417.9  315.84  4438.7  315.77  4538.7  311.08
  4618.4  309.13  4720.7  307.88  4787.0  308.72  4793.6  308.30  4801.3  305.67
  4815.6  308.62  4879.3  308.37  4900.2  309.86  4913.5  309.18  4943.0  308.47
  4971.6  309.17  4984.8  308.17  4992.5  308.73  4993.9  304.36  4994.2  303.86
  4998.8  304.36  5002.7  304.36  5006.9  308.20  5021.5  309.26  5065.5  308.64
  5142.3  309.07  5271.5  313.69  5421.5  313.60  5682.6  316.73  5999.6  323.55
#Mann=9,-1,0
  4148.1    0.07       0  4618.4    0.12       0  4720.7     0.1       0
  4913.5    0.05       0  4984.8     0.1       0  4993.9    0.05       0
  4998.8     0.1       0  5065.5   0.035       0  5682.6    0.05       0
Bank Sta=4993.9,4998.8
Exp/Cntr=0.3,0.1

Type RM Length L Ch R = 1,6738,471,471,471
BEGIN DESCRIPTION:
StreamM00 10.0
END DESCRIPTION:
XS GIS Cut Line= 3
      2539124.97     13791074.97      2539525.00     13791475.00
      2540325.01     13792275.01
#Sta/Elev= 30
  4434.4  321.79  4547.6  316.47  4612.7  312.23  4674.9  309.34  4739.3  307.70
  4830.4  307.09  4844.6  303.78  4858.7  306.89  4872.8  307.36  4971.8  306.69
  4983.5  301.89  4983.9  301.39  4988.5  301.89  4996.6  306.06  5028.4  308.04
  5068.0  307.67  5127.4  308.08  5212.3  307.09  5283.0  307.81  5325.4  307.40
  5382.0  308.51  5410.2  308.10  5466.8  308.72  5551.5  310.33  5565.8  309.81
  5629.9  310.46  5817.0  313.88  5947.6  317.61  6018.4  318.52  6131.5  321.26
#Mann=9,-1,0
  4434.4    0.07       0  4612.7    0.12       0  4739.3     0.1       0
  4983.5    0.05       0  4988.5     0.1       0  5068.0   0.035       0
  5551.5    0.05       0  5629.9    0.07       0  5817.0    0.05       0
Bank Sta=4983.5,4988.5
Exp/Cntr=0.3,0.1

Type RM Length L Ch R = 1,6267,436,436,436
BEGIN DESCRIPTION:
StreamM00 9.0
END DESCRIPTION:
XS GIS Cut Line= 3
      2538874.98     13791274.97      2539125.00     13791675.00
      2539624.99     13792474.98
#Sta/Elev= 30
  4528.5  318.53  4617.7  314.33  4761.4  307.42  4815.6  306.26  4844.1  306.16
  4877.0  305.12  4941.3  306.36  4950.1  305.45  4956.0  300.90  4962.3  300.48
  4962.7  299.98  4967.5  300.48  4977.2  301.59  4986.7  300.77  4992.6  305.28
  4997.3  305.40  5117.6  305.05  5138.8  306.06  5144.7  305.25  5171.3  305.32
  5189.0  305.40  5315.9  305.83  5349.1  306.77  5425.2  309.72  5527.0  311.44
  5543.4  311.52  5704.8  312.73  5779.6  313.22  5882.7  314.76  5943.6  315.77
#Mann=16,-1,0
  4528.5    0.07       0  4617.7    0.12       0  4815.6   0.035       0
  4844.1     0.1       0  4962.3    0.05       0  4967.5     0.1       0
  5171.3   0.035       0  5189.0     0.1       0  5315.9    0.07       0
  5349.1   0.035       0  5425.2    0.07       0  5527.0   0.035       0
  5543.4    0.07       0  5704.8   0.035       0  5779.6    0.07       0
  5882.7   0.035       0
Bank Sta=4962.3,4967.5
Exp/Cntr=0.3,0.1

Type RM Length L Ch R = 1,5831,485,485,485
BEGIN DESCRIPTION:
StreamM00 8.0
END DESCRIPTION:
XS GIS Cut Line= 3
      2538624.99     13791374.97      2538775.00     13791725.00
      2539524.99     13792524.99
#Sta/Elev= 30
  4615.1  318.13  4886.5  304.45  4952.4  304.19  4963.3  302.64  4981.4  304.05
  4986.9  302.60  4993.2  298.16  4999.4  298.16  5003.0  302.39  5009.9  304.24
  5116.3  304.76  5123.2  303.64  5142.0  295.79  5142.4  295.29  5147.3  295.79
  5158.8  302.46  5173.0  304.96  5201.3  304.00  5208.2  300.45  5229.2  304.33
  5243.3  302.55  5264.8  304.43  5307.3  304.00  5321.5  302.88  5328.3  298.72
  5356.7  303.83  5411.7  303.33  5569.1  308.78  5851.9  311.56  6092.5  316.49
#Mann=5,-1,0
  4615.1    0.12       0  4886.5     0.1       0  5142.0    0.05       0
  5147.3     0.1       0  5411.7    0.07       0
Bank Sta=5142,5147.3
Exp/Cntr=0.3,0.1

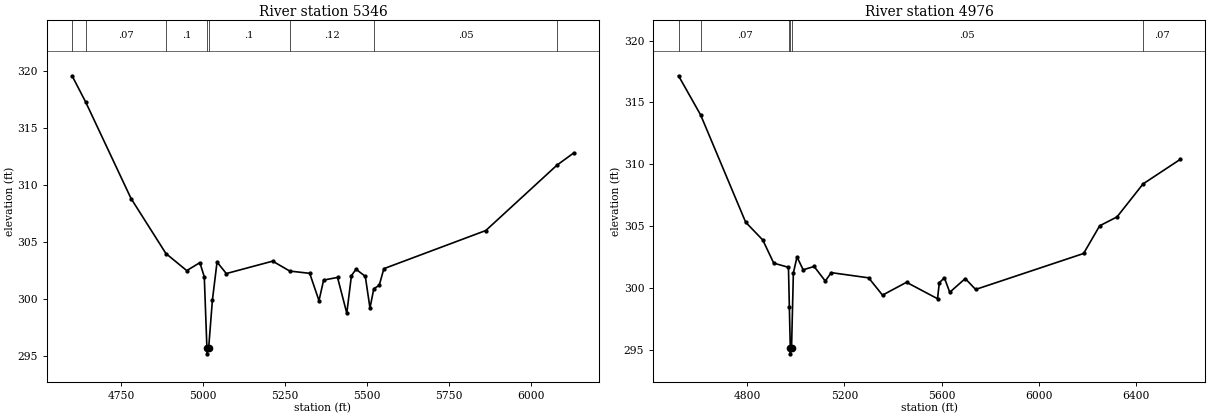
Type RM Length L Ch R = 1,5346,370,370,370
BEGIN DESCRIPTION:
StreamM00 7.0
END DESCRIPTION:
XS GIS Cut Line= 3
      2538325.00     13791425.04      2538325.00     13791825.00
      2539124.98     13792624.98
#Sta/Elev= 30
  4599.9  319.57  4641.5  317.26  4779.9  308.79  4886.3  303.96  4949.9  302.46
  4989.9  303.16  5003.4  301.91  5011.4  295.65  5011.8  295.15  5016.7  295.65
  5028.1  299.85  5042.3  303.21  5070.6  302.20  5212.0  303.29  5264.2  302.42
  5325.1  302.22  5353.4  299.82  5367.6  301.63  5410.0  301.86  5438.3  298.72
  5452.4  302.02  5466.6  302.58  5494.8  301.95  5509.0  299.17  5520.7  300.87
  5537.3  301.17  5551.4  302.63  5862.5  305.98  6079.6  311.72  6131.2  312.80
#Mann=8,-1,0
  4599.9    0.12       0  4641.5    0.07       0  4886.3     0.1       0
  5011.4    0.05       0  5016.7     0.1       0  5264.2    0.12       0
  5520.7    0.05       0  6079.6    0.07       0
Bank Sta=5011.4,5016.7
Exp/Cntr=0.3,0.1

Type RM Length L Ch R = 1,4976,0,0,0
BEGIN DESCRIPTION:
H21142
END DESCRIPTION:
XS GIS Cut Line= 4
      2537940.59     13791396.99      2538043.76     13792114.49
      2538540.82     13792700.65      2539089.48     13792864.78
#Sta/Elev= 30
  4517.0  317.15  4608.0  313.98  4793.4  305.30  4863.9  303.86  4909.0  301.99
  4969.6  301.65  4973.3  298.44  4977.1  295.15  4977.5  294.65  4982.4  295.15
  4989.8  301.19  5004.8  302.49  5030.2  301.45  5075.3  301.72  5121.2  300.54
  5145.8  301.22  5299.7  300.80  5356.9  299.40  5455.7  300.44  5583.4  299.11
  5590.8  300.41  5611.7  300.80  5633.7  299.63  5697.4  300.74  5740.3  299.86
  6184.8  302.77  6251.0  305.01  6322.4  305.73  6429.7  308.40  6583.1  310.39
#Mann=6,-1,0
  4517.0    0.12       0  4608.0    0.07       0  4973.3    0.05       0
  4977.1    0.05       0  4982.4    0.05       0  6429.7    0.07       0
Bank Sta=4977.1,4982.4
Exp/Cntr=0.3,0.1

Chan Stop Cuts=-1