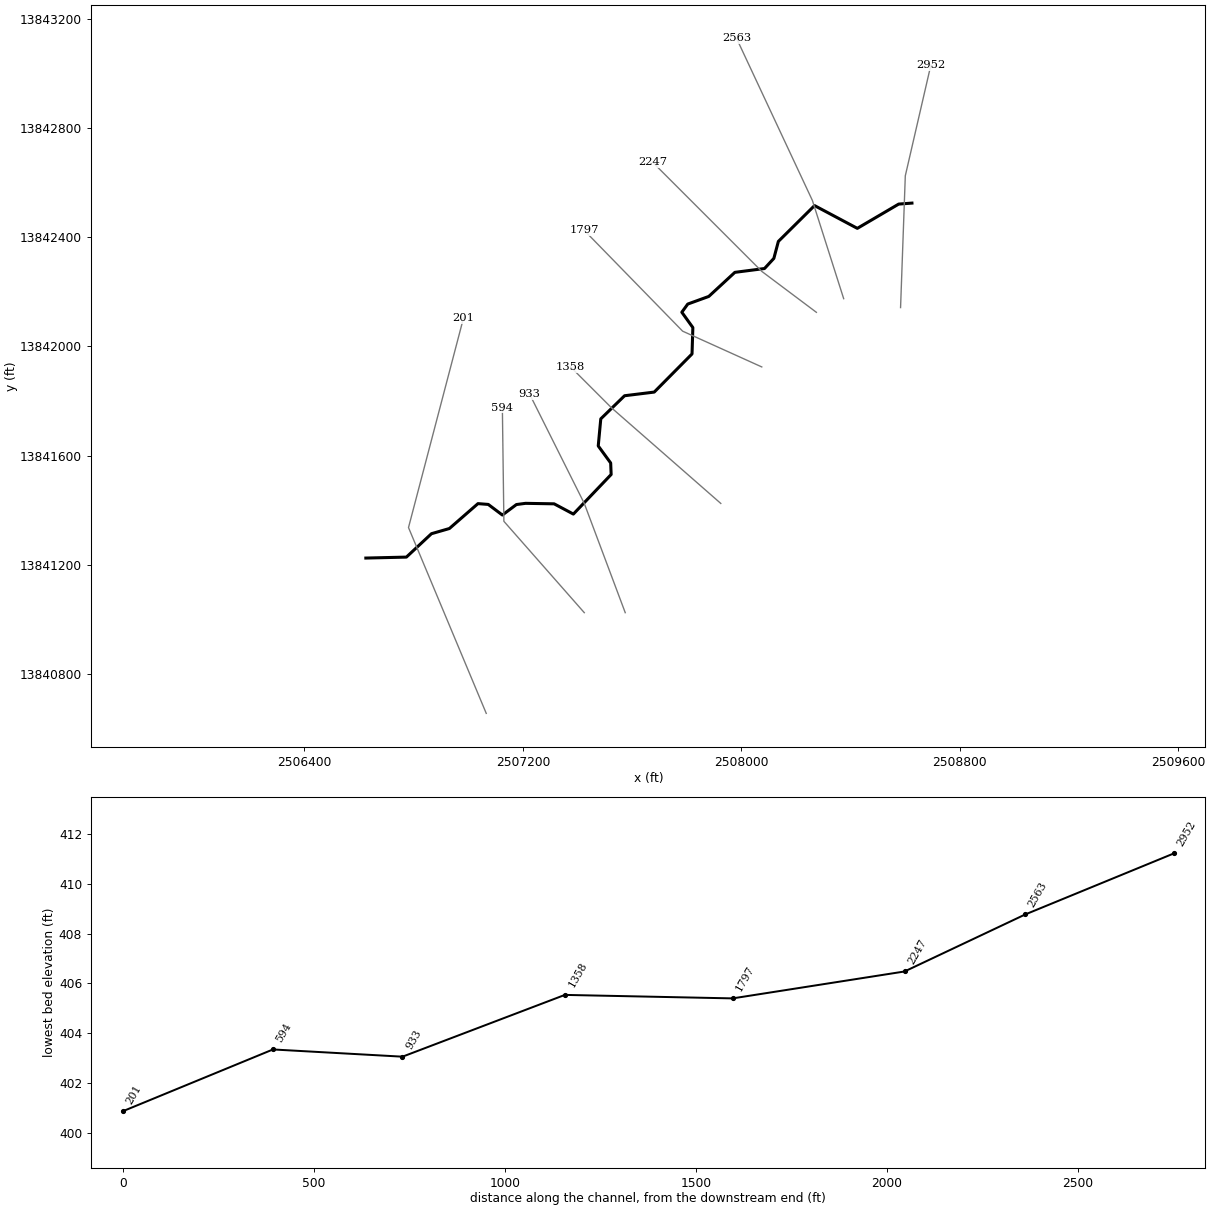
--- StreamM011.prj (project) ---

Proj Title=StreamM011 Base Level Engineering
Current Plan=p01
Default Exp/Contr=0.3,0.1
English Units
Geom File=g01
Flow File=f01
Plan File=p01
BEGIN DESCRIPTION:
StreamM011
END DESCRIPTION:

--- StreamM011.p01 (plan) ---

Plan Title=Multiple Run
Short Identifier=Multiple
Geom File=g01
Flow File=f01
Subcritical Flow
K Sum by GR= 0
Std Step Tol= 0.01
Critical Tol= 0.01
Num of Std Step Trials= 20
Max Error Tol= 0.3
Flow Tol Ratio= 0.001
Split Flow NTrial= 30
Split Flow Tol= 0.02
Split Flow Ratio= 0.02
Log Output Level= 0
Friction Slope Method= 1
Unsteady Friction Slope Method= 2
Unsteady Bridges Friction Slope Method= 1
Parabolic Critical Depth
Global Vel Dist=  1 , 1 , 1
Global Log Level= 0
CheckData=True
Encroach Param= -1, 0, 0, 0
BEGIN DESCRIPTION:
Multiple Run
END DESCRIPTION:

--- StreamM011.f01 (steady flow) ---

Flow Title=Multiple
Number of Profiles=7
Profile Names=10-year,25-year,50-year,1pct_min,100-year,1pct_plu,500-year
River Rch & RM= StreamM011,Reach-1,2952
     908    1484    2012    1320    2633    5254    4466
Boundary for River Rch & Prof#=StreamM011,Reach-1,1
Up Type=0
Dn Type=3
Dn Slope=0.005
Boundary for River Rch & Prof#=StreamM011,Reach-1,2
Up Type=0
Dn Type=3
Dn Slope=0.005
Boundary for River Rch & Prof#=StreamM011,Reach-1,3
Up Type=0
Dn Type=3
Dn Slope=0.005
Boundary for River Rch & Prof#=StreamM011,Reach-1,4
Up Type=0
Dn Type=3
Dn Slope=0.005
Boundary for River Rch & Prof#=StreamM011,Reach-1,5
Up Type=0
Dn Type=3
Dn Slope=0.005
Boundary for River Rch & Prof#=StreamM011,Reach-1,6
Up Type=0
Dn Type=3
Dn Slope=0.005
Boundary for River Rch & Prof#=StreamM011,Reach-1,7
Up Type=0
Dn Type=3
Dn Slope=0.005

--- StreamM011.g01 (geometry) ---

Geom Title=Existing Conditions

River Reach=StreamM011,Reach-1
Reach XY= 30
      2508625.00     13842525.00      2508576.49     13842521.40
      2508425.00     13842432.50      2508268.27     13842515.89
      2508135.79     13842384.66      2508119.26     13842322.43
      2508085.10     13842285.39      2507976.50     13842271.37
      2507881.00     13842183.18      2507803.97     13842155.23
      2507782.23     13842125.31      2507822.63     13842069.12
      2507819.60     13841972.57      2507681.17     13841832.86
      2507572.56     13841819.48      2507485.42     13841734.81
      2507476.12     13841635.55      2507521.66     13841573.25
      2507523.38     13841531.03      2507385.06     13841386.10
      2507314.56     13841423.62      2507209.81     13841425.41
      2507176.47     13841420.99      2507124.99     13841382.59
      2507073.35     13841421.43      2507035.64     13841424.35
      2506931.04     13841333.18      2506865.33     13841314.20
      2506773.55     13841228.51      2506625.00     13841225.00

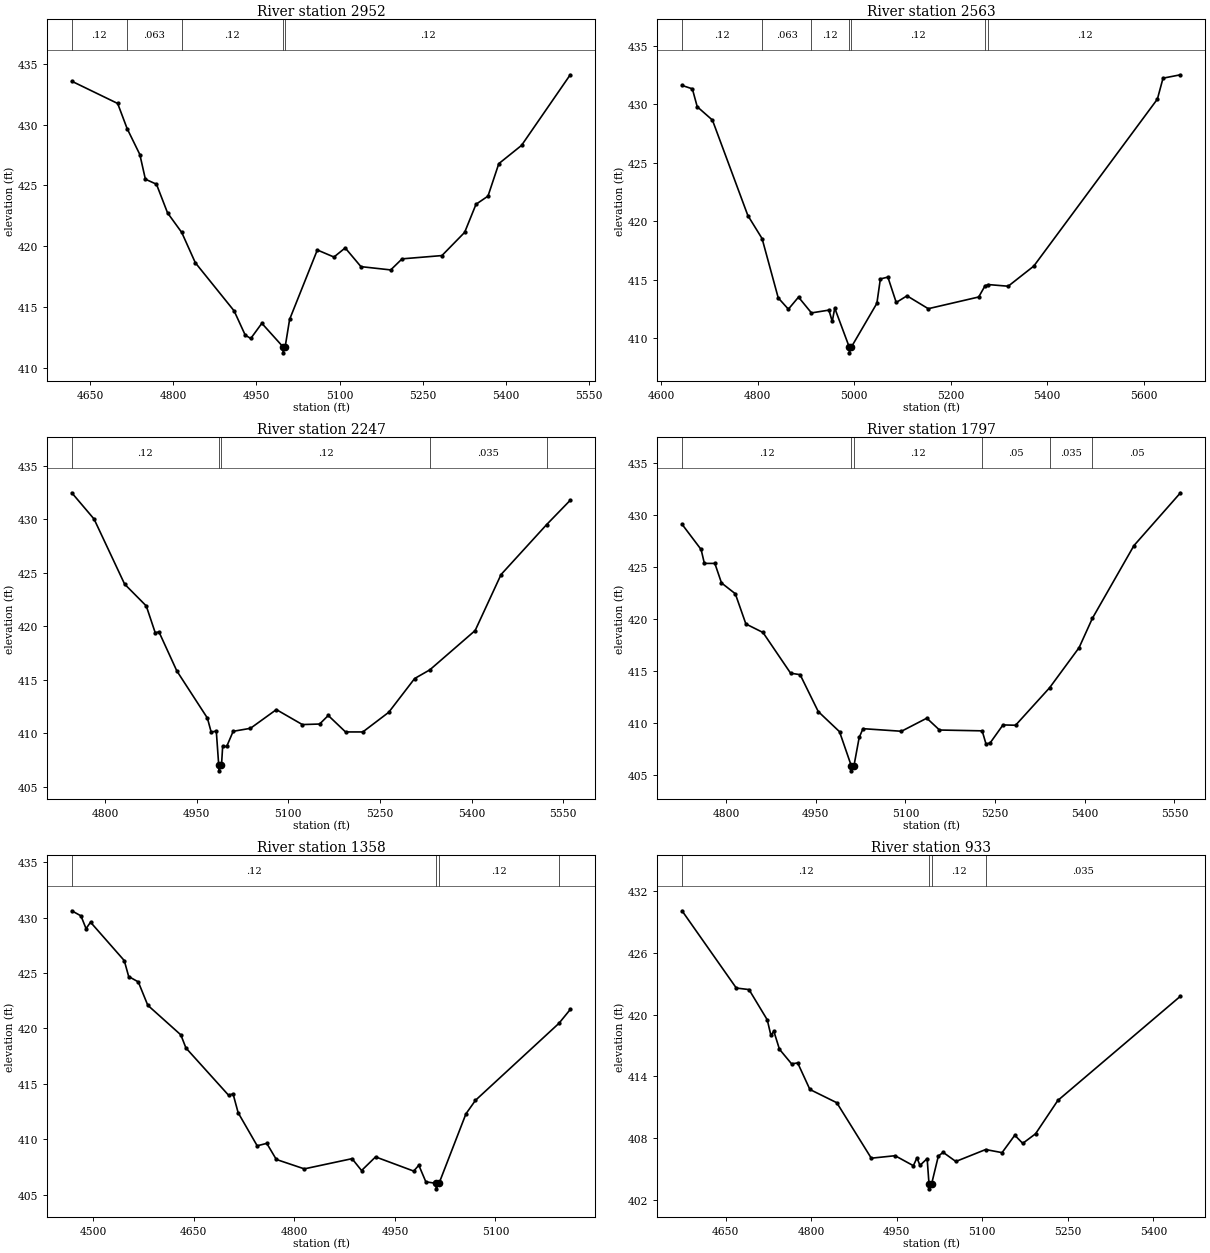
Type RM Length L Ch R = 1,2952,389,389,389
BEGIN DESCRIPTION:
H21144
END DESCRIPTION:
XS GIS Cut Line= 3
      2508583.33     13842142.28      2508600.69     13842624.93
      2508694.31     13843030.60
#Sta/Elev= 30
  4616.9  433.56  4699.7  431.73  4716.7  429.67  4739.7  427.53  4749.7  425.50
  4769.7  425.09  4789.7  422.73  4815.3  421.12  4839.8  418.63  4909.8  414.67
  4929.8  412.68  4939.8  412.40  4959.8  413.65  4997.9  411.72  4998.1  411.22
  5001.9  411.72  5009.9  413.97  5059.9  419.68  5089.9  419.10  5110.2  419.85
  5138.6  418.31  5192.3  418.04  5212.8  418.95  5284.7  419.22  5325.7  421.13
  5346.2  423.44  5367.8  424.11  5387.3  426.78  5428.3  428.28  5516.2  434.09
#Mann=5,-1,0
  4616.9    0.12       0  4716.7   0.063       0  4815.3    0.12       0
  4997.9    0.05       0  5001.9    0.12       0
Bank Sta=4997.9,5001.9
Exp/Cntr=0.3,0.1

Type RM Length L Ch R = 1,2563,316,316,316
BEGIN DESCRIPTION:
StreamM011 6.0
END DESCRIPTION:
XS GIS Cut Line= 3
      2508375.00     13842174.99      2508260.42     13842534.65
      2507982.63     13843128.41
#Sta/Elev= 30
  4643.2  431.61  4664.6  431.32  4674.7  429.79  4706.2  428.65  4779.6  420.50
  4809.1  418.53  4842.6  413.46  4863.6  412.50  4884.6  413.53  4911.4  412.18
  4947.6  412.42  4954.5  411.45  4959.7  412.59  4989.7  409.27  4990.0  408.77
  4994.2  409.27  5047.0  413.00  5054.2  415.08  5069.8  415.24  5087.1  413.07
  5109.4  413.64  5153.5  412.54  5258.0  413.54  5271.2  414.50  5278.2  414.60
  5319.1  414.46  5372.2  416.18  5628.3  430.44  5640.0  432.23  5676.2  432.52
#Mann=7,-1,0
  4643.2    0.12       0  4809.1   0.063       0  4911.4    0.12       0
  4989.7    0.05       0  4994.2    0.12       0  5271.2    0.07       0
  5278.2    0.12       0
Bank Sta=4989.7,4994.2
Exp/Cntr=0.3,0.1

Type RM Length L Ch R = 1,2247,450,450,450
BEGIN DESCRIPTION:
StreamM011 5.0
END DESCRIPTION:
XS GIS Cut Line= 3
      2508275.00     13842125.00      2508075.00     13842275.00
      2507674.99     13842675.01
#Sta/Elev= 30
  4745.8  432.50  4782.3  430.04  4832.3  423.95  4867.7  421.91  4882.3  419.41
  4888.5  419.48  4917.7  415.83  4967.7  411.42  4973.9  410.11  4982.3  410.20
  4986.3  406.98  4986.6  406.48  4990.8  406.98  4992.7  408.76  4999.3  408.76
  5009.9  410.18  5038.2  410.46  5080.6  412.21  5123.1  410.81  5151.4  410.86
  5165.5  411.66  5193.8  410.12  5222.1  410.12  5264.5  411.96  5306.9  415.12
  5331.7  415.93  5405.9  419.61  5448.3  424.85  5523.0  429.53  5561.5  431.80
#Mann=5,-1,0
  4745.8    0.12       0  4986.3    0.05       0  4990.8    0.12       0
  5331.7   0.035       0  5523.0    0.05       0
Bank Sta=4986.3,4990.8
Exp/Cntr=0.3,0.1

Type RM Length L Ch R = 1,1797,439,439,439
BEGIN DESCRIPTION:
StreamM011 4.0
END DESCRIPTION:
XS GIS Cut Line= 3
      2508075.01     13841924.99      2507785.17     13842055.99
      2507425.01     13842424.99
#Sta/Elev= 30
  4726.4  429.14  4758.3  426.71  4763.8  425.37  4781.3  425.37  4792.4  423.49
  4815.5  422.45  4833.2  419.54  4861.8  418.72  4908.0  414.80  4923.9  414.66
  4954.2  411.11  4989.8  409.17  5009.4  405.90  5009.8  405.40  5014.0  405.90
  5022.7  408.61  5029.1  409.46  5093.4  409.21  5135.8  410.47  5157.0  409.33
  5228.4  409.25  5234.9  407.97  5241.9  408.10  5263.2  409.82  5284.3  409.79
  5341.2  413.40  5390.5  417.26  5412.7  420.08  5482.3  427.09  5560.1  432.17
#Mann=6,-1,0
  4726.4    0.12       0  5009.4    0.05       0  5014.0    0.12       0
  5228.4    0.05       0  5341.2   0.035       0  5412.7    0.05       0
Bank Sta=5009.4,5014
Exp/Cntr=0.3,0.1

Type RM Length L Ch R = 1,1358,425,425,425
BEGIN DESCRIPTION:
StreamM011 3.0
END DESCRIPTION:
XS GIS Cut Line= 3
      2507924.98     13841425.02      2507525.00     13841775.00
      2507375.01     13841924.99
#Sta/Elev= 30
  4468.0  430.61  4481.7  430.15  4489.3  429.00  4496.0  429.58  4546.3  426.12
  4552.9  424.68  4567.2  424.20  4581.4  422.09  4630.7  419.42  4638.3  418.24
  4701.9  413.98  4708.6  414.10  4716.2  412.40  4744.6  409.42  4758.9  409.64
  4773.1  408.19  4814.9  407.34  4886.1  408.26  4900.3  407.19  4921.2  408.42
  4978.1  407.14  4985.7  407.67  4996.2  406.17  5011.3  406.04  5011.6  405.54
  5015.9  406.04  5056.0  412.30  5070.2  413.52  5194.7  420.46  5211.6  421.71
#Mann=4,-1,0
  4468.0    0.12       0  5011.3    0.05       0  5015.9    0.12       0
  5194.7    0.07       0
Bank Sta=5011.3,5015.9
Exp/Cntr=0.3,0.1

Type RM Length L Ch R = 1,933,339,339,339
BEGIN DESCRIPTION:
StreamM011 2.0
END DESCRIPTION:
XS GIS Cut Line= 3
      2507575.00     13841024.99      2507425.00     13841425.00
      2507225.01     13841824.98
#Sta/Elev= 30
  4573.2  430.09  4668.4  422.58  4690.7  422.43  4722.7  419.49  4729.0  418.00
  4734.3  418.37  4744.1  416.63  4765.4  415.21  4776.1  415.30  4797.5  412.72
  4844.7  411.43  4905.2  406.04  4947.0  406.28  4979.0  405.31  4985.3  406.07
  4990.6  405.34  5003.2  406.00  5006.4  403.56  5006.8  403.06  5011.1  403.56
  5022.8  406.24  5031.2  406.61  5053.5  405.72  5105.8  406.88  5134.6  406.58
  5156.9  408.27  5170.9  407.48  5193.3  408.41  5232.4  411.65  5447.6  421.79
#Mann=4,-1,0
  4573.2    0.12       0  5006.4    0.05       0  5011.1    0.12       0
  5105.8   0.035       0
Bank Sta=5006.4,5011.1
Exp/Cntr=0.3,0.1

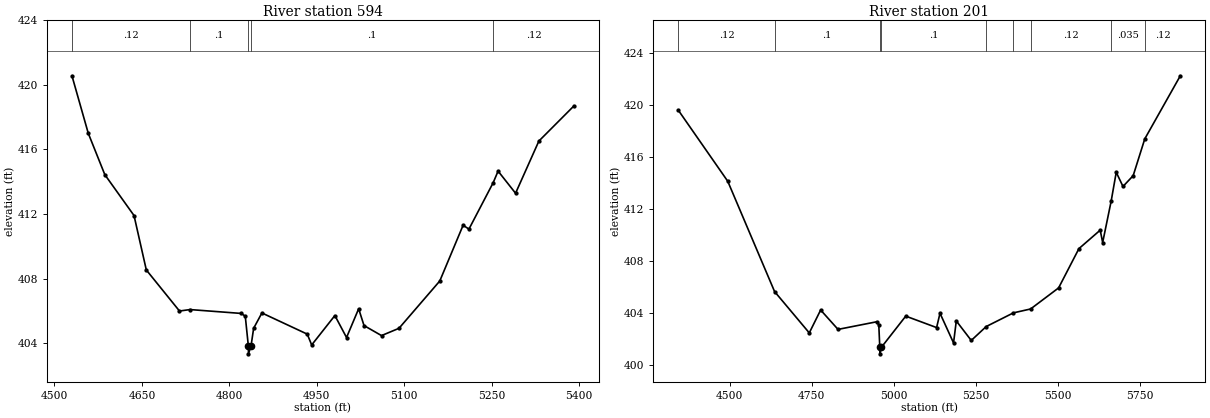
Type RM Length L Ch R = 1,594,393,393,393
BEGIN DESCRIPTION:
StreamM011 1.0
END DESCRIPTION:
XS GIS Cut Line= 3
      2507424.99     13841025.02      2507130.56     13841359.60
      2507125.00     13841774.98
#Sta/Elev= 30
  4530.0  420.56  4558.0  417.00  4586.4  414.44  4636.5  411.91  4657.6  408.54
  4714.5  406.00  4732.6  406.09  4820.8  405.85  4827.4  405.67  4832.6  403.85
  4832.9  403.35  4837.3  403.85  4841.7  404.93  4855.9  405.88  4933.7  404.57
  4941.3  403.90  4981.1  405.72  5001.1  404.36  5021.9  406.14  5031.1  405.10
  5061.1  404.48  5091.1  404.93  5161.1  407.86  5201.1  411.31  5211.1  411.07
  5252.8  413.95  5261.1  414.66  5291.1  413.29  5331.1  416.52  5391.1  418.69
#Mann=5,-1,0
  4530.0    0.12       0  4732.6     0.1       0  4832.6    0.05       0
  4837.3     0.1       0  5252.8    0.12       0
Bank Sta=4832.6,4837.3
Exp/Cntr=0.3,0.1

Type RM Length L Ch R = 1,201,0,0,0
BEGIN DESCRIPTION:
H21143
END DESCRIPTION:
XS GIS Cut Line= 3
      2507065.97     13840656.18      2506781.25     13841336.73
      2506982.65     13842104.13
#Sta/Elev= 30
  4343.2  419.59  4493.7  414.14  4636.5  405.66  4742.4  402.48  4777.1  404.24
  4830.1  402.75  4949.0  403.34  4954.5  403.08  4957.5  401.37  4957.9  400.87
  4962.3  401.37  5036.7  403.77  5130.8  402.89  5141.2  403.99  5182.5  401.71
  5190.9  403.40  5236.5  401.90  5282.2  402.97  5365.1  404.02  5417.6  404.32
  5503.0  405.94  5565.0  408.96  5629.9  410.38  5637.4  409.43  5663.4  412.62
  5678.8  414.83  5699.4  413.74  5730.5  414.57  5765.9  417.40  5874.3  422.25
#Mann=9,-1,0
  4343.2    0.12       0  4636.5     0.1       0  4957.5    0.05       0
  4962.3     0.1       0  5282.2    0.12       0  5365.1     0.1       0
  5417.6    0.12       0  5663.4   0.035       0  5765.9    0.12       0
Bank Sta=4957.5,4962.3
Exp/Cntr=0.3,0.1

Chan Stop Cuts=-1