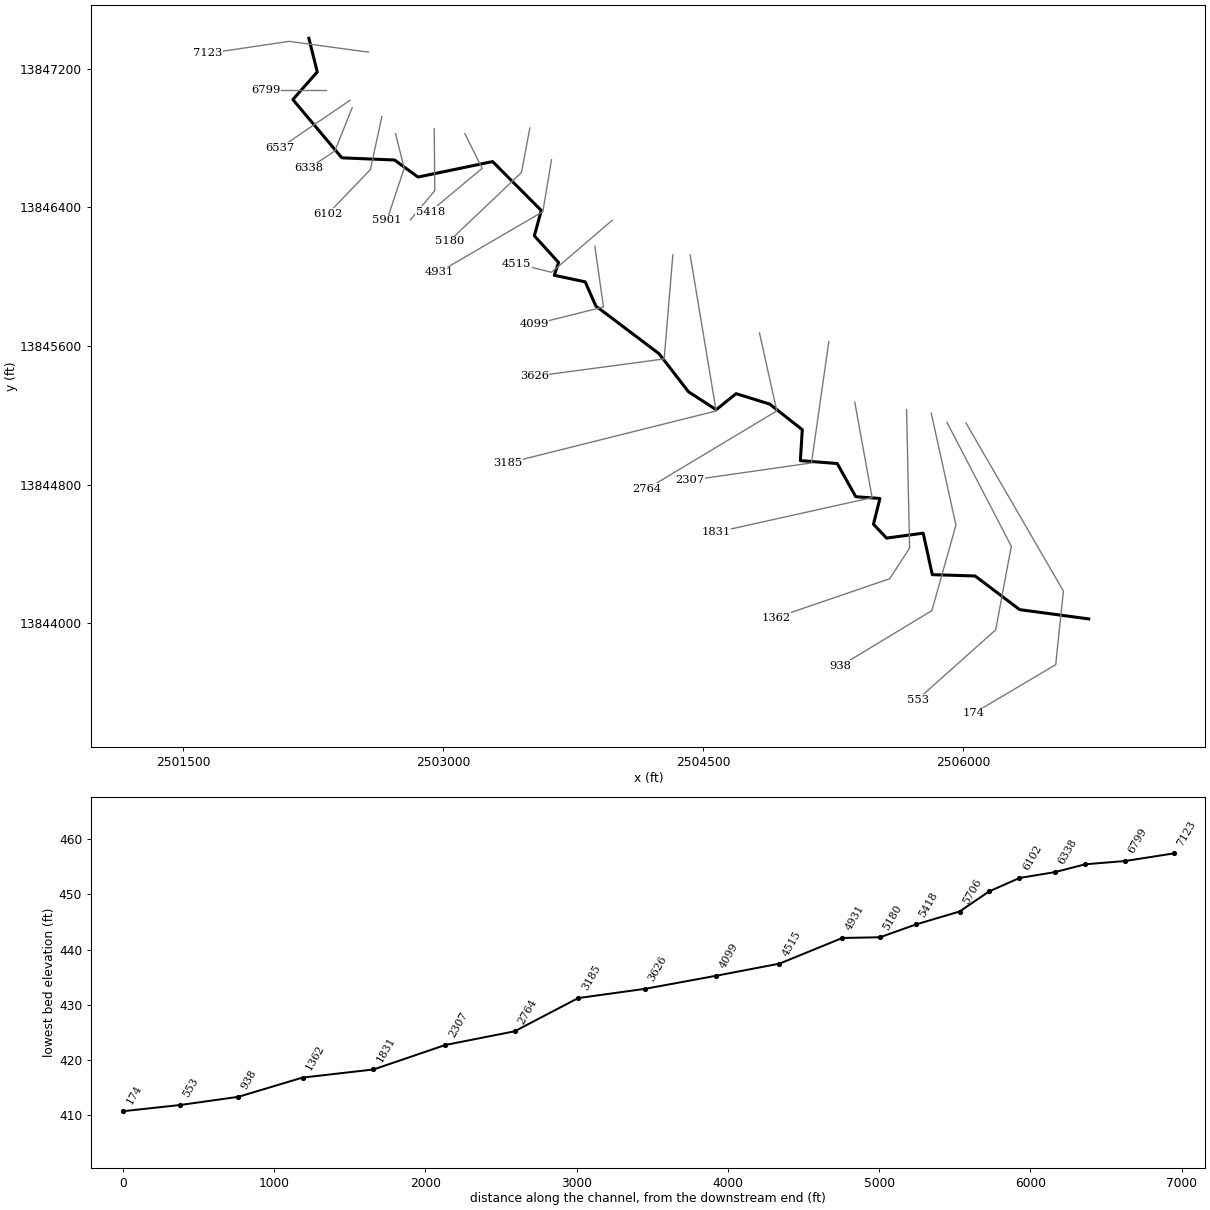
--- StreamM012.prj (project) ---

Proj Title=StreamM012 Base Level Engineering
Current Plan=p01
Default Exp/Contr=0.3,0.1
English Units
Geom File=g01
Flow File=f01
Plan File=p01
BEGIN DESCRIPTION:
StreamM012
END DESCRIPTION:

--- StreamM012.p01 (plan) ---

Plan Title=Multiple Run
Short Identifier=Multiple
Geom File=g01
Flow File=f01
Subcritical Flow
K Sum by GR= 0
Std Step Tol= 0.01
Critical Tol= 0.01
Num of Std Step Trials= 20
Max Error Tol= 0.3
Flow Tol Ratio= 0.001
Split Flow NTrial= 30
Split Flow Tol= 0.02
Split Flow Ratio= 0.02
Log Output Level= 0
Friction Slope Method= 1
Unsteady Friction Slope Method= 2
Unsteady Bridges Friction Slope Method= 1
Parabolic Critical Depth
Global Vel Dist=  1 , 1 , 1
Global Log Level= 0
CheckData=True
Encroach Param= -1, 0, 0, 0
BEGIN DESCRIPTION:
Multiple Run
END DESCRIPTION:

--- StreamM012.f01 (steady flow) ---

Flow Title=Multiple
Number of Profiles=7
Profile Names=10-year,25-year,50-year,1pct_min,100-year,1pct_plu,500-year
River Rch & RM= StreamM012,Reach-1,7123
     284     432     559     352     702    1400    1092
River Rch & RM= StreamM012,Reach-1,5706
     406     634     833     532    1061    2116    1700
River Rch & RM= StreamM012,Reach-1,3185
     498     785    1040     668    1333    2659    2164
Boundary for River Rch & Prof#=StreamM012,Reach-1,1
Up Type=0
Dn Type=3
Dn Slope=0.005
Boundary for River Rch & Prof#=StreamM012,Reach-1,2
Up Type=0
Dn Type=3
Dn Slope=0.005
Boundary for River Rch & Prof#=StreamM012,Reach-1,3
Up Type=0
Dn Type=3
Dn Slope=0.005
Boundary for River Rch & Prof#=StreamM012,Reach-1,4
Up Type=0
Dn Type=3
Dn Slope=0.005
Boundary for River Rch & Prof#=StreamM012,Reach-1,5
Up Type=0
Dn Type=3
Dn Slope=0.005
Boundary for River Rch & Prof#=StreamM012,Reach-1,6
Up Type=0
Dn Type=3
Dn Slope=0.005
Boundary for River Rch & Prof#=StreamM012,Reach-1,7
Up Type=0
Dn Type=3
Dn Slope=0.005

--- StreamM012.g01 (geometry) ---

Geom Title=Existing Conditions

River Reach=StreamM012,Reach-1
Reach XY= 30
      2502225.00     13847375.00      2502273.39     13847181.03
      2502132.59     13847021.67      2502415.20     13846685.48
      2502719.14     13846672.93      2502854.82     13846574.57
      2503285.06     13846663.90      2503565.87     13846381.74
      2503525.94     13846235.48      2503665.69     13846081.66
      2503641.20     13846007.87      2503819.58     13845969.82
      2503880.59     13845830.61      2504245.47     13845555.37
      2504415.32     13845335.78      2504575.00     13845232.09
      2504690.22     13845324.75      2504884.68     13845264.24
      2505072.02     13845116.66      2505060.87     13844938.36
      2505273.75     13844921.55      2505380.42     13844730.18
      2505520.06     13844719.96      2505482.80     13844571.55
      2505558.22     13844491.29      2505769.62     13844519.83
      2505822.22     13844280.36      2506069.07     13844272.76
      2506326.46     13844078.54      2506725.00     13844025.00

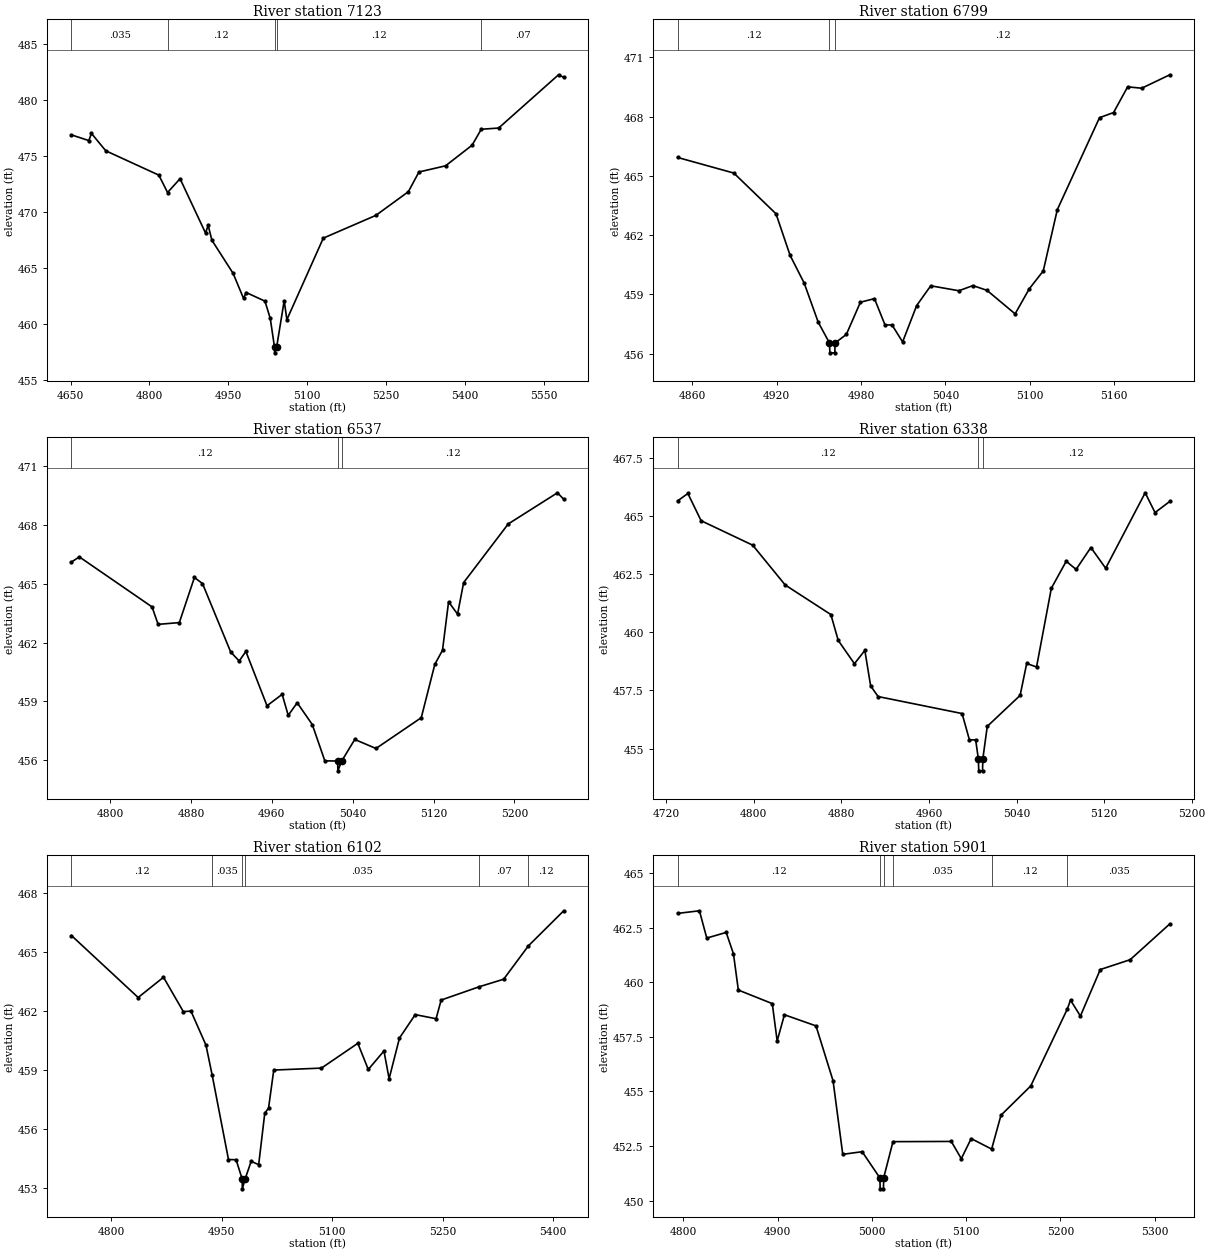
Type RM Length L Ch R = 1,7123,324,324,324
BEGIN DESCRIPTION:
H21153
END DESCRIPTION:
XS GIS Cut Line= 3
      2502569.72     13847295.14      2502111.37     13847357.64
      2501642.58     13847288.19
#Sta/Elev= 30
  4651.7  476.87  4684.7  476.36  4689.7  477.00  4717.0  475.45  4817.9  473.28
  4834.5  471.73  4858.3  472.96  4906.7  468.12  4911.8  468.79  4918.9  467.47
  4959.2  464.52  4979.0  462.29  4984.1  462.81  5019.8  462.04  5029.9  460.50
  5038.0  457.93  5038.2  457.43  5042.0  457.93  5056.4  462.08  5061.5  460.39
  5130.8  467.66  5230.8  469.69  5292.6  471.80  5312.8  473.56  5363.4  474.11
  5413.9  475.95  5431.3  477.37  5464.4  477.48  5578.3  482.23  5588.2  482.00
#Mann=5,-1,0
  4651.7   0.035       0  4834.5    0.12       0  5038.0    0.05       0
  5042.0    0.12       0  5431.3    0.07       0
Bank Sta=5038,5042
Exp/Cntr=0.3,0.1

Type RM Length L Ch R = 1,6799,262,262,262
BEGIN DESCRIPTION:
StreamM012 12.0
END DESCRIPTION:
XS GIS Cut Line= 3
      2502325.01     13847075.00      2502175.00     13847075.00
      2501975.01     13847075.00
#Sta/Elev= 30
  4849.5  465.93  4889.5  465.14  4919.5  463.08  4929.5  460.98  4939.5  459.58
  4949.5  457.60  4957.5  456.55  4957.8  456.05  4961.3  456.05  4961.5  456.55
  4969.5  456.98  4979.5  458.61  4989.5  458.79  4997.0  457.46  5002.0  457.46
  5009.5  456.60  5019.5  458.44  5029.5  459.44  5049.5  459.19  5059.5  459.45
  5069.5  459.21  5089.5  458.02  5099.5  459.28  5109.5  460.19  5119.5  463.29
  5149.5  467.94  5159.5  468.20  5169.5  469.50  5179.5  469.43  5199.5  470.11
#Mann=3,-1,0
  4849.5    0.12       0  4957.5    0.05       0  4961.5    0.12       0
Bank Sta=4957.5,4961.5
Exp/Cntr=0.3,0.1

Type RM Length L Ch R = 1,6537,199,199,199
BEGIN DESCRIPTION:
H21152
END DESCRIPTION:
XS GIS Cut Line= 2
      2502462.09     13847017.39      2502059.65     13846743.31
#Sta/Elev= 30
  4761.8  466.11  4769.6  466.37  4841.5  463.82  4847.5  462.93  4868.5  463.02
  4883.4  465.32  4891.4  465.01  4919.3  461.52  4927.7  461.06  4934.3  461.55
  4955.2  458.78  4970.2  459.36  4976.2  458.29  4985.1  458.93  5000.0  457.82
  5012.4  455.97  5025.1  455.96  5025.3  455.46  5029.1  455.96  5042.0  457.06
  5063.0  456.60  5107.8  458.17  5121.2  460.89  5128.8  461.61  5134.8  464.08
  5143.7  463.45  5149.7  465.06  5193.8  468.05  5242.5  469.64  5248.7  469.31
#Mann=3,-1,0
  4761.8    0.12       0  5025.1    0.05       0  5029.1    0.12       0
Bank Sta=5025.1,5029.1
Exp/Cntr=0.3,0.1

Type RM Length L Ch R = 1,6338,236,236,236
BEGIN DESCRIPTION:
StreamM012 11.0
END DESCRIPTION:
XS GIS Cut Line= 3
      2502474.99     13846974.98      2502375.00     13846725.00
      2502225.01     13846625.01
#Sta/Elev= 30
  4730.5  465.64  4739.9  465.96  4752.0  464.79  4799.1  463.74  4828.8  462.03
  4870.5  460.76  4877.2  459.65  4892.0  458.65  4901.5  459.22  4906.8  457.70
  4913.6  457.24  4990.3  456.51  4997.0  455.38  5002.7  455.38  5005.2  454.55
  5005.5  454.05  5009.0  454.05  5009.2  454.55  5013.3  455.96  5043.3  457.29
  5049.3  458.66  5058.3  458.51  5071.8  461.89  5085.4  463.05  5094.4  462.70
  5107.9  463.64  5121.4  462.75  5157.5  465.99  5166.5  465.14  5180.0  465.62
#Mann=3,-1,0
  4730.5    0.12       0  5005.2    0.05       0  5009.2    0.12       0
Bank Sta=5005.2,5009.2
Exp/Cntr=0.3,0.1

Type RM Length L Ch R = 1,6102,201,201,201
BEGIN DESCRIPTION:
H21151
END DESCRIPTION:
XS GIS Cut Line= 3
      2502646.08     13846923.60      2502580.12     13846618.06
      2502333.56     13846361.09
#Sta/Elev= 30
  4745.7  465.86  4836.3  462.71  4870.7  463.74  4897.7  461.99  4908.0  462.02
  4928.4  460.29  4936.8  458.77  4959.0  454.47  4969.3  454.46  4977.6  453.48
  4977.8  452.98  4981.6  453.48  4989.8  454.38  5000.0  454.21  5008.3  456.83
  5013.4  457.08  5020.5  459.02  5085.3  459.12  5134.7  460.38  5148.9  459.05
  5170.2  459.99  5177.2  458.58  5191.3  460.65  5212.7  461.84  5241.0  461.63
  5247.9  462.58  5299.1  463.25  5332.8  463.64  5366.5  465.34  5414.4  467.12
#Mann=6,-1,0
  4745.7    0.12       0  4936.8   0.035       0  4977.6   0.035       0
  4981.6   0.035       0  5299.1    0.07       0  5366.5    0.12       0
Bank Sta=4977.6,4981.6
Exp/Cntr=0.3,0.1

Type RM Length L Ch R = 1,5901,195,195,195
BEGIN DESCRIPTION:
StreamM012 10.0
END DESCRIPTION:
XS GIS Cut Line= 3
      2502724.99     13846825.03      2502775.00     13846625.00
      2502675.00     13846325.01
#Sta/Elev= 30
  4793.8  463.15  4817.0  463.27  4824.8  462.02  4845.4  462.28  4853.1  461.30
  4858.3  459.64  4894.3  459.02  4899.5  457.31  4907.2  458.51  4940.7  458.00
  4958.8  455.49  4969.1  452.12  4989.7  452.24  5008.5  451.04  5008.8  450.54
  5012.3  450.54  5012.5  451.04  5022.4  452.70  5084.3  452.71  5094.9  451.92
  5105.4  452.84  5127.1  452.36  5137.0  453.91  5168.6  455.25  5207.4  458.77
  5210.8  459.18  5221.3  458.45  5242.4  460.58  5274.1  461.03  5316.2  462.67
#Mann=6,-1,0
  4793.8    0.12       0  5008.5    0.05       0  5012.5    0.12       0
  5022.4   0.035       0  5127.1    0.12       0  5207.4   0.035       0
Bank Sta=5008.5,5012.5
Exp/Cntr=0.3,0.1

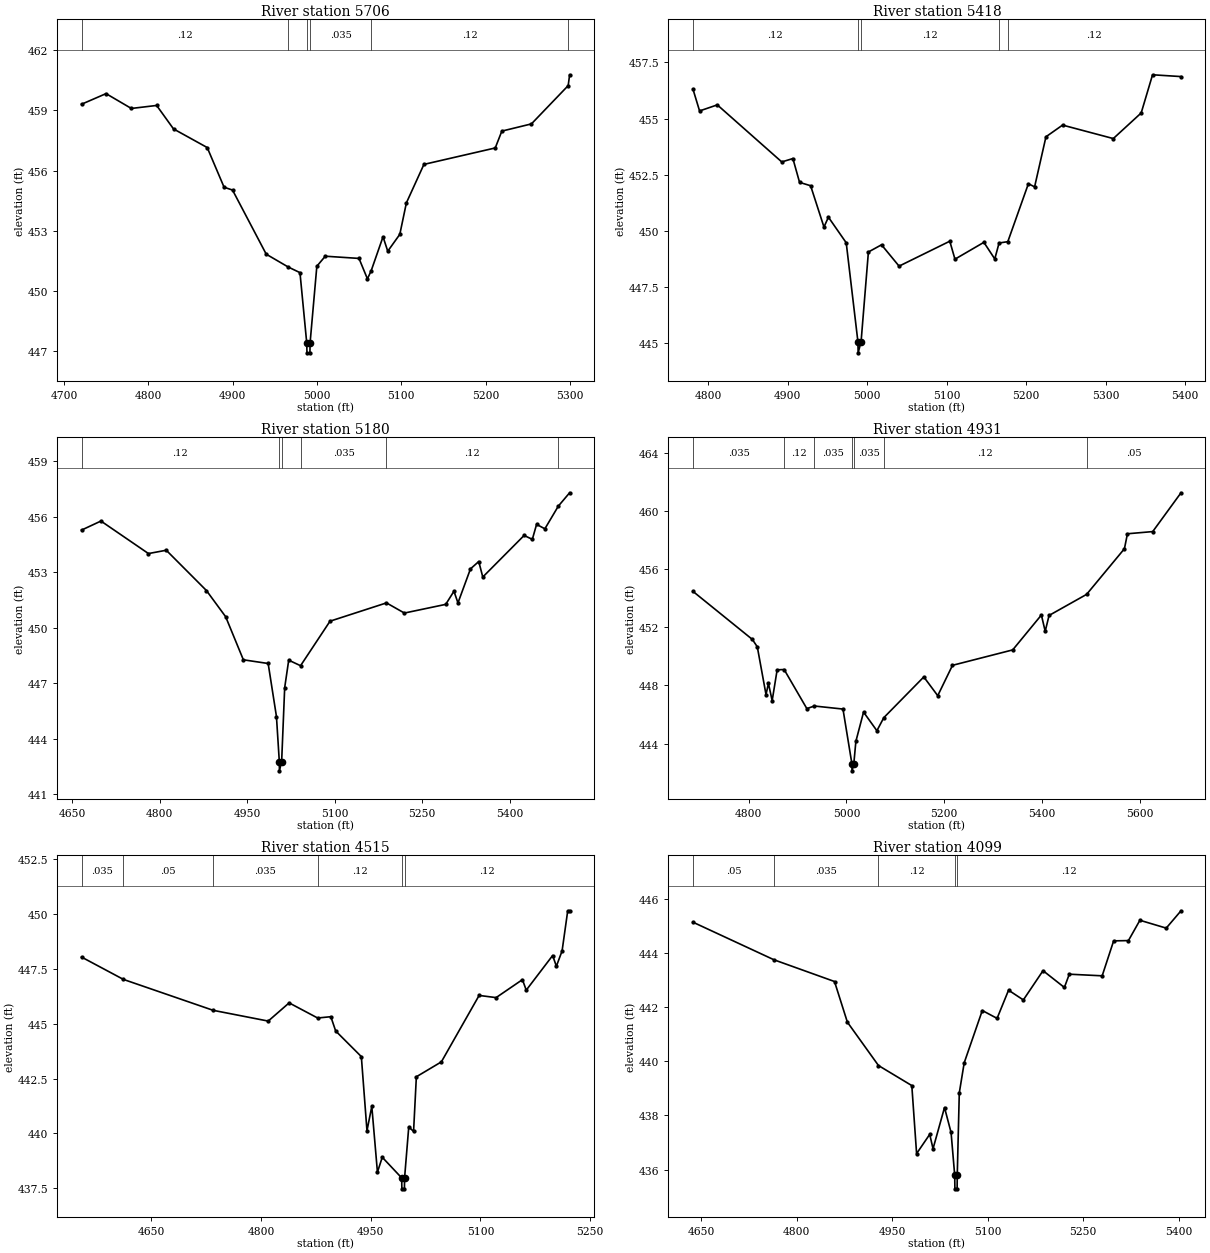
Type RM Length L Ch R = 1,5706,288,288,288
BEGIN DESCRIPTION:
H21150
END DESCRIPTION:
XS GIS Cut Line= 3
      2502948.17     13846854.13      2502951.64     13846496.53
      2502809.64     13846326.82
#Sta/Elev= 30
  4720.8  459.31  4749.9  459.84  4779.9  459.10  4809.9  459.25  4829.9  458.08
  4869.9  457.15  4889.9  455.17  4899.9  455.03  4939.9  451.83  4966.0  451.19
  4979.9  450.91  4987.9  447.41  4988.2  446.91  4991.7  446.91  4991.9  447.41
  4999.9  451.23  5009.9  451.73  5049.9  451.62  5059.9  450.60  5064.4  451.01
  5078.4  452.70  5084.0  451.98  5098.3  452.82  5106.1  454.39  5126.9  456.31
  5211.5  457.13  5219.3  457.97  5254.4  458.33  5298.0  460.24  5299.7  460.78
#Mann=6,-1,0
  4720.8    0.12       0  4966.0   0.035       0  4987.9   0.035       0
  4991.9   0.035       0  5064.4    0.12       0  5298.0    0.05       0
Bank Sta=4987.9,4991.9
Exp/Cntr=0.3,0.1

Type RM Length L Ch R = 1,5418,238,238,238
BEGIN DESCRIPTION:
StreamM012 9.0
END DESCRIPTION:
XS GIS Cut Line= 3
      2503125.00     13846824.99      2503225.00     13846625.00
      2502925.01     13846375.01
#Sta/Elev= 30
  4780.8  456.32  4789.2  455.34  4811.5  455.61  4892.6  453.07  4906.6  453.22
  4915.0  452.16  4928.9  452.01  4945.7  450.17  4951.3  450.61  4973.7  449.47
  4988.4  445.07  4988.7  444.57  4992.4  445.07  5001.6  449.06  5018.1  449.38
  5040.2  448.43  5104.0  449.54  5110.5  448.74  5146.9  449.49  5160.6  448.75
  5166.0  449.46  5177.0  449.52  5202.9  452.10  5210.7  451.96  5225.0  454.19
  5245.9  454.71  5309.7  454.11  5344.8  455.25  5359.1  456.95  5394.9  456.87
#Mann=5,-1,0
  4780.8    0.12       0  4988.4    0.05       0  4992.4    0.12       0
  5166.0   0.035       0  5177.0    0.12       0
Bank Sta=4988.4,4992.4
Exp/Cntr=0.3,0.1

Type RM Length L Ch R = 1,5180,249,249,249
BEGIN DESCRIPTION:
H21149
END DESCRIPTION:
XS GIS Cut Line= 3
      2503500.26     13846857.68      2503451.64     13846600.70
      2503034.94     13846204.83
#Sta/Elev= 30
  4666.1  455.28  4699.4  455.77  4780.8  454.01  4811.3  454.19  4880.1  452.01
  4913.1  450.59  4943.4  448.26  4985.9  448.06  5000.1  445.19  5005.0  442.75
  5005.2  442.25  5009.0  442.75  5014.2  446.75  5021.1  448.24  5041.4  447.94
  5091.9  450.35  5188.6  451.34  5219.3  450.79  5290.1  451.26  5304.2  451.97
  5311.1  451.34  5332.5  453.18  5346.7  453.58  5353.6  452.74  5424.4  454.99
  5438.5  454.78  5445.8  455.59  5460.0  455.35  5483.1  456.58  5502.4  457.30
#Mann=6,-1,0
  4666.1    0.12       0  5005.0    0.05       0  5009.0    0.12       0
  5041.4   0.035       0  5188.6    0.12       0  5483.1    0.05       0
Bank Sta=5005,5009
Exp/Cntr=0.3,0.1

Type RM Length L Ch R = 1,4931,416,416,416
BEGIN DESCRIPTION:
StreamM012 8.0
END DESCRIPTION:
XS GIS Cut Line= 3
      2503625.01     13846675.04      2503575.00     13846375.00
      2502975.00     13846025.00
#Sta/Elev= 30
  4685.8  454.47  4807.5  451.16  4817.6  450.65  4835.4  447.37  4840.4  448.13
  4848.0  446.95  4858.2  449.07  4872.5  449.09  4919.0  446.40  4934.2  446.58
  4992.9  446.37  5011.1  442.62  5011.4  442.12  5015.1  442.62  5019.3  444.15
  5035.0  446.16  5062.3  444.88  5076.5  445.78  5158.3  448.58  5186.8  447.29
  5217.0  449.38  5340.2  450.44  5398.9  452.84  5406.7  451.72  5414.6  452.81
  5491.4  454.26  5568.8  457.40  5575.0  458.43  5626.7  458.58  5684.6  461.25
#Mann=7,-1,0
  4685.8   0.035       0  4872.5    0.12       0  4934.2   0.035       0
  5011.1   0.035       0  5015.1   0.035       0  5076.5    0.12       0
  5491.4    0.05       0
Bank Sta=5011.1,5015.1
Exp/Cntr=0.3,0.1

Type RM Length L Ch R = 1,4515,416,416,416
BEGIN DESCRIPTION:
StreamM012 7.0
END DESCRIPTION:
XS GIS Cut Line= 3
      2503975.03     13846325.02      2503625.00     13846025.00
      2503424.97     13846075.01
#Sta/Elev= 30
  4554.7  448.04  4612.0  447.02  4734.7  445.61  4809.9  445.12  4838.5  445.95
  4877.5  445.26  4895.5  445.32  4902.1  444.67  4937.2  443.50  4944.9  440.12
  4951.5  441.23  4959.2  438.23  4965.8  438.91  4992.3  437.97  4992.6  437.47
  4996.1  437.47  4996.3  437.97  5002.0  440.29  5008.6  440.09  5012.4  442.58
  5046.6  443.26  5098.2  446.29  5121.4  446.19  5157.4  447.01  5162.6  446.53
  5198.7  448.11  5203.8  447.62  5211.6  448.32  5219.3  450.15  5221.9  450.15
#Mann=6,-1,0
  4554.7   0.035       0  4612.0    0.05       0  4734.7   0.035       0
  4877.5    0.12       0  4992.3    0.05       0  4996.3    0.12       0
Bank Sta=4992.3,4996.3
Exp/Cntr=0.3,0.1

Type RM Length L Ch R = 1,4099,473,473,473
BEGIN DESCRIPTION:
StreamM012 6.0
END DESCRIPTION:
XS GIS Cut Line= 3
      2503875.00     13846175.01      2503925.00     13845825.00
      2503524.97     13845724.99
#Sta/Elev= 30
  4637.4  445.13  4764.8  443.74  4859.6  442.94  4879.8  441.44  4928.6  439.84
  4980.9  439.10  4988.4  436.59  5009.0  437.30  5014.2  436.77  5032.2  438.29
  5042.5  437.37  5048.2  435.79  5048.5  435.29  5052.0  435.29  5052.2  435.79
  5055.4  438.83  5063.1  439.94  5091.5  441.87  5114.7  441.58  5132.7  442.62
  5155.9  442.26  5186.8  443.34  5220.3  442.72  5228.0  443.21  5279.6  443.15
  5297.6  444.44  5320.8  444.45  5338.8  445.20  5380.1  444.91  5403.3  445.55
#Mann=5,-1,0
  4637.4    0.05       0  4764.8   0.035       0  4928.6    0.12       0
  5048.2    0.05       0  5052.2    0.12       0
Bank Sta=5048.2,5052.2
Exp/Cntr=0.3,0.1

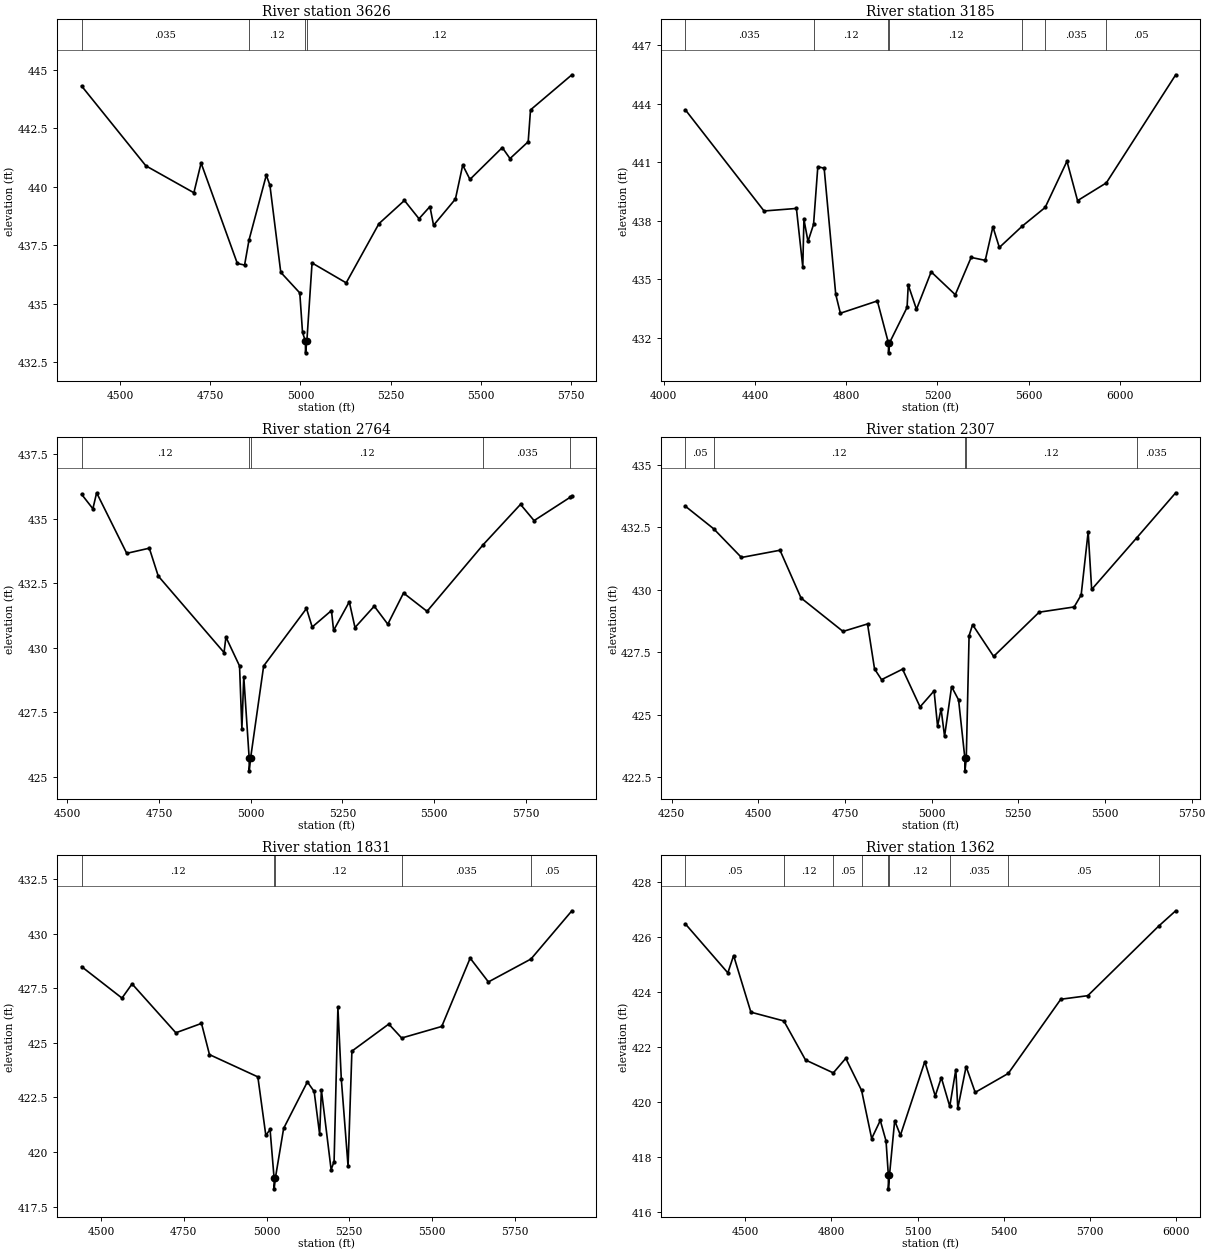
Type RM Length L Ch R = 1,3626,441,441,441
BEGIN DESCRIPTION:
StreamM012 5.0
END DESCRIPTION:
XS GIS Cut Line= 3
      2504325.00     13846124.99      2504275.00     13845525.00
      2503525.01     13845425.00
#Sta/Elev= 30
  4393.6  444.31  4571.7  440.90  4704.7  439.75  4724.7  441.02  4825.1  436.73
  4845.2  436.66  4857.5  437.73  4905.4  440.50  4915.4  440.07  4945.5  436.35
  4998.2  435.47  5005.8  433.78  5013.8  433.41  5014.1  432.91  5017.8  433.41
  5032.2  436.75  5126.8  435.90  5217.6  438.43  5288.2  439.42  5328.6  438.64
  5358.9  439.16  5368.9  438.36  5429.5  439.48  5449.7  440.93  5469.8  440.32
  5559.4  441.68  5580.8  441.21  5631.2  441.93  5637.6  443.29  5752.3  444.79
#Mann=4,-1,0
  4393.6   0.035       0  4857.5    0.12       0  5013.8    0.05       0
  5017.8    0.12       0
Bank Sta=5013.8,5017.8
Exp/Cntr=0.3,0.1

Type RM Length L Ch R = 1,3185,421,421,421
BEGIN DESCRIPTION:
StreamM012 4.0
END DESCRIPTION:
XS GIS Cut Line= 3
      2504425.01     13846124.97      2504575.00     13845225.00
      2503375.01     13844925.00
#Sta/Elev= 30
  4095.0  443.69  4439.7  438.51  4581.6  438.64  4609.5  435.64  4614.5  438.08
  4632.3  436.95  4656.7  437.82  4675.4  440.78  4703.2  440.70  4753.9  434.24
  4774.2  433.27  4936.4  433.90  4985.1  431.74  4985.4  431.24  4989.1  431.74
  5066.7  433.57  5071.8  434.72  5107.9  433.47  5172.3  435.39  5278.0  434.22
  5347.5  436.13  5409.4  435.98  5442.9  437.70  5471.2  436.64  5571.2  437.73
  5672.0  438.69  5767.6  441.06  5814.0  439.04  5940.2  439.95  6244.3  445.49
#Mann=7,-1,0
  4095.0   0.035       0  4656.7    0.12       0  4985.1    0.05       0
  4989.1    0.12       0  5571.2    0.07       0  5672.0   0.035       0
  5940.2    0.05       0
Bank Sta=4985.1,4989.1
Exp/Cntr=0.3,0.1

Type RM Length L Ch R = 1,2764,457,457,457
BEGIN DESCRIPTION:
StreamM012 3.0
END DESCRIPTION:
XS GIS Cut Line= 3
      2504825.01     13845674.97      2504925.00     13845225.00
      2504174.99     13844774.99
#Sta/Elev= 30
  4539.5  435.95  4570.2  435.39  4580.4  436.01  4662.4  433.66  4723.9  433.86
  4748.2  432.78  4927.5  429.81  4932.6  430.41  4969.7  429.29  4976.1  426.84
  4981.2  428.88  4995.9  425.72  4996.1  425.22  4999.9  425.72  5035.4  429.29
  5152.1  431.52  5167.6  430.80  5220.1  431.44  5225.9  430.67  5268.7  431.78
  5284.2  430.78  5336.7  431.61  5373.6  430.91  5416.4  432.12  5480.5  431.41
  5633.7  434.00  5735.1  435.56  5772.1  434.93  5870.9  435.84  5875.1  435.89
#Mann=5,-1,0
  4539.5    0.12       0  4995.9    0.05       0  4999.9    0.12       0
  5633.7   0.035       0  5870.9    0.05       0
Bank Sta=4995.9,4999.9
Exp/Cntr=0.3,0.1

Type RM Length L Ch R = 1,2307,476,476,476
BEGIN DESCRIPTION:
StreamM012 2.0
END DESCRIPTION:
XS GIS Cut Line= 3
      2505225.00     13845625.02      2505125.00     13844925.00
      2504425.04     13844825.01
#Sta/Elev= 30
  4289.8  433.34  4371.2  432.44  4451.4  431.29  4562.6  431.58  4623.2  429.67
  4744.4  428.33  4815.1  428.63  4835.3  426.83  4855.5  426.40  4916.1  426.82
  4966.6  425.31  5007.0  425.95  5017.1  424.54  5027.2  425.23  5037.3  424.13
  5057.5  426.12  5077.7  425.59  5095.9  423.25  5096.2  422.75  5099.9  423.25
  5108.0  428.16  5118.1  428.60  5178.8  427.33  5310.1  429.10  5411.1  429.31
  5431.3  429.79  5451.5  432.32  5461.6  430.01  5591.1  432.07  5704.0  433.88
#Mann=5,-1,0
  4289.8    0.05       0  4371.2    0.12       0  5095.9    0.05       0
  5099.9    0.12       0  5591.1   0.035       0
Bank Sta=5095.9,5099.9
Exp/Cntr=0.3,0.1

Type RM Length L Ch R = 1,1831,469,469,469
BEGIN DESCRIPTION:
StreamM012 1.0
END DESCRIPTION:
XS GIS Cut Line= 3
      2505375.01     13845274.97      2505475.00     13844725.00
      2504575.04     13844525.01
#Sta/Elev= 30
  4441.5  428.49  4563.4  427.05  4593.9  427.70  4726.1  425.46  4803.6  425.89
  4827.7  424.46  4973.8  423.44  4997.9  420.76  5010.7  421.03  5022.8  418.81
  5023.1  418.31  5026.8  418.81  5051.7  421.08  5123.4  423.21  5143.9  422.77
  5160.5  420.80  5165.7  422.84  5195.1  419.19  5204.1  419.56  5215.6  426.62
  5225.9  423.34  5246.3  419.35  5257.9  424.62  5369.3  425.86  5408.2  425.22
  5529.3  425.75  5615.1  428.88  5670.2  427.79  5798.8  428.84  5922.4  431.05
#Mann=5,-1,0
  4441.5    0.12       0  5022.8    0.05       0  5026.8    0.12       0
  5408.2   0.035       0  5798.8    0.05       0
Bank Sta=5022.8,5026.8
Exp/Cntr=0.3,0.1

Type RM Length L Ch R = 1,1362,424,424,424
BEGIN DESCRIPTION:
H21148
END DESCRIPTION:
XS GIS Cut Line= 4
      2505673.87     13845232.60      2505691.23     13844434.03
      2505576.64     13844256.95      2504918.47     13844031.78
#Sta/Elev= 30
  4292.7  426.48  4440.3  424.70  4460.3  425.33  4520.4  423.27  4635.1  422.95
  4710.4  421.53  4807.1  421.06  4850.4  421.59  4905.5  420.42  4940.5  418.67
  4970.5  419.33  4990.5  418.58  4998.5  417.34  4998.7  416.84  5002.5  417.34
  5020.5  419.32  5040.5  418.79  5125.3  421.47  5161.6  420.22  5182.7  420.89
  5212.1  419.84  5233.2  421.18  5240.1  419.77  5269.0  421.29  5300.6  420.35
  5415.6  421.04  5598.3  423.74  5692.2  423.87  5938.5  426.40  5998.0  426.96
#Mann=9,-1,0
  4292.7    0.05       0  4635.1    0.12       0  4807.1    0.05       0
  4905.5    0.12       0  4998.5    0.05       0  5002.5    0.12       0
  5212.1   0.035       0  5415.6    0.05       0  5938.5   0.035       0
Bank Sta=4998.5,5002.5
Exp/Cntr=0.3,0.1

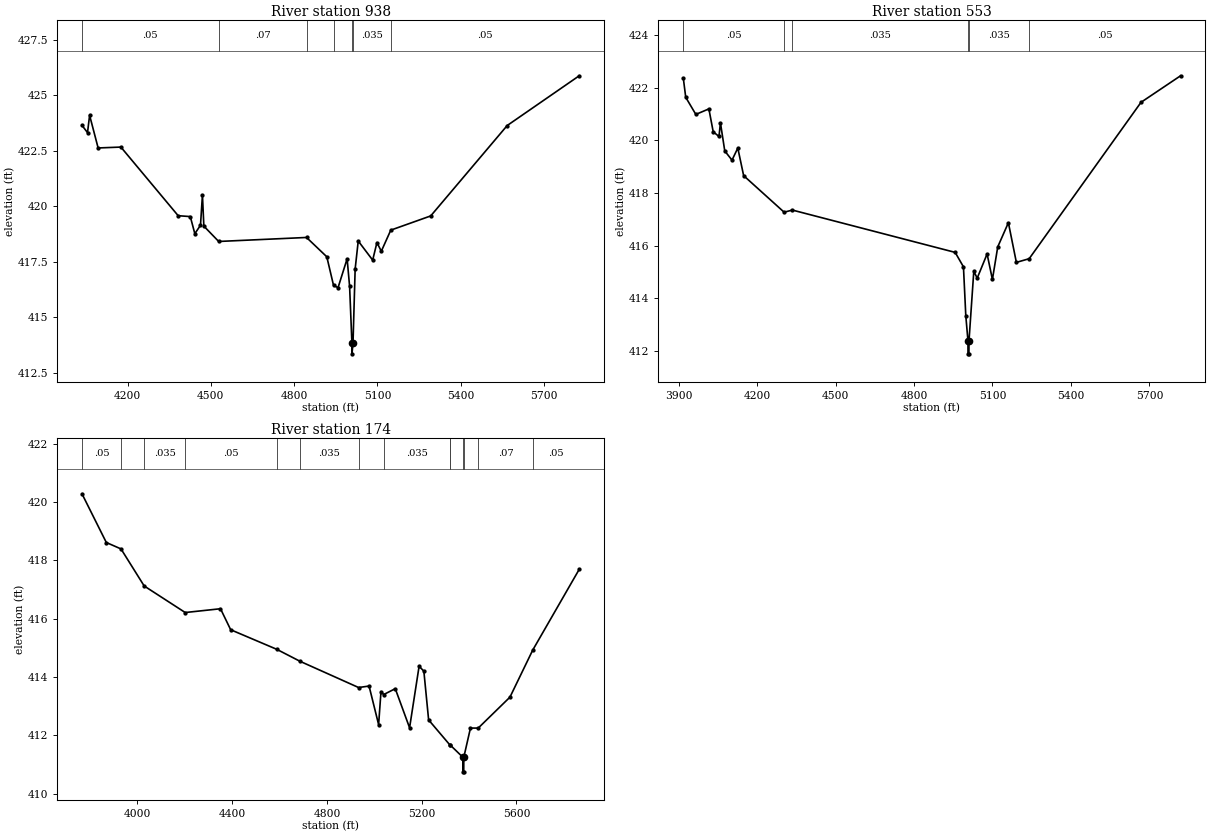
Type RM Length L Ch R = 1,938,385,385,385
BEGIN DESCRIPTION:
H21147
END DESCRIPTION:
XS GIS Cut Line= 4
      2505816.22     13845211.83      2505958.59     13844565.98
      2505819.70     13844072.92      2505291.94     13843753.49
#Sta/Elev= 30
  4035.9  423.65  4055.9  423.32  4063.4  424.10  4094.1  422.63  4176.0  422.67
  4382.3  419.58  4426.0  419.54  4442.3  418.77  4462.7  419.15  4469.7  420.51
  4474.8  419.11  4528.2  418.42  4844.5  418.60  4917.5  417.73  4941.8  416.44
  4958.0  416.34  4990.7  417.64  4999.6  416.40  5007.9  413.86  5008.2  413.36
  5011.9  413.86  5019.6  417.18  5030.7  418.44  5082.7  417.58  5098.0  418.37
  5113.8  417.98  5147.9  418.93  5291.7  419.57  5567.1  423.64  5826.4  425.88
#Mann=7,-1,0
  4035.9    0.05       0  4528.2    0.07       0  4844.5    0.12       0
  4941.8   0.035       0  5007.9   0.035       0  5011.9   0.035       0
  5147.9    0.05       0
Bank Sta=5007.9,5011.9
Exp/Cntr=0.3,0.1

Type RM Length L Ch R = 1,553,379,379,379
BEGIN DESCRIPTION:
H21146
END DESCRIPTION:
XS GIS Cut Line= 4
      2505906.48     13845159.77      2506278.03     13844444.45
      2506187.75     13843961.81      2505736.91     13843559.52
#Sta/Elev= 30
  3917.8  422.37  3927.1  421.64  3965.7  420.99  4015.6  421.20  4032.1  420.33
  4054.2  420.15  4059.8  420.67  4076.3  419.60  4104.0  419.25  4126.2  419.71
  4148.5  418.66  4303.2  417.27  4335.0  417.35  4957.3  415.74  4989.0  415.19
  4998.0  413.32  5006.2  412.38  5006.4  411.88  5009.9  411.88  5010.2  412.38
  5028.5  415.02  5041.6  414.76  5079.4  415.68  5099.7  414.71  5120.1  415.95
  5160.8  416.87  5191.3  415.36  5240.3  415.50  5667.9  421.45  5819.1  422.46
#Mann=6,-1,0
  3917.8    0.05       0  4303.2    0.07       0  4335.0   0.035       0
  5006.2   0.035       0  5010.2   0.035       0  5240.3    0.05       0
Bank Sta=5006.2,5010.2
Exp/Cntr=0.3,0.1

Type RM Length L Ch R = 1,174,0,0,0
BEGIN DESCRIPTION:
H21145
END DESCRIPTION:
XS GIS Cut Line= 4
      2506016.41     13845155.39      2506578.56     13844185.75
      2506534.37     13843761.09      2506060.10     13843479.95
#Sta/Elev= 30
  3766.1  420.28  3868.9  418.61  3930.9  418.39  4028.8  417.12  4202.0  416.21
  4350.9  416.34  4393.9  415.62  4588.2  414.95  4686.3  414.54  4933.8  413.64
  4978.1  413.69  5018.4  412.37  5028.4  413.50  5040.0  413.40  5088.7  413.60
  5149.1  412.26  5189.3  414.37  5209.4  414.20  5229.5  412.53  5319.4  411.67
  5320.5  411.67  5374.0  411.25  5374.2  410.75  5377.7  410.75  5378.0  411.25
  5406.1  412.25  5438.9  412.25  5572.8  413.31  5668.8  414.92  5865.2  417.69
#Mann=14,-1,0
  3766.1    0.05       0  3930.9    0.07       0  4028.8   0.035       0
  4202.0    0.05       0  4588.2    0.12       0  4686.3   0.035       0
  4933.8     0.1       0  5040.0   0.035       0  5319.4    0.07       0
  5320.5     0.1       0  5374.0    0.05       0  5378.0     0.1       0
  5438.9    0.07       0  5668.8    0.05       0
Bank Sta=5374,5378
Exp/Cntr=0.3,0.1

Chan Stop Cuts=-1