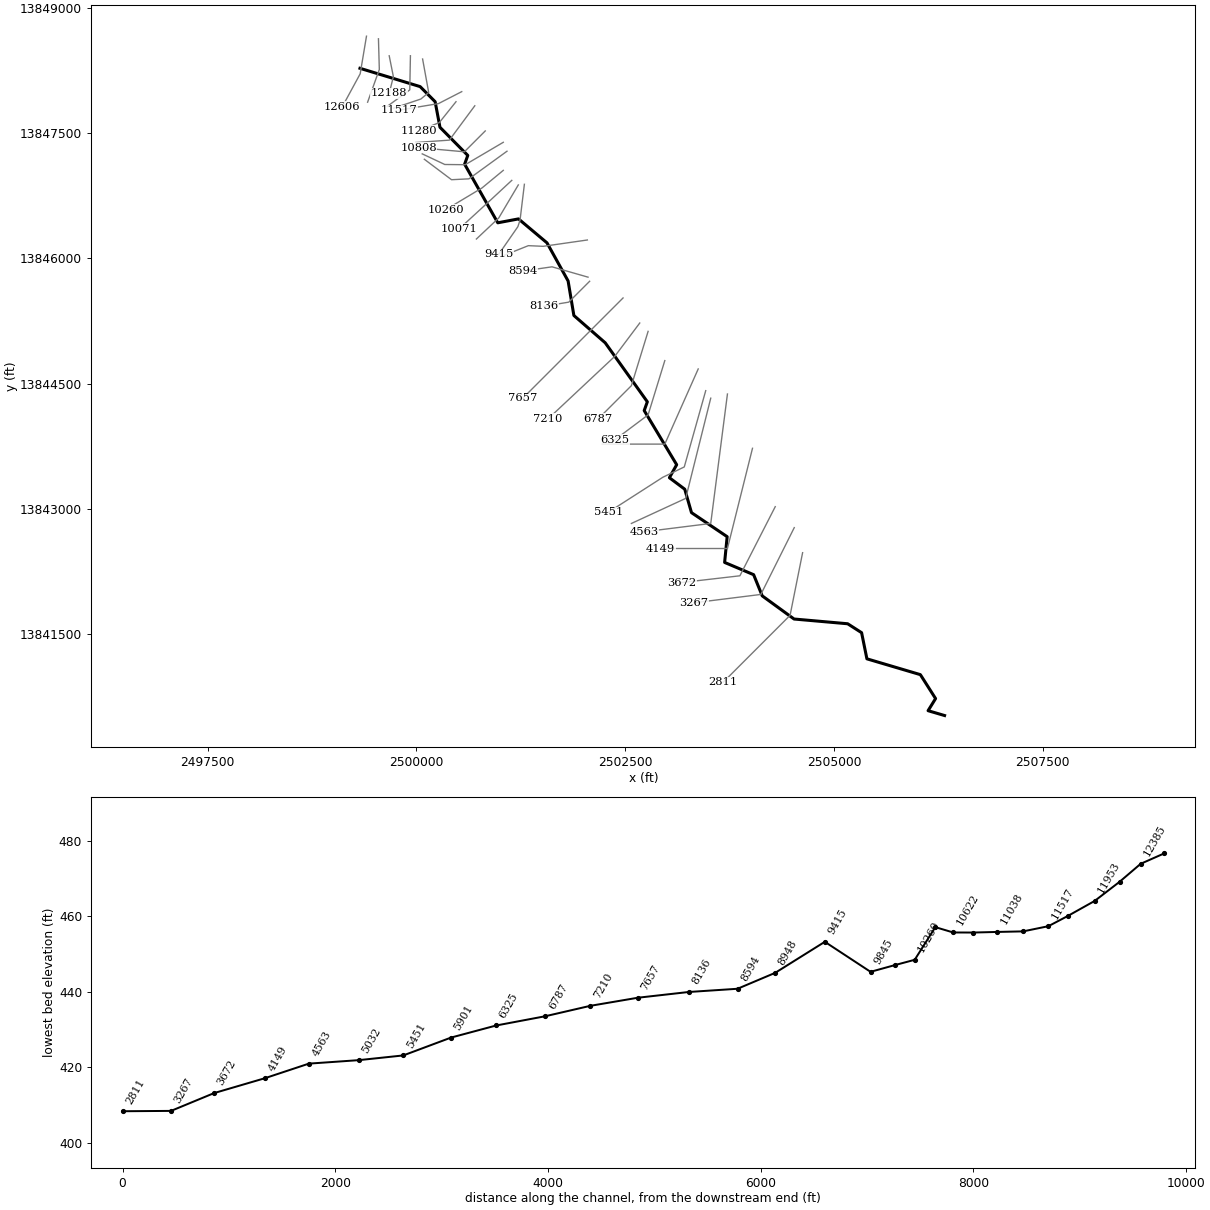
--- StreamM013.prj (project) ---

Proj Title=StreamM013 Base Level Engineering
Current Plan=p01
Default Exp/Contr=0.3,0.1
English Units
Geom File=g01
Flow File=f01
Plan File=p01
BEGIN DESCRIPTION:
StreamM013
END DESCRIPTION:

--- StreamM013.p01 (plan) ---

Plan Title=Multiple Run
Short Identifier=Multiple
Geom File=g01
Flow File=f01
Subcritical Flow
K Sum by GR= 0
Std Step Tol= 0.01
Critical Tol= 0.01
Num of Std Step Trials= 20
Max Error Tol= 0.3
Flow Tol Ratio= 0.001
Split Flow NTrial= 30
Split Flow Tol= 0.02
Split Flow Ratio= 0.02
Log Output Level= 0
Friction Slope Method= 1
Unsteady Friction Slope Method= 2
Unsteady Bridges Friction Slope Method= 1
Parabolic Critical Depth
Global Vel Dist=  1 , 1 , 1
Global Log Level= 0
CheckData=True
Encroach Param= -1, 0, 0, 0
BEGIN DESCRIPTION:
Multiple Run
END DESCRIPTION:

--- StreamM013.f01 (steady flow) ---

Flow Title=Multiple
Number of Profiles=7
Profile Names=10-year,25-year,50-year,1pct_min,100-year,1pct_plu,500-year
River Rch & RM= StreamM013,Reach-1,12606
     292     447     581     368     734    1464    1154
River Rch & RM= StreamM013,Reach-1,11517
     517     823    1097     710    1416    2825    2332
River Rch & RM= StreamM013,Reach-1,9845
     670    1081    1454     949    1893    3777    3172
River Rch & RM= StreamM013,Reach-1,7657
     968    1584    2149    1411    2815    5617    4781
Boundary for River Rch & Prof#=StreamM013,Reach-1,1
Up Type=0
Dn Type=3
Dn Slope=0.005
Boundary for River Rch & Prof#=StreamM013,Reach-1,2
Up Type=0
Dn Type=3
Dn Slope=0.005
Boundary for River Rch & Prof#=StreamM013,Reach-1,3
Up Type=0
Dn Type=3
Dn Slope=0.005
Boundary for River Rch & Prof#=StreamM013,Reach-1,4
Up Type=0
Dn Type=3
Dn Slope=0.005
Boundary for River Rch & Prof#=StreamM013,Reach-1,5
Up Type=0
Dn Type=3
Dn Slope=0.005
Boundary for River Rch & Prof#=StreamM013,Reach-1,6
Up Type=0
Dn Type=3
Dn Slope=0.005
Boundary for River Rch & Prof#=StreamM013,Reach-1,7
Up Type=0
Dn Type=3
Dn Slope=0.005

--- StreamM013.g01 (geometry) ---

Geom Title=Existing Conditions

River Reach=StreamM013,Reach-1
Reach XY= 30
      2499325.00     13848275.00      2500045.55     13848055.55
      2500225.00     13847875.00      2500282.82     13847568.81
      2500615.85     13847231.73      2500578.16     13847126.65
      2500975.00     13846425.00      2501223.27     13846471.69
      2501564.48     13846184.78      2501817.17     13845728.40
      2501886.24     13845315.00      2502261.37     13844988.21
      2502765.85     13844281.73      2502728.37     13844176.74
      2503117.12     13843528.22      2503029.96     13843372.46
      2503213.77     13843235.02      2503294.47     13842954.46
      2503721.60     13842666.56      2503691.22     13842358.32
      2504038.63     13842211.56      2504141.49     13841957.95
      2504522.62     13841680.70      2505164.56     13841623.94
      2505331.38     13841516.98      2505394.91     13841204.07
      2506035.10     13841014.61      2506217.16     13840728.23
      2506127.43     13840583.11      2506325.00     13840525.00

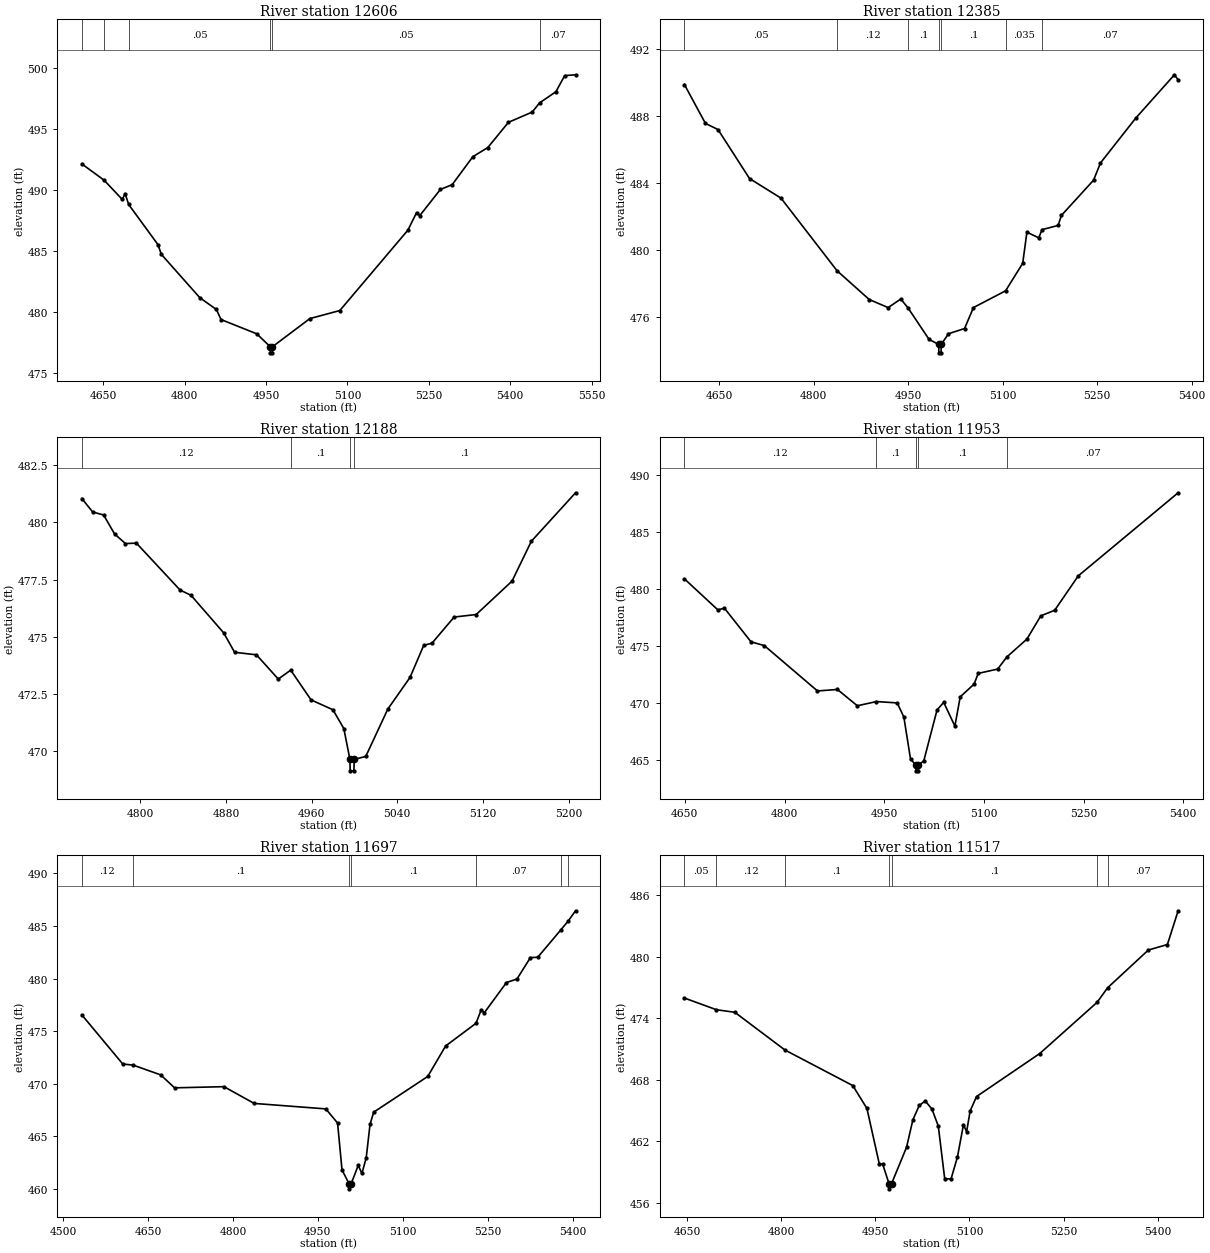
Type RM Length L Ch R = 1,12606,221,221,221
BEGIN DESCRIPTION:
H21165
END DESCRIPTION:
XS GIS Cut Line= 3
      2499403.04     13848659.62      2499327.52     13848209.10
      2499111.37     13847810.66
#Sta/Elev= 30
  4610.4  492.12  4651.6  490.78  4685.1  489.20  4690.2  489.69  4696.8  488.79
  4750.9  485.49  4757.0  484.70  4828.0  481.14  4858.4  480.18  4867.1  479.35
  4932.9  478.18  4957.8  477.12  4958.1  476.62  4961.6  476.62  4961.8  477.12
  5030.8  479.43  5086.0  480.09  5211.4  486.68  5227.6  488.13  5233.3  487.87
  5271.3  490.02  5293.2  490.42  5331.2  492.71  5358.8  493.46  5396.8  495.53
  5440.6  496.37  5454.1  497.12  5484.3  498.04  5500.5  499.36  5520.5  499.43
#Mann=6,-1,0
  4610.4    0.05       0  4651.6    0.07       0  4696.8    0.05       0
  4957.8    0.05       0  4961.8    0.05       0  5454.1    0.07       0
Bank Sta=4957.8,4961.8
Exp/Cntr=0.3,0.1

Type RM Length L Ch R = 1,12385,197,197,197
BEGIN DESCRIPTION:
H21164
END DESCRIPTION:
XS GIS Cut Line= 3
      2499546.27     13848628.36      2499556.69     13848261.18
      2499416.41     13847868.93
#Sta/Elev= 30
  4594.6  489.88  4628.0  487.56  4648.0  487.19  4698.0  484.27  4748.0  483.10
  4836.9  478.77  4888.1  477.05  4918.1  476.57  4938.1  477.08  4949.5  476.56
  4983.1  474.67  4998.4  474.37  4998.6  473.87  5002.1  473.87  5002.4  474.37
  5013.9  475.01  5039.4  475.32  5053.5  476.57  5104.5  477.57  5131.7  479.21
  5138.4  481.07  5157.2  480.73  5162.4  481.22  5187.9  481.47  5193.2  482.07
  5244.2  484.17  5255.2  485.20  5311.1  487.87  5372.6  490.46  5378.5  490.16
#Mann=7,-1,0
  4594.6    0.05       0  4836.9    0.12       0  4949.5     0.1       0
  4998.4    0.05       0  5002.4     0.1       0  5104.5   0.035       0
  5162.4    0.07       0
Bank Sta=4998.4,5002.4
Exp/Cntr=0.3,0.1

Type RM Length L Ch R = 1,12188,235,235,235
BEGIN DESCRIPTION:
StreamM013 22.0
END DESCRIPTION:
XS GIS Cut Line= 3
      2499675.01     13848424.97      2499725.00     13848175.00
      2499674.99     13847974.98
#Sta/Elev= 30
  4745.4  481.04  4755.6  480.45  4765.8  480.32  4776.0  479.49  4786.2  479.07
  4796.4  479.09  4837.2  477.04  4847.4  476.81  4877.9  475.17  4888.1  474.32
  4908.5  474.21  4928.9  473.15  4940.5  473.54  4959.5  472.24  4979.9  471.81
  4990.1  470.99  4995.8  469.64  4996.0  469.14  4999.5  469.14  4999.8  469.64
  5010.6  469.77  5031.2  471.84  5051.9  473.22  5064.7  474.62  5072.5  474.72
  5093.1  475.86  5113.7  475.97  5147.2  477.43  5165.2  479.17  5206.5  481.29
#Mann=4,-1,0
  4745.4    0.12       0  4940.5     0.1       0  4995.8    0.05       0
  4999.8     0.1       0
Bank Sta=4995.8,4999.8
Exp/Cntr=0.3,0.1

Type RM Length L Ch R = 1,11953,256,256,256
BEGIN DESCRIPTION:
H21163
END DESCRIPTION:
XS GIS Cut Line= 3
      2499929.09     13848425.26      2499921.27     13848016.39
      2499651.47     13847819.23
#Sta/Elev= 30
  4649.3  480.91  4699.6  478.19  4709.6  478.33  4749.6  475.38  4769.6  475.05
  4849.6  471.07  4879.6  471.20  4909.6  469.77  4938.4  470.14  4969.6  470.02
  4979.6  468.78  4989.6  465.11  4997.6  464.56  4997.9  464.06  5001.4  464.06
  5001.6  464.56  5009.6  464.94  5029.6  469.41  5039.6  470.07  5056.4  467.98
  5064.4  470.55  5085.3  471.67  5091.5  472.61  5120.8  472.99  5134.7  474.06
  5164.8  475.62  5185.7  477.66  5206.6  478.15  5242.1  481.17  5392.4  488.46
#Mann=5,-1,0
  4649.3    0.12       0  4938.4     0.1       0  4997.6    0.05       0
  5001.6     0.1       0  5134.7    0.07       0
Bank Sta=4997.6,5001.6
Exp/Cntr=0.3,0.1

Type RM Length L Ch R = 1,11697,180,180,180
BEGIN DESCRIPTION:
H21162
END DESCRIPTION:
XS GIS Cut Line= 4
      2500074.91     13848386.22      2500147.84     13847985.14
      2500054.09     13847907.02      2499729.32     13847797.89
#Sta/Elev= 30
  4533.0  476.55  4605.4  471.88  4623.5  471.78  4672.4  470.85  4696.9  469.62
  4784.2  469.73  4837.5  468.14  4964.1  467.62  4984.9  466.28  4992.7  461.83
  5005.0  460.53  5005.3  460.03  5009.0  460.53  5021.4  462.26  5027.9  461.49
  5035.5  462.98  5042.2  466.14  5048.7  467.31  5144.2  470.70  5175.7  473.59
  5229.5  475.75  5238.7  477.04  5244.0  476.74  5283.3  479.62  5301.8  479.95
  5325.5  481.98  5338.6  482.02  5379.7  484.64  5391.9  485.43  5405.3  486.43
#Mann=7,-1,0
  4533.0    0.12       0  4623.5     0.1       0  5005.0    0.05       0
  5009.0     0.1       0  5229.5    0.07       0  5379.7    0.12       0
  5391.9    0.07       0
Bank Sta=5005,5009
Exp/Cntr=0.3,0.1

Type RM Length L Ch R = 1,11517,237,237,237
BEGIN DESCRIPTION:
H21161
END DESCRIPTION:
XS GIS Cut Line= 3
      2500543.65     13847995.55      2500265.02     13847852.33
      2499798.14     13847774.52
#Sta/Elev= 30
  4645.8  475.98  4696.8  474.84  4726.1  474.59  4806.0  470.91  4914.1  467.44
  4936.6  465.21  4956.3  459.80  4961.6  459.80  4971.8  457.87  4972.0  457.37
  4975.8  457.87  4999.7  461.42  5009.8  464.10  5019.9  465.50  5029.5  465.94
  5040.2  465.15  5050.3  463.49  5060.5  458.36  5070.6  458.33  5080.8  460.48
  5090.4  463.63  5095.4  462.94  5101.0  464.96  5111.2  466.37  5212.0  470.57
  5303.3  475.56  5319.9  476.97  5384.9  480.66  5415.3  481.20  5432.4  484.49
#Mann=7,-1,0
  4645.8    0.05       0  4696.8    0.12       0  4806.0     0.1       0
  4971.8    0.05       0  4975.8     0.1       0  5303.3    0.12       0
  5319.9    0.07       0
Bank Sta=4971.8,4975.8
Exp/Cntr=0.3,0.1

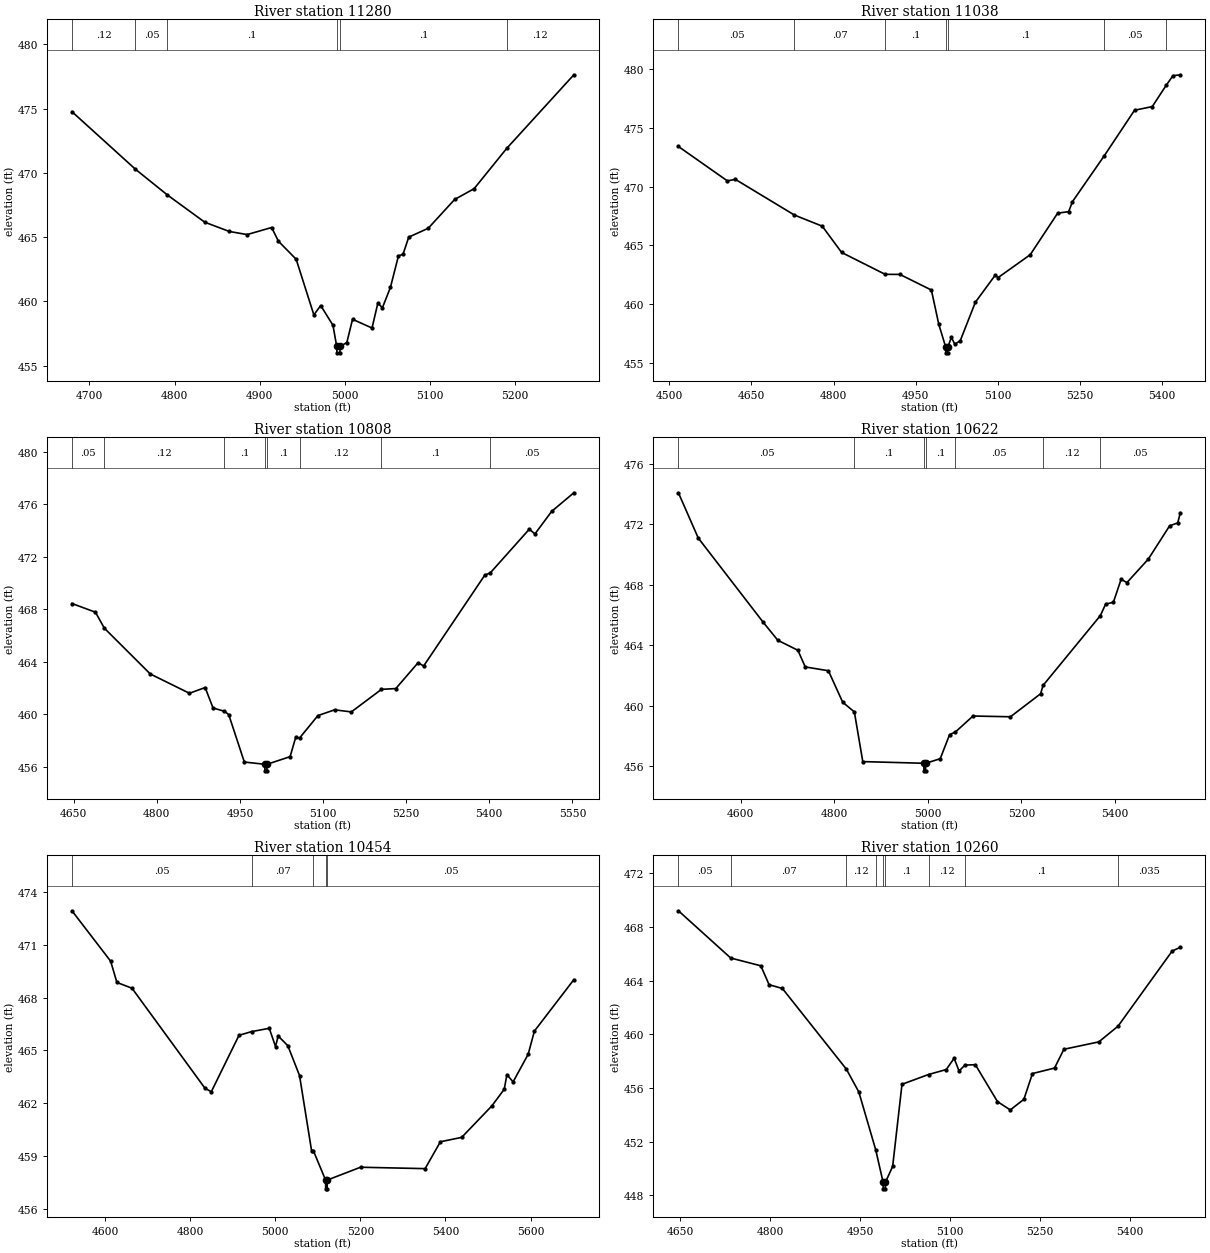
Type RM Length L Ch R = 1,11280,242,242,242
BEGIN DESCRIPTION:
StreamM013 20.0
END DESCRIPTION:
XS GIS Cut Line= 3
      2500474.98     13847874.97      2500275.00     13847625.00
      2500024.98     13847524.99
#Sta/Elev= 30
  4679.5  474.76  4754.1  470.28  4791.6  468.28  4835.5  466.16  4864.4  465.44
  4885.2  465.20  4914.0  465.75  4922.0  464.68  4942.8  463.28  4963.6  458.95
  4971.6  459.68  4986.0  458.15  4990.4  456.50  4990.7  456.00  4994.2  456.00
  4994.4  456.50  5002.3  456.80  5009.0  458.61  5031.9  457.93  5038.7  459.86
  5044.1  459.51  5053.5  461.09  5062.9  463.54  5068.3  463.67  5075.0  465.00
  5097.9  465.69  5128.9  467.93  5151.8  468.77  5190.0  471.90  5268.9  477.63
#Mann=6,-1,0
  4679.5    0.12       0  4754.1    0.05       0  4791.6     0.1       0
  4990.4    0.05       0  4994.4     0.1       0  5190.0    0.12       0
Bank Sta=4990.4,4994.4
Exp/Cntr=0.3,0.1

Type RM Length L Ch R = 1,11038,230,230,230
BEGIN DESCRIPTION:
H21166
END DESCRIPTION:
XS GIS Cut Line= 3
      2500699.89     13847826.25      2500395.23     13847414.83
      2499991.59     13847386.18
#Sta/Elev= 30
  4516.6  473.43  4606.0  470.50  4620.6  470.63  4728.4  467.59  4779.3  466.64
  4814.7  464.40  4894.1  462.54  4921.1  462.53  4978.6  461.20  4992.1  458.28
  5004.7  456.35  5004.9  455.85  5008.4  455.85  5008.7  456.35  5015.1  457.17
  5021.3  456.59  5031.2  456.87  5058.9  460.16  5095.4  462.48  5100.4  462.26
  5159.1  464.21  5209.2  467.75  5229.3  467.88  5236.2  468.73  5294.6  472.66
  5349.6  476.52  5382.0  476.83  5407.3  478.64  5419.8  479.46  5433.2  479.54
#Mann=7,-1,0
  4516.6    0.05       0  4728.4    0.07       0  4894.1     0.1       0
  5004.7    0.05       0  5008.7     0.1       0  5294.6    0.05       0
  5407.3    0.07       0
Bank Sta=5004.7,5008.7
Exp/Cntr=0.3,0.1

Type RM Length L Ch R = 1,10808,186,186,186
BEGIN DESCRIPTION:
StreamM013 19.0
END DESCRIPTION:
XS GIS Cut Line= 3
      2500825.01     13847525.01      2500575.00     13847275.00
      2500025.03     13847325.00
#Sta/Elev= 30
  4646.8  468.44  4689.2  467.78  4705.3  466.56  4788.2  463.07  4858.9  461.60
  4887.2  462.04  4901.4  460.48  4921.9  460.23  4929.7  459.98  4957.9  456.36
  4994.8  456.19  4995.1  455.69  4998.6  455.69  4998.8  456.19  5040.5  456.77
  5050.6  458.24  5057.8  458.20  5090.7  459.90  5120.9  460.34  5151.0  460.18
  5205.4  461.90  5231.3  461.96  5271.5  463.93  5281.5  463.68  5392.0  470.61
  5401.7  470.77  5472.3  474.11  5482.3  473.74  5512.5  475.46  5552.6  476.88
#Mann=8,-1,0
  4646.8    0.05       0  4705.3    0.12       0  4921.9     0.1       0
  4994.8    0.05       0  4998.8     0.1       0  5057.8    0.12       0
  5205.4     0.1       0  5401.7    0.05       0
Bank Sta=4994.8,4998.8
Exp/Cntr=0.3,0.1

Type RM Length L Ch R = 1,10622,168,168,168
BEGIN DESCRIPTION:
H21167
END DESCRIPTION:
XS GIS Cut Line= 4
      2501041.08     13847388.79      2500585.34     13847120.56
      2500340.54     13847123.16      2500070.63     13847250.33
#Sta/Elev= 30
  4467.3  474.07  4509.7  471.08  4648.4  465.52  4679.6  464.33  4722.5  463.67
  4738.2  462.57  4787.6  462.32  4818.2  460.24  4843.1  459.60  4861.1  456.32
  4991.4  456.21  4991.7  455.71  4995.2  455.71  4995.4  456.21  5026.5  456.51
  5046.5  458.10  5059.1  458.28  5096.5  459.33  5176.5  459.28  5240.9  460.80
  5246.1  461.35  5368.5  465.96  5379.8  466.72  5396.3  466.84  5412.9  468.36
  5425.3  468.14  5470.9  469.69  5516.5  471.89  5533.7  472.08  5539.3  472.75
#Mann=7,-1,0
  4467.3    0.05       0  4843.1     0.1       0  4991.4    0.05       0
  4995.4     0.1       0  5059.1    0.05       0  5246.1    0.12       0
  5368.5    0.05       0
Bank Sta=4991.4,4995.4
Exp/Cntr=0.3,0.1

Type RM Length L Ch R = 1,10454,194,194,194
BEGIN DESCRIPTION:
H21160
END DESCRIPTION:
XS GIS Cut Line= 4
      2501085.37     13847282.04      2500629.61     13846951.29
      2500421.27     13846940.87      2500095.77     13847185.65
#Sta/Elev= 30
  4522.6  472.95  4613.5  470.08  4628.2  468.87  4663.7  468.54  4835.3  462.84
  4850.0  462.65  4915.0  465.86  4944.4  466.07  4986.1  466.26  5000.8  465.22
  5007.0  465.82  5029.7  465.27  5057.2  463.57  5085.5  459.29  5089.7  459.29
  5118.4  457.62  5118.6  457.12  5122.1  457.12  5122.4  457.62  5200.5  458.35
  5352.2  458.27  5388.1  459.80  5438.1  460.05  5508.9  461.84  5538.1  462.79
  5544.3  463.62  5558.9  463.21  5594.3  464.78  5608.9  466.10  5701.6  469.03
#Mann=5,-1,0
  4522.6    0.05       0  4944.4    0.07       0  5089.7    0.05       0
  5118.4    0.05       0  5122.4    0.05       0
Bank Sta=5118.4,5122.4
Exp/Cntr=0.3,0.1

Type RM Length L Ch R = 1,10260,189,189,189
BEGIN DESCRIPTION:
StreamM013 18.0
END DESCRIPTION:
XS GIS Cut Line= 3
      2501041.04     13847052.83      2500785.86     13846841.91
      2500350.93     13846581.48
#Sta/Elev= 30
  4646.7  469.20  4734.0  465.68  4784.3  465.10  4798.1  463.69  4820.3  463.41
  4927.1  457.40  4947.9  455.70  4976.1  451.39  4988.4  448.98  4988.7  448.48
  4992.2  448.48  4992.4  448.98  5004.4  450.15  5020.0  456.27  5064.3  457.00
  5093.9  457.37  5107.0  458.21  5115.3  457.26  5125.1  457.70  5142.5  457.73
  5179.4  454.98  5200.8  454.36  5223.5  455.15  5237.8  457.07  5274.7  457.48
  5290.3  458.88  5348.6  459.43  5380.7  460.60  5471.1  466.20  5484.7  466.48
#Mann=9,-1,0
  4646.7    0.05       0  4734.0    0.07       0  4927.1    0.12       0
  4976.1     0.1       0  4988.4    0.05       0  4992.4     0.1       0
  5064.3    0.12       0  5125.1     0.1       0  5380.7   0.035       0
Bank Sta=4988.4,4992.4
Exp/Cntr=0.3,0.1

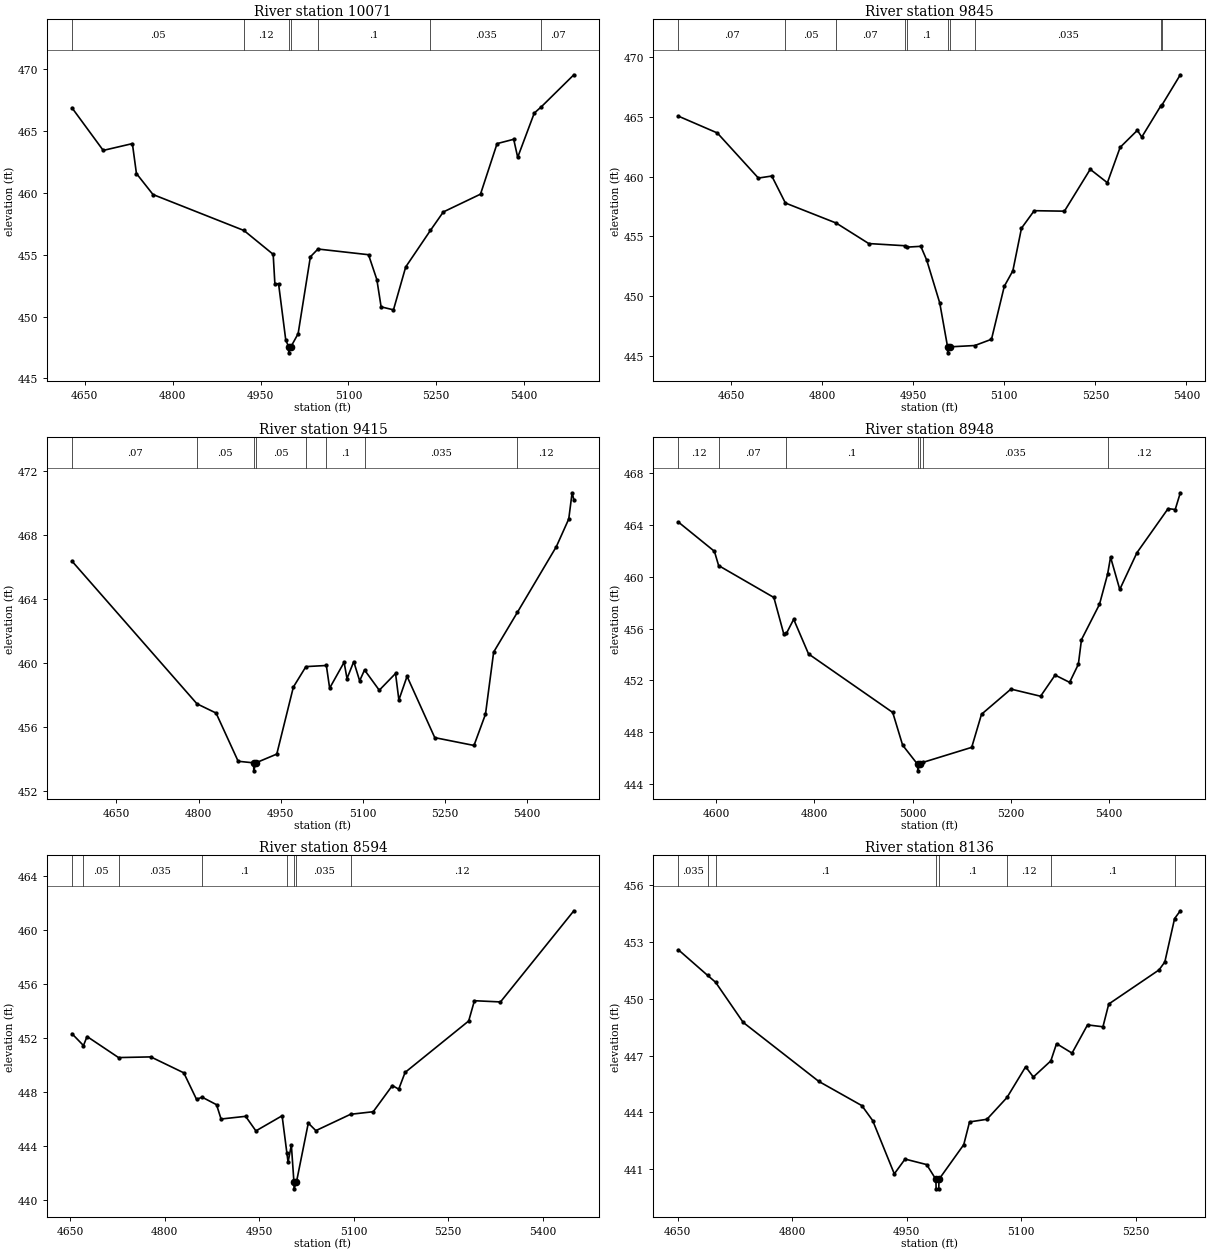
Type RM Length L Ch R = 1,10071,226,226,226
BEGIN DESCRIPTION:
StreamM013 17.0
END DESCRIPTION:
XS GIS Cut Line= 3
      2501142.64     13846933.07      2500887.42     13846696.08
      2500512.41     13846352.32
#Sta/Elev= 30
  4628.0  466.89  4681.4  463.44  4731.2  463.99  4738.1  461.57  4766.4  459.87
  4921.7  456.96  4971.6  455.03  4974.5  452.65  4980.8  452.65  4993.1  448.09
  4998.0  447.56  4998.2  447.06  5002.0  447.56  5014.2  448.61  5035.1  454.83
  5048.1  455.46  5134.4  455.00  5148.6  452.99  5155.9  450.78  5177.0  450.54
  5197.9  454.01  5240.0  456.96  5262.1  458.46  5325.6  459.90  5353.9  463.99
  5382.3  464.34  5389.1  462.88  5417.4  466.46  5429.7  466.98  5485.0  469.56
#Mann=7,-1,0
  4628.0    0.05       0  4921.7    0.12       0  4998.0    0.05       0
  5002.0    0.12       0  5048.1     0.1       0  5240.0   0.035       0
  5429.7    0.07       0
Bank Sta=4998,5002
Exp/Cntr=0.3,0.1

Type RM Length L Ch R = 1,9845,430,430,430
BEGIN DESCRIPTION:
StreamM013 16.0
END DESCRIPTION:
XS GIS Cut Line= 3
      2501220.76     13846878.39      2500986.38     13846482.54
      2500719.09     13846230.82
#Sta/Elev= 30
  4562.9  465.03  4627.0  463.63  4694.7  459.87  4716.8  460.04  4739.2  457.79
  4822.9  456.12  4876.6  454.41  4935.6  454.23  4939.1  454.11  4962.4  454.18
  4972.2  453.02  4993.6  449.46  5006.5  445.80  5006.7  445.30  5010.5  445.80
  5051.4  445.91  5078.9  446.43  5100.0  450.85  5114.1  452.14  5128.3  455.69
  5149.3  457.15  5199.1  457.11  5241.6  460.60  5269.9  459.48  5290.9  462.43
  5319.3  463.85  5326.6  463.29  5357.6  465.86  5359.5  465.93  5390.1  468.48
#Mann=10,-1,0
  4562.9    0.07       0  4739.2    0.05       0  4822.9    0.07       0
  4935.6    0.12       0  4939.1     0.1       0  5006.5    0.05       0
  5010.5     0.1       0  5051.4   0.035       0  5357.6    0.07       0
  5359.5    0.12       0
Bank Sta=5006.5,5010.5
Exp/Cntr=0.3,0.1

Type RM Length L Ch R = 1,9415,467,467,467
BEGIN DESCRIPTION:
H21159
END DESCRIPTION:
XS GIS Cut Line= 4
      2501293.67     13846886.23      2501241.59     13846456.50
      2501215.54     13846378.37      2500987.17     13846048.79
#Sta/Elev= 30
  4568.8  466.38  4797.0  457.44  4831.9  456.86  4872.2  453.84  4900.5  453.74
  4900.7  453.24  4904.5  453.74  4942.7  454.29  4973.0  458.49  4995.9  459.77
  5033.2  459.84  5039.2  458.42  5065.6  460.04  5070.9  459.02  5083.2  460.08
  5094.0  458.88  5102.9  459.56  5129.8  458.29  5159.5  459.34  5165.6  457.68
  5180.5  459.16  5231.1  455.32  5302.7  454.83  5323.7  456.79  5338.6  460.68
  5382.1  463.18  5453.1  467.29  5475.7  469.02  5481.8  470.66  5485.0  470.23
#Mann=8,-1,0
  4568.8    0.07       0  4797.0    0.05       0  4900.5    0.05       0
  4904.5    0.05       0  4995.9    0.07       0  5033.2     0.1       0
  5102.9   0.035       0  5382.1    0.12       0
Bank Sta=4900.5,4904.5
Exp/Cntr=0.3,0.1

Type RM Length L Ch R = 1,8948,354,354,354
BEGIN DESCRIPTION:
StreamM013 15.0
END DESCRIPTION:
XS GIS Cut Line= 4
      2502047.69     13846219.15      2501518.87     13846143.32
      2501341.26     13846151.30      2501051.87     13846035.54
#Sta/Elev= 30
  4522.5  464.20  4595.9  461.95  4604.5  460.85  4717.2  458.39  4737.4  455.58
  4742.9  455.63  4757.6  456.71  4787.9  454.04  4959.6  449.53  4979.8  447.01
  5010.4  445.53  5010.7  445.03  5014.4  445.53  5021.1  445.68  5120.7  446.84
  5140.7  449.39  5200.7  451.33  5261.2  450.78  5290.8  452.41  5320.4  451.85
  5338.2  453.24  5344.6  455.14  5381.3  457.86  5397.9  460.19  5403.9  461.50
  5422.7  459.01  5457.7  461.84  5521.3  465.24  5535.8  465.17  5546.2  466.46
#Mann=7,-1,0
  4522.5    0.12       0  4604.5    0.07       0  4742.9     0.1       0
  5010.4    0.05       0  5014.4     0.1       0  5021.1   0.035       0
  5397.9    0.12       0
Bank Sta=5010.4,5014.4
Exp/Cntr=0.3,0.1

Type RM Length L Ch R = 1,8594,458,458,458
BEGIN DESCRIPTION:
StreamM013 14.0
END DESCRIPTION:
XS GIS Cut Line= 3
      2502055.73     13845774.11      2501624.64     13845897.85
      2501279.72     13845848.01
#Sta/Elev= 30
  4652.7  452.31  4671.0  451.43  4676.7  452.10  4726.7  450.54  4777.9  450.59
  4830.3  449.41  4850.6  447.44  4859.3  447.61  4882.3  447.05  4889.5  445.99
  4928.5  446.19  4944.8  445.11  4986.4  446.23  4994.1  443.44  4995.9  442.79
  5001.1  444.07  5005.2  441.32  5005.4  440.82  5009.2  441.32  5028.0  445.69
  5040.0  445.13  5095.1  446.34  5131.1  446.53  5161.5  448.47  5171.6  448.20
  5181.7  449.44  5282.7  453.25  5291.8  454.75  5333.2  454.66  5449.7  461.41
#Mann=8,-1,0
  4652.7   0.035       0  4671.0    0.05       0  4726.7   0.035       0
  4859.3     0.1       0  4994.1   0.035       0  5005.2   0.035       0
  5009.2   0.035       0  5095.1    0.12       0
Bank Sta=5005.2,5009.2
Exp/Cntr=0.3,0.1

Type RM Length L Ch R = 1,8136,479,479,479
BEGIN DESCRIPTION:
StreamM013 13.0
END DESCRIPTION:
XS GIS Cut Line= 3
      2502075.02     13845725.02      2501825.00     13845475.00
      2501525.02     13845425.00
#Sta/Elev= 30
  4650.8  452.58  4689.1  451.23  4699.5  450.87  4735.7  448.75  4834.7  445.64
  4891.2  444.36  4905.4  443.57  4933.7  440.76  4947.8  441.54  4976.1  441.25
  4988.2  440.47  4988.5  439.97  4992.0  439.97  4992.2  440.47  5024.7  442.30
  5032.3  443.50  5055.1  443.64  5081.4  444.79  5105.8  446.41  5115.9  445.87
  5138.8  446.72  5146.3  447.63  5166.6  447.13  5186.9  448.62  5207.1  448.52
  5214.7  449.72  5280.6  451.52  5288.2  451.94  5301.0  454.23  5308.5  454.64
#Mann=8,-1,0
  4650.8   0.035       0  4689.1    0.05       0  4699.5     0.1       0
  4988.2    0.05       0  4992.2     0.1       0  5081.4    0.12       0
  5138.8     0.1       0  5301.0    0.12       0
Bank Sta=4988.2,4992.2
Exp/Cntr=0.3,0.1

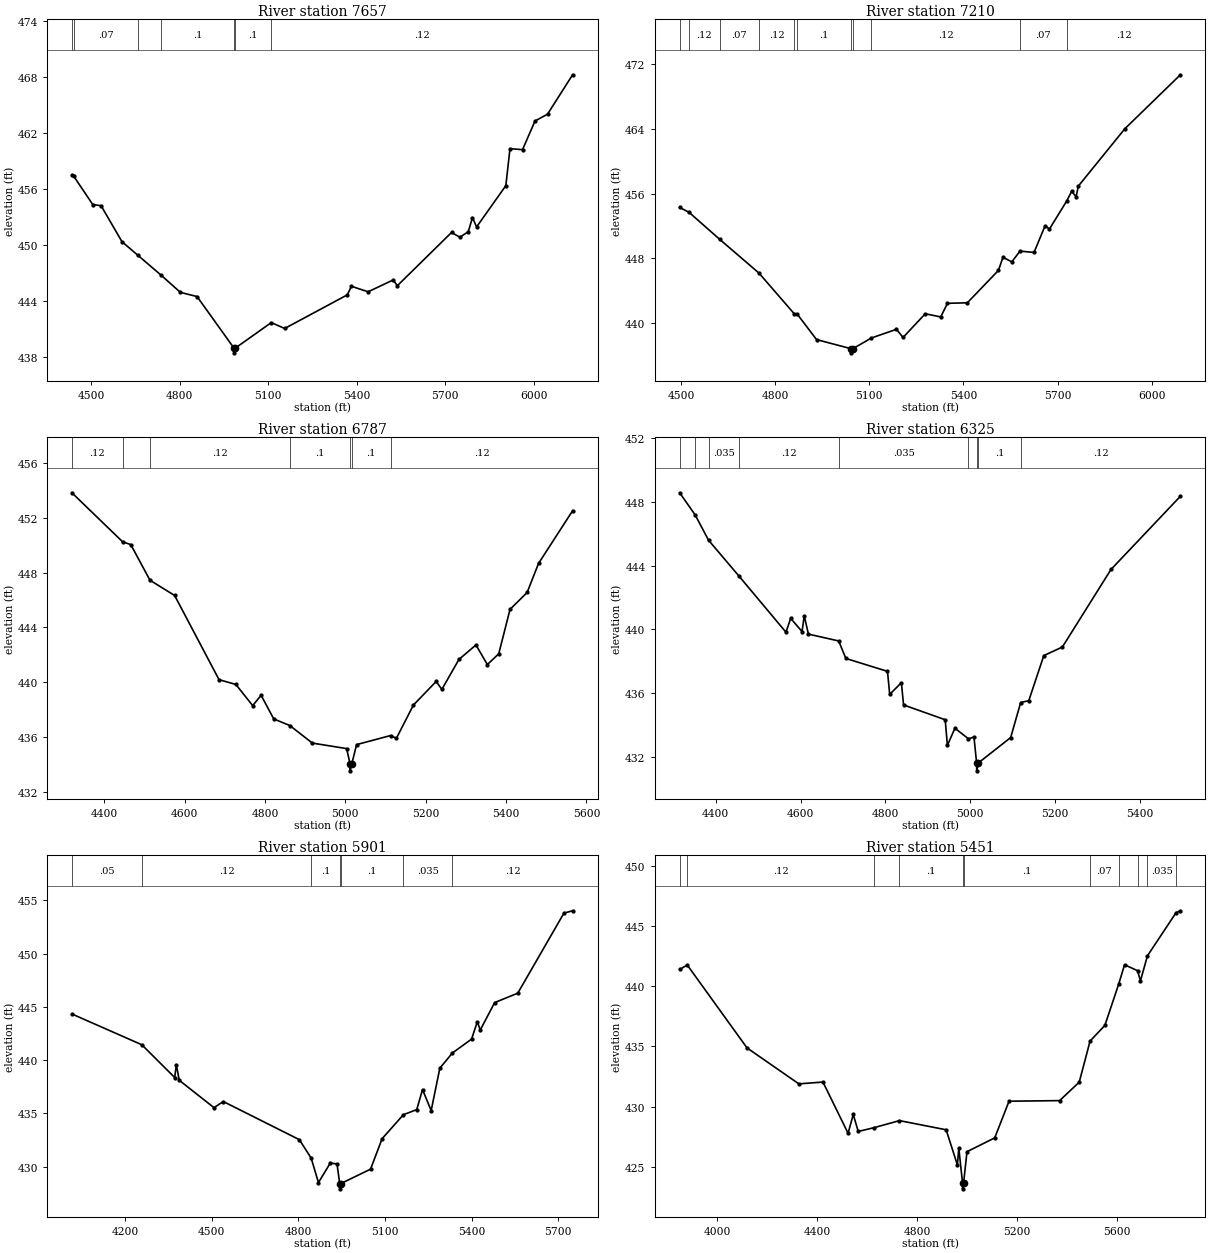
Type RM Length L Ch R = 1,7657,447,447,447
BEGIN DESCRIPTION:
StreamM013 12.0
END DESCRIPTION:
XS GIS Cut Line= 3
      2502475.01     13845525.01      2502075.00     13845125.00
      2501274.98     13844324.98
#Sta/Elev= 30
  4434.3  457.46  4440.8  457.36  4505.0  454.34  4533.3  454.21  4604.0  450.36
  4656.9  448.93  4737.8  446.74  4802.0  444.93  4858.6  444.48  4983.8  438.95
  4984.1  438.45  4987.9  438.95  5110.1  441.69  5155.6  441.06  5367.7  444.66
  5381.8  445.58  5438.4  444.99  5523.3  446.26  5537.4  445.64  5721.2  451.35
  5749.5  450.83  5777.8  451.43  5792.0  452.94  5806.1  451.94  5905.1  456.36
  5919.2  460.32  5961.7  460.22  6004.1  463.29  6046.5  464.02  6131.4  468.24
#Mann=7,-1,0
  4434.3   0.035       0  4440.8    0.07       0  4656.9    0.05       0
  4737.8     0.1       0  4983.8    0.05       0  4987.9     0.1       0
  5110.1    0.12       0
Bank Sta=4983.8,4987.9
Exp/Cntr=0.3,0.1

Type RM Length L Ch R = 1,7210,423,423,423
BEGIN DESCRIPTION:
StreamM013 11.0
END DESCRIPTION:
XS GIS Cut Line= 3
      2502674.97     13845224.96      2502375.00     13844825.00
      2501575.03     13844075.03
#Sta/Elev= 30
  4495.3  454.29  4525.2  453.68  4622.7  450.35  4748.2  446.17  4860.1  441.16
  4869.9  441.11  4931.7  437.95  5042.7  436.81  5043.0  436.31  5046.9  436.81
  5106.8  438.15  5186.5  439.22  5207.5  438.21  5278.3  441.14  5327.7  440.75
  5349.1  442.43  5412.6  442.50  5511.8  446.51  5526.0  448.12  5554.3  447.56
  5580.5  448.89  5625.1  448.72  5660.3  452.01  5674.4  451.62  5729.6  455.10
  5745.3  456.29  5759.4  455.60  5766.3  456.92  5914.8  464.02  6091.8  470.69
#Mann=11,-1,0
  4495.3    0.07       0  4525.2    0.12       0  4622.7    0.07       0
  4748.2    0.12       0  4860.1    0.07       0  4869.9     0.1       0
  5042.7    0.05       0  5046.9     0.1       0  5106.8    0.12       0
  5580.5    0.07       0  5729.6    0.12       0
Bank Sta=5042.7,5046.9
Exp/Cntr=0.3,0.1

Type RM Length L Ch R = 1,6787,462,462,462
BEGIN DESCRIPTION:
StreamM013 10.0
END DESCRIPTION:
XS GIS Cut Line= 3
      2502774.99     13845124.95      2502575.00     13844475.00
      2502175.01     13844075.01
#Sta/Elev= 30
  4319.7  453.81  4445.9  450.24  4466.1  450.04  4514.0  447.44  4575.3  446.33
  4685.8  440.20  4727.7  439.85  4769.5  438.31  4790.5  439.06  4821.9  437.34
  4861.9  436.86  4918.0  435.58  5003.3  435.18  5011.8  434.06  5012.0  433.56
  5016.0  434.06  5028.0  435.47  5112.5  436.13  5127.0  435.93  5169.4  438.35
  5226.0  440.07  5240.1  439.49  5282.6  441.67  5325.0  442.73  5353.3  441.30
  5381.6  442.08  5409.8  445.32  5452.3  446.55  5480.6  448.66  5565.4  452.50
#Mann=7,-1,0
  4319.7    0.12       0  4445.9    0.07       0  4514.0    0.12       0
  4861.9     0.1       0  5011.8    0.05       0  5016.0     0.1       0
  5112.5    0.12       0
Bank Sta=5011.8,5016
Exp/Cntr=0.3,0.1

Type RM Length L Ch R = 1,6325,424,424,424
BEGIN DESCRIPTION:
StreamM013 9.0
END DESCRIPTION:
XS GIS Cut Line= 3
      2502975.00     13844775.00      2502775.00     13844125.00
      2502374.98     13843824.99
#Sta/Elev= 30
  4315.1  448.58  4351.8  447.18  4383.1  445.60  4455.7  443.32  4565.6  439.82
  4576.7  440.69  4603.5  439.86  4608.7  440.85  4618.5  439.70  4689.9  439.27
  4706.8  438.17  4804.9  437.36  4810.1  435.91  4837.6  436.65  4842.8  435.25
  4940.9  434.32  4946.1  432.71  4963.8  433.79  4995.8  433.12  5008.7  433.24
  5014.9  431.61  5015.2  431.11  5019.2  431.61  5095.2  433.20  5118.8  435.40
  5137.9  435.52  5173.3  438.35  5217.1  438.89  5331.6  443.76  5495.2  448.36
#Mann=9,-1,0
  4315.1    0.07       0  4351.8    0.12       0  4383.1   0.035       0
  4455.7    0.12       0  4689.9   0.035       0  4995.8     0.1       0
  5014.9    0.05       0  5019.2     0.1       0  5118.8    0.12       0
Bank Sta=5014.9,5019.2
Exp/Cntr=0.3,0.1

Type RM Length L Ch R = 1,5901,450,450,450
BEGIN DESCRIPTION:
StreamM013 8.0
END DESCRIPTION:
XS GIS Cut Line= 3
      2503375.00     13844675.01      2502975.00     13843775.00
      2502224.99     13843775.00
#Sta/Elev= 30
  4015.1  444.34  4257.4  441.45  4371.4  438.37  4376.9  439.58  4387.2  438.11
  4507.6  435.54  4539.7  436.12  4803.0  432.54  4844.0  430.82  4869.4  428.51
  4910.4  430.34  4933.7  430.26  4943.1  428.42  4943.4  427.92  4947.4  428.42
  5050.0  429.77  5090.0  432.63  5163.7  434.88  5210.0  435.36  5230.0  437.24
  5260.0  435.27  5290.0  439.25  5333.7  440.68  5400.0  441.98  5420.0  443.62
  5430.0  442.83  5480.0  445.41  5560.0  446.29  5720.0  453.81  5750.0  454.03
#Mann=7,-1,0
  4015.1    0.05       0  4257.4    0.12       0  4844.0     0.1       0
  4943.1    0.05       0  4947.4     0.1       0  5163.7   0.035       0
  5333.7    0.12       0
Bank Sta=4943.1,4947.4
Exp/Cntr=0.3,0.1

Type RM Length L Ch R = 1,5451,419,419,419
BEGIN DESCRIPTION:
H21158
END DESCRIPTION:
XS GIS Cut Line= 4
      2503464.99     13844415.03      2503208.12     13843501.69
      2502951.25     13843378.01      2502300.25     13842959.85
#Sta/Elev= 30
  3848.5  441.39  3878.9  441.76  4118.6  434.88  4326.4  431.90  4423.0  432.05
  4523.7  427.80  4544.5  429.36  4564.4  427.95  4626.8  428.26  4729.8  428.85
  4916.8  428.09  4962.1  425.17  4967.6  426.57  4982.6  423.69  4982.9  423.19
  4986.9  423.69  5000.5  426.27  5111.7  427.42  5169.1  430.46  5371.9  430.51
  5450.5  432.04  5494.0  435.45  5553.3  436.75  5609.0  440.19  5632.2  441.78
  5684.4  441.29  5695.9  440.44  5724.0  442.52  5839.0  446.11  5856.1  446.26
#Mann=11,-1,0
  3848.5    0.05       0  3878.9    0.12       0  4626.8    0.05       0
  4729.8     0.1       0  4982.6    0.05       0  4986.9     0.1       0
  5494.0    0.07       0  5609.0   0.035       0  5684.4    0.07       0
  5724.0   0.035       0  5839.0    0.12       0
Bank Sta=4982.6,4986.9
Exp/Cntr=0.3,0.1

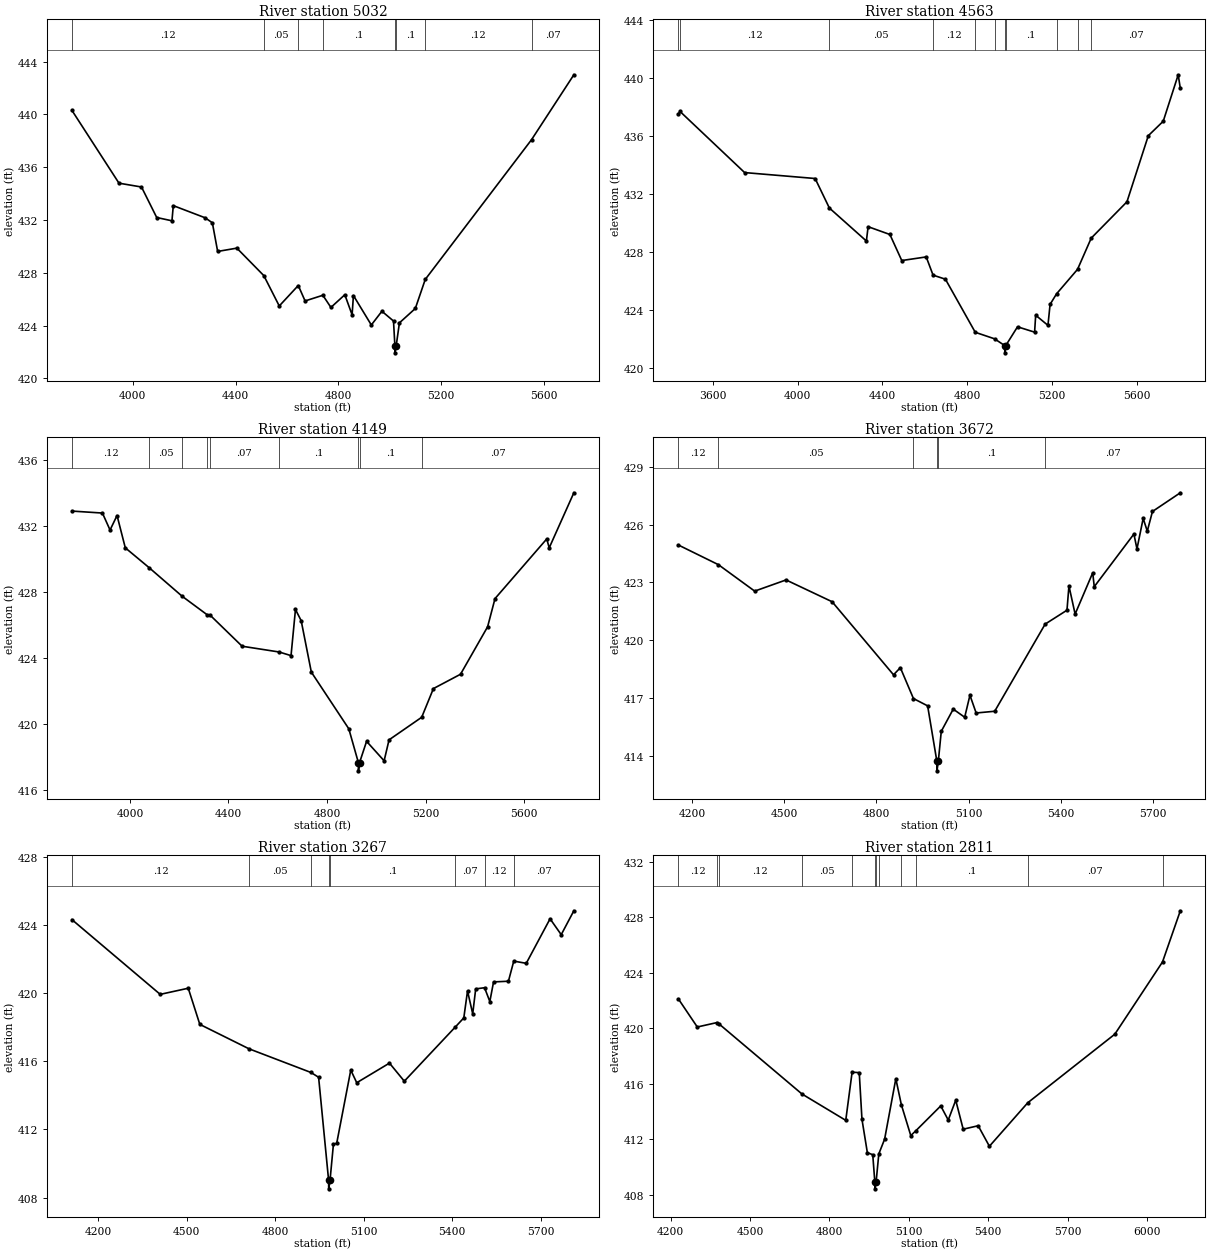
Type RM Length L Ch R = 1,5032,469,469,469
BEGIN DESCRIPTION:
StreamM013 7.0
END DESCRIPTION:
XS GIS Cut Line= 3
      2503525.00     13844324.99      2503225.00     13843125.00
      2502575.01     13842825.01
#Sta/Elev= 30
  3763.0  440.30  3946.0  434.79  4033.6  434.50  4092.8  432.19  4152.1  431.94
  4157.3  433.09  4281.0  432.17  4309.3  431.79  4329.9  429.62  4404.6  429.87
  4509.5  427.79  4569.6  425.49  4643.6  427.04  4670.1  425.87  4739.2  426.30
  4770.6  425.38  4824.7  426.34  4853.0  424.82  4858.2  426.28  4927.8  424.05
  4969.0  425.09  5014.1  424.35  5019.6  422.44  5019.9  421.94  5024.3  422.44
  5037.1  424.21  5099.0  425.30  5137.6  427.50  5551.4  438.09  5715.8  443.00
#Mann=8,-1,0
  3763.0    0.12       0  4509.5    0.05       0  4643.6    0.12       0
  4739.2     0.1       0  5019.6    0.05       0  5024.3     0.1       0
  5137.6    0.12       0  5551.4    0.07       0
Bank Sta=5019.6,5024.3
Exp/Cntr=0.3,0.1

Type RM Length L Ch R = 1,4563,414,414,414
BEGIN DESCRIPTION:
StreamM013 6.0
END DESCRIPTION:
XS GIS Cut Line= 3
      2503724.99     13844374.95      2503525.00     13842825.00
      2502725.03     13842725.00
#Sta/Elev= 30
  3437.2  437.53  3444.4  437.71  3749.7  433.48  4082.5  433.07  4149.7  431.03
  4324.4  428.75  4332.6  429.74  4435.4  429.20  4491.4  427.40  4606.8  427.65
  4639.2  426.39  4697.5  426.11  4838.3  422.44  4929.3  421.99  4977.5  421.52
  4977.8  421.02  4982.2  421.52  5037.8  422.82  5118.4  422.45  5123.5  423.62
  5181.4  422.92  5191.5  424.37  5222.1  425.10  5321.0  426.79  5385.7  428.95
  5554.3  431.46  5655.1  436.03  5725.6  437.03  5796.2  440.24  5806.2  439.30
#Mann=11,-1,0
  3437.2   0.035       0  3444.4    0.12       0  4149.7    0.05       0
  4639.2    0.12       0  4838.3    0.07       0  4929.3     0.1       0
  4977.5    0.05       0  4982.2     0.1       0  5222.1    0.07       0
  5321.0    0.12       0  5385.7    0.07       0
Bank Sta=4977.5,4982.2
Exp/Cntr=0.3,0.1

Type RM Length L Ch R = 1,4149,477,477,477
BEGIN DESCRIPTION:
StreamM013 5.0
END DESCRIPTION:
XS GIS Cut Line= 3
      2504025.00     13843725.01      2503725.00     13842525.00
      2502925.04     13842525.00
#Sta/Elev= 30
  3764.7  432.92  3888.4  432.80  3919.3  431.77  3947.7  432.65  3981.2  430.69
  4078.4  429.48  4212.1  427.75  4314.2  426.62  4323.7  426.63  4455.3  424.72
  4605.7  424.37  4653.8  424.15  4671.8  426.95  4695.0  426.27  4736.2  423.15
  4888.3  419.71  4927.1  417.66  4927.4  417.16  4931.9  417.66  4960.4  418.95
  5031.6  417.77  5051.6  419.04  5184.1  420.41  5231.6  422.15  5341.6  423.02
  5451.6  425.90  5481.6  427.61  5691.6  431.23  5701.6  430.69  5801.6  434.03
#Mann=9,-1,0
  3764.7    0.12       0  4078.4    0.05       0  4212.1    0.07       0
  4314.2    0.05       0  4323.7    0.07       0  4605.7     0.1       0
  4927.1    0.05       0  4931.9     0.1       0  5184.1    0.07       0
Bank Sta=4927.1,4931.9
Exp/Cntr=0.3,0.1

Type RM Length L Ch R = 1,3672,405,405,405
BEGIN DESCRIPTION:
H21157
END DESCRIPTION:
XS GIS Cut Line= 3
      2504297.41     13843025.98      2503874.07     13842198.32
      2503174.87     13842117.46
#Sta/Elev= 30
  4155.8  424.94  4286.1  423.92  4404.0  422.55  4506.1  423.13  4656.0  422.00
  4855.9  418.21  4878.1  418.58  4920.7  416.98  4966.9  416.60  4996.9  413.73
  4997.3  413.23  5001.7  413.73  5011.3  415.28  5050.2  416.43  5087.5  416.01
  5104.6  417.15  5124.8  416.23  5185.2  416.32  5349.4  420.84  5420.4  421.56
  5426.8  422.82  5446.9  421.36  5504.2  423.50  5509.2  422.78  5638.2  425.51
  5648.2  424.74  5668.4  426.32  5681.8  425.66  5698.6  426.68  5789.3  427.65
#Mann=6,-1,0
  4155.8    0.12       0  4286.1    0.05       0  4920.7     0.1       0
  4996.9    0.05       0  5001.7     0.1       0  5349.4    0.07       0
Bank Sta=4996.9,5001.7
Exp/Cntr=0.3,0.1

Type RM Length L Ch R = 1,3267,456,456,456
BEGIN DESCRIPTION:
StreamM013 4.0
END DESCRIPTION:
XS GIS Cut Line= 3
      2504525.01     13842775.03      2504125.00     13841975.00
      2503324.98     13841875.00
#Sta/Elev= 30
  4111.4  424.30  4410.5  419.92  4505.5  420.28  4544.7  418.16  4711.2  416.73
  4921.4  415.34  4947.2  415.06  4981.1  409.02  4981.4  408.52  4985.9  409.02
  4997.5  411.15  5008.4  411.18  5056.2  415.48  5076.4  414.74  5187.3  415.89
  5237.6  414.83  5410.6  418.01  5439.2  418.54  5451.8  420.12  5469.4  418.78
  5479.5  420.24  5509.5  420.31  5527.4  419.50  5540.0  420.65  5590.4  420.69
  5608.5  421.87  5650.8  421.74  5731.5  424.35  5769.3  423.42  5812.1  424.82
#Mann=8,-1,0
  4111.4    0.12       0  4711.2    0.05       0  4921.4     0.1       0
  4981.1    0.05       0  4985.9     0.1       0  5410.6    0.07       0
  5509.5    0.12       0  5608.5    0.07       0
Bank Sta=4981.1,4985.9
Exp/Cntr=0.3,0.1

Type RM Length L Ch R = 1,2811,452,452,452
BEGIN DESCRIPTION:
StreamM013 3.0
END DESCRIPTION:
XS GIS Cut Line= 3
      2504624.99     13842474.96      2504475.00     13841725.00
      2503674.99     13840924.99
#Sta/Elev= 30
  4229.9  422.12  4301.2  420.10  4375.9  420.42  4381.6  420.35  4696.6  415.27
  4862.1  413.37  4886.1  416.84  4913.1  416.81  4923.3  413.45  4943.7  411.04
  4964.1  410.89  4971.9  408.93  4972.2  408.43  4976.8  408.93  4987.0  410.95
  5008.9  412.01  5051.3  416.37  5072.2  414.49  5107.8  412.27  5127.0  412.62
  5221.0  414.41  5249.3  413.39  5277.6  414.82  5305.8  412.73  5362.4  412.98
  5404.8  411.50  5549.9  414.64  5878.6  419.58  6058.8  424.79  6126.1  428.48
#Mann=12,-1,0
  4229.9    0.12       0  4375.9    0.05       0  4381.6    0.12       0
  4696.6    0.05       0  4886.1    0.12       0  4971.9    0.05       0
  4976.8    0.12       0  4987.0     0.1       0  5072.2    0.07       0
  5127.0     0.1       0  5549.9    0.07       0  6058.8    0.05       0
Bank Sta=4971.9,4976.8
Exp/Cntr=0.3,0.1