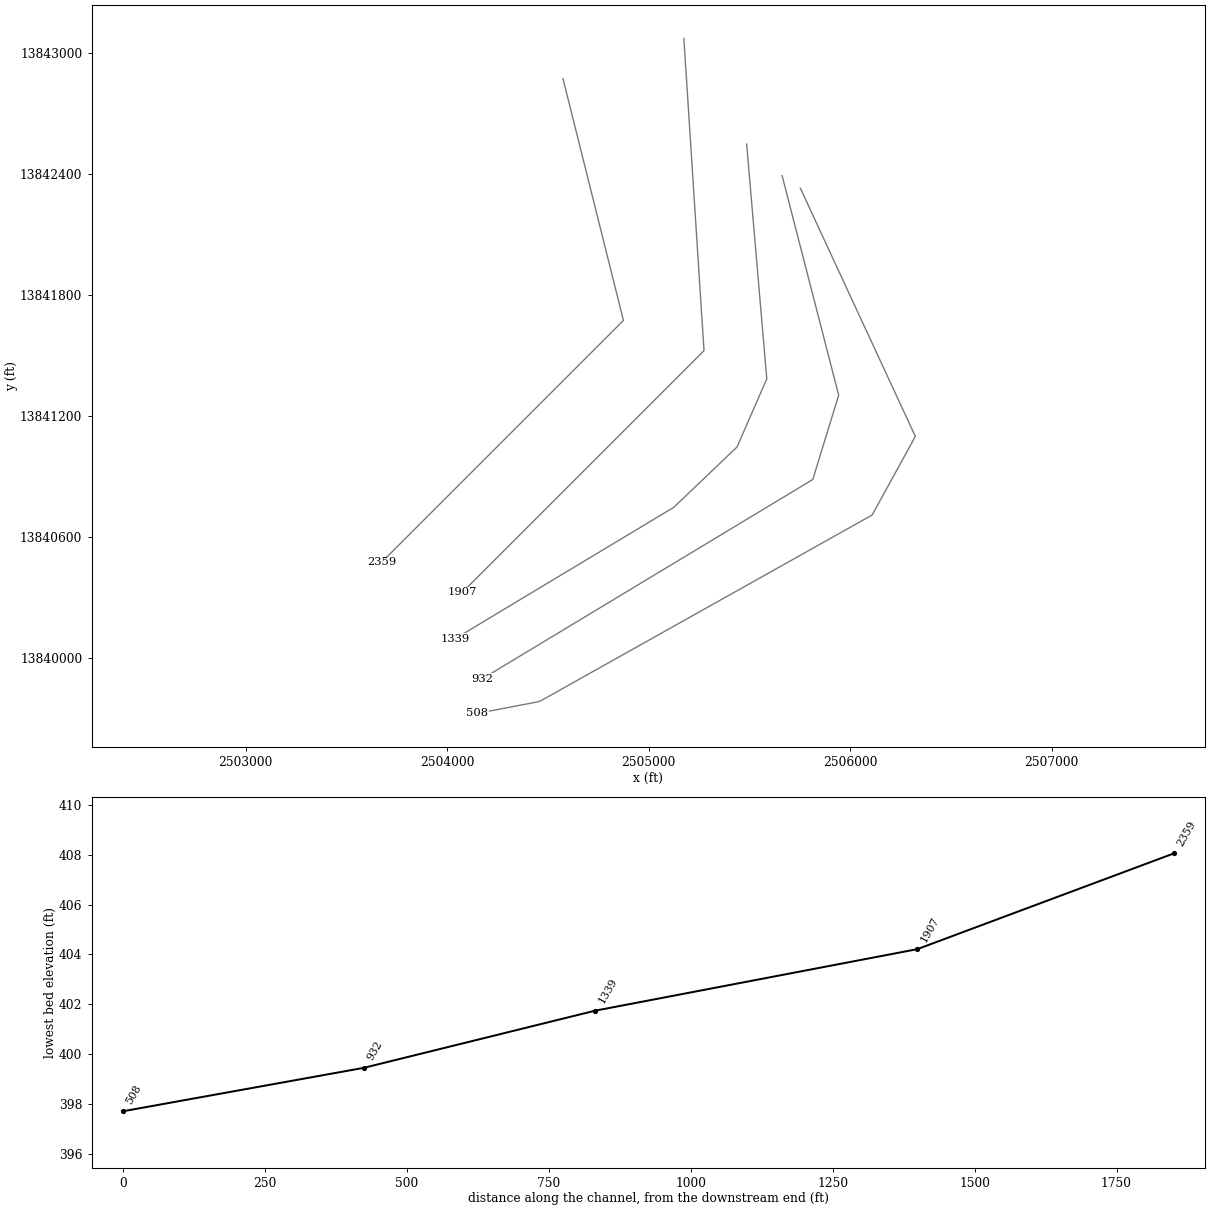
HEC-RAS study StreamM013.prj: StreamM013 Base Level Engineering

--- StreamM013.g01 (geometry) --- (continued)

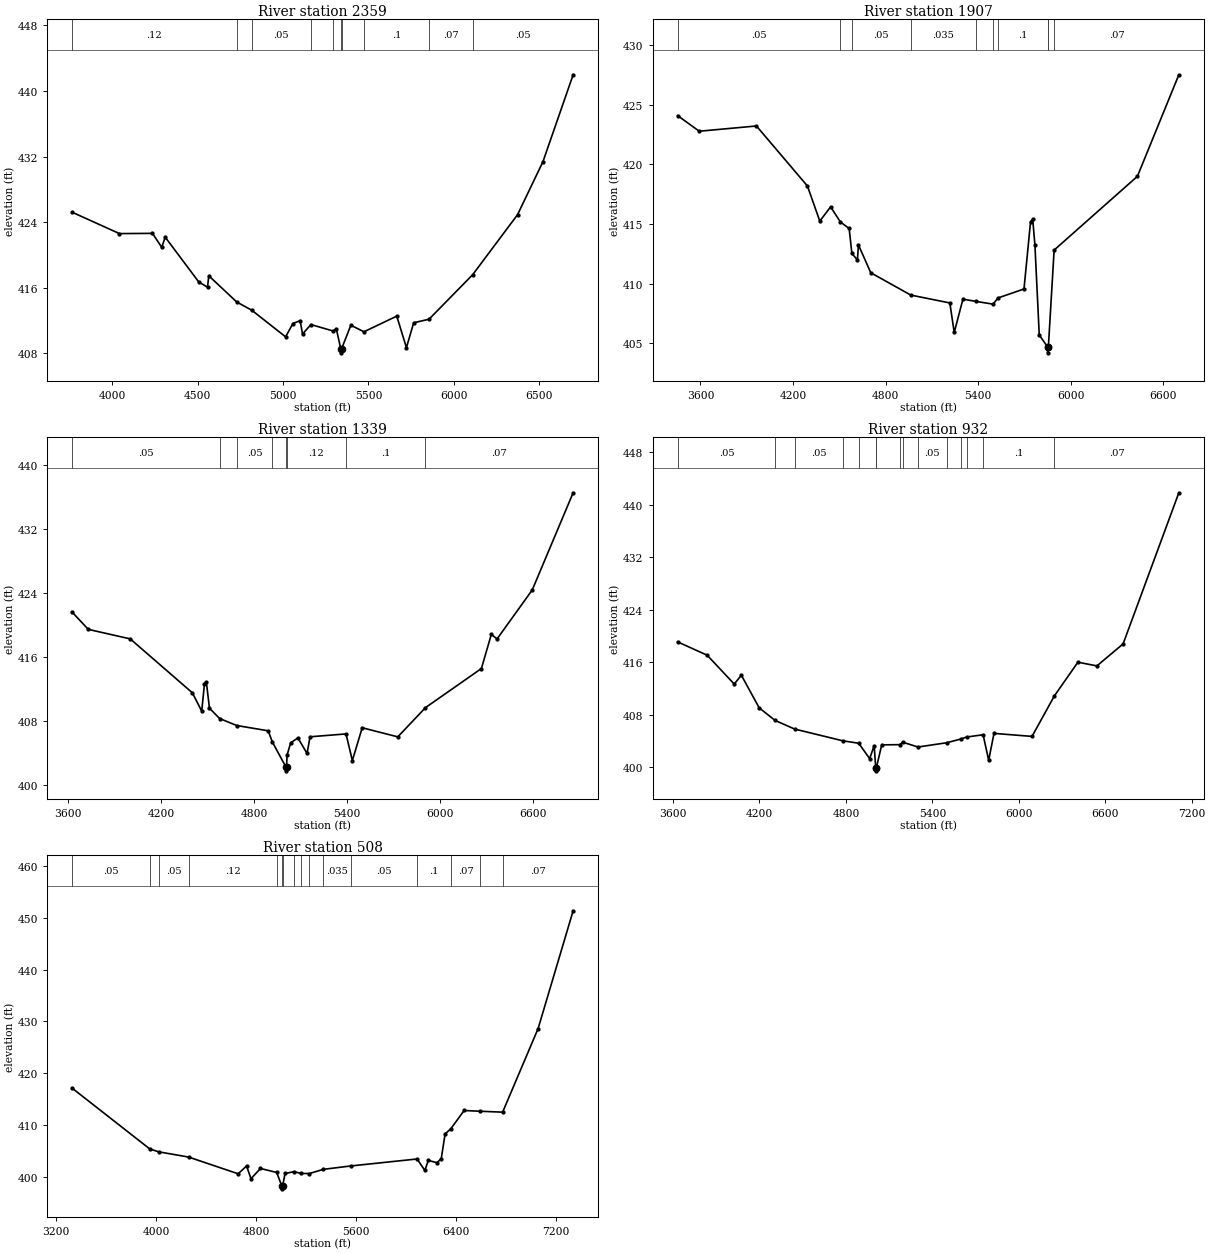
Type RM Length L Ch R = 1,2359,452,452,452
BEGIN DESCRIPTION:
StreamM013 2.0
END DESCRIPTION:
XS GIS Cut Line= 3
      2504575.01     13842874.97      2504875.00     13841675.00
      2503674.97     13840474.97
#Sta/Elev= 30
  3763.9  425.22  4042.2  422.60  4235.5  422.63  4289.6  420.93  4310.2  422.16
  4506.0  416.71  4557.6  416.06  4565.3  417.45  4729.0  414.25  4816.8  413.25
  5014.9  410.00  5057.4  411.63  5099.8  411.98  5113.9  410.34  5163.0  411.50
  5292.4  410.72  5311.9  410.95  5337.8  408.55  5338.1  408.05  5342.7  408.55
  5396.8  411.42  5473.5  410.62  5665.5  412.53  5722.1  408.68  5764.5  411.72
  5854.3  412.15  6110.1  417.59  6372.6  424.91  6521.1  431.37  6697.9  441.98
#Mann=10,-1,0
  3763.9    0.12       0  4729.0    0.07       0  4816.8    0.05       0
  5163.0   0.035       0  5292.4    0.07       0  5337.8    0.05       0
  5342.7    0.07       0  5473.5     0.1       0  5854.3    0.07       0
  6110.1    0.05       0
Bank Sta=5337.8,5342.7
Exp/Cntr=0.3,0.1

Type RM Length L Ch R = 1,1907,568,568,568
BEGIN DESCRIPTION:
StreamM013 1.0
END DESCRIPTION:
XS GIS Cut Line= 3
      2505175.00     13843075.04      2505275.00     13841525.00
      2504075.02     13840325.02
#Sta/Elev= 30
  3451.7  424.09  3592.0  422.78  3962.8  423.22  4293.5  418.19  4373.7  415.25
  4443.8  416.44  4507.6  415.17  4564.1  414.63  4581.7  412.54  4617.9  411.99
  4624.2  413.26  4704.3  410.92  4963.8  409.05  5217.1  408.39  5245.4  405.92
  5302.0  408.71  5386.1  408.52  5497.5  408.29  5529.3  408.81  5697.9  409.56
  5740.4  415.20  5754.5  415.39  5768.6  413.28  5796.9  405.70  5851.0  404.71
  5851.3  404.21  5856.0  404.71  5893.3  412.82  6433.3  419.00  6702.0  427.51
#Mann=10,-1,0
  3451.7    0.05       0  4507.6    0.07       0  4581.7    0.05       0
  4963.8   0.035       0  5386.1    0.12       0  5497.5   0.035       0
  5529.3     0.1       0  5851.0   0.035       0  5856.0     0.1       0
  5893.3    0.07       0
Bank Sta=5851,5856
Exp/Cntr=0.3,0.1

Type RM Length L Ch R = 1,1339,407,407,407
BEGIN DESCRIPTION:
J21151
END DESCRIPTION:
XS GIS Cut Line= 5
      2505486.63     13842550.33      2505586.52     13841384.91
      2505439.06     13841047.18      2505125.11     13840747.50
      2504040.57     13840095.83
#Sta/Elev= 30
  3624.4  421.63  3730.1  419.44  4001.1  418.25  4402.6  411.50  4462.8  409.21
  4480.7  412.65  4492.9  412.81  4513.0  409.57  4578.9  408.28  4689.1  407.41
  4892.2  406.75  4918.9  405.36  5006.0  402.24  5006.4  401.74  5011.0  402.24
  5014.0  403.70  5037.4  405.24  5084.2  405.86  5143.2  403.91  5162.6  406.00
  5394.9  406.36  5435.8  403.03  5499.6  407.13  5729.3  405.99  5908.3  409.65
  6269.5  414.54  6333.6  418.82  6370.5  418.24  6597.8  424.37  6861.9  436.53
#Mann=8,-1,0
  3624.4    0.05       0  4578.9   0.035       0  4689.1    0.05       0
  4918.9    0.12       0  5006.0    0.05       0  5011.0    0.12       0
  5394.9     0.1       0  5908.3    0.07       0
Bank Sta=5006,5011
Exp/Cntr=0.3,0.1

Type RM Length L Ch R = 1,932,424,424,424
BEGIN DESCRIPTION:
J21150
END DESCRIPTION:
XS GIS Cut Line= 4
      2505662.64     13842393.31      2505943.28     13841304.04
      2505814.84     13840885.45      2504173.73     13839896.02
#Sta/Elev= 30
  3631.7  419.11  3836.5  417.08  4024.7  412.68  4074.0  414.03  4197.9  409.05
  4308.6  407.13  4444.0  405.82  4779.8  404.02  4888.6  403.66  4964.7  401.31
  4996.1  403.30  5006.5  399.95  5006.9  399.45  5011.6  399.95  5048.4  403.41
  5173.3  403.44  5195.7  403.81  5299.7  403.08  5498.5  403.73  5595.6  404.29
  5639.1  404.61  5752.2  404.95  5790.8  401.06  5827.7  405.16  6091.7  404.70
  6246.4  410.86  6410.1  416.01  6542.1  415.45  6723.9  418.80  7110.7  441.84
#Mann=15,-1,0
  3631.7    0.05       0  4308.6   0.035       0  4444.0    0.05       0
  4779.8    0.12       0  4888.6     0.1       0  5006.5    0.05       0
  5011.6     0.1       0  5173.3    0.12       0  5195.7   0.035       0
  5299.7    0.05       0  5498.5    0.12       0  5595.6    0.05       0
  5639.1    0.12       0  5752.2     0.1       0  6246.4    0.07       0
Bank Sta=5006.5,5011.6
Exp/Cntr=0.3,0.1

Type RM Length L Ch R = 1,508,0,0,0
BEGIN DESCRIPTION:
J21149
END DESCRIPTION:
XS GIS Cut Line= 6
      2505753.00     13842331.53      2506323.82     13841099.50
      2506109.77     13840709.44      2504463.91     13839786.62
      2504449.64     13839781.87      2504149.96     13839724.79
#Sta/Elev= 30
  3325.6  417.16  3948.7  405.40  4019.3  404.85  4259.2  403.84  4655.7  400.61
  4722.8  402.12  4758.2  399.66  4834.0  401.64  4963.8  400.87  5005.9  398.21
  5006.3  397.71  5011.0  398.21  5030.8  400.67  5103.9  401.03  5156.6  400.68
  5225.6  400.66  5336.8  401.47  5559.1  402.13  6086.9  403.47  6149.0  401.26
  6177.1  403.19  6245.9  402.75  6280.3  403.51  6311.1  408.30  6356.2  409.28
  6463.7  412.82  6594.2  412.67  6771.4  412.50  7055.4  428.63  7335.4  451.34
#Mann=16,-1,0
  3325.6    0.05       0  3948.7   0.035       0  4019.3    0.05       0
  4259.2    0.12       0  4963.8     0.1       0  5005.9    0.05       0
  5011.0     0.1       0  5103.9    0.12       0  5156.6   0.035       0
  5225.6    0.05       0  5336.8   0.035       0  5559.1    0.05       0
  6086.9     0.1       0  6356.2    0.07       0  6594.2    0.12       0
  6771.4    0.07       0
Bank Sta=5005.9,5011
Exp/Cntr=0.3,0.1

Chan Stop Cuts=-1