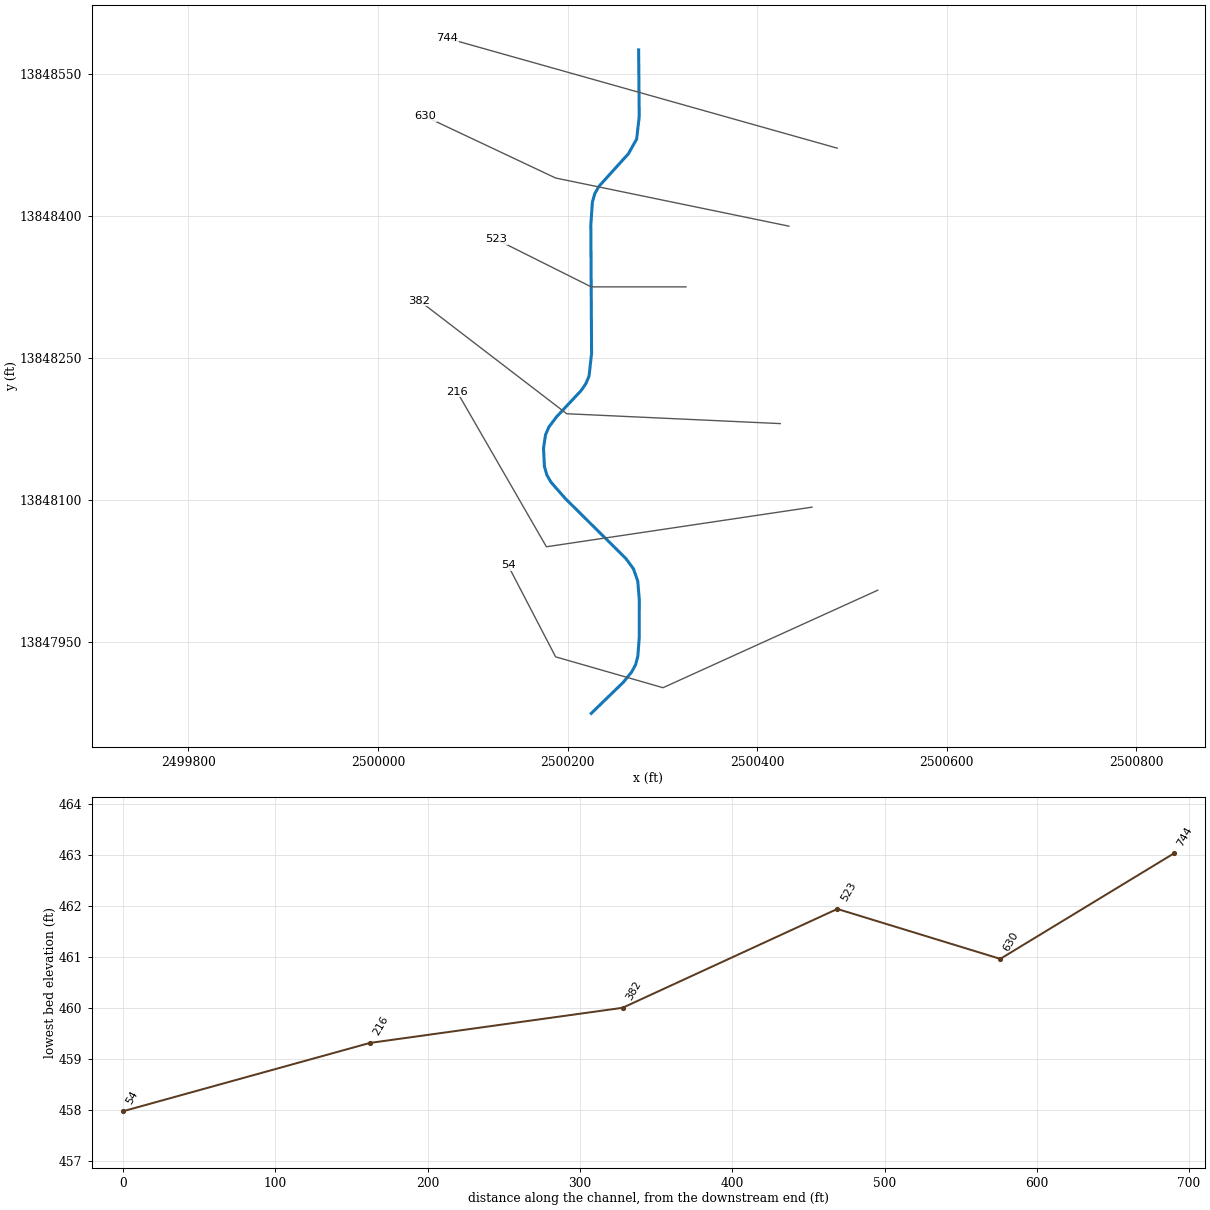
--- StreamM014.prj (project) ---

Proj Title=StreamM014 Base Level Engineering
Current Plan=p01
Default Exp/Contr=0.3,0.1
English Units
Geom File=g01
Flow File=f01
Plan File=p01
BEGIN DESCRIPTION:
StreamM014
END DESCRIPTION:

--- StreamM014.p01 (plan) ---

Plan Title=Multiple Run
Short Identifier=Multiple
Geom File=g01
Flow File=f01
Subcritical Flow
K Sum by GR= 0
Std Step Tol= 0.01
Critical Tol= 0.01
Num of Std Step Trials= 20
Max Error Tol= 0.3
Flow Tol Ratio= 0.001
Split Flow NTrial= 30
Split Flow Tol= 0.02
Split Flow Ratio= 0.02
Log Output Level= 0
Friction Slope Method= 1
Unsteady Friction Slope Method= 2
Unsteady Bridges Friction Slope Method= 1
Parabolic Critical Depth
Global Vel Dist=  1 , 1 , 1
Global Log Level= 0
CheckData=True
Encroach Param= -1, 0, 0, 0
BEGIN DESCRIPTION:
Multiple Run
END DESCRIPTION:

--- StreamM014.f01 (steady flow) ---

Flow Title=Multiple
Number of Profiles=7
Profile Names=10-year,25-year,50-year,1pct_min,100-year,1pct_plu,500-year
River Rch & RM= StreamM014,Reach-1,744
     305     470     613     390     778    1553    1235
Boundary for River Rch & Prof#=StreamM014,Reach-1,1
Up Type=0
Dn Type=3
Dn Slope=0.005
Boundary for River Rch & Prof#=StreamM014,Reach-1,2
Up Type=0
Dn Type=3
Dn Slope=0.005
Boundary for River Rch & Prof#=StreamM014,Reach-1,3
Up Type=0
Dn Type=3
Dn Slope=0.005
Boundary for River Rch & Prof#=StreamM014,Reach-1,4
Up Type=0
Dn Type=3
Dn Slope=0.005
Boundary for River Rch & Prof#=StreamM014,Reach-1,5
Up Type=0
Dn Type=3
Dn Slope=0.005
Boundary for River Rch & Prof#=StreamM014,Reach-1,6
Up Type=0
Dn Type=3
Dn Slope=0.005
Boundary for River Rch & Prof#=StreamM014,Reach-1,7
Up Type=0
Dn Type=3
Dn Slope=0.005

--- StreamM014.g01 (geometry) ---

Geom Title=Existing Conditions

River Reach=StreamM014,Reach-1
Reach XY= 30
      2500275.00     13848575.00      2500275.63     13848504.74
      2500272.90     13848480.87      2500264.14     13848465.36
      2500233.10     13848431.07      2500228.75     13848423.45
      2500226.20     13848414.50      2500224.57     13848390.18
      2500225.35     13848254.85      2500222.71     13848230.93
      2500219.21     13848222.65      2500214.09     13848215.33
      2500188.53     13848188.03      2500180.35     13848177.17
      2500176.78     13848168.87      2500174.64     13848154.79
      2500175.60     13848135.62      2500178.14     13848126.64
      2500182.50     13848118.95      2500197.76     13848101.55
      2500261.63     13848038.30      2500269.59     13848027.43
      2500274.07     13848014.53      2500275.68     13847995.11
      2500275.65     13847954.97      2500274.19     13847935.46
      2500271.82     13847926.41      2500267.65     13847918.68
      2500258.96     13847907.95      2500225.00     13847875.00

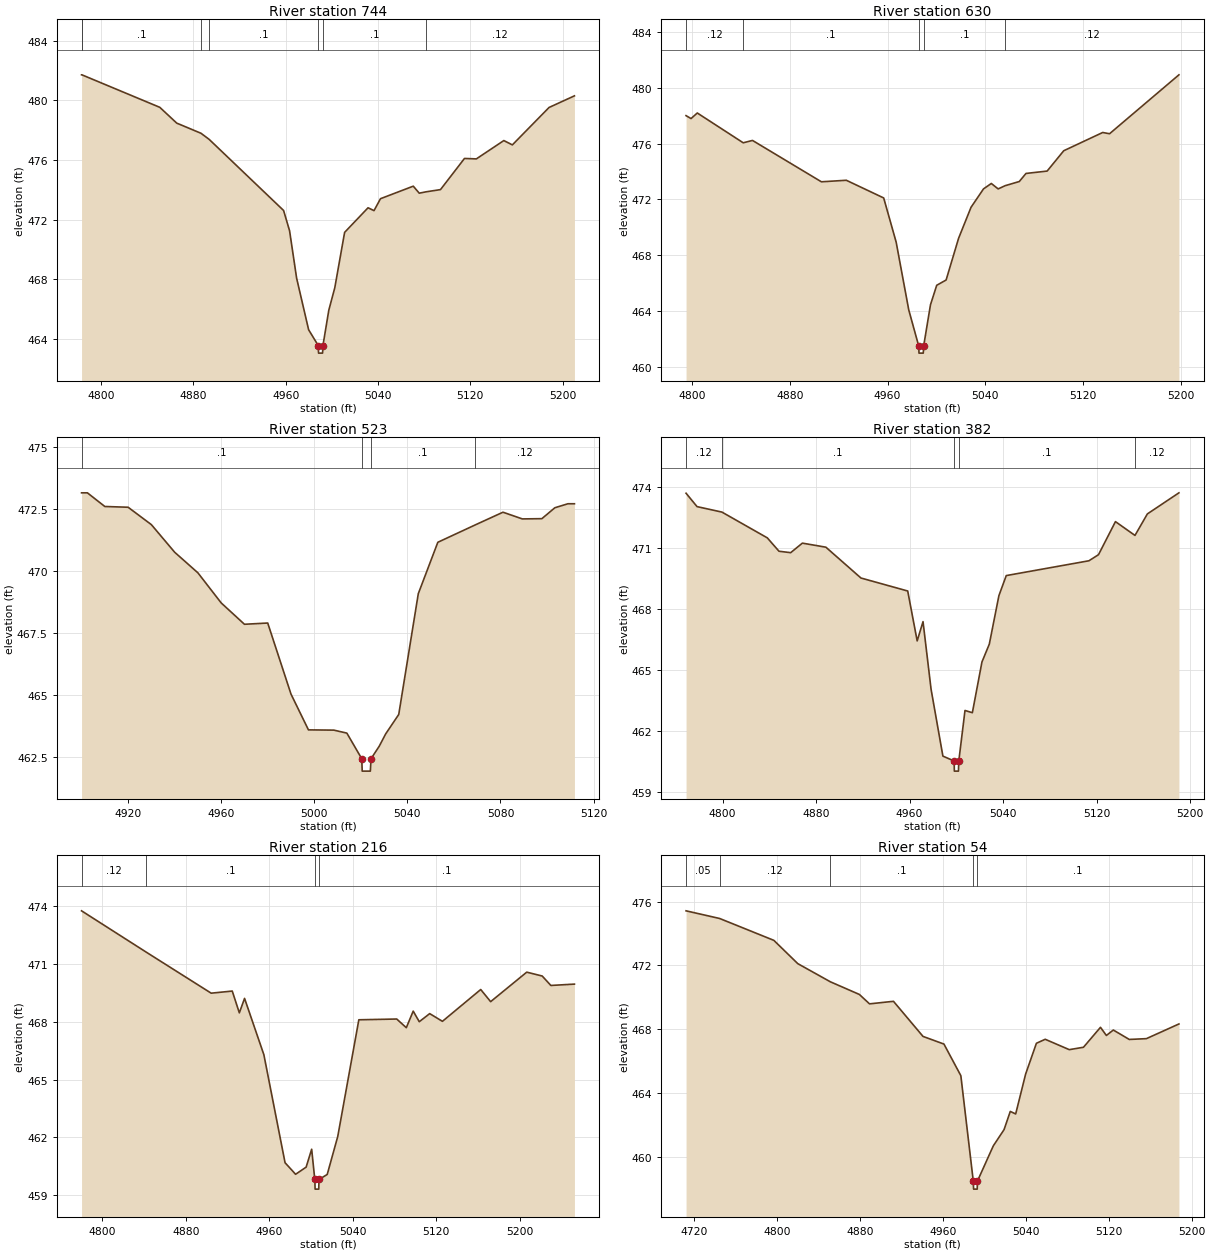
Type RM Length L Ch R = 1,744,114,114,114
BEGIN DESCRIPTION:
MXS18473
END DESCRIPTION:
XS GIS Cut Line= 2
      2500484.42     13848471.37      2500073.23     13848587.22
#Sta/Elev= 30
  4783.0  481.71  4783.3  481.71  4850.8  479.53  4865.5  478.47  4886.5  477.79
  4893.6  477.38  4958.1  472.61  4963.3  471.25  4969.4  468.07  4979.8  464.61
  4988.2  463.54  4988.4  463.04  4991.9  463.04  4992.2  463.54  4997.3  465.92
  5002.5  467.43  5011.0  471.14  5031.3  472.79  5036.5  472.60  5042.1  473.40
  5070.5  474.24  5075.7  473.77  5081.5  473.86  5094.1  474.01  5114.9  476.10
  5125.2  476.07  5149.0  477.30  5156.4  477.01  5188.2  479.52  5210.2  480.30
#Mann=7,-1,0
  4783.0    0.12       0  4783.3     0.1       0  4886.5    0.12       0
  4893.6     0.1       0  4988.2    0.05       0  4992.2     0.1       0
  5081.5    0.12       0
Bank Sta=4988.2,4992.2
Exp/Cntr=0.3,0.1

Type RM Length L Ch R = 1,630,107,107,107
BEGIN DESCRIPTION:
H21170
END DESCRIPTION:
XS GIS Cut Line= 3
      2500433.49     13848389.07      2500187.42     13848439.84
      2500049.73     13848504.79
#Sta/Elev= 30
  4795.0  478.02  4799.1  477.81  4804.2  478.21  4841.8  476.07  4849.4  476.24
  4905.8  473.27  4926.2  473.38  4956.8  472.11  4967.0  468.94  4977.3  464.08
  4985.5  461.47  4985.7  460.97  4989.2  460.97  4989.5  461.47  4995.1  464.44
  5000.2  465.84  5007.9  466.22  5018.1  469.21  5028.3  471.44  5038.5  472.76
  5044.9  473.15  5050.5  472.76  5056.2  472.99  5067.8  473.29  5073.3  473.87
  5090.6  474.04  5104.2  475.50  5136.1  476.81  5141.7  476.72  5198.5  480.95
#Mann=5,-1,0
  4795.0    0.12       0  4841.8     0.1       0  4985.5    0.05       0
  4989.5     0.1       0  5056.2    0.12       0
Bank Sta=4985.5,4989.5
Exp/Cntr=0.3,0.1

Type RM Length L Ch R = 1,523,141,141,141
BEGIN DESCRIPTION:
StreamM014 1.0
END DESCRIPTION:
XS GIS Cut Line= 3
      2500324.99     13848325.00      2500225.00     13848325.00
      2500125.00     13848375.00
#Sta/Elev= 30
  4900.0  473.15  4902.5  473.15  4910.0  472.60  4920.0  472.57  4930.0  471.87
  4940.0  470.76  4950.0  469.93  4960.0  468.72  4970.0  467.86  4980.0  467.91
  4990.0  465.05  4997.5  463.61  5008.4  463.60  5014.0  463.48  5020.4  462.45
  5020.6  461.95  5024.1  461.95  5024.4  462.45  5027.9  462.95  5030.7  463.45
  5036.3  464.23  5044.7  469.09  5053.1  471.16  5069.2  471.86  5081.1  472.37
  5089.4  472.10  5097.8  472.11  5103.4  472.55  5109.0  472.71  5111.8  472.71
#Mann=4,-1,0
  4900.0     0.1       0  5020.4    0.05       0  5024.4     0.1       0
  5069.2    0.12       0
Bank Sta=5020.4,5024.4
Exp/Cntr=0.3,0.1

Type RM Length L Ch R = 1,382,166,166,166
BEGIN DESCRIPTION:
H21169
END DESCRIPTION:
XS GIS Cut Line= 3
      2500424.43     13848180.73      2500199.14     13848191.15
      2500043.53     13848310.44
#Sta/Elev= 30
  4768.8  473.71  4778.2  473.05  4799.5  472.78  4838.3  471.51  4848.3  470.85
  4858.3  470.78  4868.3  471.25  4888.4  471.05  4918.4  469.53  4958.4  468.89
  4966.5  466.43  4971.5  467.38  4978.4  464.04  4988.5  460.75  4998.1  460.51
  4998.3  460.01  5001.8  460.01  5002.1  460.51  5007.4  463.00  5013.7  462.89
  5021.9  465.39  5028.2  466.27  5036.4  468.66  5042.7  469.65  5113.4  470.38
  5121.6  470.68  5136.1  472.31  5152.8  471.63  5163.4  472.69  5190.4  473.73
#Mann=5,-1,0
  4768.8    0.12       0  4799.5     0.1       0  4998.1    0.05       0
  5002.1     0.1       0  5152.8    0.12       0
Bank Sta=4998.1,5002.1
Exp/Cntr=0.3,0.1

Type RM Length L Ch R = 1,216,162,162,162
BEGIN DESCRIPTION:
MXS18472
END DESCRIPTION:
XS GIS Cut Line= 3
      2500457.83     13848092.56      2500177.71     13848050.78
      2500083.26     13848214.57
#Sta/Elev= 30
  4780.1  473.75  4842.0  471.61  4904.3  469.48  4924.5  469.59  4931.3  468.46
  4936.3  469.21  4954.8  466.29  4975.1  460.69  4985.2  460.09  4995.3  460.46
  5000.6  461.39  5003.6  459.82  5003.9  459.32  5007.4  459.32  5007.6  459.82
  5015.5  460.08  5025.6  462.05  5045.8  468.10  5082.1  468.14  5091.3  467.69
  5097.9  468.55  5103.7  468.00  5113.7  468.42  5125.9  468.02  5162.6  469.67
  5172.1  469.04  5206.7  470.57  5221.5  470.37  5229.8  469.88  5252.4  469.95
#Mann=4,-1,0
  4780.1    0.12       0  4842.0     0.1       0  5003.6    0.05       0
  5007.6     0.1       0
Bank Sta=5003.6,5007.6
Exp/Cntr=0.3,0.1

Type RM Length L Ch R = 1,54,0,0,0
BEGIN DESCRIPTION:
H21168
END DESCRIPTION:
XS GIS Cut Line= 4
      2500527.25     13848004.94      2500300.70     13847902.08
      2500187.42     13847934.64      2500137.21     13848031.19
#Sta/Elev= 30
  4712.2  475.42  4744.6  474.94  4796.9  473.57  4820.0  472.11  4851.5  470.97
  4879.4  470.18  4889.2  469.59  4912.3  469.75  4940.8  467.55  4961.0  467.07
  4977.3  465.09  4989.3  458.48  4989.6  457.98  4993.1  457.98  4993.3  458.48
  5008.6  460.69  5019.0  461.71  5025.0  462.85  5030.2  462.69  5039.8  465.19
  5050.2  467.12  5058.7  467.37  5081.9  466.72  5095.6  466.87  5112.0  468.12
  5117.7  467.61  5124.4  467.95  5139.8  467.36  5156.3  467.41  5187.7  468.33
#Mann=5,-1,0
  4712.2    0.05       0  4744.6    0.12       0  4851.5     0.1       0
  4989.3    0.05       0  4993.3     0.1       0
Bank Sta=4989.3,4993.3
Exp/Cntr=0.3,0.1

Chan Stop Cuts=-1