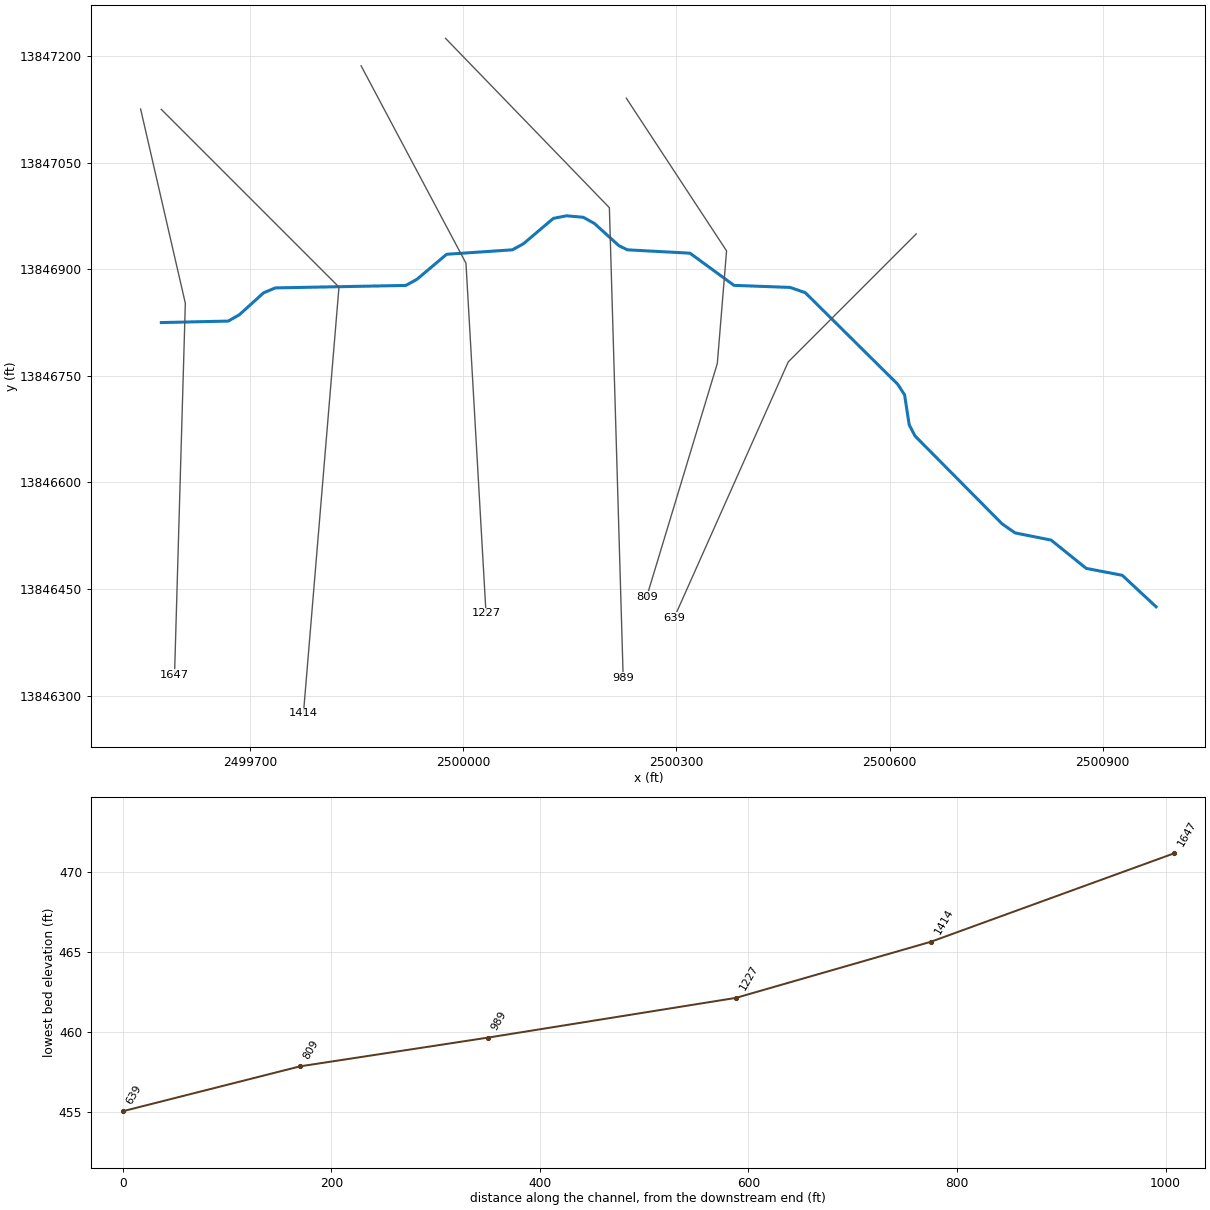
--- StreamM015.prj (project) ---

Proj Title=StreamM015 Base Level Engineering
Current Plan=p01
Default Exp/Contr=0.3,0.1
English Units
Geom File=g01
Flow File=f01
Plan File=p01
BEGIN DESCRIPTION:
StreamM015
END DESCRIPTION:

--- StreamM015.p01 (plan) ---

Plan Title=Multiple Run
Short Identifier=Multiple
Geom File=g01
Flow File=f01
Subcritical Flow
K Sum by GR= 0
Std Step Tol= 0.01
Critical Tol= 0.01
Num of Std Step Trials= 20
Max Error Tol= 0.3
Flow Tol Ratio= 0.001
Split Flow NTrial= 30
Split Flow Tol= 0.02
Split Flow Ratio= 0.02
Log Output Level= 0
Friction Slope Method= 1
Unsteady Friction Slope Method= 2
Unsteady Bridges Friction Slope Method= 1
Parabolic Critical Depth
Global Vel Dist=  1 , 1 , 1
Global Log Level= 0
CheckData=True
Encroach Param= -1, 0, 0, 0
BEGIN DESCRIPTION:
Multiple Run
END DESCRIPTION:

--- StreamM015.f01 (steady flow) ---

Flow Title=Multiple
Number of Profiles=7
Profile Names=10-year,25-year,50-year,1pct_min,100-year,1pct_plu,500-year
River Rch & RM= StreamM015,Reach-1,1647
     234     354     455     285     570    1136     879
Boundary for River Rch & Prof#=StreamM015,Reach-1,1
Up Type=0
Dn Type=3
Dn Slope=0.005
Boundary for River Rch & Prof#=StreamM015,Reach-1,2
Up Type=0
Dn Type=3
Dn Slope=0.005
Boundary for River Rch & Prof#=StreamM015,Reach-1,3
Up Type=0
Dn Type=3
Dn Slope=0.005
Boundary for River Rch & Prof#=StreamM015,Reach-1,4
Up Type=0
Dn Type=3
Dn Slope=0.005
Boundary for River Rch & Prof#=StreamM015,Reach-1,5
Up Type=0
Dn Type=3
Dn Slope=0.005
Boundary for River Rch & Prof#=StreamM015,Reach-1,6
Up Type=0
Dn Type=3
Dn Slope=0.005
Boundary for River Rch & Prof#=StreamM015,Reach-1,7
Up Type=0
Dn Type=3
Dn Slope=0.005

--- StreamM015.g01 (geometry) ---

Geom Title=Existing Conditions

River Reach=StreamM015,Reach-1
Reach XY= 30
      2499575.00     13846825.00      2499669.13     13846827.10
      2499684.64     13846835.86      2499718.93     13846866.90
      2499735.50     13846873.80      2499919.06     13846877.26
      2499934.65     13846885.85      2499976.60     13846921.14
      2500069.03     13846927.38      2500084.65     13846935.95
      2500126.73     13846971.63      2500145.18     13846975.28
      2500168.88     13846973.18      2500184.53     13846964.44
      2500218.95     13846933.24      2500230.97     13846927.38
      2500319.03     13846922.65      2500380.98     13846877.36
      2500459.78     13846874.48      2500481.17     13846867.14
      2500611.37     13846738.21      2500621.02     13846723.35
      2500627.53     13846681.05      2500635.78     13846665.32
      2500758.32     13846541.64      2500776.63     13846528.95
      2500827.19     13846518.90      2500876.67     13846479.04
      2500927.36     13846469.33      2500975.00     13846425.00

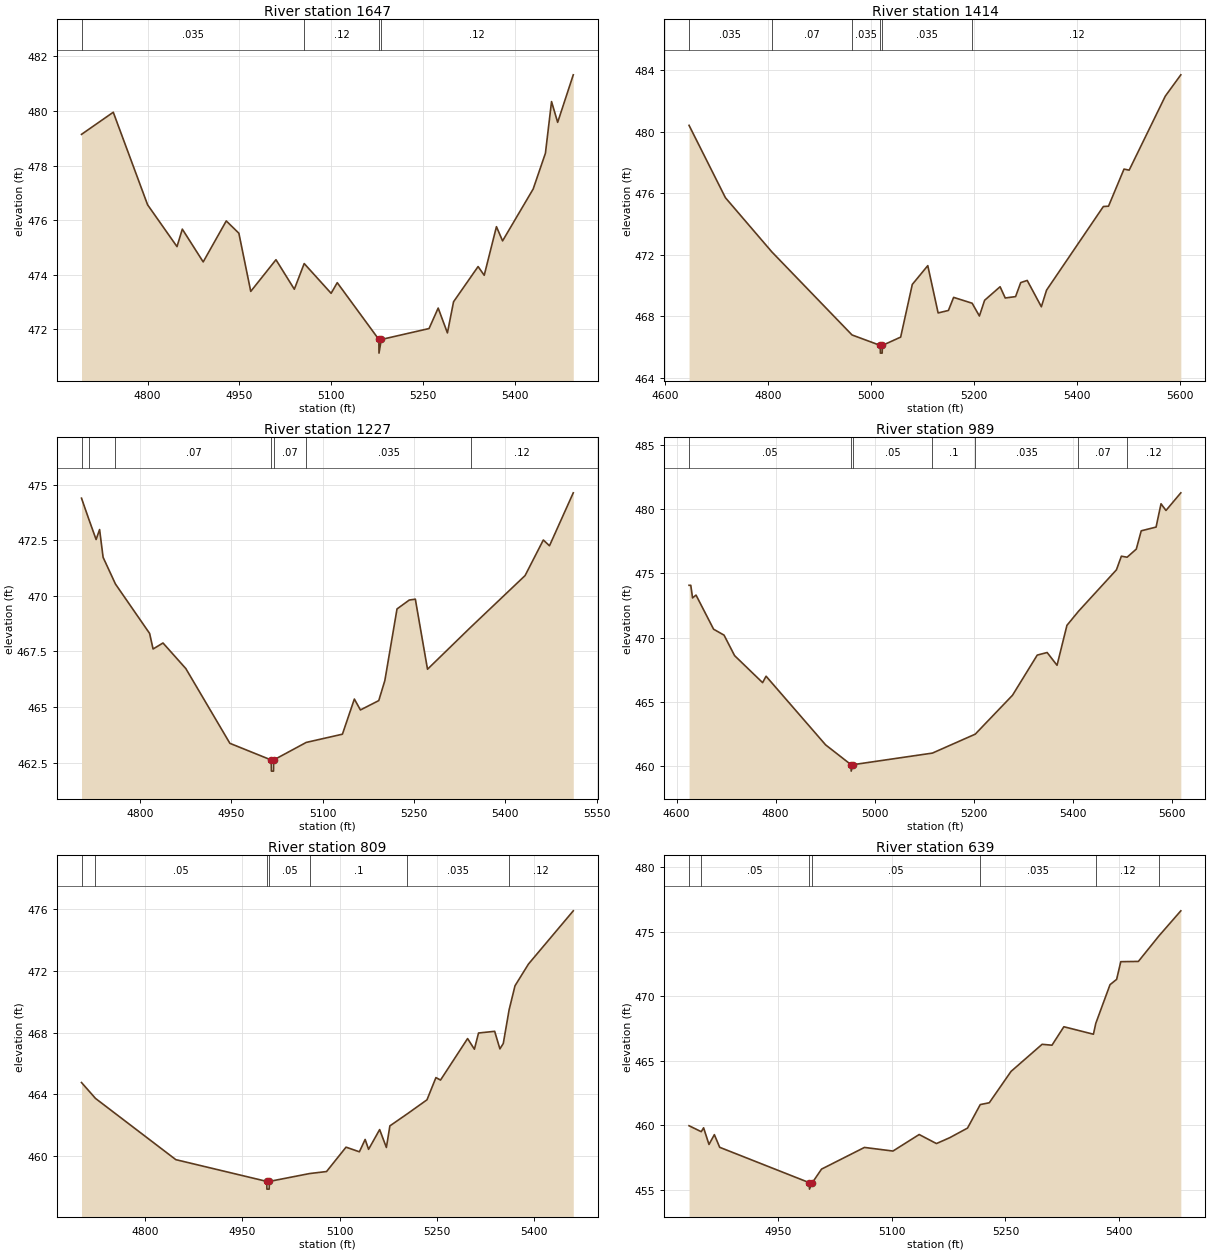
Type RM Length L Ch R = 1,1647,233,233,233
BEGIN DESCRIPTION:
H21177
END DESCRIPTION:
XS GIS Cut Line= 3
      2499545.83     13847125.55      2499608.77     13846852.11
      2499593.59     13846329.52
#Sta/Elev= 30
  4691.9  479.14  4743.8  479.95  4799.9  476.56  4847.9  475.03  4856.6  475.67
  4890.7  474.47  4928.4  475.97  4949.0  475.52  4968.4  473.39  5009.6  474.55
  5039.6  473.47  5055.7  474.41  5099.7  473.32  5109.7  473.71  5177.7  471.63
  5177.9  471.13  5181.7  471.63  5259.7  472.03  5274.6  472.78  5289.7  471.87
  5299.7  473.01  5339.8  474.30  5349.8  473.98  5369.8  475.76  5379.8  475.24
  5429.8  477.14  5449.8  478.45  5459.8  480.34  5469.8  479.58  5495.3  481.32
#Mann=4,-1,0
  4691.9   0.035       0  5055.7    0.12       0  5177.7   0.035       0
  5181.7    0.12       0
Bank Sta=5177.7,5181.7
Exp/Cntr=0.3,0.1

Type RM Length L Ch R = 1,1414,187,187,187
BEGIN DESCRIPTION:
StreamM015 2.0
END DESCRIPTION:
XS GIS Cut Line= 3
      2499575.03     13847124.97      2499825.00     13846875.00
      2499775.00     13846274.99
#Sta/Elev= 30
  4646.5  480.41  4717.2  475.71  4807.2  472.20  4963.2  466.80  5018.1  466.12
  5018.3  465.62  5021.8  465.62  5022.1  466.12  5057.7  466.66  5080.3  470.08
  5110.4  471.30  5130.5  468.23  5150.5  468.39  5160.6  469.24  5196.6  468.86
  5210.7  468.03  5220.8  469.05  5250.9  469.93  5260.9  469.20  5281.0  469.29
  5291.0  470.20  5303.6  470.34  5331.1  468.63  5341.2  469.71  5451.6  475.14
  5461.6  475.16  5491.7  477.57  5501.7  477.50  5572.0  482.31  5602.1  483.69
#Mann=6,-1,0
  4646.5   0.035       0  4807.2    0.07       0  4963.2   0.035       0
  5018.1   0.035       0  5022.1   0.035       0  5196.6    0.12       0
Bank Sta=5018.1,5022.1
Exp/Cntr=0.3,0.1

Type RM Length L Ch R = 1,1227,238,238,238
BEGIN DESCRIPTION:
H21176
END DESCRIPTION:
XS GIS Cut Line= 3
      2499856.15     13847186.34      2500003.73     13846908.54
      2500031.94     13846415.91
#Sta/Elev= 30
  4703.8  474.39  4715.5  473.47  4727.8  472.53  4733.5  472.98  4739.3  471.73
  4759.6  470.53  4815.7  468.31  4821.4  467.61  4837.7  467.88  4875.2  466.73
  4947.6  463.37  5015.5  462.62  5015.8  462.12  5019.3  462.12  5019.5  462.62
  5073.0  463.41  5132.5  463.78  5152.1  465.36  5162.1  464.87  5192.2  465.29
  5202.2  466.19  5222.2  469.41  5242.3  469.81  5252.3  469.85  5272.3  466.70
  5343.3  468.59  5432.6  470.91  5462.6  472.51  5472.7  472.25  5511.8  474.63
#Mann=7,-1,0
  4703.8    0.07       0  4715.5    0.05       0  4759.6    0.07       0
  5015.5    0.05       0  5019.5    0.07       0  5073.0   0.035       0
  5343.3    0.12       0
Bank Sta=5015.5,5019.5
Exp/Cntr=0.3,0.1

Type RM Length L Ch R = 1,989,180,180,180
BEGIN DESCRIPTION:
StreamM015 1.0
END DESCRIPTION:
XS GIS Cut Line= 3
      2499974.97     13847225.03      2500205.56     13846986.66
      2500225.00     13846325.00
#Sta/Elev= 30
  4625.2  474.07  4628.7  474.07  4632.3  473.09  4639.3  473.31  4674.8  470.66
  4695.9  470.20  4717.2  468.61  4773.8  466.51  4780.8  467.01  4901.1  461.68
  4952.5  460.14  4952.8  459.64  4956.5  460.14  5116.9  461.04  5203.4  462.51
  5278.7  465.53  5328.7  468.65  5348.7  468.85  5368.7  467.86  5388.7  470.96
  5412.0  472.05  5488.7  475.27  5498.7  476.33  5510.3  476.25  5528.8  476.88
  5538.8  478.30  5568.8  478.59  5578.8  480.40  5588.8  479.88  5618.8  481.25
#Mann=7,-1,0
  4625.2    0.05       0  4952.5    0.05       0  4956.5    0.05       0
  5116.9     0.1       0  5203.4   0.035       0  5412.0    0.07       0
  5510.3    0.12       0
Bank Sta=4952.5,4956.5
Exp/Cntr=0.3,0.1

Type RM Length L Ch R = 1,809,170,170,170
BEGIN DESCRIPTION:
H21175
END DESCRIPTION:
XS GIS Cut Line= 4
      2500229.40     13847140.78      2500370.49     13846925.90
      2500357.47     13846767.48      2500258.00     13846438.81
#Sta/Elev= 30
  4701.5  464.76  4723.1  463.73  4847.2  459.76  4987.6  458.35  4987.8  457.85
  4991.3  457.85  4991.6  458.35  5053.8  458.86  5079.9  458.99  5110.0  460.57
  5130.6  460.27  5139.5  461.07  5144.8  460.43  5161.9  461.71  5172.3  460.55
  5177.7  461.95  5203.9  462.71  5235.0  463.64  5248.8  465.08  5255.9  464.92
  5297.7  467.61  5308.2  466.92  5314.6  467.97  5339.5  468.08  5347.6  466.94
  5352.8  467.29  5361.8  469.47  5370.9  471.03  5391.7  472.44  5460.9  475.89
#Mann=7,-1,0
  4701.5    0.12       0  4723.1    0.05       0  4987.6    0.05       0
  4991.6    0.05       0  5053.8     0.1       0  5203.9   0.035       0
  5361.8    0.12       0
Bank Sta=4987.6,4991.6
Exp/Cntr=0.3,0.1

Type RM Length L Ch R = 1,639,0,0,0
BEGIN DESCRIPTION:
H21174
END DESCRIPTION:
XS GIS Cut Line= 3
      2500637.42     13846949.77      2500457.29     13846769.65
      2500296.84     13846409.72
#Sta/Elev= 30
  4832.6  459.96  4848.7  459.50  4851.8  459.80  4858.9  458.51  4866.0  459.27
  4873.0  458.29  4991.2  455.55  4991.5  455.05  4995.2  455.55  5007.4  456.60
  5064.0  458.28  5101.6  458.00  5136.2  459.28  5159.0  458.58  5176.7  459.04
  5200.0  459.78  5216.8  461.60  5228.7  461.74  5257.4  464.17  5298.4  466.27
  5311.4  466.20  5327.1  467.63  5366.1  467.05  5369.2  467.89  5388.0  470.89
  5396.7  471.30  5402.2  472.67  5425.4  472.69  5452.7  474.68  5481.4  476.61
#Mann=7,-1,0
  4832.6    0.07       0  4848.7    0.05       0  4991.2    0.05       0
  4995.2    0.05       0  5216.8   0.035       0  5369.2    0.12       0
  5452.7    0.07       0
Bank Sta=4991.2,4995.2
Exp/Cntr=0.3,0.1

Chan Stop Cuts=-1