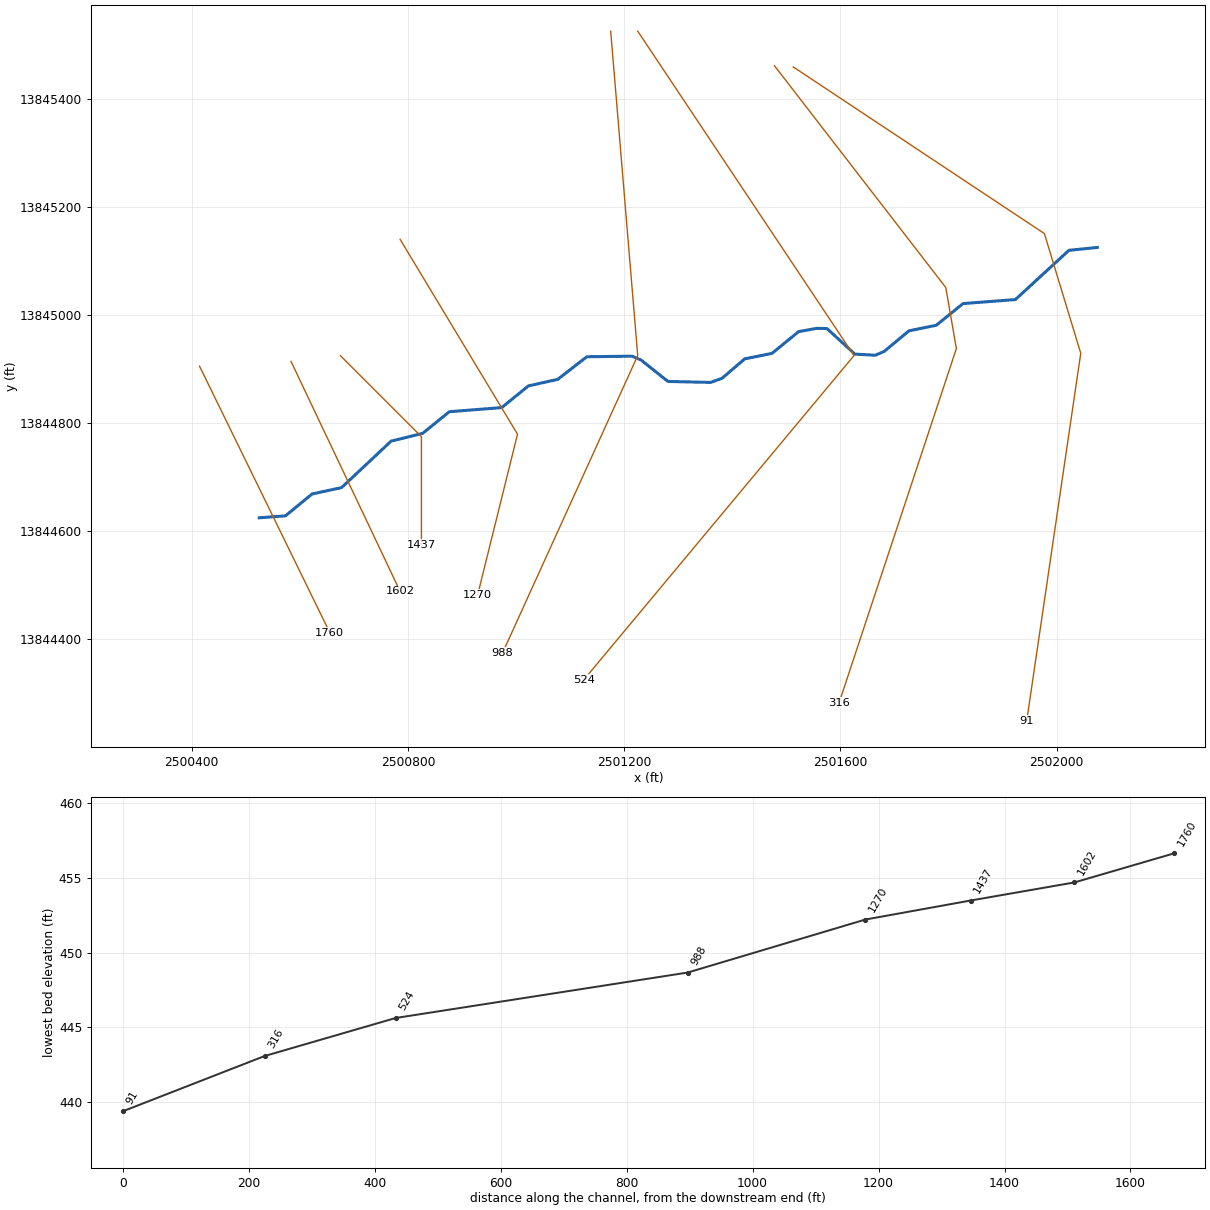
--- StreamM016.prj (project) ---

Proj Title=StreamM016 Base Level Engineering
Current Plan=p01
Default Exp/Contr=0.3,0.1
English Units
Geom File=g01
Flow File=f01
Plan File=p01
BEGIN DESCRIPTION:
StreamM016
END DESCRIPTION:

--- StreamM016.p01 (plan) ---

Plan Title=Multiple Run
Short Identifier=Multiple
Geom File=g01
Flow File=f01
Subcritical Flow
K Sum by GR= 0
Std Step Tol= 0.01
Critical Tol= 0.01
Num of Std Step Trials= 20
Max Error Tol= 0.3
Flow Tol Ratio= 0.001
Split Flow NTrial= 30
Split Flow Tol= 0.02
Split Flow Ratio= 0.02
Log Output Level= 0
Friction Slope Method= 1
Unsteady Friction Slope Method= 2
Unsteady Bridges Friction Slope Method= 1
Parabolic Critical Depth
Global Vel Dist=  1 , 1 , 1
Global Log Level= 0
CheckData=True
Encroach Param= -1, 0, 0, 0
BEGIN DESCRIPTION:
Multiple Run
END DESCRIPTION:

--- StreamM016.f01 (steady flow) ---

Flow Title=Multiple
Number of Profiles=7
Profile Names=10-year,25-year,50-year,1pct_min,100-year,1pct_plu,500-year
River Rch & RM= StreamM016,Reach-1,1760
     202     302     385     240     478     954     726
River Rch & RM= StreamM016,Reach-1,524
     319     493     644     409     816    1629    1295
Boundary for River Rch & Prof#=StreamM016,Reach-1,1
Up Type=0
Dn Type=3
Dn Slope=0.005
Boundary for River Rch & Prof#=StreamM016,Reach-1,2
Up Type=0
Dn Type=3
Dn Slope=0.005
Boundary for River Rch & Prof#=StreamM016,Reach-1,3
Up Type=0
Dn Type=3
Dn Slope=0.005
Boundary for River Rch & Prof#=StreamM016,Reach-1,4
Up Type=0
Dn Type=3
Dn Slope=0.005
Boundary for River Rch & Prof#=StreamM016,Reach-1,5
Up Type=0
Dn Type=3
Dn Slope=0.005
Boundary for River Rch & Prof#=StreamM016,Reach-1,6
Up Type=0
Dn Type=3
Dn Slope=0.005
Boundary for River Rch & Prof#=StreamM016,Reach-1,7
Up Type=0
Dn Type=3
Dn Slope=0.005

--- StreamM016.g01 (geometry) ---

Geom Title=Existing Conditions

River Reach=StreamM016,Reach-1
Reach XY= 30
      2500525.00     13844625.00      2500573.51     13844628.60
      2500622.76     13844669.03      2500677.30     13844680.83
      2500768.95     13844766.84      2500827.17     13844781.14
      2500876.58     13844821.17      2500973.42     13844828.83
      2501022.82     13844868.89      2501077.18     13844881.12
      2501130.97     13844922.86      2501214.45     13844923.89
      2501231.04     13844916.90      2501280.97     13844877.17
      2501359.73     13844875.37      2501381.05     13844883.04
      2501422.81     13844918.89      2501473.32     13844929.06
      2501522.64     13844969.32      2501556.08     13844975.42
      2501575.00     13844975.00      2501626.60     13844927.71
      2501664.38     13844925.66      2501680.97     13844932.78
      2501726.72     13844970.79      2501777.18     13844981.11
      2501826.59     13845021.17      2501923.50     13845028.61
      2502022.49     13845119.67      2502075.00     13845125.00

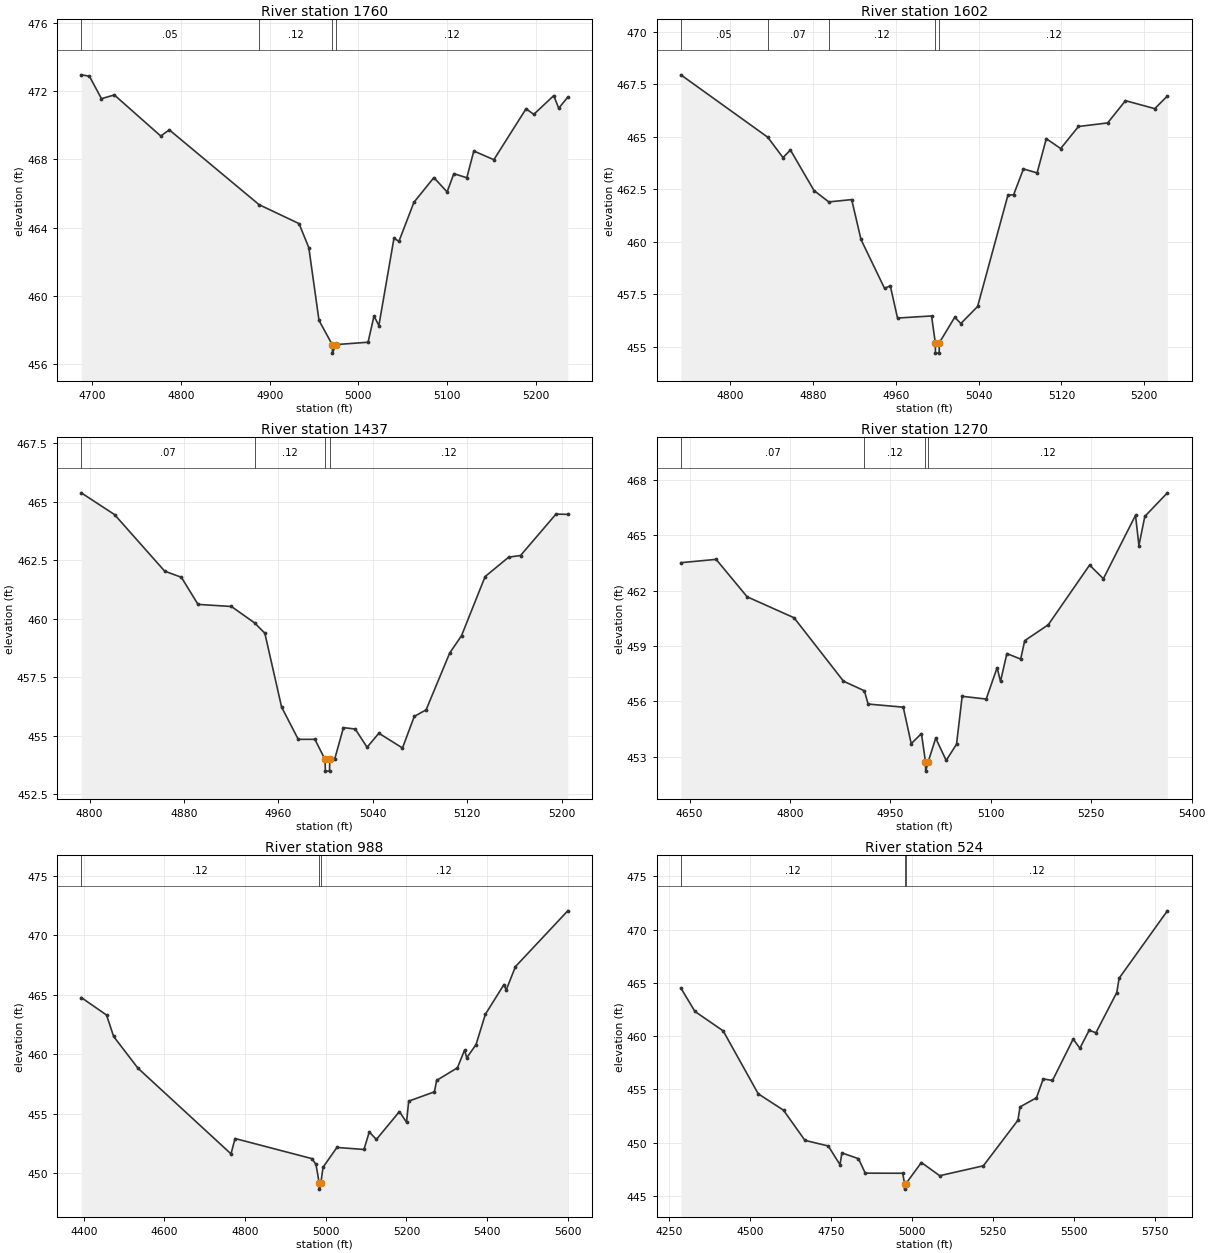
Type RM Length L Ch R = 1,1760,158,158,158
BEGIN DESCRIPTION:
H21182
END DESCRIPTION:
XS GIS Cut Line= 2
      2500414.57     13844905.45      2500655.47     13844412.79
#Sta/Elev= 30
  4687.6  472.96  4696.8  472.88  4710.4  471.56  4724.9  471.78  4777.2  469.37
  4786.9  469.73  4888.1  465.34  4933.1  464.23  4944.1  462.82  4955.6  458.55
  4970.5  457.13  4970.8  456.63  4974.5  457.13  5010.9  457.27  5017.6  458.81
  5023.1  458.25  5040.1  463.37  5045.7  463.19  5062.6  465.48  5085.1  466.93
  5100.0  466.09  5107.6  467.16  5122.2  466.92  5130.1  468.49  5152.7  467.98
  5189.0  470.97  5197.7  470.64  5220.2  471.74  5225.8  471.00  5236.0  471.65
#Mann=4,-1,0
  4687.6    0.05       0  4888.1    0.12       0  4970.5    0.05       0
  4974.5    0.12       0
Bank Sta=4970.5,4974.5
Exp/Cntr=0.3,0.1

Type RM Length L Ch R = 1,1602,165,165,165
BEGIN DESCRIPTION:
H21181
END DESCRIPTION:
XS GIS Cut Line= 2
      2500583.84     13844914.14      2500785.40     13844489.34
#Sta/Elev= 30
  4752.2  467.94  4836.2  464.97  4850.9  464.00  4858.1  464.36  4880.9  462.43
  4895.2  461.89  4917.3  462.00  4926.3  460.10  4949.1  457.77  4954.6  457.90
  4961.6  456.36  4994.5  456.46  4998.1  455.19  4998.3  454.69  5001.8  454.69
  5002.1  455.19  5016.9  456.40  5022.8  456.10  5039.0  456.91  5068.3  462.21
  5073.8  462.23  5083.3  463.46  5096.5  463.27  5105.4  464.90  5119.3  464.43
  5136.5  465.48  5164.7  465.65  5181.9  466.71  5210.2  466.33  5222.4  466.93
#Mann=5,-1,0
  4752.2    0.05       0  4836.2    0.07       0  4895.2    0.12       0
  4998.1    0.05       0  5002.1    0.12       0
Bank Sta=4998.1,5002.1
Exp/Cntr=0.3,0.1

Type RM Length L Ch R = 1,1437,167,167,167
BEGIN DESCRIPTION:
StreamM016 3.0
END DESCRIPTION:
XS GIS Cut Line= 3
      2500675.03     13844924.97      2500825.00     13844775.00
      2500825.00     13844574.98
#Sta/Elev= 30
  4793.0  465.38  4821.2  464.45  4863.7  462.03  4877.8  461.77  4891.9  460.61
  4920.2  460.52  4939.8  459.82  4948.5  459.38  4962.7  456.22  4976.8  454.84
  4990.9  454.84  4999.5  453.98  4999.8  453.48  5003.3  453.48  5003.5  453.98
  5007.6  453.98  5015.1  455.34  5025.1  455.28  5035.1  454.50  5045.1  455.10
  5065.1  454.47  5075.1  455.82  5085.1  456.10  5105.1  458.53  5115.1  459.27
  5135.1  461.80  5155.1  462.63  5165.1  462.70  5195.1  464.47  5205.1  464.46
#Mann=4,-1,0
  4793.0    0.07       0  4939.8    0.12       0  4999.5    0.05       0
  5003.5    0.12       0
Bank Sta=4999.5,5003.5
Exp/Cntr=0.3,0.1

Type RM Length L Ch R = 1,1270,282,282,282
BEGIN DESCRIPTION:
H21180
END DESCRIPTION:
XS GIS Cut Line= 3
      2500785.66     13845139.82      2501002.69     13844779.55
      2500928.91     13844482.26
#Sta/Elev= 30
  4636.8  463.52  4689.5  463.70  4735.8  461.67  4806.0  460.53  4879.8  457.09
  4911.0  456.57  4916.6  455.85  4969.1  455.68  4981.0  453.70  4996.3  454.25
  5002.3  452.71  5002.6  452.21  5006.3  452.71  5017.6  454.00  5033.2  452.79
  5048.7  453.67  5057.1  456.27  5093.0  456.12  5109.3  457.82  5114.4  457.08
  5123.9  458.59  5144.5  458.29  5150.6  459.29  5185.7  460.15  5247.5  463.39
  5268.1  462.65  5316.1  466.09  5321.2  464.45  5330.0  466.03  5363.7  467.31
#Mann=4,-1,0
  4636.8    0.07       0  4911.0    0.12       0  5002.3    0.05       0
  5006.3    0.12       0
Bank Sta=5002.3,5006.3
Exp/Cntr=0.3,0.1

Type RM Length L Ch R = 1,988,464,464,464
BEGIN DESCRIPTION:
StreamM016 2.0
END DESCRIPTION:
XS GIS Cut Line= 3
      2501175.00     13845524.98      2501225.00     13844925.00
      2500975.00     13844375.01
#Sta/Elev= 30
  4393.9  464.76  4456.6  463.29  4474.2  461.49  4534.4  458.83  4765.2  451.63
  4775.2  452.92  4965.9  451.23  4975.9  450.74  4983.9  449.17  4984.2  448.67
  4987.9  449.17  4993.4  450.51  5027.8  452.17  5094.8  452.00  5108.0  453.47
  5125.6  452.84  5182.7  455.18  5200.3  454.29  5205.8  456.06  5269.5  456.84
  5275.0  457.80  5326.6  458.86  5344.2  460.35  5349.7  459.70  5372.7  460.81
  5395.8  463.35  5441.9  465.85  5447.4  465.39  5470.5  467.36  5600.1  472.04
#Mann=3,-1,0
  4393.9    0.12       0  4983.9    0.05       0  4987.9    0.12       0
Bank Sta=4983.9,4987.9
Exp/Cntr=0.3,0.1

Type RM Length L Ch R = 1,524,208,208,208
BEGIN DESCRIPTION:
StreamM016 1.0
END DESCRIPTION:
XS GIS Cut Line= 3
      2501224.99     13845525.01      2501625.00     13844925.00
      2501125.03     13844325.04
#Sta/Elev= 30
  4285.3  464.51  4328.9  462.31  4416.0  460.49  4524.2  454.58  4602.3  453.04
  4668.4  450.21  4740.5  449.68  4776.6  447.93  4782.6  449.03  4833.7  448.49
  4854.7  447.13  4970.4  447.12  4975.9  446.13  4976.1  445.63  4979.9  446.13
  5027.9  448.13  5084.5  446.89  5219.3  447.82  5326.0  452.10  5332.5  453.35
  5383.3  454.21  5404.1  455.98  5432.7  455.83  5496.5  459.72  5517.3  458.86
  5546.0  460.55  5566.8  460.31  5631.2  464.09  5638.4  465.43  5787.4  471.76
#Mann=3,-1,0
  4285.3    0.12       0  4975.9    0.05       0  4979.9    0.12       0
Bank Sta=4975.9,4979.9
Exp/Cntr=0.3,0.1

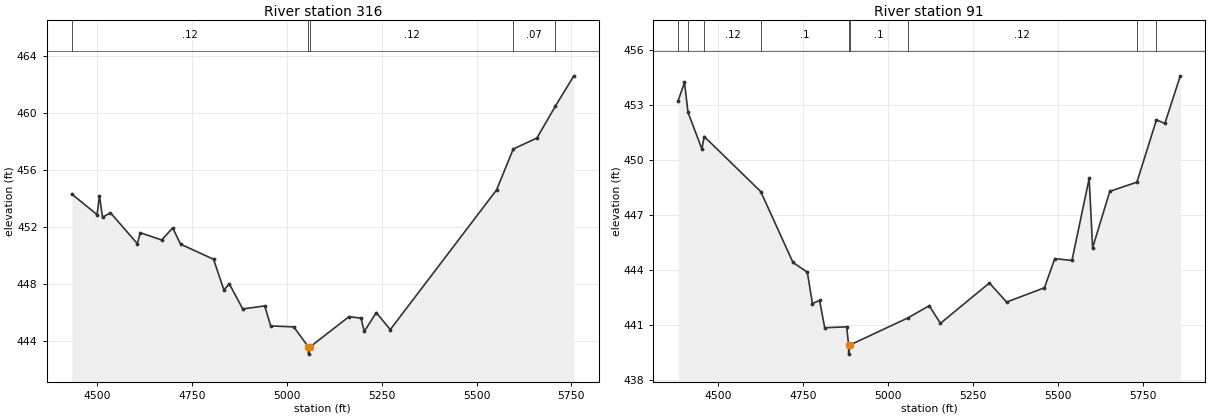
Type RM Length L Ch R = 1,316,225,225,225
BEGIN DESCRIPTION:
H21179
END DESCRIPTION:
XS GIS Cut Line= 4
      2501477.92     13845461.02      2501794.79     13845050.82
      2501814.32     13844937.97      2501597.32     13844282.62
#Sta/Elev= 30
  4433.2  454.31  4499.8  452.87  4506.2  454.18  4514.3  452.68  4535.2  453.00
  4605.8  450.84  4614.0  451.60  4670.1  451.09  4699.1  451.94  4719.9  450.80
  4806.9  449.74  4834.0  447.60  4848.5  448.01  4883.8  446.26  4941.8  446.47
  4957.4  445.07  5018.3  445.00  5056.9  443.59  5057.2  443.09  5060.9  443.59
  5164.0  445.72  5195.6  445.61  5204.0  444.68  5235.7  446.00  5272.6  444.81
  5552.7  454.60  5596.7  457.47  5659.1  458.24  5707.2  460.45  5756.4  462.60
#Mann=5,-1,0
  4433.2    0.12       0  5056.9    0.05       0  5060.9    0.12       0
  5596.7    0.07       0  5707.2    0.12       0
Bank Sta=5056.9,5060.9
Exp/Cntr=0.3,0.1

Type RM Length L Ch R = 1,91,0,0,0
BEGIN DESCRIPTION:
H21178
END DESCRIPTION:
XS GIS Cut Line= 4
      2501512.66     13845458.82      2501977.08     13845150.65
      2502044.36     13844929.29      2501944.53     13844250.01
#Sta/Elev= 30
  4383.9  453.23  4402.3  454.22  4412.6  452.59  4453.4  450.59  4460.1  451.27
  4626.2  448.27  4721.1  444.40  4763.2  443.87  4778.2  442.16  4799.2  442.33
  4814.3  440.84  4878.8  440.89  4884.5  439.90  4884.7  439.40  4888.5  439.90
  5058.1  441.37  5121.4  442.04  5154.3  441.08  5298.2  443.28  5348.8  442.24
  5460.0  443.02  5490.3  444.61  5540.8  444.51  5591.4  448.98  5601.5  445.20
  5652.0  448.28  5731.7  448.78  5789.1  452.18  5813.7  451.98  5859.2  454.58
#Mann=9,-1,0
  4383.9    0.12       0  4412.6     0.1       0  4460.1    0.12       0
  4626.2     0.1       0  4884.5    0.05       0  4888.5     0.1       0
  5058.1    0.12       0  5731.7    0.07       0  5789.1    0.12       0
Bank Sta=4884.5,4888.5
Exp/Cntr=0.3,0.1

Chan Stop Cuts=-1