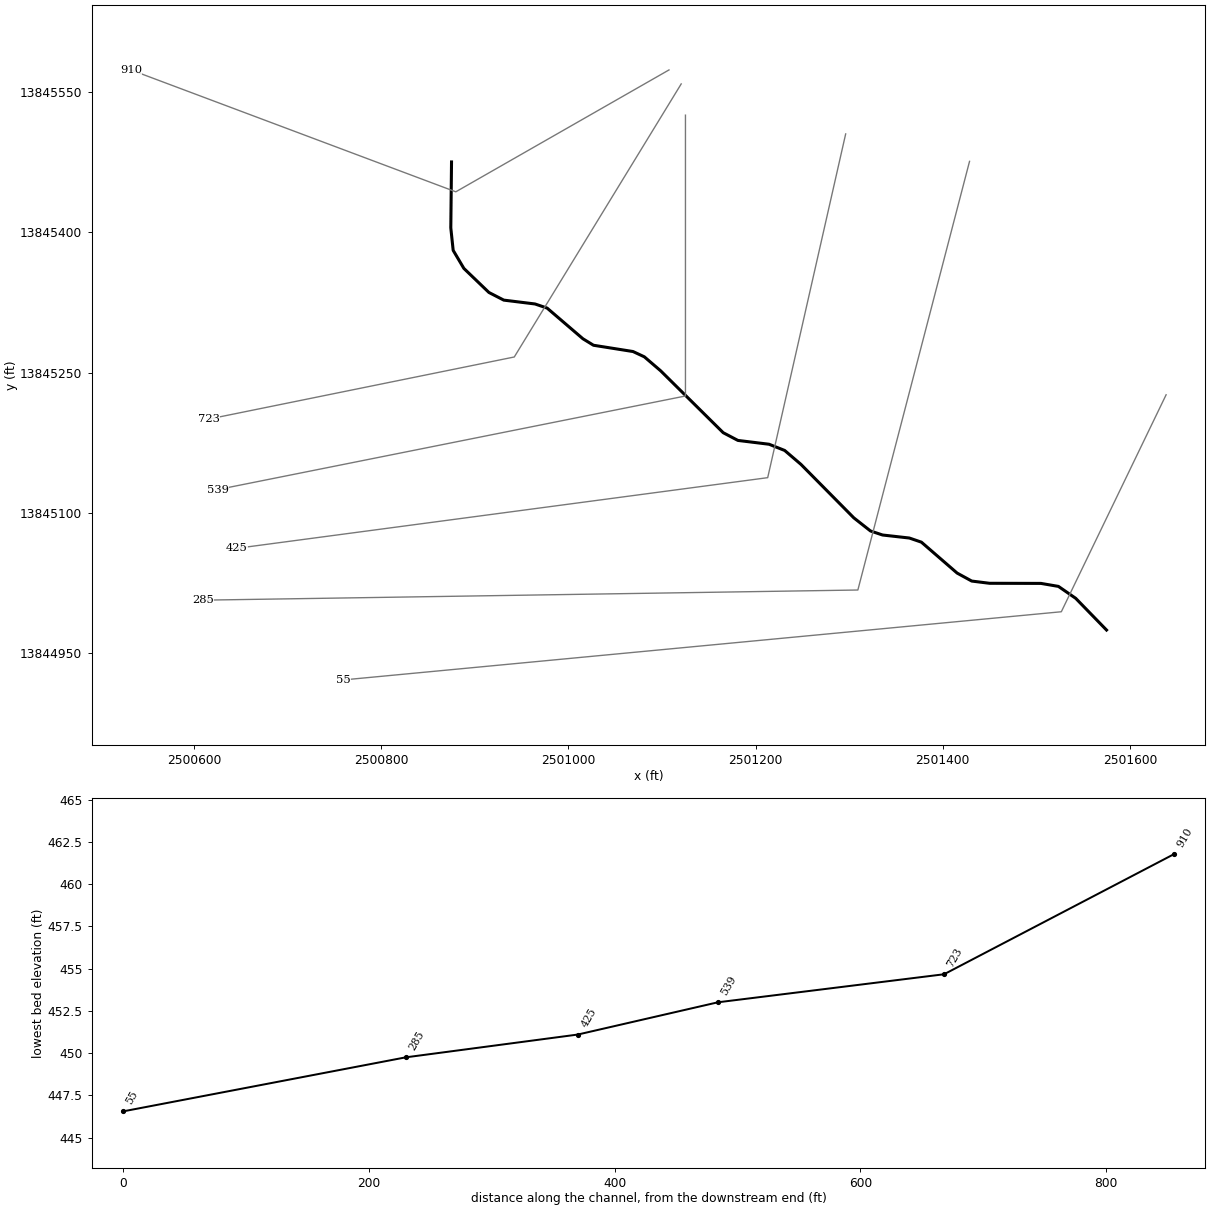
--- StreamM017.prj (project) ---

Proj Title=StreamM017 Base Level Engineering
Current Plan=p01
Default Exp/Contr=0.3,0.1
English Units
Geom File=g01
Flow File=f01
Plan File=p01
BEGIN DESCRIPTION:
StreamM017
END DESCRIPTION:

--- StreamM017.p01 (plan) ---

Plan Title=Multiple Run
Short Identifier=Multiple
Geom File=g01
Flow File=f01
Subcritical Flow
K Sum by GR= 0
Std Step Tol= 0.01
Critical Tol= 0.01
Num of Std Step Trials= 20
Max Error Tol= 0.3
Flow Tol Ratio= 0.001
Split Flow NTrial= 30
Split Flow Tol= 0.02
Split Flow Ratio= 0.02
Log Output Level= 0
Friction Slope Method= 1
Unsteady Friction Slope Method= 2
Unsteady Bridges Friction Slope Method= 1
Parabolic Critical Depth
Global Vel Dist=  1 , 1 , 1
Global Log Level= 0
CheckData=True
Encroach Param= -1, 0, 0, 0
BEGIN DESCRIPTION:
Multiple Run
END DESCRIPTION:

--- StreamM017.f01 (steady flow) ---

Flow Title=Multiple
Number of Profiles=7
Profile Names=10-year,25-year,50-year,1pct_min,100-year,1pct_plu,500-year
River Rch & RM= StreamM017,Reach-1,910
     161     235     297     183     365     728     541
Boundary for River Rch & Prof#=StreamM017,Reach-1,1
Up Type=0
Dn Type=3
Dn Slope=0.005
Boundary for River Rch & Prof#=StreamM017,Reach-1,2
Up Type=0
Dn Type=3
Dn Slope=0.005
Boundary for River Rch & Prof#=StreamM017,Reach-1,3
Up Type=0
Dn Type=3
Dn Slope=0.005
Boundary for River Rch & Prof#=StreamM017,Reach-1,4
Up Type=0
Dn Type=3
Dn Slope=0.005
Boundary for River Rch & Prof#=StreamM017,Reach-1,5
Up Type=0
Dn Type=3
Dn Slope=0.005
Boundary for River Rch & Prof#=StreamM017,Reach-1,6
Up Type=0
Dn Type=3
Dn Slope=0.005
Boundary for River Rch & Prof#=StreamM017,Reach-1,7
Up Type=0
Dn Type=3
Dn Slope=0.005

--- StreamM017.g01 (geometry) ---

Geom Title=Existing Conditions

River Reach=StreamM017,Reach-1
Reach XY= 30
      2500875.00     13845475.00      2500874.22     13845404.60
      2500876.77     13845380.55      2500888.19     13845361.28
      2500914.95     13845335.59      2500930.84     13845327.41
      2500964.25     13845323.29      2500977.16     13845318.89
      2501015.45     13845286.10      2501026.73     13845279.19
      2501068.96     13845272.49      2501081.05     13845266.84
      2501098.45     13845251.94      2501165.33     13845185.80
      2501181.05     13845177.54      2501214.36     13845173.45
      2501231.04     13845166.82      2501248.44     13845151.94
      2501304.93     13845094.82      2501322.71     13845080.84
      2501335.62     13845076.51      2501364.29     13845073.28
      2501377.17     13845068.86      2501415.34     13845035.83
      2501430.95     13845027.30      2501449.97     13845024.93
      2501504.92     13845024.81      2501523.60     13845021.61
      2501542.05     13845008.88      2501575.00     13844975.00

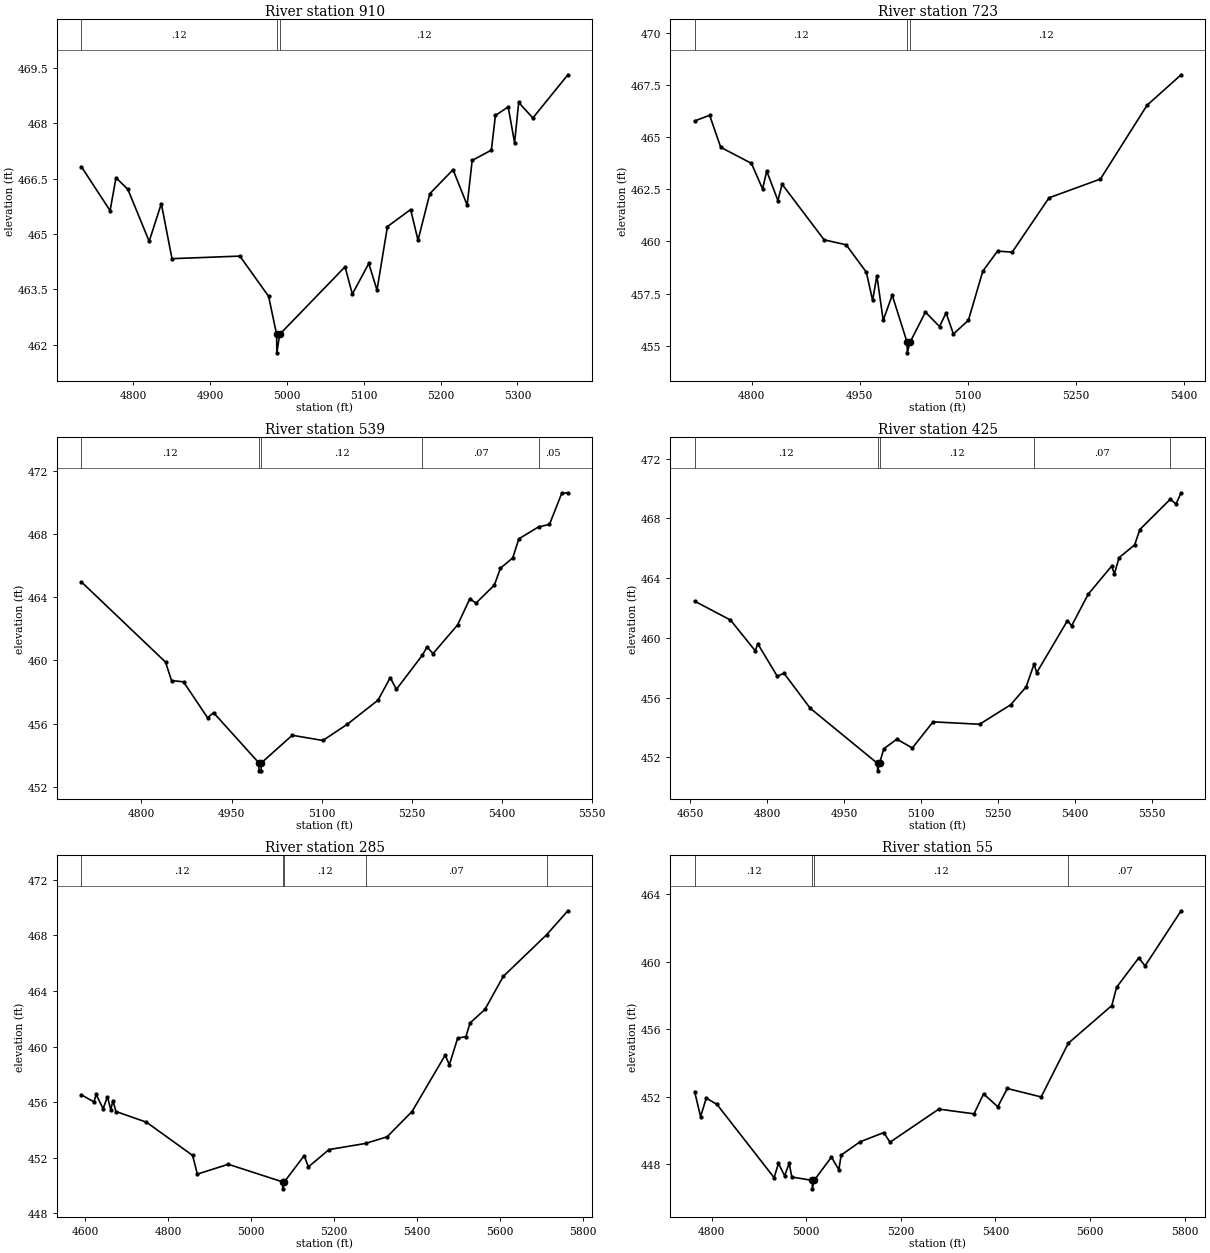
Type RM Length L Ch R = 1,910,187,187,187
BEGIN DESCRIPTION:
MXS18475
END DESCRIPTION:
XS GIS Cut Line= 3
      2501107.40     13845573.29      2500879.56     13845443.10
      2500532.29     13845573.32
#Sta/Elev= 30
  4732.3  466.82  4769.6  465.63  4777.3  466.52  4792.7  466.21  4820.5  464.80
  4836.3  465.82  4850.2  464.33  4938.6  464.40  4976.0  463.31  4986.4  462.28
  4986.7  461.78  4990.4  462.28  5075.5  464.11  5085.0  463.37  5106.4  464.20
  5117.1  463.48  5130.7  465.20  5160.9  465.66  5170.5  464.83  5185.9  466.09
  5216.1  466.74  5234.5  465.78  5241.0  466.99  5266.0  467.27  5271.3  468.21
  5287.9  468.44  5296.2  467.47  5301.6  468.56  5320.0  468.14  5365.6  469.31
#Mann=3,-1,0
  4732.3    0.12       0  4986.4    0.05       0  4990.4    0.12       0
Bank Sta=4986.4,4990.4
Exp/Cntr=0.3,0.1

Type RM Length L Ch R = 1,723,184,184,184
BEGIN DESCRIPTION:
H21185
END DESCRIPTION:
XS GIS Cut Line= 3
      2501120.45     13845558.35      2500942.06     13845266.67
      2500615.24     13845200.26
#Sta/Elev= 30
  4720.7  465.77  4741.5  466.04  4756.9  464.51  4799.5  463.74  4815.0  462.52
  4820.8  463.37  4836.3  461.96  4842.1  462.74  4900.5  460.08  4931.1  459.84
  4959.1  458.53  4967.8  457.18  4973.7  458.36  4982.5  456.23  4995.0  457.43
  5015.7  455.17  5015.9  454.67  5019.7  455.17  5041.1  456.62  5060.7  455.93
  5069.8  456.58  5080.0  455.57  5100.8  456.23  5120.8  458.58  5141.2  459.54
  5161.6  459.49  5212.7  462.09  5284.1  462.99  5348.8  466.52  5396.1  467.98
#Mann=3,-1,0
  4720.7    0.12       0  5015.7    0.05       0  5019.7    0.12       0
Bank Sta=5015.7,5019.7
Exp/Cntr=0.3,0.1

Type RM Length L Ch R = 1,539,114,114,114
BEGIN DESCRIPTION:
StreamM017 1.0
END DESCRIPTION:
XS GIS Cut Line= 3
      2501125.00     13845524.99      2501125.00     13845225.00
      2500624.99     13845125.00
#Sta/Elev= 30
  4700.0  464.96  4840.0  459.89  4850.0  458.72  4870.0  458.64  4910.0  456.37
  4920.0  456.69  4995.5  453.51  4995.7  453.01  4999.2  453.01  4999.5  453.51
  5051.0  455.26  5102.0  454.93  5142.8  455.96  5193.8  457.48  5214.2  458.91
  5224.3  458.16  5267.7  460.33  5275.3  460.84  5285.5  460.43  5326.3  462.24
  5346.7  463.90  5356.9  463.62  5387.5  464.76  5397.7  465.83  5418.1  466.48
  5428.3  467.69  5461.0  468.44  5479.3  468.60  5499.7  470.57  5509.9  470.60
#Mann=5,-1,0
  4700.0    0.12       0  4995.5    0.05       0  4999.5    0.12       0
  5267.7    0.07       0  5461.0    0.05       0
Bank Sta=4995.5,4999.5
Exp/Cntr=0.3,0.1

Type RM Length L Ch R = 1,425,140,140,140
BEGIN DESCRIPTION:
H21184
END DESCRIPTION:
XS GIS Cut Line= 3
      2501296.22     13845504.93      2501212.89     13845137.76
      2500645.20     13845062.24
#Sta/Elev= 30
  4658.5  462.46  4728.4  461.20  4776.7  459.14  4781.8  459.60  4819.8  457.43
  4832.8  457.64  4884.0  455.29  5015.3  451.60  5015.6  451.10  5019.3  451.60
  5027.6  452.58  5053.1  453.22  5083.3  452.63  5123.7  454.38  5214.5  454.22
  5275.0  455.52  5305.3  456.72  5320.8  458.25  5325.9  457.67  5386.0  461.16
  5394.1  460.81  5426.3  462.92  5472.4  464.82  5477.4  464.28  5486.8  465.38
  5517.1  466.23  5527.2  467.26  5586.6  469.29  5597.8  468.97  5607.7  469.72
#Mann=5,-1,0
  4658.5    0.12       0  5015.3    0.05       0  5019.3    0.12       0
  5320.8    0.07       0  5586.6    0.05       0
Bank Sta=5015.3,5019.3
Exp/Cntr=0.3,0.1

Type RM Length L Ch R = 1,285,230,230,230
BEGIN DESCRIPTION:
MXS18474
END DESCRIPTION:
XS GIS Cut Line= 3
      2501428.60     13845475.64      2501309.25     13845017.75
      2500609.11     13845006.91
#Sta/Elev= 30
  4590.7  456.52  4621.0  456.01  4626.2  456.55  4643.0  455.52  4653.4  456.38
  4661.5  455.46  4666.6  456.10  4674.0  455.32  4747.6  454.55  4858.8  452.16
  4870.4  450.81  4944.9  451.52  5076.1  450.25  5076.4  449.75  5080.1  450.25
  5128.1  452.14  5138.1  451.33  5188.1  452.58  5276.1  453.02  5328.2  453.50
  5388.2  455.32  5468.2  459.38  5478.2  458.68  5498.2  460.60  5518.2  460.72
  5528.2  461.70  5564.0  462.67  5608.2  465.05  5712.7  468.05  5764.1  469.78
#Mann=5,-1,0
  4590.7    0.12       0  5076.1    0.05       0  5080.1    0.12       0
  5276.1    0.07       0  5712.7    0.05       0
Bank Sta=5076.1,5080.1
Exp/Cntr=0.3,0.1

Type RM Length L Ch R = 1,55,0,0,0
BEGIN DESCRIPTION:
H21183
END DESCRIPTION:
XS GIS Cut Line= 3
      2501638.67     13845226.29      2501526.69     13844994.53
      2500759.24     13844921.69
#Sta/Elev= 30
  4764.2  452.30  4776.7  450.83  4788.8  451.92  4811.4  451.55  4932.2  447.21
  4941.4  448.06  4954.4  447.32  4964.0  448.06  4969.6  447.25  5012.8  447.05
  5013.0  446.55  5016.8  447.05  5053.4  448.43  5069.0  447.68  5074.0  448.55
  5113.7  449.33  5163.9  449.88  5177.2  449.31  5280.3  451.27  5354.8  450.99
  5374.9  452.17  5405.0  451.41  5425.1  452.49  5496.7  451.99  5554.1  455.17
  5646.1  457.40  5656.1  458.48  5702.9  460.22  5716.4  459.75  5792.5  463.01
#Mann=4,-1,0
  4764.2    0.12       0  5012.8    0.05       0  5016.8    0.12       0
  5554.1    0.07       0
Bank Sta=5012.8,5016.8
Exp/Cntr=0.3,0.1

Chan Stop Cuts=-1