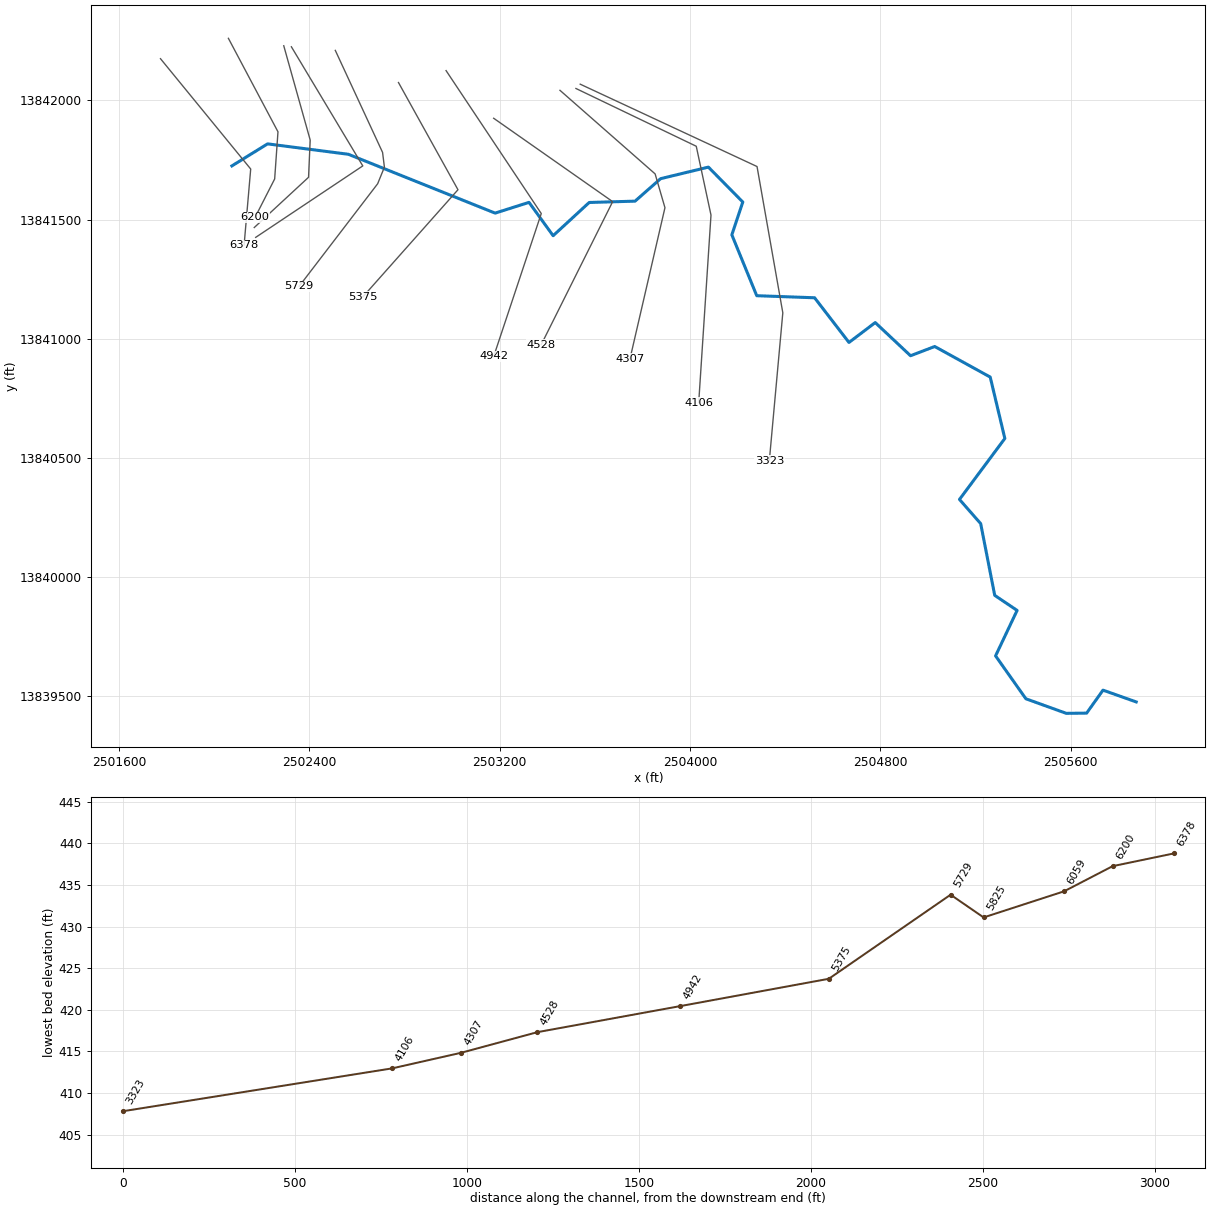
--- StreamM018.prj (project) ---

Proj Title=StreamM018 Base Level Engineering
Current Plan=p01
Default Exp/Contr=0.3,0.1
English Units
Geom File=g01
Flow File=f01
Plan File=p01
BEGIN DESCRIPTION:
StreamM018
END DESCRIPTION:

--- StreamM018.p01 (plan) ---

Plan Title=Multiple Run
Short Identifier=Multiple
Geom File=g01
Flow File=f01
Subcritical Flow
K Sum by GR= 0
Std Step Tol= 0.01
Critical Tol= 0.01
Num of Std Step Trials= 20
Max Error Tol= 0.3
Flow Tol Ratio= 0.001
Split Flow NTrial= 30
Split Flow Tol= 0.02
Split Flow Ratio= 0.02
Log Output Level= 0
Friction Slope Method= 1
Unsteady Friction Slope Method= 2
Unsteady Bridges Friction Slope Method= 1
Parabolic Critical Depth
Global Vel Dist=  1 , 1 , 1
Global Log Level= 0
CheckData=True
Encroach Param= -1, 0, 0, 0
BEGIN DESCRIPTION:
Multiple Run
END DESCRIPTION:

--- StreamM018.f01 (steady flow) ---

Flow Title=Multiple
Number of Profiles=7
Profile Names=10-year,25-year,50-year,1pct_min,100-year,1pct_plu,500-year
River Rch & RM= StreamM018,Reach-1,6378
     288     436     561     352     702    1400    1081
Boundary for River Rch & Prof#=StreamM018,Reach-1,1
Up Type=0
Dn Type=3
Dn Slope=0.005
Boundary for River Rch & Prof#=StreamM018,Reach-1,2
Up Type=0
Dn Type=3
Dn Slope=0.005
Boundary for River Rch & Prof#=StreamM018,Reach-1,3
Up Type=0
Dn Type=3
Dn Slope=0.005
Boundary for River Rch & Prof#=StreamM018,Reach-1,4
Up Type=0
Dn Type=3
Dn Slope=0.005
Boundary for River Rch & Prof#=StreamM018,Reach-1,5
Up Type=0
Dn Type=3
Dn Slope=0.005
Boundary for River Rch & Prof#=StreamM018,Reach-1,6
Up Type=0
Dn Type=3
Dn Slope=0.005
Boundary for River Rch & Prof#=StreamM018,Reach-1,7
Up Type=0
Dn Type=3
Dn Slope=0.005

--- StreamM018.g01 (geometry) ---

Geom Title=Existing Conditions

River Reach=StreamM018,Reach-1
Reach XY= 30
      2502075.00     13841725.00      2502224.99     13841817.49
      2502564.50     13841773.80      2503181.11     13841526.80
      2503323.58     13841571.96      2503424.79     13841431.98
      2503576.46     13841571.46      2503769.14     13841577.07
      2503876.50     13841671.38      2504077.30     13841719.91
      2504221.87     13841573.37      2504175.77     13841435.69
      2504280.41     13841180.17      2504523.55     13841171.47
      2504668.05     13840983.85      2504778.33     13841067.39
      2504926.65     13840928.16      2505028.31     13840966.93
      2505261.53     13840838.57      2505322.95     13840580.86
      2505132.30     13840324.92      2505221.43     13840223.53
      2505280.46     13839922.34      2505374.47     13839859.10
      2505283.98     13839668.34      2505411.35     13839488.26
      2505581.06     13839427.13      2505666.65     13839428.00
      2505735.47     13839524.48      2505875.00     13839475.00

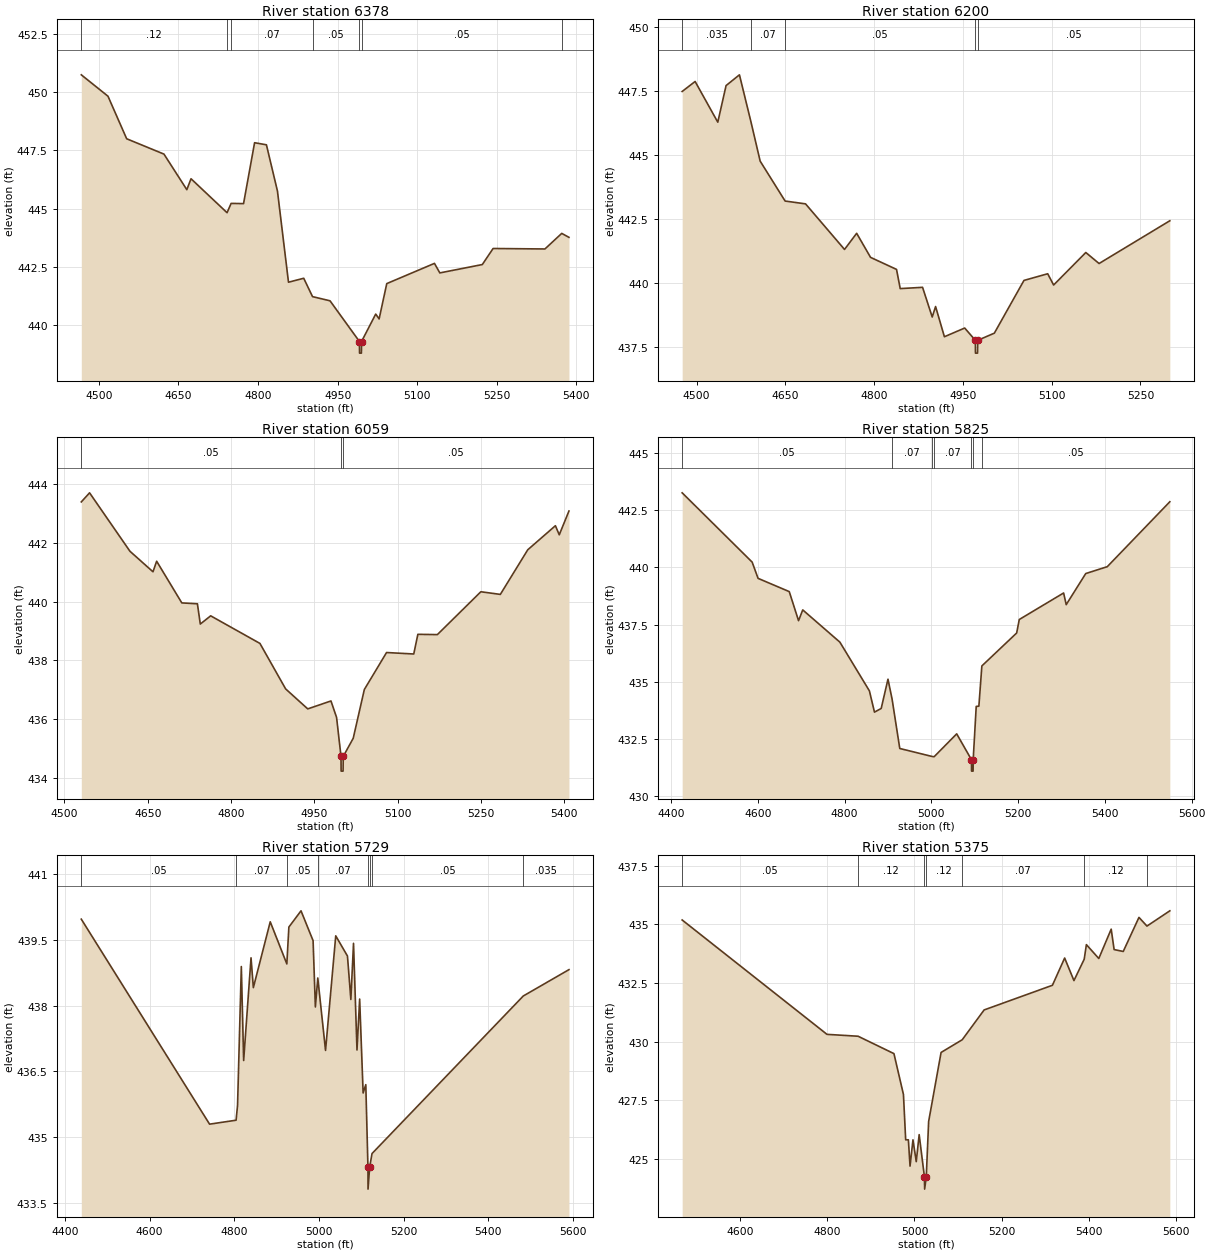
Type RM Length L Ch R = 1,6378,178,178,178
BEGIN DESCRIPTION:
StreamM018 5.0
END DESCRIPTION:
XS GIS Cut Line= 3
      2501774.97     13842175.03      2502154.05     13841711.92
      2502126.28     13841392.50
#Sta/Elev= 30
  4466.9  450.75  4517.2  449.83  4552.4  448.00  4622.7  447.34  4665.8  445.81
  4673.7  446.28  4741.6  444.82  4749.3  445.22  4772.7  445.21  4793.5  447.83
  4815.8  447.74  4836.6  445.75  4857.4  441.83  4886.1  442.00  4902.7  441.21
  4935.7  441.03  4991.1  439.28  4991.3  438.78  4994.8  438.78  4995.1  439.28
  5021.8  440.46  5028.2  440.25  5042.6  441.77  5132.5  442.64  5142.6  442.23
  5222.7  442.59  5243.0  443.28  5340.7  443.26  5372.4  443.93  5386.0  443.76
#Mann=7,-1,0
  4466.9    0.12       0  4741.6   0.035       0  4749.3    0.07       0
  4902.7    0.05       0  4991.1    0.05       0  4995.1    0.05       0
  5372.4   0.035       0
Bank Sta=4991.1,4995.1
Exp/Cntr=0.3,0.1

Type RM Length L Ch R = 1,6200,141,141,141
BEGIN DESCRIPTION:
H21191
END DESCRIPTION:
XS GIS Cut Line= 4
      2502060.32     13842260.49      2502268.64     13841868.17
      2502254.75     13841670.26      2502172.16     13841508.52
#Sta/Elev= 30
  4475.5  447.47  4497.4  447.86  4535.7  446.27  4549.7  447.70  4572.3  448.12
  4591.8  446.28  4607.3  444.75  4649.5  443.19  4684.0  443.08  4749.9  441.30
  4770.4  441.93  4793.9  440.99  4837.8  440.52  4844.0  439.77  4881.8  439.82
  4898.1  438.66  4903.8  439.07  4918.7  437.89  4953.0  438.23  4971.0  437.75
  4971.2  437.25  4974.7  437.25  4975.0  437.75  5003.1  438.03  5053.2  440.09
  5093.3  440.35  5103.3  439.91  5157.7  441.18  5180.1  440.75  5299.7  442.42
#Mann=5,-1,0
  4475.5   0.035       0  4591.8    0.07       0  4649.5    0.05       0
  4971.0    0.05       0  4975.0    0.05       0
Bank Sta=4971,4975
Exp/Cntr=0.3,0.1

Type RM Length L Ch R = 1,6059,234,234,234
BEGIN DESCRIPTION:
H21190
END DESCRIPTION:
XS GIS Cut Line= 4
      2502292.94     13842229.31      2502404.05     13841833.45
      2502397.11     13841677.20      2502168.99     13841466.36
#Sta/Elev= 30
  4530.3  443.40  4545.2  443.71  4617.9  441.72  4659.4  441.02  4666.0  441.38
  4711.3  439.96  4739.4  439.93  4744.6  439.24  4763.3  439.52  4852.0  438.58
  4898.3  437.03  4938.1  436.35  4979.9  436.62  4990.0  436.06  4998.0  434.73
  4998.2  434.23  5001.7  434.23  5002.0  434.73  5020.0  435.35  5040.0  437.01
  5080.0  438.27  5129.0  438.22  5136.4  438.89  5171.5  438.88  5249.8  440.34
  5284.9  440.25  5334.3  441.77  5384.1  442.59  5391.0  442.28  5408.5  443.09
#Mann=3,-1,0
  4530.3    0.05       0  4998.0    0.05       0  5002.0    0.05       0
Bank Sta=4998,5002
Exp/Cntr=0.3,0.1

Type RM Length L Ch R = 1,5825,96,96,96
BEGIN DESCRIPTION:
StreamM018 4.0
END DESCRIPTION:
XS GIS Cut Line= 3
      2502325.00     13842225.00      2502625.00     13841725.00
      2502175.02     13841425.02
#Sta/Elev= 30
  4425.8  443.26  4587.1  440.23  4600.7  439.52  4672.6  438.94  4694.0  437.67
  4703.7  438.14  4789.3  436.73  4857.3  434.60  4869.0  433.67  4884.5  433.83
  4900.1  435.11  4909.5  434.25  4927.3  432.08  5002.0  431.73  5006.5  431.72
  5058.5  432.72  5092.5  431.59  5092.8  431.09  5096.3  431.09  5096.5  431.59
  5103.5  433.92  5109.6  433.93  5116.5  435.69  5196.7  437.13  5202.7  437.72
  5304.9  438.88  5310.9  438.37  5355.9  439.73  5405.5  440.03  5549.7  442.87
#Mann=7,-1,0
  4425.8    0.05       0  4909.5    0.07       0  5002.0    0.05       0
  5006.5    0.07       0  5092.5    0.05       0  5096.5    0.07       0
  5116.5    0.05       0
Bank Sta=5092.5,5096.5
Exp/Cntr=0.3,0.1

Type RM Length L Ch R = 1,5729,354,354,354
BEGIN DESCRIPTION:
H21189
END DESCRIPTION:
XS GIS Cut Line= 5
      2502509.56     13842209.86      2502708.17     13841781.69
      2502715.90     13841719.78      2502687.53     13841650.14
      2502357.63     13841219.71
#Sta/Elev= 30
  4438.5  439.97  4741.5  435.30  4804.1  435.39  4807.6  435.73  4816.5  438.89
  4822.0  436.75  4839.4  439.09  4844.9  438.41  4884.8  439.91  4924.0  438.95
  4928.8  439.79  4957.5  440.16  4986.0  439.48  4991.4  437.97  4997.1  438.63
  5015.4  436.98  5039.5  439.59  5067.2  439.13  5075.2  438.14  5081.5  439.42
  5089.7  436.99  5096.0  438.15  5104.2  436.01  5110.5  436.20  5115.6  434.32
  5115.8  433.82  5119.6  434.32  5125.2  434.63  5482.5  438.22  5590.4  438.82
#Mann=8,-1,0
  4438.5    0.05       0  4804.1    0.07       0  4924.0    0.05       0
  4997.1    0.07       0  5115.6    0.05       0  5119.6    0.07       0
  5125.2    0.05       0  5482.5   0.035       0
Bank Sta=5115.6,5119.6
Exp/Cntr=0.3,0.1

Type RM Length L Ch R = 1,5375,433,433,433
BEGIN DESCRIPTION:
StreamM018 3.0
END DESCRIPTION:
XS GIS Cut Line= 3
      2502775.00     13842074.99      2503025.00     13841625.00
      2502624.97     13841174.96
#Sta/Elev= 30
  4468.0  435.18  4799.7  430.31  4870.9  430.23  4953.0  429.49  4974.8  427.75
  4979.9  425.82  4986.1  425.82  4989.9  424.70  4996.6  425.82  5004.1  424.89
  5010.8  426.04  5023.0  424.22  5023.3  423.72  5027.0  424.22  5032.5  426.60
  5061.0  429.54  5109.4  430.08  5159.6  431.35  5316.0  432.40  5344.0  433.56
  5365.3  432.60  5388.8  433.51  5393.8  434.13  5422.2  433.54  5450.6  434.79
  5457.3  433.92  5478.2  433.84  5514.2  435.29  5532.5  434.92  5584.9  435.57
#Mann=7,-1,0
  4468.0    0.05       0  4870.9    0.12       0  5023.0    0.05       0
  5027.0    0.12       0  5109.4    0.07       0  5388.8    0.12       0
  5532.5    0.07       0
Bank Sta=5023,5027
Exp/Cntr=0.3,0.1

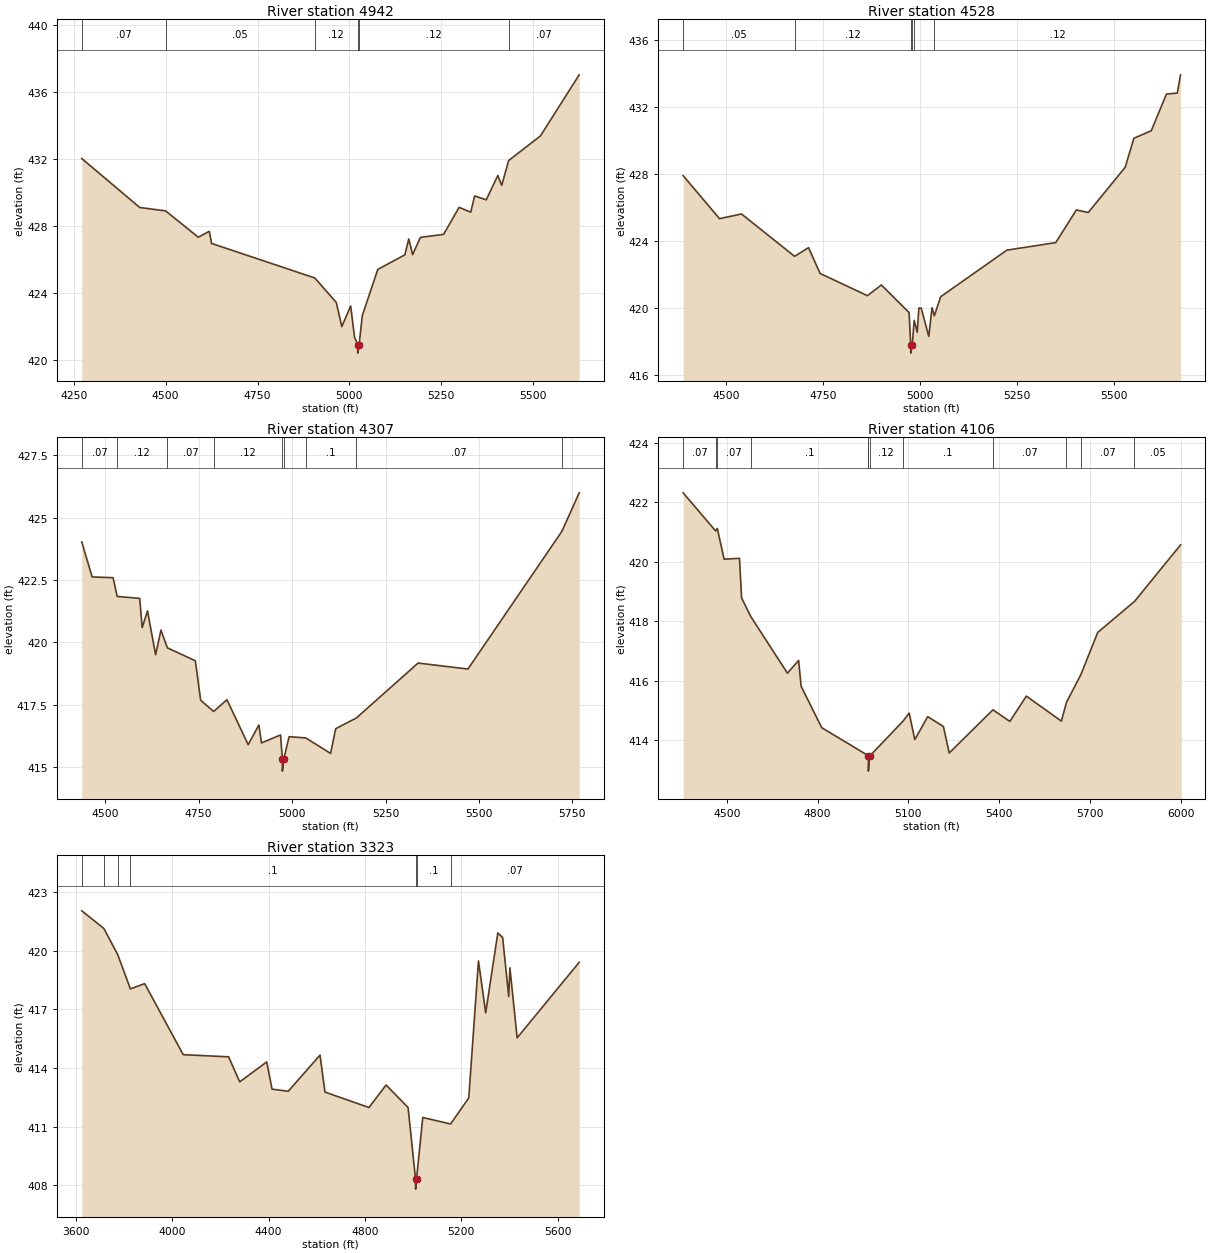
Type RM Length L Ch R = 1,4942,414,414,414
BEGIN DESCRIPTION:
StreamM018 2.0
END DESCRIPTION:
XS GIS Cut Line= 3
      2502974.99     13842125.01      2503375.00     13841525.00
      2503174.99     13840924.98
#Sta/Elev= 30
  4271.7  432.03  4429.5  429.11  4499.8  428.91  4588.7  427.34  4618.7  427.69
  4624.8  426.97  4905.8  424.91  4964.3  423.45  4979.3  422.01  5003.4  423.24
  5013.9  421.39  5022.4  420.93  5022.7  420.43  5026.4  420.93  5035.0  422.66
  5077.2  425.42  5150.9  426.29  5161.5  427.24  5172.0  426.30  5193.1  427.33
  5256.3  427.51  5298.5  429.12  5330.1  428.83  5340.7  429.80  5372.3  429.57
  5403.9  431.02  5414.5  430.43  5433.3  431.91  5519.9  433.38  5625.3  437.02
#Mann=6,-1,0
  4271.7    0.07       0  4499.8    0.05       0  4905.8    0.12       0
  5022.4    0.05       0  5026.4    0.12       0  5433.3    0.07       0
Bank Sta=5022.4,5026.4
Exp/Cntr=0.3,0.1

Type RM Length L Ch R = 1,4528,221,221,221
BEGIN DESCRIPTION:
StreamM018 1.0
END DESCRIPTION:
XS GIS Cut Line= 3
      2503175.02     13841924.98      2503675.00     13841575.00
      2503375.01     13840975.02
#Sta/Elev= 30
  4389.7  427.91  4483.4  425.34  4540.1  425.62  4676.8  423.09  4712.7  423.61
  4742.4  422.07  4864.4  420.74  4900.2  421.38  4971.7  419.73  4975.8  417.81
  4976.0  417.31  4979.8  417.81  4984.8  419.27  4992.6  418.56  4996.9  420.00
  5002.8  420.00  5022.4  418.31  5030.7  420.02  5036.7  419.54  5053.1  420.68
  5223.6  423.46  5349.4  423.91  5402.5  425.86  5433.2  425.71  5528.3  428.41
  5550.6  430.14  5595.4  430.59  5634.5  432.78  5662.4  432.84  5670.8  433.93
#Mann=6,-1,0
  4389.7    0.05       0  4676.8    0.12       0  4975.8    0.05       0
  4979.8    0.12       0  4984.8    0.07       0  5036.7    0.12       0
Bank Sta=4975.8,4979.8
Exp/Cntr=0.3,0.1

Type RM Length L Ch R = 1,4307,201,201,201
BEGIN DESCRIPTION:
H21188
END DESCRIPTION:
XS GIS Cut Line= 4
      2503453.63     13842042.23      2503853.46     13841691.41
      2503894.73     13841549.54      2503747.71     13840915.02
#Sta/Elev= 30
  4437.3  424.02  4465.0  422.62  4521.0  422.59  4532.0  421.84  4592.2  421.76
  4598.9  420.59  4613.1  421.26  4634.9  419.50  4649.1  420.49  4666.4  419.78
  4741.2  419.26  4755.4  417.68  4790.1  417.23  4825.7  417.70  4882.6  415.90
  4911.1  416.69  4918.1  415.97  4969.2  416.29  4973.9  415.34  4974.1  414.84
  4977.9  415.34  4992.1  416.22  5036.7  416.17  5103.1  415.55  5116.7  416.54
  5172.1  416.97  5337.2  419.17  5470.6  418.93  5722.1  424.45  5768.3  425.99
#Mann=9,-1,0
  4437.3    0.07       0  4532.0    0.12       0  4666.4    0.07       0
  4790.1    0.12       0  4973.9    0.05       0  4977.9    0.12       0
  5036.7     0.1       0  5172.1    0.07       0  5722.1    0.05       0
Bank Sta=4973.9,4977.9
Exp/Cntr=0.3,0.1

Type RM Length L Ch R = 1,4106,783,783,783
BEGIN DESCRIPTION:
H21187
END DESCRIPTION:
XS GIS Cut Line= 4
      2503520.72     13842049.95      2504026.29     13841807.48
      2504088.19     13841518.58      2504036.60     13840731.84
#Sta/Elev= 30
  4355.2  422.31  4462.7  421.03  4468.3  421.11  4490.7  420.08  4541.5  420.11
  4548.5  418.78  4579.1  418.15  4700.1  416.25  4737.0  416.68  4745.4  415.81
  4813.4  414.42  4967.3  413.48  4967.6  413.46  4967.8  412.96  4971.6  413.46
  5082.3  414.64  5102.5  414.91  5121.2  414.02  5163.9  414.79  5215.7  414.46
  5235.0  413.57  5379.6  415.02  5435.4  414.63  5490.0  415.48  5605.8  414.64
  5622.6  415.27  5670.6  416.21  5726.0  417.62  5847.5  418.66  5999.8  420.56
#Mann=12,-1,0
  4355.2    0.07       0  4462.7    0.12       0  4468.3    0.07       0
  4579.1     0.1       0  4967.3    0.12       0  4967.6    0.05       0
  4971.6    0.12       0  5082.3     0.1       0  5379.6    0.07       0
  5622.6     0.1       0  5670.6    0.07       0  5847.5    0.05       0
Bank Sta=4967.6,4971.6
Exp/Cntr=0.3,0.1

Type RM Length L Ch R = 1,3323,0,0,0
BEGIN DESCRIPTION:
H21186
END DESCRIPTION:
XS GIS Cut Line= 4
      2503538.75     13842068.02      2504281.66     13841722.36
      2504389.99     13841108.44      2504333.39     13840488.41
#Sta/Elev= 30
  3624.7  422.03  3716.4  421.13  3774.0  419.79  3826.5  418.04  3885.8  418.31
  4045.9  414.68  4234.5  414.57  4280.3  413.29  4392.6  414.31  4414.7  412.92
  4482.0  412.81  4614.0  414.66  4634.3  412.77  4817.1  411.98  4888.2  413.13
  4979.6  411.98  5010.6  408.31  5010.8  407.81  5014.6  408.31  5040.5  411.47
  5156.2  411.14  5231.6  412.47  5271.8  419.47  5301.9  416.82  5352.1  420.90
  5372.2  420.67  5397.4  417.65  5402.4  419.12  5432.4  415.54  5690.1  419.40
#Mann=7,-1,0
  3624.7    0.07       0  3716.4    0.12       0  3774.0    0.07       0
  3826.5     0.1       0  5010.6    0.05       0  5014.6     0.1       0
  5156.2    0.07       0
Bank Sta=5010.6,5014.6
Exp/Cntr=0.3,0.1

Chan Stop Cuts=-1