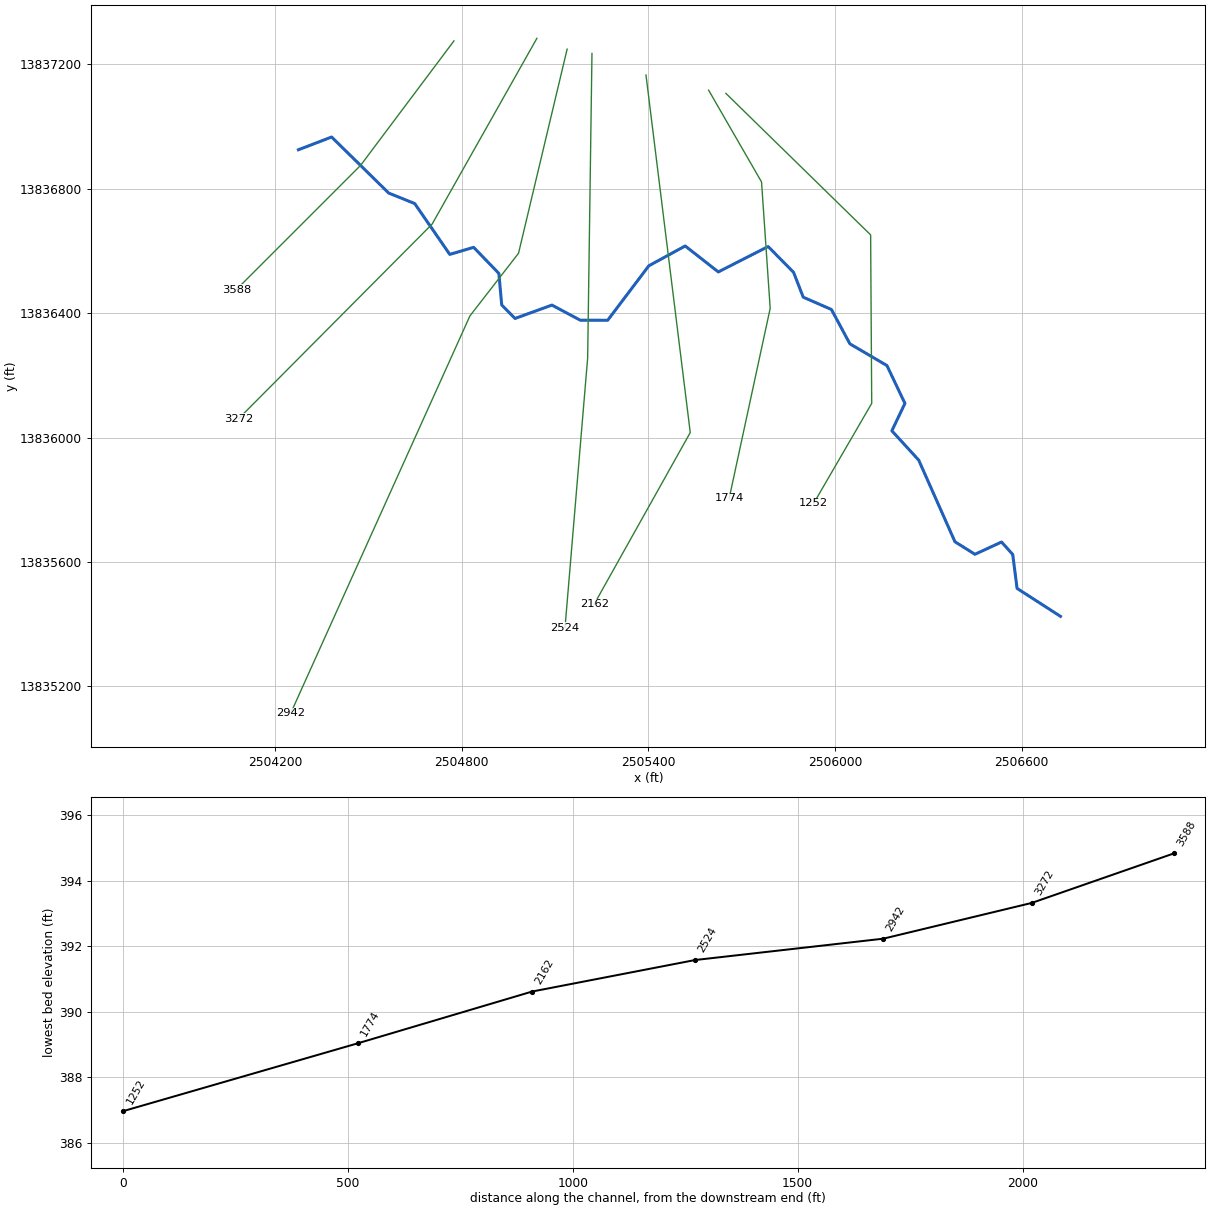
--- StreamM019.prj (project) ---

Proj Title=StreamM019 Base Level Engineering
Current Plan=p01
Default Exp/Contr=0.3,0.1
English Units
Geom File=g01
Flow File=f01
Plan File=p01
BEGIN DESCRIPTION:
StreamM019
END DESCRIPTION:

--- StreamM019.p01 (plan) ---

Plan Title=Multiple Run
Short Identifier=Multiple
Geom File=g01
Flow File=f01
Subcritical Flow
K Sum by GR= 0
Std Step Tol= 0.01
Critical Tol= 0.01
Num of Std Step Trials= 20
Max Error Tol= 0.3
Flow Tol Ratio= 0.001
Split Flow NTrial= 30
Split Flow Tol= 0.02
Split Flow Ratio= 0.02
Log Output Level= 0
Friction Slope Method= 1
Unsteady Friction Slope Method= 2
Unsteady Bridges Friction Slope Method= 1
Parabolic Critical Depth
Global Vel Dist=  1 , 1 , 1
Global Log Level= 0
CheckData=True
Encroach Param= -1, 0, 0, 0
BEGIN DESCRIPTION:
Multiple Run
END DESCRIPTION:

--- StreamM019.f01 (steady flow) ---

Flow Title=Multiple
Number of Profiles=7
Profile Names=10-year,25-year,50-year,1pct_min,100-year,1pct_plu,500-year
River Rch & RM= StreamM019,Reach-1,3588
     790    1279    1721    1122    2238    4466    3746
Boundary for River Rch & Prof#=StreamM019,Reach-1,1
Up Type=0
Dn Type=3
Dn Slope=0.005
Boundary for River Rch & Prof#=StreamM019,Reach-1,2
Up Type=0
Dn Type=3
Dn Slope=0.005
Boundary for River Rch & Prof#=StreamM019,Reach-1,3
Up Type=0
Dn Type=3
Dn Slope=0.005
Boundary for River Rch & Prof#=StreamM019,Reach-1,4
Up Type=0
Dn Type=3
Dn Slope=0.005
Boundary for River Rch & Prof#=StreamM019,Reach-1,5
Up Type=0
Dn Type=3
Dn Slope=0.005
Boundary for River Rch & Prof#=StreamM019,Reach-1,6
Up Type=0
Dn Type=3
Dn Slope=0.005
Boundary for River Rch & Prof#=StreamM019,Reach-1,7
Up Type=0
Dn Type=3
Dn Slope=0.005

--- StreamM019.g01 (geometry) ---

Geom Title=Existing Conditions

River Reach=StreamM019,Reach-1
Reach XY= 30
      2504275.00     13836925.00      2504381.72     13836966.02
      2504565.34     13836785.79      2504648.84     13836752.14
      2504761.64     13836588.64      2504838.36     13836611.36
      2504919.48     13836527.45      2504928.61     13836426.02
      2504971.30     13836382.68      2505090.06     13836425.69
      2505180.98     13836377.17      2505269.29     13836376.89
      2505401.49     13836552.02      2505518.45     13836615.75
      2505624.91     13836532.31      2505785.08     13836613.93
      2505866.83     13836531.07      2505897.87     13836451.17
      2505988.55     13836411.51      2506047.87     13836301.17
      2506166.98     13836231.34      2506224.86     13836109.59
      2506182.83     13836021.60      2506269.14     13835927.30
      2506385.63     13835664.88      2506449.92     13835624.56
      2506535.42     13835664.04      2506571.39     13835623.98
      2506585.37     13835514.89      2506725.00     13835425.00

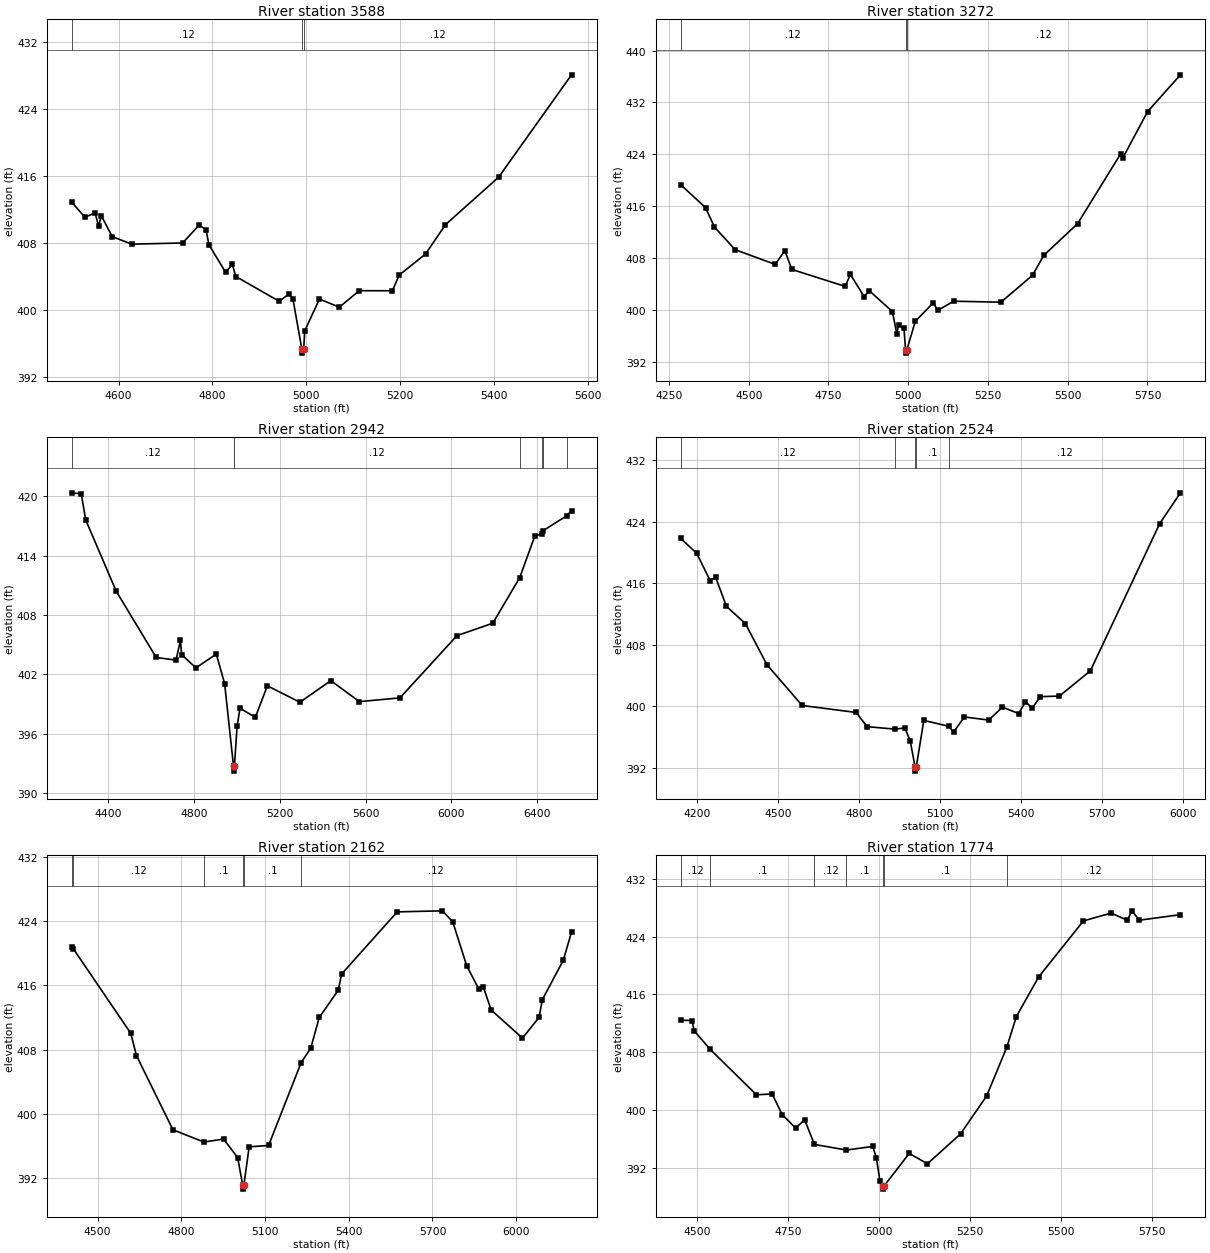
Type RM Length L Ch R = 1,3588,316,316,316
BEGIN DESCRIPTION:
StreamM019 5.0
END DESCRIPTION:
XS GIS Cut Line= 3
      2504775.01     13837275.01      2504475.00     13836875.00
      2504075.00     13836475.00
#Sta/Elev= 30
  4500.0  412.87  4528.1  411.07  4550.0  411.57  4557.3  410.04  4563.6  411.21
  4586.5  408.75  4628.1  407.85  4736.5  407.99  4771.9  410.13  4786.5  409.57
  4792.7  407.76  4828.1  404.51  4842.7  405.42  4850.0  403.98  4942.7  401.02
  4963.6  401.91  4971.9  401.25  4990.7  395.33  4991.0  394.83  4994.7  395.33
  4996.9  397.50  5028.3  401.29  5070.7  400.32  5113.2  402.29  5183.9  402.28
  5198.0  404.14  5254.6  406.68  5297.0  410.18  5410.1  415.84  5565.7  428.08
#Mann=3,-1,0
  4500.0    0.12       0  4990.7    0.05       0  4994.7    0.12       0
Bank Sta=4990.7,4994.7
Exp/Cntr=0.3,0.1

Type RM Length L Ch R = 1,3272,330,330,330
BEGIN DESCRIPTION:
H21197
END DESCRIPTION:
XS GIS Cut Line= 3
      2505041.65     13837283.25      2504704.86     13836686.06
      2504083.36     13836061.09
#Sta/Elev= 30
  4286.4  419.32  4364.8  415.76  4392.5  412.78  4457.5  409.28  4582.9  407.01
  4613.5  409.11  4635.2  406.23  4802.7  403.61  4818.6  405.47  4862.0  402.04
  4877.9  402.95  4950.3  399.74  4964.5  396.28  4969.7  397.67  4986.8  397.13
  4991.8  393.82  4992.1  393.32  4995.9  393.82  5022.2  398.22  5078.7  401.09
  5092.9  399.91  5142.4  401.33  5290.9  401.18  5389.9  405.34  5425.2  408.41
  5531.3  413.31  5665.6  424.03  5672.7  423.42  5750.5  430.58  5853.4  436.25
#Mann=3,-1,0
  4286.4    0.12       0  4991.8    0.05       0  4995.9    0.12       0
Bank Sta=4991.8,4995.9
Exp/Cntr=0.3,0.1

Type RM Length L Ch R = 1,2942,418,418,418
BEGIN DESCRIPTION:
H21196
END DESCRIPTION:
XS GIS Cut Line= 4
      2505138.90     13837248.59      2504982.64     13836592.31
      2504826.39     13836390.92      2504249.99     13835113.13
#Sta/Elev= 30
  4228.9  420.34  4273.7  420.24  4294.3  417.61  4436.5  410.41  4623.2  403.71
  4715.7  403.44  4736.3  405.43  4741.8  404.00  4808.2  402.66  4903.5  404.05
  4942.4  401.06  4983.8  392.73  4984.1  392.23  4987.9  392.73  5000.4  396.74
  5014.0  398.58  5085.5  397.67  5141.6  400.85  5293.3  399.19  5437.6  401.37
  5570.8  399.25  5760.2  399.63  6025.6  405.91  6193.0  407.17  6318.5  411.77
  6389.0  415.98  6423.0  416.18  6427.8  416.52  6537.1  418.01  6560.2  418.53
#Mann=7,-1,0
  4228.9    0.12       0  4983.8    0.05       0  4987.9    0.12       0
  6318.5    0.07       0  6423.0    0.05       0  6427.8    0.07       0
  6537.1    0.05       0
Bank Sta=4983.8,4987.9
Exp/Cntr=0.3,0.1

Type RM Length L Ch R = 1,2524,362,362,362
BEGIN DESCRIPTION:
H21195
END DESCRIPTION:
XS GIS Cut Line= 3
      2505218.75     13837234.67      2505204.86     13836255.50
      2505132.05     13835388.72
#Sta/Elev= 30
  4139.6  421.84  4199.3  419.88  4249.3  416.32  4269.3  416.77  4309.3  412.99
  4379.3  410.75  4459.3  405.40  4589.3  400.11  4789.3  399.20  4829.3  397.36
  4934.6  397.03  4969.4  397.20  4989.4  395.49  5007.3  392.08  5007.6  391.58
  5011.4  392.08  5039.4  398.17  5131.3  397.41  5149.5  396.65  5189.6  398.62
  5279.9  398.21  5330.1  399.90  5390.3  399.06  5415.6  400.60  5440.5  399.77
  5470.6  401.26  5540.9  401.33  5655.5  404.61  5912.2  423.75  5988.7  427.74
#Mann=5,-1,0
  4139.6    0.12       0  4934.6     0.1       0  5007.3    0.05       0
  5011.4     0.1       0  5131.3    0.12       0
Bank Sta=5007.3,5011.4
Exp/Cntr=0.3,0.1

Type RM Length L Ch R = 1,2162,388,388,388
BEGIN DESCRIPTION:
H21194
END DESCRIPTION:
XS GIS Cut Line= 3
      2505392.37     13837165.19      2505534.72     13836015.92
      2505225.72     13835463.88
#Sta/Elev= 30
  4407.4  420.76  4413.3  420.57  4619.2  410.04  4639.4  407.27  4770.3  398.01
  4881.2  396.49  4951.7  396.86  5002.1  394.55  5020.1  391.12  5020.4  390.62
  5024.4  391.12  5043.2  395.89  5112.9  396.06  5229.1  406.35  5264.1  408.21
  5294.3  412.01  5362.1  415.39  5374.9  417.44  5573.7  425.17  5735.8  425.30
  5772.8  423.91  5822.6  418.45  5866.0  415.55  5881.9  415.83  5910.3  412.94
  6022.4  409.44  6081.7  412.01  6093.7  414.24  6168.5  419.13  6198.1  422.65
#Mann=6,-1,0
  4407.4    0.07       0  4413.3    0.12       0  4881.2     0.1       0
  5020.1    0.05       0  5024.4     0.1       0  5229.1    0.12       0
Bank Sta=5020.1,5024.4
Exp/Cntr=0.3,0.1

Type RM Length L Ch R = 1,1774,522,522,522
BEGIN DESCRIPTION:
H21193
END DESCRIPTION:
XS GIS Cut Line= 4
      2505593.75     13837116.61      2505763.89     13836821.48
      2505791.67     13836415.23      2505659.86     13835804.76
#Sta/Elev= 30
  4454.7  412.43  4486.3  412.37  4492.1  410.94  4536.4  408.37  4663.0  402.10
  4706.1  402.21  4733.6  399.36  4770.8  397.49  4795.4  398.64  4822.2  395.23
  4910.0  394.45  4982.3  394.95  4992.3  393.39  5002.3  390.10  5010.1  389.54
  5010.4  389.04  5014.5  389.54  5082.5  393.98  5132.6  392.55  5223.3  396.68
  5294.9  401.92  5350.2  408.65  5376.7  412.93  5438.1  418.43  5560.9  426.17
  5637.2  427.25  5681.4  426.25  5693.9  427.56  5714.3  426.26  5827.1  427.03
#Mann=7,-1,0
  4454.7    0.12       0  4536.4     0.1       0  4822.2    0.12       0
  4910.0     0.1       0  5010.1    0.05       0  5014.5     0.1       0
  5350.2    0.12       0
Bank Sta=5010.1,5014.5
Exp/Cntr=0.3,0.1

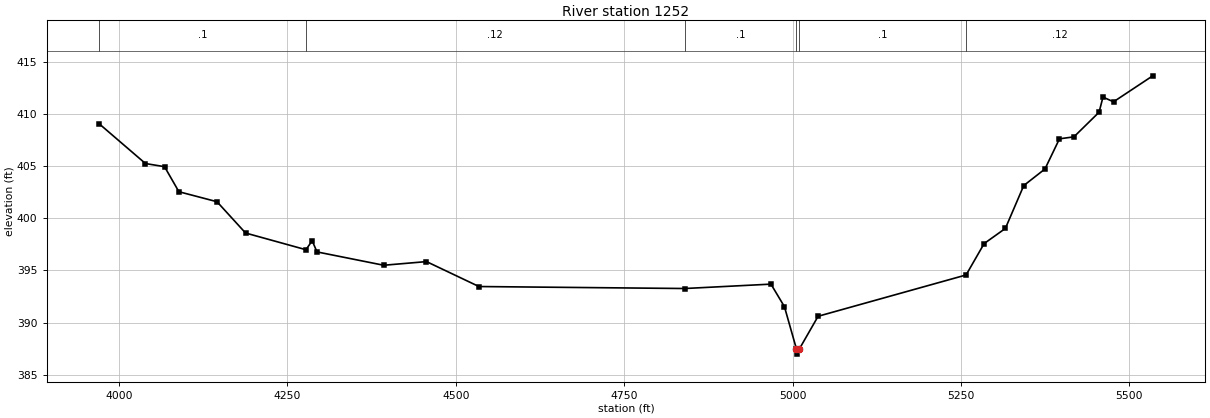
Type RM Length L Ch R = 1,1252,0,0,0
BEGIN DESCRIPTION:
H21192
END DESCRIPTION:
XS GIS Cut Line= 4
      2505649.28     13837106.23      2506114.58     13836651.34
      2506118.06     13836109.67      2505931.51     13835788.40
#Sta/Elev= 30
  3970.9  409.04  4039.4  405.24  4067.7  404.94  4089.0  402.54  4145.6  401.58
  4188.0  398.58  4277.6  396.98  4286.9  397.84  4294.0  396.77  4393.1  395.49
  4456.6  395.84  4534.5  393.45  4840.0  393.26  4968.0  393.68  4988.0  391.52
  5005.8  387.47  5006.1  386.97  5010.2  387.47  5038.0  390.60  5257.7  394.56
  5284.5  397.57  5316.0  399.02  5343.3  403.13  5374.8  404.72  5396.3  407.61
  5417.8  407.80  5455.1  410.16  5460.9  411.61  5476.6  411.16  5534.8  413.65
#Mann=6,-1,0
  3970.9     0.1       0  4277.6    0.12       0  4840.0     0.1       0
  5005.8    0.05       0  5010.2     0.1       0  5257.7    0.12       0
Bank Sta=5005.8,5010.2
Exp/Cntr=0.3,0.1

Chan Stop Cuts=-1