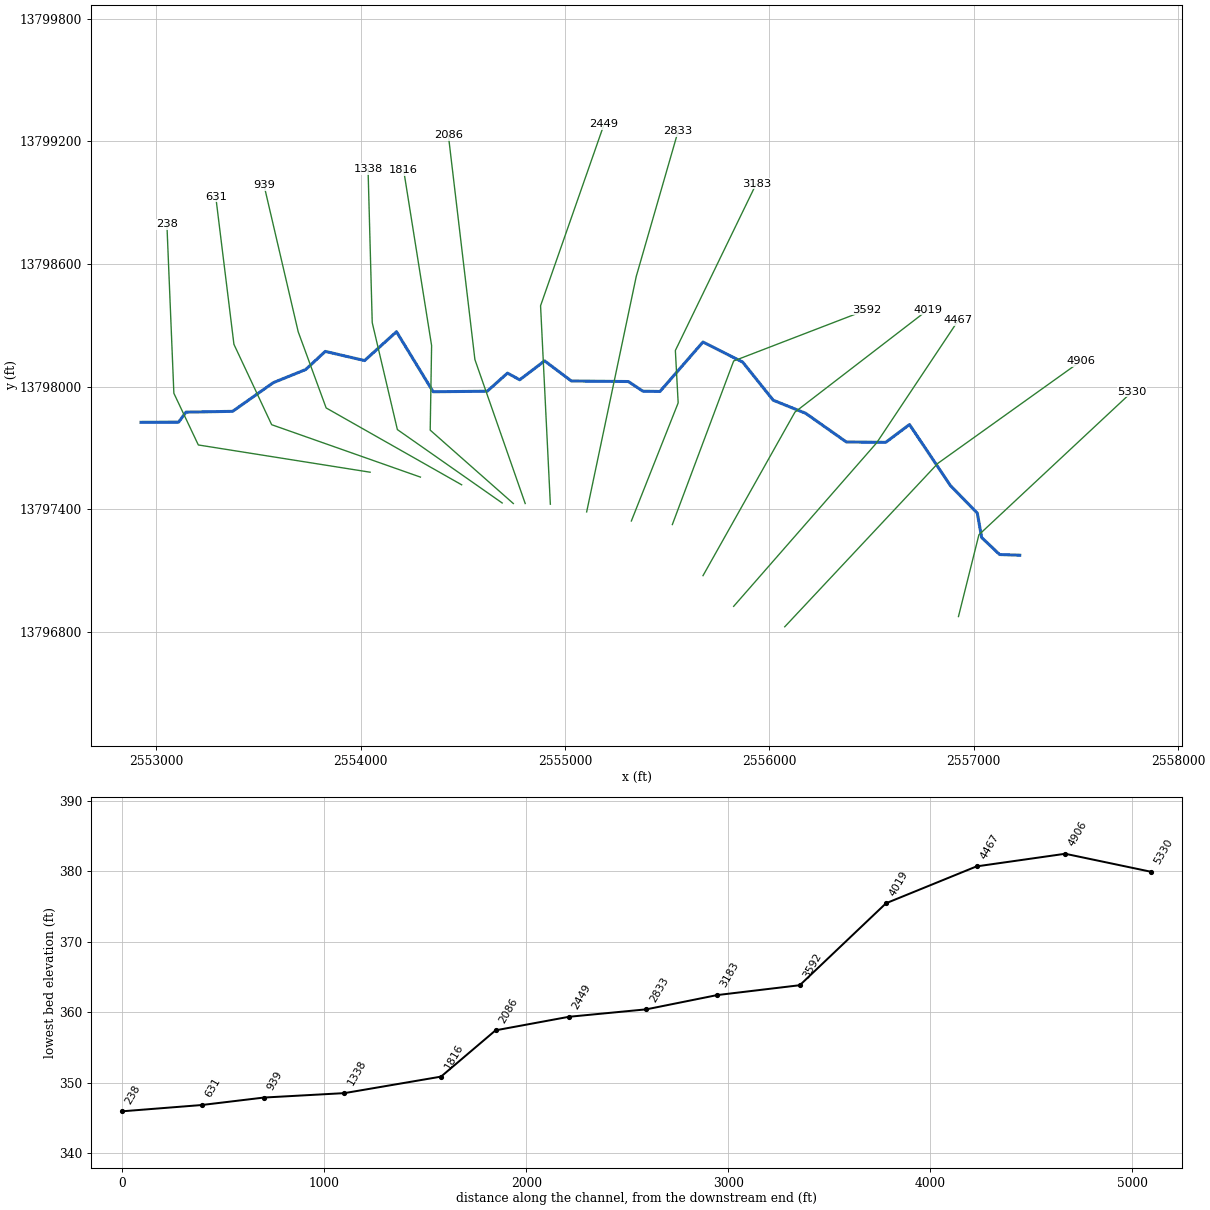
--- StreamM02.prj (project) ---

Proj Title=StreamM02 Base Level Engineering
Current Plan=p01
Default Exp/Contr=0.3,0.1
English Units
Geom File=g01
Flow File=f01
Plan File=p01
Y Axis Title=Elevation
X Axis Title(PF)=Main Channel Distance
X Axis Title(XS)=Station
BEGIN DESCRIPTION:
StreamM02
END DESCRIPTION:
DSS Export Rating Curves= 0
DSS Export Rating Curve Sorted= 0
DSS Export Volume Flow Curves= 0
DXF OffsetX= 0
DXF OffsetY= 0
DXF ScaleX= 1
DXF ScaleY= 10

--- StreamM02.p01 (plan) ---

Plan Title=Multiple Run
Short Identifier=Multiple
Geom File=g01
Flow File=f01
Subcritical Flow
K Sum by GR= 0
Std Step Tol= 0.01
Critical Tol= 0.01
Num of Std Step Trials= 20
Max Error Tol= 0.3
Flow Tol Ratio= 0.001
Split Flow NTrial= 30
Split Flow Tol= 0.02
Split Flow Ratio= 0.02
Log Output Level= 0
Friction Slope Method= 1
Unsteady Friction Slope Method= 2
Unsteady Bridges Friction Slope Method= 1
Parabolic Critical Depth
Global Vel Dist=  1 , 1 , 1
Global Log Level= 0
CheckData=True
Encroach Param= -1, 0, 0, 0
BEGIN DESCRIPTION:
Multiple Run
END DESCRIPTION:

--- StreamM02.f01 (steady flow) ---

Flow Title=Multiple
Number of Profiles=7
Profile Names=10-year,25-year,50-year,1pct_min,100-year,1pct_plu,500-year
River Rch & RM= StreamM02,Reach-1,5330
    1071    1769    2417    1599    3190    6364    5497
Boundary for River Rch & Prof#=StreamM02,Reach-1,1
Up Type=0
Dn Type=3
Dn Slope=0.005
Boundary for River Rch & Prof#=StreamM02,Reach-1,2
Up Type=0
Dn Type=3
Dn Slope=0.005
Boundary for River Rch & Prof#=StreamM02,Reach-1,3
Up Type=0
Dn Type=3
Dn Slope=0.005
Boundary for River Rch & Prof#=StreamM02,Reach-1,4
Up Type=0
Dn Type=3
Dn Slope=0.005
Boundary for River Rch & Prof#=StreamM02,Reach-1,5
Up Type=0
Dn Type=3
Dn Slope=0.005
Boundary for River Rch & Prof#=StreamM02,Reach-1,6
Up Type=0
Dn Type=3
Dn Slope=0.005
Boundary for River Rch & Prof#=StreamM02,Reach-1,7
Up Type=0
Dn Type=3
Dn Slope=0.005

--- StreamM02.g01 (geometry) ---

Geom Title=Existing Conditions
Program Version=4.10

River Reach=StreamM02       ,Reach-1
Reach XY= 30
        2557225.       13797175.      2557126.39     13797178.37
      2557038.39     13797261.67      2557017.14     13797381.17
      2556885.78     13797515.32      2556685.32     13797814.17
      2556569.15     13797727.07      2556376.55     13797728.75
      2556177.29     13797869.15      2556018.68     13797933.07
      2555869.38     13798119.38       2555674.9     13798217.72
      2555464.53     13797975.93      2555380.98     13797977.16
      2555309.78     13798024.48      2555030.86     13798027.07
        2554900.     13798125.58      2554778.33     13798033.02
      2554718.34     13798065.68      2554619.15     13797977.07
      2554354.56     13797974.46      2554175.21     13798268.02
      2554019.11     13798126.96      2553826.64     13798171.86
      2553731.05     13798083.16      2553572.71     13798019.15
      2553373.45     13797878.75      2553145.29     13797874.71
      2553109.06     13797825.94        2552925.       13797825.

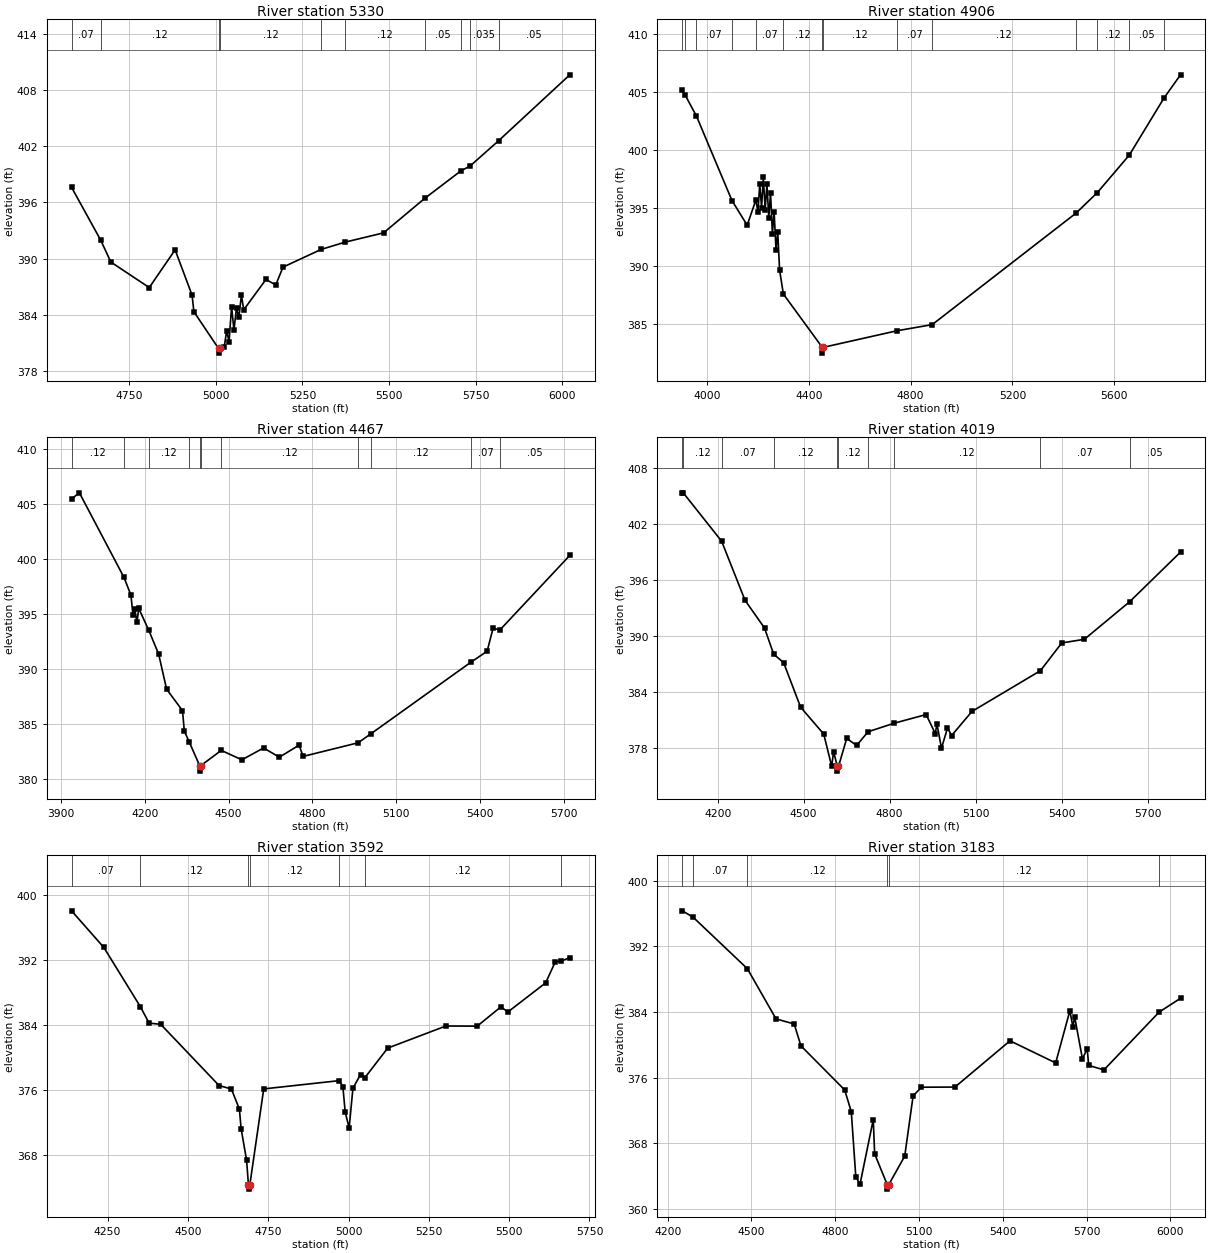
Type RM Length L Ch R = 1 ,5330    ,424,424,424
BEGIN DESCRIPTION:
StreamM02 12.0
END DESCRIPTION:
XS GIS Cut Line= 3
        2556925.     13796874.99        2557025.       13797275.
      2557774.98     13797974.98
#Sta/Elev= 30
  4583.4  397.61  4667.1  392.01  4696.8  389.65  4807.6  386.93  4882.3  390.95
  4931.3  386.11  4936.4  384.36  5007.6  380.44  5007.9  379.94  5011.7  380.44
  5023.8  380.55  5031.1  382.31    5038  381.16  5045.3  384.89  5052.1  382.41
  5059.5  384.75  5066.3  383.74  5073.6  386.09  5080.5  384.57  5144.5  387.79
  5172.8  387.21  5193.8  389.11  5304.1     391  5372.7  391.77    5484  392.76
  5602.6  396.43  5706.9  399.36  5733.9  399.89  5816.3  402.59  6021.6  409.61
#Mann= 10 ,-1 , 0
  4583.4     .07       0  4667.1     .12       0  5007.6     .05       0
  5011.7     .12       0  5304.1     .07       0  5372.7     .12       0
  5602.6     .05       0  5706.9     .12       0  5733.9    .035       0
  5816.3     .05       0
Bank Sta=5007.6,5011.7
XS Rating Curve= 0 ,0
Exp/Cntr=0.3,0.1

Type RM Length L Ch R = 1 ,4906    ,439,439,439
BEGIN DESCRIPTION:
StreamM02 11.0
END DESCRIPTION:
XS GIS Cut Line= 3
      2556075.01     13796825.01        2556825.       13797625.
        2557525.       13798125.
#Sta/Elev= 30
  3903.2  405.17  3915.1  404.73  3958.4  402.97  4098.3  395.66  4157.9  393.53
  4192.2   395.7  4200.4  394.66  4207.3  397.08  4214.6  395.05  4221.4  397.68
  4228.7  394.85  4235.6  397.11  4242.9  394.19  4249.8  396.31  4257.1   392.8
  4263.9  394.68  4271.2   391.4  4278.1  392.91  4285.4  389.65  4300.2  387.59
  4452.9  382.99  4453.1  382.49    4457  382.99  4746.3  384.42  4884.8  384.95
    5450  394.58  5533.5  396.35  5658.8  399.58  5794.9   404.5    5860  406.51
#Mann= 14 ,-1 , 0
  3903.2     .07       0  3915.1     .12       0  3958.4     .07       0
  4098.3     .12       0  4192.2     .07       0  4300.2     .12       0
  4452.9     .05       0    4457     .12       0  4746.3     .07       0
  4884.8     .12       0    5450     .07       0  5533.5     .12       0
  5658.8     .05       0  5794.9     .07       0
Bank Sta=4452.9,4457
XS Rating Curve= 0 ,0
Exp/Cntr=0.3,0.1

Type RM Length L Ch R = 1 ,4467    ,448,448,448
BEGIN DESCRIPTION:
StreamM02 10.0
END DESCRIPTION:
XS GIS Cut Line= 3
      2555825.02     13796925.03        2556525.       13797725.
      2556925.01     13798325.01
#Sta/Elev= 30
  3937.6   405.5  3965.6  406.05  4125.4  398.34  4150.2  396.73  4157.3  394.94
  4163.9  395.51  4171.5  394.24  4178.2  395.52  4213.7  393.55  4249.4  391.36
  4277.8  388.17  4334.8  386.21  4341.4  384.34  4358.6  383.37  4396.3   381.2
  4396.6   380.7  4400.4   381.2  4473.6  382.59  4547.4  381.73  4625.2  382.81
  4681.7  381.97  4752.4  383.07  4766.6  382.04  4963.5  383.28  5008.9  384.09
  5366.3   390.6  5425.7  391.62  5446.8   393.7  5472.3  393.58  5721.7  400.35
#Mann= 11 ,-1 , 0
  3937.6     .12       0  4125.4     .07       0  4213.7     .12       0
  4358.6     .07       0  4396.3     .05       0  4400.4     .07       0
  4473.6     .12       0  4963.5     .07       0  5008.9     .12       0
  5366.3     .07       0  5472.3     .05       0
Bank Sta=4396.3,4400.4
XS Rating Curve= 0 ,0
Exp/Cntr=0.3,0.1

Type RM Length L Ch R = 1 ,4019    ,427,427,427
BEGIN DESCRIPTION:
StreamM02 9.0
END DESCRIPTION:
XS GIS Cut Line= 3
      2555675.01     13797075.02        2556125.       13797875.
      2556774.99     13798374.99
#Sta/Elev= 30
  4076.7  405.32  4080.6   405.3  4213.9  400.13  4295.6  393.79  4363.5  390.82
  4395.5  388.01  4430.1  387.11  4489.4  382.33    4570  379.45  4597.8     376
  4604.5  377.57  4617.3  375.97  4617.6  375.47  4621.5  375.97  4650.3  378.98
  4684.8  378.22  4724.6  379.69  4814.6   380.6  4927.3  381.54  4959.2   379.5
  4964.9  380.53  4980.8  377.93  5001.8  380.09  5016.3  379.29    5087  381.87
  5325.9  386.24  5400.5  389.22  5479.3  389.61  5637.6  393.65  5814.6  398.96
#Mann= 10 ,-1 , 0
  4076.7     .07       0  4080.6     .12       0  4213.9     .07       0
  4395.5     .12       0  4617.3     .05       0  4621.5     .12       0
  4724.6     .07       0  4814.6     .12       0  5325.9     .07       0
  5637.6     .05       0
Bank Sta=4617.3,4621.5
XS Rating Curve= 0 ,0
Exp/Cntr=0.3,0.1

Type RM Length L Ch R = 1 ,3592    ,409,409,409
BEGIN DESCRIPTION:
StreamM02 8.0
END DESCRIPTION:
XS GIS Cut Line= 3
      2555525.01     13797325.02        2555825.       13798125.
        2556475.       13798375.
#Sta/Elev= 30
    4138  398.08  4238.5  393.57  4351.9   386.3  4379.2  384.27  4415.7  384.11
  4597.2  376.58  4635.5  376.16  4660.4  373.67  4665.7  371.27  4682.7  367.42
  4688.6  364.34  4688.9  363.84  4692.8  364.34  4736.1  376.17  4971.8  377.19
  4982.6  376.41  4989.7  373.31    5002  371.37  5013.8  376.26  5037.4  377.94
  5051.3  377.57    5122  381.19  5303.1  383.91  5400.6  383.89  5474.5  386.27
  5495.9  385.63  5613.8  389.22  5643.8  391.82  5662.1   391.9  5688.8  392.31
#Mann= 7 ,-1 , 0
    4138     .07       0  4351.9     .12       0  4688.6     .05       0
  4692.8     .12       0  4971.8     .07       0  5051.3     .12       0
  5662.1     .07       0
Bank Sta=4688.6,4692.8
XS Rating Curve= 0 ,0
Exp/Cntr=0.3,0.1

Type RM Length L Ch R = 1 ,3183    ,350,350,350
BEGIN DESCRIPTION:
H21206
END DESCRIPTION:
XS GIS Cut Line= 4
      2555324.48     13797342.43      2555553.47     13797920.02
       2555539.8     13798176.34      2555935.48     13798991.58
#Sta/Elev= 30
  4252.4  396.33  4290.6  395.57  4485.5  389.28  4588.1  383.17  4653.2  382.55
  4677.2  379.89  4833.9  374.52  4857.6  371.87  4873.7  363.97  4888.7  363.01
  4936.3  370.91  4941.3  366.73  4986.8  362.94  4987.1  362.44    4991  362.94
    5049  366.46    5079   373.8    5109  374.85    5229  374.87    5426   380.5
  5589.6  377.81  5640.3  384.16  5651.4  382.19  5657.3  383.45  5685.4  378.31
  5702.4  379.52    5708   377.5  5762.5  376.96  5959.8  383.99  6036.6  385.68
#Mann= 6 ,-1 , 0
  4252.4     .05       0  4290.6     .07       0  4485.5     .12       0
  4986.8     .05       0    4991     .12       0  5959.8     .05       0
Bank Sta=4986.8,4991
XS Rating Curve= 0 ,0
Exp/Cntr=0.3,0.1

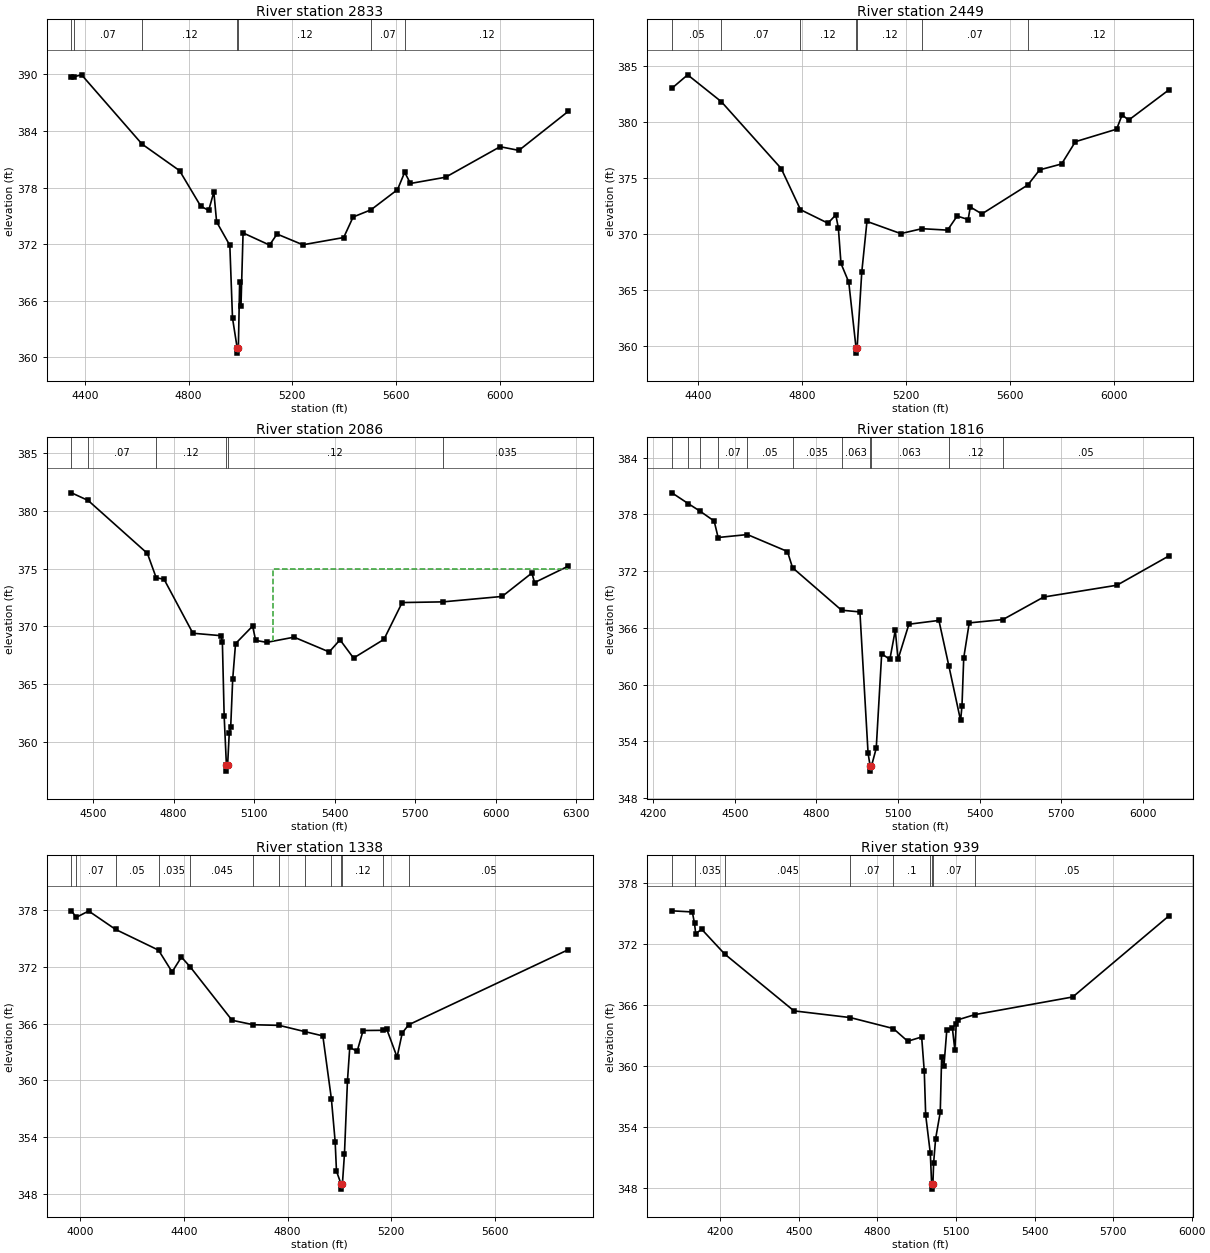
Type RM Length L Ch R = 1 ,2833    ,384,384,384
BEGIN DESCRIPTION:
H21205
END DESCRIPTION:
XS GIS Cut Line= 3
      2555105.76     13797386.88      2555348.41     13798538.61
      2555553.48     13799249.51
#Sta/Elev= 30
  4347.7  389.76    4358  389.76  4386.7  389.96  4619.9  382.61  4764.8  379.79
  4846.5  376.02  4877.2  375.57  4897.2  377.52  4907.9  374.35  4958.9  371.86
  4969.2  364.15  4987.5  360.92  4987.7  360.42  4991.8  360.92  4996.8  367.99
  5001.9   365.4    5010  373.18  5112.2  371.89  5141.1  373.06  5240.7  371.92
  5398.4  372.69  5434.8  374.87  5503.6  375.63    5606  377.77  5633.8  379.61
  5656.3  378.43  5791.6  379.09  6002.2  382.33  6074.7  381.94  6264.6  386.07
#Mann= 7 ,-1 , 0
  4347.7     .05       0    4358     .07       0  4619.9     .12       0
  4987.5     .05       0  4991.8     .12       0  5503.6     .07       0
  5633.8     .12       0
Bank Sta=4987.5,4991.8
XS Rating Curve= 0 ,0
Exp/Cntr=0.3,0.1

Type RM Length L Ch R = 1 ,2449    ,363,363,363
BEGIN DESCRIPTION:
H21204
END DESCRIPTION:
XS GIS Cut Line= 3
      2554928.04     13797424.49       2554880.2     13798395.07
       2555191.2     13799283.65
#Sta/Elev= 30
  4298.3  383.05  4358.9  384.25  4488.6  381.85  4719.3  375.87  4793.6  372.19
  4899.5  370.98  4929.6  371.72  4939.6  370.54  4949.6  367.38  4979.6  365.71
  5007.5  359.86  5007.8  359.36  5011.9  359.86  5029.7   366.6  5049.7  371.14
  5179.9  370.05  5261.6  370.49  5360.2  370.36  5397.1  371.62  5439.5  371.31
  5447.9  372.43  5492.5  371.81  5669.5   374.4    5715  375.75  5799.7  376.28
  5852.7  378.27  6011.6  379.39  6032.8  380.67  6057.9   380.2  6211.5  382.88
#Mann= 7 ,-1 , 0
  4298.3     .05       0  4488.6     .07       0  4793.6     .12       0
  5007.5     .05       0  5011.9     .12       0  5261.6     .07       0
  5669.5     .12       0
Bank Sta=5007.5,5011.9
XS Rating Curve= 0 ,0
Exp/Cntr=0.3,0.1

Type RM Length L Ch R = 1 ,2086    ,270,270,270
BEGIN DESCRIPTION:
H21203
END DESCRIPTION:
XS GIS Cut Line= 3
      2554804.99     13797427.91      2554558.94     13798131.91
      2554429.07     13799228.99
#Sta/Elev= 30
  4419.5  381.56  4481.4   380.9  4702.3  376.31  4735.1   374.2  4764.4  374.07
  4871.9  369.39  4976.4  369.18  4981.7  368.67  4988.4  362.22  4996.8  357.94
  4997.1  357.44  5001.2  357.94  5007.4  360.75  5012.7  361.23  5020.2   365.4
  5030.8  368.49  5094.4  370.01  5105.8  368.77  5147.3   368.6  5248.9  369.05
  5379.8  367.77  5420.1  368.82  5470.5  367.24  5583.9  368.86  5651.7  372.05
  5803.9  372.11  6024.3  372.58  6135.1  374.61  6145.1  373.78    6270   375.2
#Mann= 6 ,-1 , 0
  4419.5     .05       0  4481.4     .07       0  4735.1     .12       0
  4996.8     .05       0  5001.2     .12       0  5803.9    .035       0
#XS Ineff= 2 , 0
       0                    5170       0     375
Permanent Ineff=
       F       F
Bank Sta=4996.8,5001.2
XS Rating Curve= 0 ,0
Exp/Cntr=0.3,0.1

Type RM Length L Ch R = 1 ,1816    ,478,478,478
BEGIN DESCRIPTION:
H21202
END DESCRIPTION:
XS GIS Cut Line= 4
      2554746.92     13797427.86      2554340.21     13797786.73
      2554347.04     13798200.26      2554210.35     13799058.05
#Sta/Elev= 30
    4269  380.27  4329.5  379.12  4372.5  378.33  4424.2  377.29  4438.7  375.55
  4546.4  375.86  4693.5  374.07  4712.2  372.36  4892.3  367.87  4959.7  367.69
  4989.7  352.77  4997.5  351.37  4997.8  350.87  5001.9  351.37  5019.7  353.29
  5039.7  363.27  5069.7  362.67  5089.7  365.76  5099.7  362.68  5139.7  366.39
    5250  366.79  5286.7  361.96  5329.6  356.22  5334.7  357.73  5341.2  362.84
  5361.4  366.53  5485.1  366.88  5634.8  369.26  5904.2  370.51  6093.6  373.58
#Mann= 11 ,-1 , 0
    4269     .05       0  4329.5     .07       0  4372.5     .05       0
  4438.7     .07       0  4546.4     .05       0  4712.2    .035       0
  4892.3    .063       0  4997.5     .05       0  5001.9    .063       0
  5286.7     .12       0  5485.1     .05       0
Bank Sta=4997.5,5001.9
XS Rating Curve= 0 ,0
Exp/Cntr=0.3,0.1

Type RM Length L Ch R = 1 ,1338    ,399,399,399
BEGIN DESCRIPTION:
H21201
END DESCRIPTION:
XS GIS Cut Line= 4
      2554692.23     13797430.61      2554179.58     13797789.46
      2554056.55     13798312.36      2554036.04     13799064.23
#Sta/Elev= 30
  3966.8   377.9  3985.1  377.21    4033  377.88  4136.8  375.94  4302.4  373.75
  4354.8  371.45  4390.7  373.02    4425  371.97    4586  366.35  4667.7  365.88
  4768.2  365.81  4868.6  365.14  4936.1   364.7  4969.1  358.05  4983.6  353.55
  4988.7  350.43  5006.8  349.03  5007.1  348.53  5011.5  349.03  5019.5  352.25
  5031.1  359.97    5040   363.5  5068.3  363.07  5091.4  365.27  5169.1  365.29
  5182.4  365.43  5222.4  362.46  5242.4  365.02  5267.5  365.88  5881.9  373.79
#Mann= 13 ,-1 , 0
  3966.8     .05       0  3985.1     .07       0  4136.8     .05       0
  4302.4    .035       0    4425    .045       0  4667.7     .07       0
  4768.2     .12       0  4868.6      .1       0  4969.1     .12       0
  5006.8     .05       0  5011.5     .12       0  5169.1     .07       0
  5267.5     .05       0
Bank Sta=5006.8,5011.5
XS Rating Curve= 0 ,0
Exp/Cntr=0.3,0.1

Type RM Length L Ch R = 1 ,939     ,308,308,308
BEGIN DESCRIPTION:
H21200
END DESCRIPTION:
XS GIS Cut Line= 4
      2554494.01     13797519.46      2553830.98     13797895.41
      2553694.28     13798267.93      2553526.81     13798985.64
#Sta/Elev= 30
  4015.6   375.3  4093.5  375.19  4101.8  374.06  4106.4  373.06  4129.4  373.48
  4216.9  371.05  4481.5  365.45  4696.6  364.79  4860.9  363.71  4915.8  362.46
  4969.1  362.88  4979.1   359.5  4984.5  355.18  5002.2  351.42  5007.2   348.4
  5007.6   347.9    5012   348.4  5014.9  350.52  5022.4  352.86  5040.1  355.48
  5045.4  360.94  5054.3  360.06    5065  363.53  5086.3  363.78  5095.8   361.6
  5101.1  364.18  5107.6  364.57    5172  365.08    5546  366.82  5911.6  374.77
#Mann= 9 ,-1 , 0
  4015.6     .05       0  4101.8    .035       0  4216.9    .045       0
  4696.6     .07       0  4860.9      .1       0  5002.2     .07       0
  5007.2     .05       0    5012     .07       0    5172     .05       0
Bank Sta=5007.2,5012
XS Rating Curve= 0 ,0
Exp/Cntr=0.3,0.1

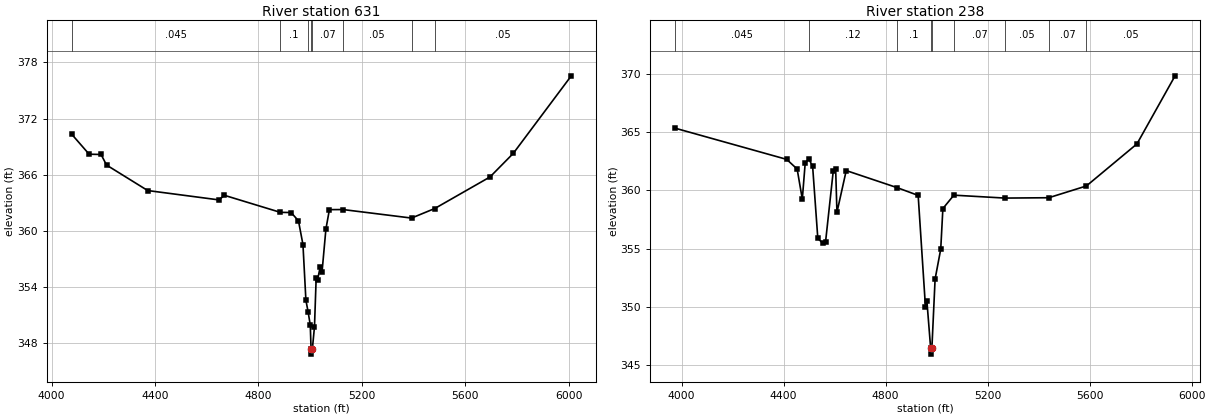
Type RM Length L Ch R = 1 ,631     ,393,393,393
BEGIN DESCRIPTION:
H21199
END DESCRIPTION:
XS GIS Cut Line= 4
      2554292.37     13797557.06      2553564.41     13797813.39
      2553379.86     13798206.41      2553290.99     13798927.58
#Sta/Elev= 30
  4077.4  370.33    4145  368.19  4191.2  368.16  4212.4  367.03  4371.5  364.31
  4647.1  363.31  4668.3   363.8  4884.7  361.98  4926.4  361.96  4954.8  361.07
  4972.1  358.54  4983.5  352.59    4992  351.36  5000.4  349.95  5003.5  347.34
  5003.9  346.84  5008.3  347.34  5016.7  349.77  5023.2  354.97  5028.7  354.79
  5038.8  356.15    5046  355.65  5060.9   360.2  5074.4  362.27  5126.8  362.28
    5392  361.37  5481.9  362.39  5695.6  365.76  5785.7  368.28    6010  376.56
#Mann= 8 ,-1 , 0
  4077.4    .045       0  4884.7      .1       0    4992     .07       0
  5003.5     .05       0  5008.3     .07       0  5126.8     .05       0
    5392     .07       0  5481.9     .05       0
Bank Sta=5003.5,5008.3
XS Rating Curve= 0 ,0
Exp/Cntr=0.3,0.1

Type RM Length L Ch R = 1 ,238     ,0,0,0
BEGIN DESCRIPTION:
H21198
END DESCRIPTION:
XS GIS Cut Line= 4
      2554046.31     13797580.99      2553205.56     13797714.28
      2553085.94     13797967.18      2553051.76     13798794.26
#Sta/Elev= 30
  3976.2  365.33  4412.4  362.66  4453.4  361.83  4473.6  359.25  4484.8  362.31
  4499.2  362.71  4514.1  362.05  4534.4  355.88  4554.6  355.45  4564.8  355.59
  4595.1   361.7  4604.4   361.8  4609.4  358.12  4645.8   361.7    4846  360.23
  4927.8  359.57  4956.4  350.01    4962  350.52  4976.8  346.45  4977.1  345.95
  4981.6  346.45  4994.2  352.39  5016.3  354.96  5024.7  358.44  5067.7  359.59
  5267.8  359.34  5439.8  359.37  5587.4  360.38  5785.6  363.99    5935  369.83
#Mann= 9 ,-1 , 0
  3976.2    .045       0  4499.2     .12       0    4846      .1       0
  4976.8     .05       0  4981.6      .1       0  5067.7     .07       0
  5267.8     .05       0  5439.8     .07       0  5587.4     .05       0
Bank Sta=4976.8,4981.6
XS Rating Curve= 0 ,0
Exp/Cntr=0.3,0.1

Chan Stop Cuts=-1
Use User Specified Reach Order=0
Composite Channel Slope=5