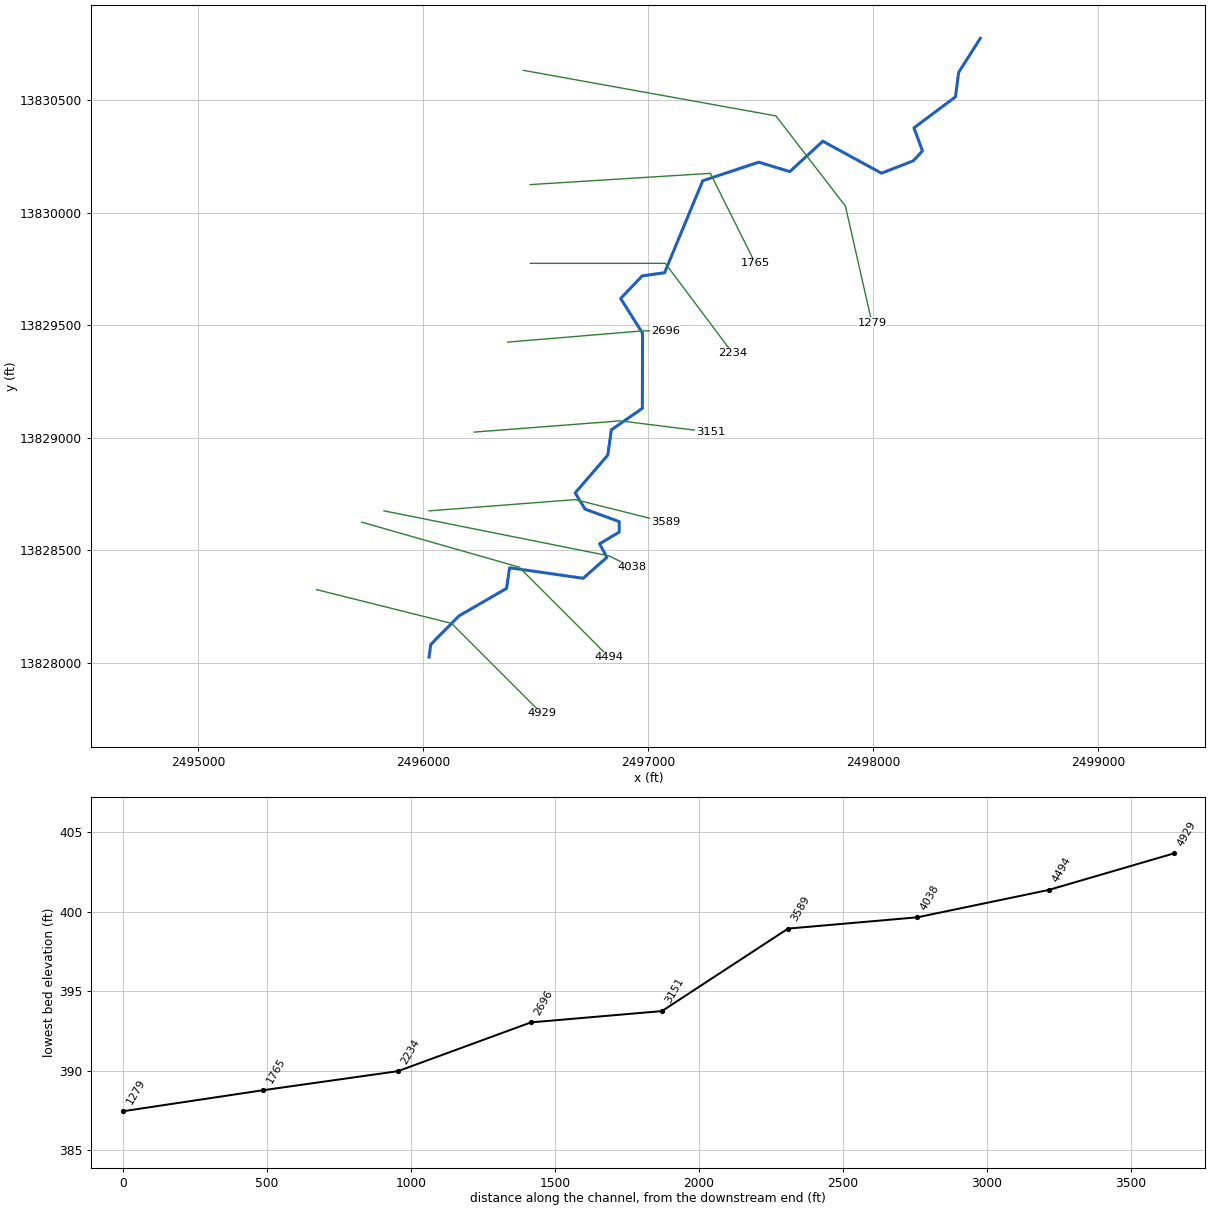
--- StreamM020.prj (project) ---

Proj Title=StreamM020 Base Level Engineering
Current Plan=p01
Default Exp/Contr=0.3,0.1
English Units
Geom File=g01
Flow File=f01
Plan File=p01
BEGIN DESCRIPTION:
StreamM020
END DESCRIPTION:

--- StreamM020.p01 (plan) ---

Plan Title=Multiple Run
Short Identifier=Multiple
Geom File=g01
Flow File=f01
Subcritical Flow
K Sum by GR= 0
Std Step Tol= 0.01
Critical Tol= 0.01
Num of Std Step Trials= 20
Max Error Tol= 0.3
Flow Tol Ratio= 0.001
Split Flow NTrial= 30
Split Flow Tol= 0.02
Split Flow Ratio= 0.02
Log Output Level= 0
Friction Slope Method= 1
Unsteady Friction Slope Method= 2
Unsteady Bridges Friction Slope Method= 1
Parabolic Critical Depth
Global Vel Dist=  1 , 1 , 1
Global Log Level= 0
CheckData=True
Encroach Param= -1, 0, 0, 0
BEGIN DESCRIPTION:
Multiple Run
END DESCRIPTION:

--- StreamM020.f01 (steady flow) ---

Flow Title=Multiple
Number of Profiles=7
Profile Names=10-year,25-year,50-year,1pct_min,100-year,1pct_plu,500-year
River Rch & RM= StreamM020,Reach-1,4929
     913    1502    2044    1348    2690    5367    4609
River Rch & RM= StreamM020,Reach-1,4494
    1008    1658    2258    1489    2970    5926    5085
Boundary for River Rch & Prof#=StreamM020,Reach-1,1
Up Type=0
Dn Type=3
Dn Slope=0.005
Boundary for River Rch & Prof#=StreamM020,Reach-1,2
Up Type=0
Dn Type=3
Dn Slope=0.005
Boundary for River Rch & Prof#=StreamM020,Reach-1,3
Up Type=0
Dn Type=3
Dn Slope=0.005
Boundary for River Rch & Prof#=StreamM020,Reach-1,4
Up Type=0
Dn Type=3
Dn Slope=0.005
Boundary for River Rch & Prof#=StreamM020,Reach-1,5
Up Type=0
Dn Type=3
Dn Slope=0.005
Boundary for River Rch & Prof#=StreamM020,Reach-1,6
Up Type=0
Dn Type=3
Dn Slope=0.005
Boundary for River Rch & Prof#=StreamM020,Reach-1,7
Up Type=0
Dn Type=3
Dn Slope=0.005

--- StreamM020.g01 (geometry) ---

Geom Title=Existing Conditions

River Reach=StreamM020,Reach-1
Reach XY= 30
      2496025.00     13828025.00      2496032.76     13828081.21
      2496158.33     13828208.35      2496369.71     13828330.55
      2496383.03     13828422.10      2496709.85     13828375.38
      2496815.70     13828468.32      2496782.94     13828528.57
      2496870.21     13828580.65      2496870.19     13828627.24
      2496718.45     13828682.75      2496674.49     13828754.76
      2496819.47     13828922.58      2496835.39     13829035.10
      2496973.02     13829130.67      2496973.94     13829464.56
      2496876.57     13829618.96      2496972.62     13829719.46
      2497071.63     13829733.15      2497241.45     13830142.14
      2497490.28     13830224.61      2497628.42     13830182.80
      2497774.91     13830317.71      2498035.69     13830175.74
      2498177.86     13830230.82      2498217.74     13830274.70
      2498180.11     13830377.30      2498364.61     13830514.90
      2498378.62     13830623.50      2498475.00     13830775.00

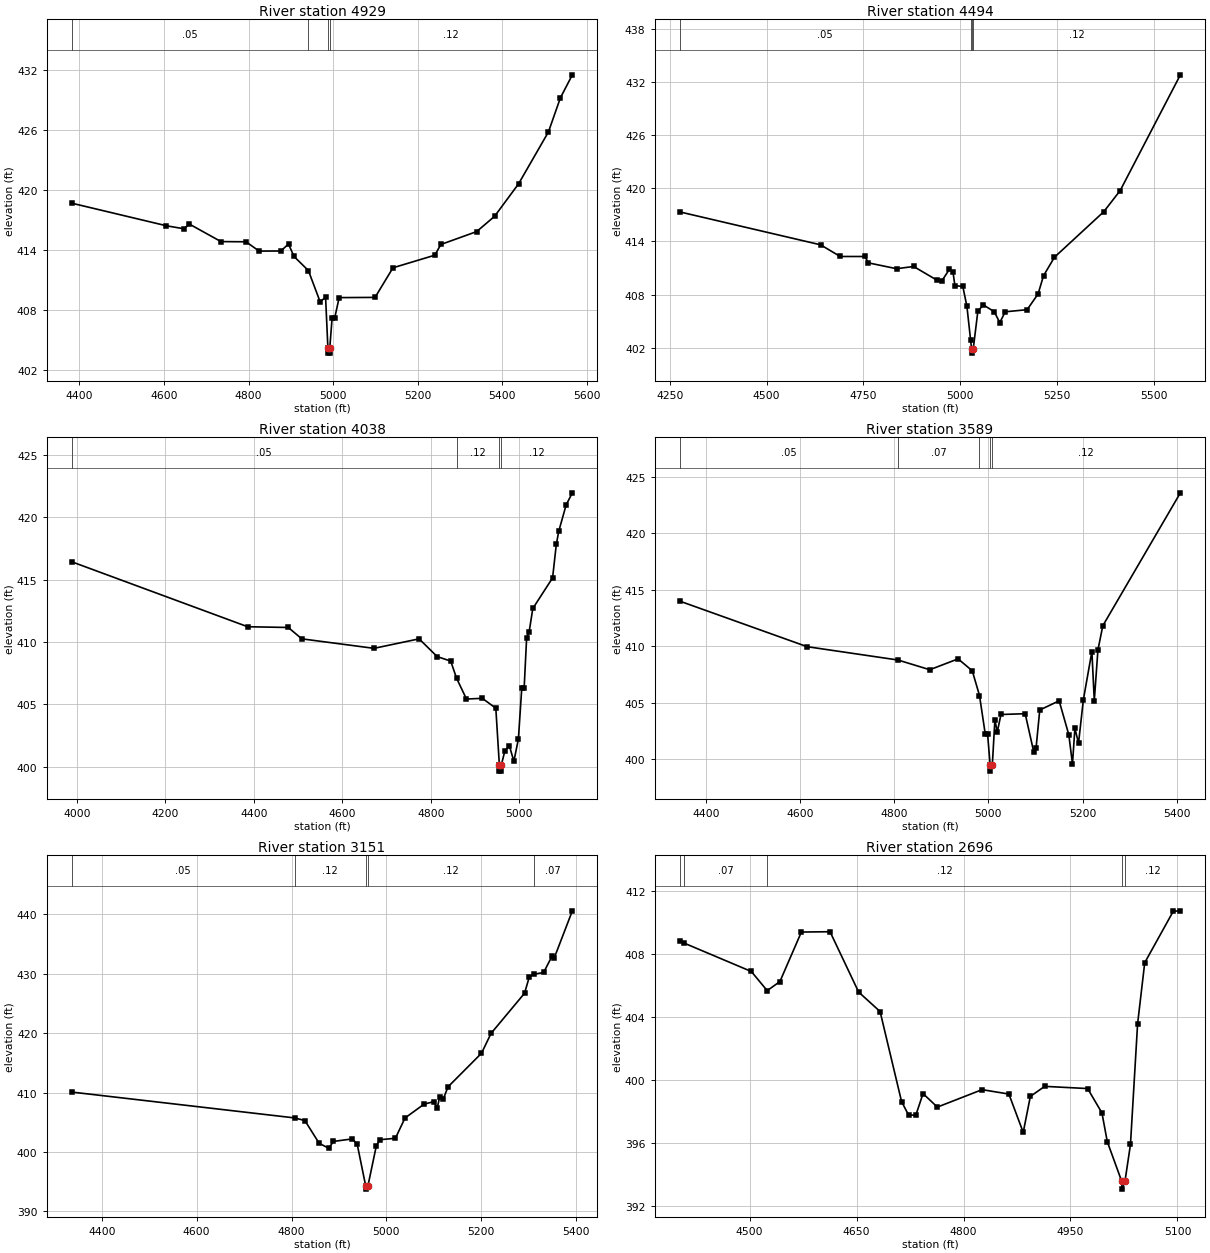
Type RM Length L Ch R = 1,4929,435,435,435
BEGIN DESCRIPTION:
StreamM020 8.0
END DESCRIPTION:
XS GIS Cut Line= 3
      2495524.97     13828325.01      2496125.00     13828175.00
      2496525.01     13827774.99
#Sta/Elev= 30
  4381.8  418.67  4606.0  416.41  4647.3  416.11  4660.1  416.58  4734.9  414.83
  4794.1  414.81  4825.1  413.88  4876.6  413.89  4894.6  414.59  4907.5  413.35
  4941.7  411.93  4969.4  408.81  4982.3  409.27  4987.8  404.18  4988.1  403.68
  4991.9  403.68  4992.2  404.18  4997.7  407.18  5003.8  407.18  5014.4  409.23
  5099.3  409.25  5141.7  412.21  5240.7  413.47  5254.9  414.54  5339.7  415.83
  5382.1  417.36  5438.7  420.60  5509.4  425.79  5537.7  429.20  5566.0  431.50
#Mann=4,-1,0
  4381.8    0.05       0  4941.7    0.12       0  4987.8    0.05       0
  4992.2    0.12       0
Bank Sta=4987.8,4992.2
Exp/Cntr=0.3,0.1

Type RM Length L Ch R = 1,4494,456,456,456
BEGIN DESCRIPTION:
StreamM020 7.0
END DESCRIPTION:
XS GIS Cut Line= 3
      2495725.03     13828624.99      2496425.00     13828425.00
      2496825.02     13828024.98
#Sta/Elev= 30
  4275.6  417.34  4639.6  413.62  4690.3  412.30  4754.0  412.30  4763.1  411.58
  4835.9  410.92  4880.1  411.17  4941.2  409.60  4952.9  409.54  4972.4  410.85
  4981.5  410.60  4986.7  409.00  5007.1  408.92  5017.7  406.66  5027.3  402.84
  5029.7  401.88  5030.0  401.38  5034.1  401.88  5046.0  406.12  5060.2  406.83
  5088.4  406.06  5102.6  404.83  5116.7  406.05  5173.3  406.29  5201.6  408.07
  5215.7  410.13  5244.0  412.22  5371.3  417.36  5413.7  419.75  5569.3  432.83
#Mann=4,-1,0
  4275.6    0.05       0  5027.3    0.12       0  5029.7    0.05       0
  5034.1    0.12       0
Bank Sta=5029.7,5034.1
Exp/Cntr=0.3,0.1

Type RM Length L Ch R = 1,4038,449,449,449
BEGIN DESCRIPTION:
StreamM020 6.0
END DESCRIPTION:
XS GIS Cut Line= 3
      2495825.01     13828675.00      2496825.00     13828475.00
      2496925.00     13828425.00
#Sta/Elev= 30
  3988.2  416.42  4385.9  411.22  4477.7  411.16  4508.3  410.25  4671.5  409.49
  4773.4  410.25  4814.2  408.83  4844.8  408.47  4858.3  407.08  4880.5  405.43
  4916.2  405.49  4946.8  404.70  4954.8  400.16  4955.1  399.66  4958.9  399.66
  4959.3  400.16  4967.2  401.27  4977.4  401.69  4987.6  400.45  4997.8  402.22
  5005.4  406.28  5010.8  406.28  5016.4  410.30  5022.0  410.78  5030.4  412.68
  5075.1  415.13  5083.5  417.81  5089.1  418.87  5105.8  420.98  5119.8  421.94
#Mann=4,-1,0
  3988.2    0.05       0  4858.3    0.12       0  4954.8    0.05       0
  4959.3    0.12       0
Bank Sta=4954.8,4959.3
Exp/Cntr=0.3,0.1

Type RM Length L Ch R = 1,3589,438,438,438
BEGIN DESCRIPTION:
StreamM020 5.0
END DESCRIPTION:
XS GIS Cut Line= 3
      2496025.05     13828675.00      2496675.00     13828725.00
      2497075.02     13828625.00
#Sta/Elev= 30
  4343.8  413.99  4614.5  409.96  4807.7  408.78  4875.3  407.92  4935.5  408.88
  4965.6  407.83  4981.0  405.64  4993.2  402.24  4998.2  402.24  5003.7  399.45
  5004.0  398.95  5008.2  399.45  5013.7  403.46  5018.9  402.43  5026.6  403.96
  5078.1  404.03  5096.2  400.67  5101.3  401.02  5109.1  404.36  5150.3  405.17
  5170.9  402.16  5178.6  399.58  5183.8  402.74  5191.5  401.42  5201.8  405.27
  5219.9  409.53  5225.0  405.18  5232.7  409.66  5243.1  411.81  5408.0  423.57
#Mann=5,-1,0
  4343.8    0.05       0  4807.7    0.07       0  4981.0    0.12       0
  5003.7    0.05       0  5008.2    0.12       0
Bank Sta=5003.7,5008.2
Exp/Cntr=0.3,0.1

Type RM Length L Ch R = 1,3151,455,455,455
BEGIN DESCRIPTION:
StreamM020 4.0
END DESCRIPTION:
XS GIS Cut Line= 3
      2496225.03     13829025.00      2496875.00     13829075.00
      2497274.99     13829025.00
#Sta/Elev= 30
  4336.8  410.10  4806.3  405.75  4828.2  405.30  4858.3  401.47  4878.4  400.65
  4888.4  401.79  4928.5  402.22  4938.5  401.28  4956.4  394.26  4956.7  393.76
  4960.9  394.26  4978.7  401.04  4986.2  402.08  5018.9  402.32  5039.1  405.73
  5079.4  408.07  5099.6  408.48  5107.1  407.44  5112.1  409.24  5119.7  408.90
  5129.8  410.98  5200.3  416.63  5220.5  419.98  5291.0  426.73  5301.1  429.49
  5310.3  429.93  5331.3  430.23  5349.0  432.99  5354.0  432.75  5391.8  440.61
#Mann=5,-1,0
  4336.8    0.05       0  4806.3    0.12       0  4956.4    0.05       0
  4960.9    0.12       0  5310.3    0.07       0
Bank Sta=4956.4,4960.9
Exp/Cntr=0.3,0.1

Type RM Length L Ch R = 1,2696,462,462,462
BEGIN DESCRIPTION:
StreamM020 3.0
END DESCRIPTION:
XS GIS Cut Line= 3
      2496374.96     13829425.00      2496975.00     13829475.00
      2497074.98     13829475.00
#Sta/Elev= 30
  4402.0  408.85  4408.0  408.71  4502.4  406.90  4524.7  405.68  4542.5  406.26
  4572.6  409.41  4612.8  409.43  4652.9  405.59  4683.0  404.35  4713.1  398.62
  4723.1  397.75  4733.2  397.77  4743.2  399.13  4763.3  398.27  4826.0  399.38
  4863.6  399.10  4883.7  396.66  4893.7  398.95  4913.8  399.59  4974.0  399.45
  4994.1  397.90  5001.6  396.07  5021.8  393.55  5022.2  393.05  5026.4  393.55
  5034.1  395.89  5044.1  403.57  5054.1  407.46  5094.1  410.73  5104.1  410.76
#Mann=5,-1,0
  4402.0    0.05       0  4408.0    0.07       0  4524.7    0.12       0
  5021.8    0.05       0  5026.4    0.12       0
Bank Sta=5021.8,5026.4
Exp/Cntr=0.3,0.1

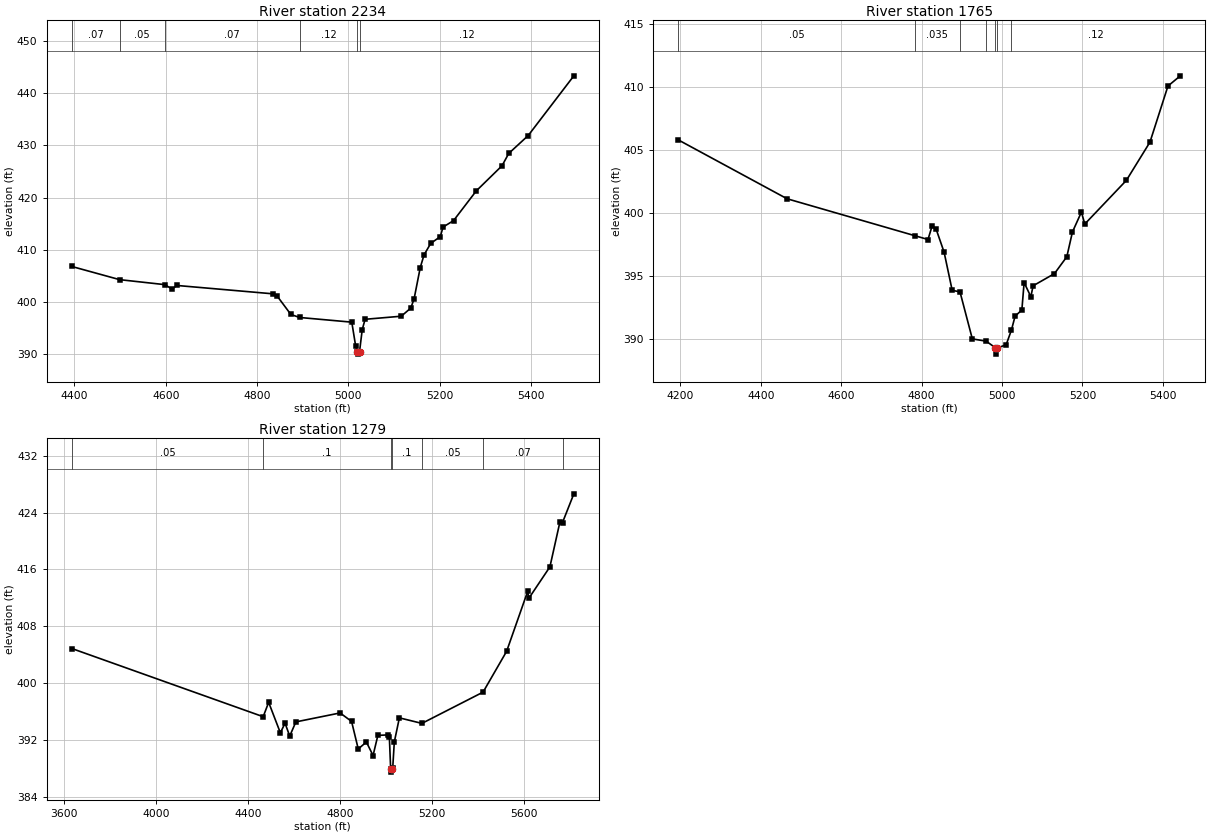
Type RM Length L Ch R = 1,2234,469,469,469
BEGIN DESCRIPTION:
StreamM020 2.0
END DESCRIPTION:
XS GIS Cut Line= 3
      2496475.02     13829775.00      2497075.00     13829775.00
      2497375.01     13829374.99
#Sta/Elev= 30
  4394.1  406.79  4499.1  404.26  4597.6  403.31  4614.1  402.45  4624.1  403.15
  4834.1  401.55  4844.1  401.11  4874.1  397.59  4893.1  397.01  5007.6  396.11
  5016.0  391.57  5019.8  390.48  5020.2  389.98  5024.6  390.48  5030.5  394.70
  5036.8  396.66  5116.0  397.25  5136.8  398.81  5144.1  400.58  5157.6  406.59
  5166.0  409.03  5180.5  411.21  5201.4  412.51  5207.6  414.35  5230.5  415.58
  5280.5  421.30  5336.8  426.11  5351.4  428.46  5394.1  431.90  5494.1  443.35
#Mann=6,-1,0
  4394.1    0.07       0  4499.1    0.05       0  4597.6    0.07       0
  4893.1    0.12       0  5019.8    0.05       0  5024.6    0.12       0
Bank Sta=5019.8,5024.6
Exp/Cntr=0.3,0.1

Type RM Length L Ch R = 1,1765,486,486,486
BEGIN DESCRIPTION:
StreamM020 1.0
END DESCRIPTION:
XS GIS Cut Line= 3
      2496474.97     13830125.00      2497275.00     13830175.00
      2497475.00     13829775.00
#Sta/Elev= 30
  4194.7  405.81  4465.3  401.13  4782.5  398.20  4815.9  397.89  4826.0  398.95
  4836.0  398.73  4856.0  396.88  4876.1  393.85  4895.5  393.73  4926.2  389.99
  4960.6  389.81  4983.8  389.28  4984.2  388.78  4988.7  389.28  5010.3  389.52
  5023.5  390.70  5032.6  391.80  5049.4  392.29  5055.0  394.47  5071.8  393.34
  5077.3  394.21  5130.5  395.18  5161.2  396.52  5175.2  398.49  5197.5  400.07
  5205.9  399.12  5309.3  402.59  5368.0  405.63  5412.8  410.09  5443.5  410.90
#Mann=7,-1,0
  4194.7    0.05       0  4782.5   0.035       0  4895.5    0.12       0
  4960.6   0.035       0  4983.8   0.035       0  4988.7   0.035       0
  5023.5    0.12       0
Bank Sta=4983.8,4988.7
Exp/Cntr=0.3,0.1

Type RM Length L Ch R = 1,1279,0,0,0
BEGIN DESCRIPTION:
H21207
END DESCRIPTION:
XS GIS Cut Line= 4
      2496444.09     13830632.81      2497566.48     13830430.41
      2497875.61     13830029.29      2497993.37     13829510.40
#Sta/Elev= 30
  3635.7  404.86  4466.4  395.26  4490.2  397.28  4541.0  392.99  4561.3  394.35
  4581.6  392.53  4608.3  394.53  4800.2  395.79  4850.0  394.60  4879.0  390.72
  4914.3  391.70  4943.3  389.80  4964.1  392.63  5007.6  392.70  5014.0  392.44
  5019.6  387.96  5020.0  387.46  5024.6  387.96  5028.5  387.98  5035.5  391.70
  5057.5  395.10  5155.2  394.32  5420.7  398.72  5522.9  404.46  5614.4  412.91
  5619.5  411.93  5710.8  416.35  5753.9  422.62  5765.5  422.59  5814.7  426.63
#Mann=7,-1,0
  3635.7    0.05       0  4466.4     0.1       0  5019.6    0.05       0
  5024.6     0.1       0  5155.2    0.05       0  5420.7    0.07       0
  5765.5    0.05       0
Bank Sta=5019.6,5024.6
Exp/Cntr=0.3,0.1

Chan Stop Cuts=-1