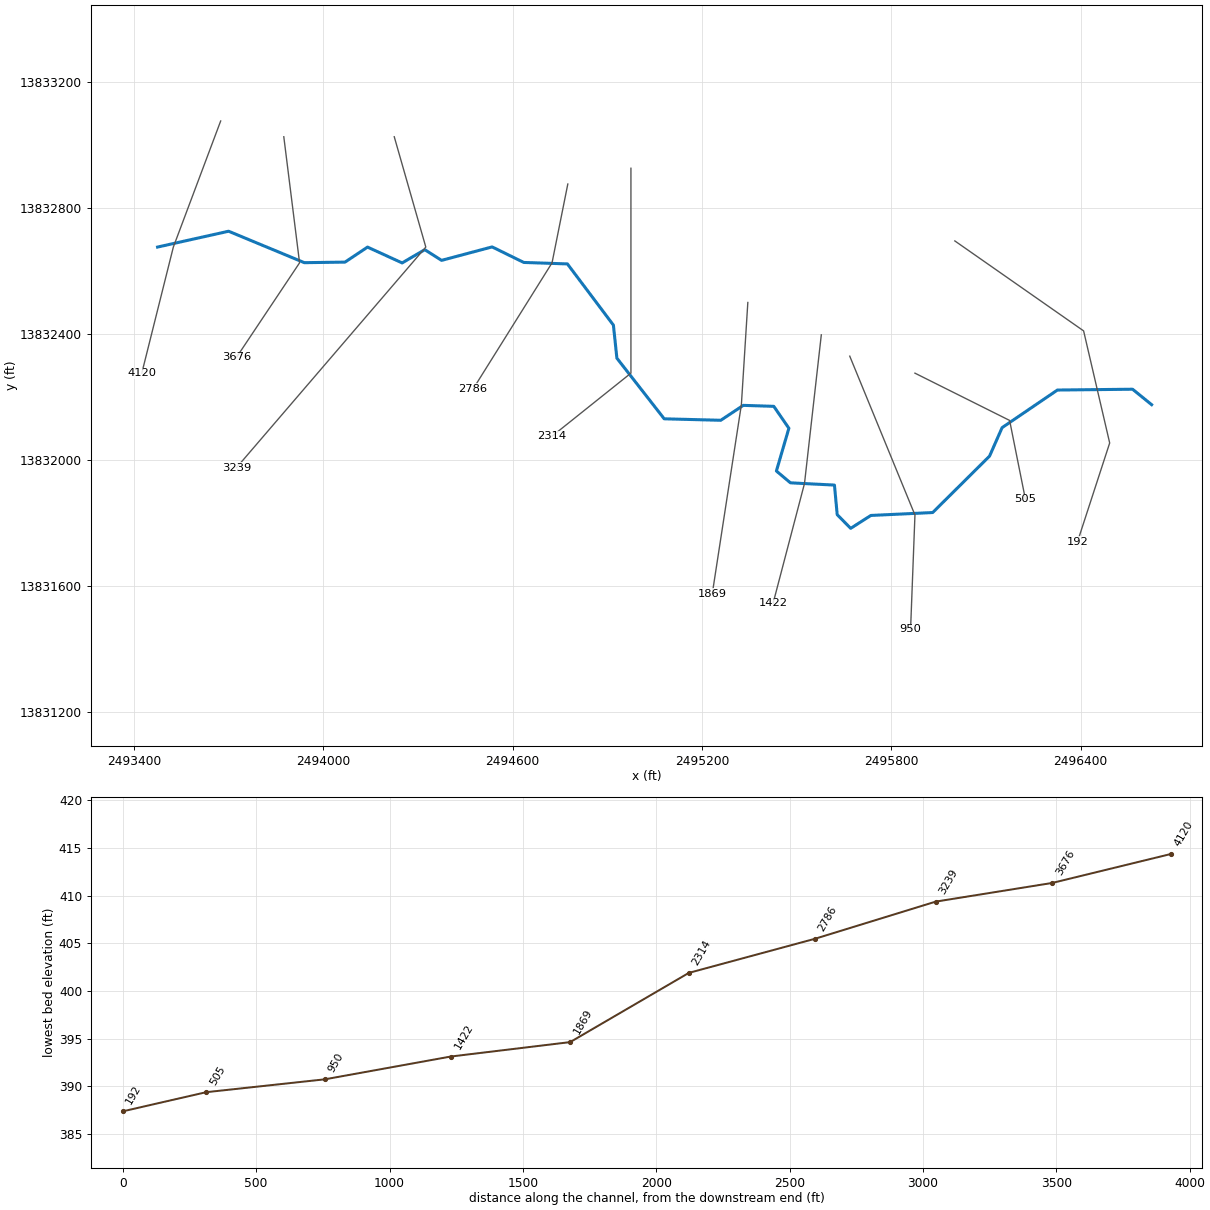
--- StreamM021.prj (project) ---

Proj Title=StreamM021 Base Level Engineering
Current Plan=p01
Default Exp/Contr=0.3,0.1
English Units
Geom File=g01
Flow File=f01
Plan File=p01
BEGIN DESCRIPTION:
StreamM021
END DESCRIPTION:

--- StreamM021.p01 (plan) ---

Plan Title=Multiple Run
Short Identifier=Multiple
Geom File=g01
Flow File=f01
Subcritical Flow
K Sum by GR= 0
Std Step Tol= 0.01
Critical Tol= 0.01
Num of Std Step Trials= 20
Max Error Tol= 0.3
Flow Tol Ratio= 0.001
Split Flow NTrial= 30
Split Flow Tol= 0.02
Split Flow Ratio= 0.02
Log Output Level= 0
Friction Slope Method= 1
Unsteady Friction Slope Method= 2
Unsteady Bridges Friction Slope Method= 1
Parabolic Critical Depth
Global Vel Dist=  1 , 1 , 1
Global Log Level= 0
CheckData=True
Encroach Param= -1, 0, 0, 0
BEGIN DESCRIPTION:
Multiple Run
END DESCRIPTION:

--- StreamM021.f01 (steady flow) ---

Flow Title=Multiple
Number of Profiles=7
Profile Names=10-year,25-year,50-year,1pct_min,100-year,1pct_plu,500-year
River Rch & RM= StreamM021,Reach-1,4120
     942    1552    2115    1397    2787    5560    4787
River Rch & RM= StreamM021,Reach-1,3239
    1053    1741    2379    1573    3139    6264    5412
Boundary for River Rch & Prof#=StreamM021,Reach-1,1
Up Type=0
Dn Type=3
Dn Slope=0.005
Boundary for River Rch & Prof#=StreamM021,Reach-1,2
Up Type=0
Dn Type=3
Dn Slope=0.005
Boundary for River Rch & Prof#=StreamM021,Reach-1,3
Up Type=0
Dn Type=3
Dn Slope=0.005
Boundary for River Rch & Prof#=StreamM021,Reach-1,4
Up Type=0
Dn Type=3
Dn Slope=0.005
Boundary for River Rch & Prof#=StreamM021,Reach-1,5
Up Type=0
Dn Type=3
Dn Slope=0.005
Boundary for River Rch & Prof#=StreamM021,Reach-1,6
Up Type=0
Dn Type=3
Dn Slope=0.005
Boundary for River Rch & Prof#=StreamM021,Reach-1,7
Up Type=0
Dn Type=3
Dn Slope=0.005

--- StreamM021.g01 (geometry) ---

Geom Title=Existing Conditions

River Reach=StreamM021,Reach-1
Reach XY= 30
      2493475.00     13832675.00      2493700.07     13832725.23
      2493940.22     13832625.50      2494069.07     13832627.28
      2494140.40     13832674.90      2494250.04     13832624.69
      2494321.77     13832666.68      2494374.90     13832632.79
      2494535.17     13832675.50      2494635.51     13832626.23
      2494773.75     13832621.55      2494919.46     13832427.42
      2494930.52     13832322.57      2495080.44     13832130.18
      2495259.78     13832125.52      2495330.98     13832172.84
      2495427.72     13832169.72      2495475.53     13832100.13
      2495435.94     13831964.56      2495480.46     13831927.07
      2495619.92     13831919.95      2495628.64     13831826.10
      2495671.30     13831782.68      2495735.43     13831823.61
      2495931.19     13831832.81      2496111.36     13832011.80
      2496151.16     13832102.14      2496326.47     13832221.45
      2496564.60     13832224.04      2496625.00     13832175.00

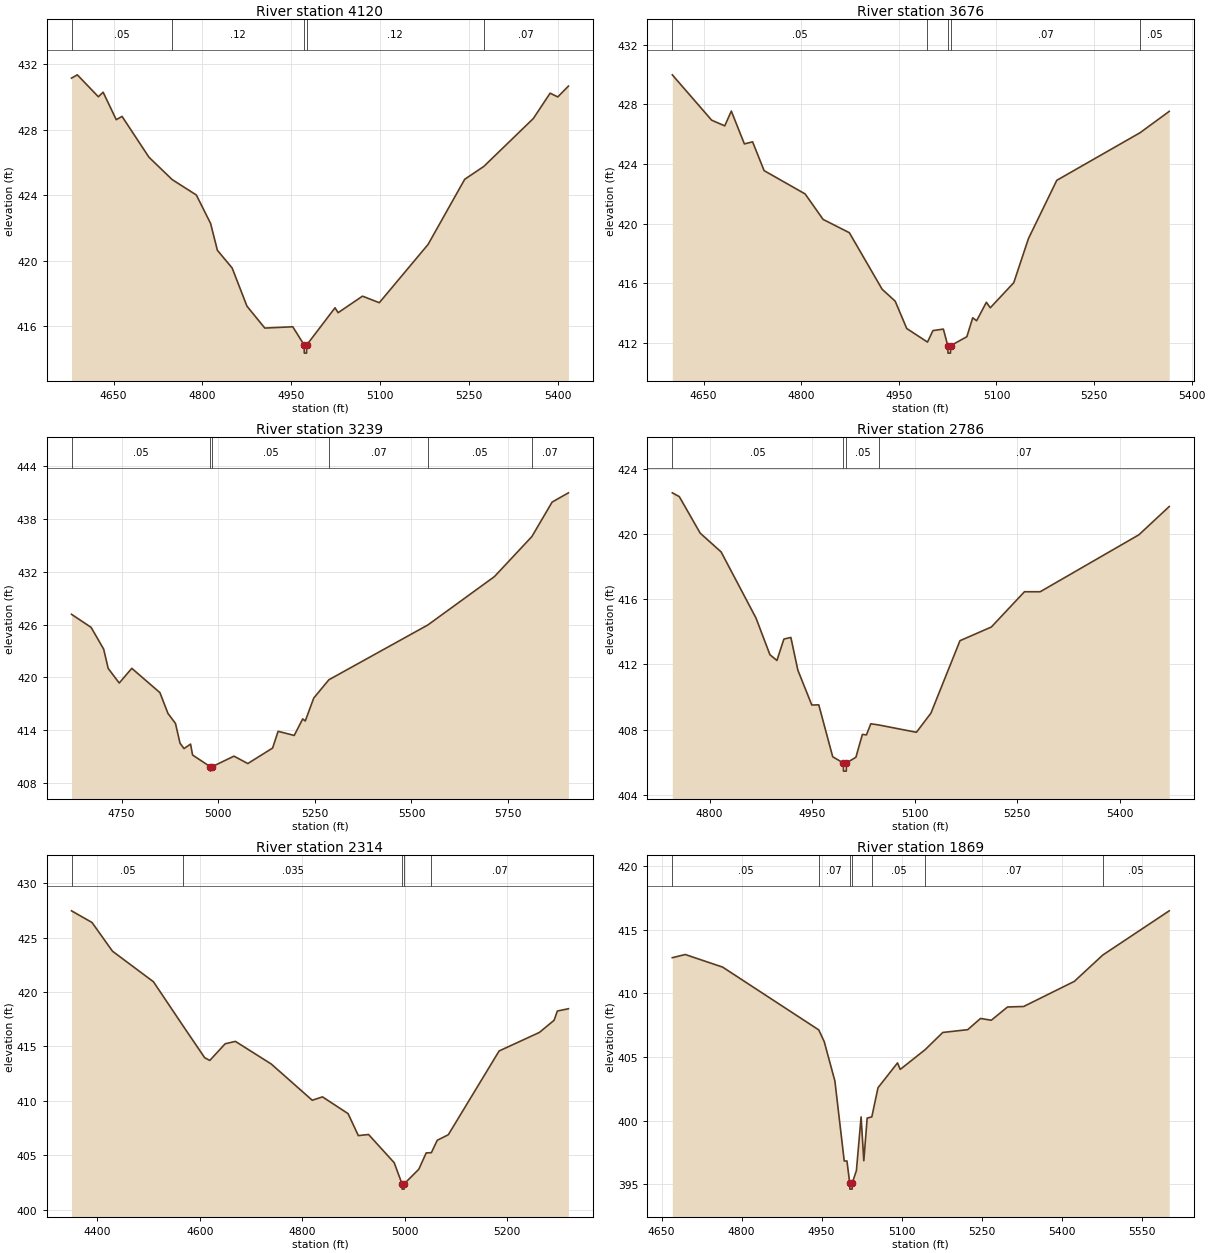
Type RM Length L Ch R = 1,4120,444,444,444
BEGIN DESCRIPTION:
StreamM021 9.0
END DESCRIPTION:
XS GIS Cut Line= 3
      2493675.00     13833074.99      2493525.00     13832675.00
      2493425.00     13832275.00
#Sta/Elev= 30
  4578.8  431.15  4588.6  431.35  4624.2  430.01  4632.2  430.29  4654.4  428.61
  4664.2  428.81  4709.6  426.32  4748.9  424.95  4789.7  424.01  4813.8  422.27
  4825.3  420.63  4850.2  419.55  4875.2  417.22  4905.4  415.88  4952.6  415.96
  4971.8  414.85  4972.1  414.35  4975.9  414.35  4976.2  414.85  5024.0  417.12
  5029.2  416.82  5070.4  417.83  5098.8  417.43  5181.2  420.99  5243.1  424.97
  5275.2  425.75  5359.0  428.68  5387.4  430.23  5400.3  430.00  5418.3  430.66
#Mann=5,-1,0
  4578.8    0.05       0  4748.9    0.12       0  4971.8    0.05       0
  4976.2    0.12       0  5275.2    0.07       0
Bank Sta=4971.8,4976.2
Exp/Cntr=0.3,0.1

Type RM Length L Ch R = 1,3676,437,437,437
BEGIN DESCRIPTION:
StreamM021 8.0
END DESCRIPTION:
XS GIS Cut Line= 3
      2493875.00     13833024.99      2493925.00     13832625.00
      2493724.98     13832324.97
#Sta/Elev= 30
  4601.8  429.97  4662.3  426.93  4682.4  426.55  4692.5  427.54  4712.6  425.34
  4725.2  425.48  4742.9  423.55  4805.9  421.99  4833.6  420.28  4873.9  419.39
  4924.3  415.60  4944.4  414.80  4962.1  412.97  4994.0  412.06  5002.4  412.83
  5018.4  412.93  5025.2  411.82  5025.5  411.32  5029.3  411.32  5029.6  411.82
  5054.5  412.42  5063.5  413.69  5069.5  413.49  5084.5  414.73  5090.5  414.36
  5126.6  416.04  5149.1  418.99  5192.7  422.90  5320.7  426.09  5365.5  427.52
#Mann=5,-1,0
  4601.8    0.05       0  4994.0    0.07       0  5025.2    0.05       0
  5029.6    0.07       0  5320.7    0.05       0
Bank Sta=5025.2,5029.6
Exp/Cntr=0.3,0.1

Type RM Length L Ch R = 1,3239,453,453,453
BEGIN DESCRIPTION:
StreamM021 7.0
END DESCRIPTION:
XS GIS Cut Line= 3
      2494225.01     13833024.96      2494325.00     13832675.00
      2493725.01     13831975.01
#Sta/Elev= 30
  4620.3  427.16  4671.0  425.68  4703.5  423.21  4715.2  421.02  4743.8  419.36
  4776.3  421.03  4849.1  418.27  4869.9  415.91  4889.4  414.77  4901.1  412.53
  4911.5  411.92  4928.4  412.43  4933.6  411.19  4979.4  409.86  4979.7  409.36
  4983.9  409.86  5040.8  411.06  5076.5  410.22  5140.7  411.98  5154.9  413.88
  5196.6  413.41  5218.6  415.29  5225.2  415.05  5247.1  417.65  5286.3  419.73
  5542.4  425.95  5714.7  431.44  5811.7  435.99  5864.0  439.90  5906.2  440.95
#Mann=6,-1,0
  4620.3    0.05       0  4979.4    0.05       0  4983.9    0.05       0
  5286.3    0.07       0  5542.4    0.05       0  5811.7    0.07       0
Bank Sta=4979.4,4983.9
Exp/Cntr=0.3,0.1

Type RM Length L Ch R = 1,2786,472,472,472
BEGIN DESCRIPTION:
StreamM021 6.0
END DESCRIPTION:
XS GIS Cut Line= 3
      2494775.00     13832875.02      2494725.00     13832625.00
      2494474.98     13832224.97
#Sta/Elev= 30
  4745.4  422.51  4755.6  422.28  4786.2  420.04  4816.8  418.89  4867.8  414.84
  4888.2  412.59  4898.4  412.24  4908.6  413.55  4918.8  413.65  4929.0  411.65
  4949.4  409.51  4959.6  409.52  4980.0  406.34  4995.5  405.96  4995.8  405.46
  4999.8  405.46  5000.1  405.96  5013.9  406.31  5023.4  407.71  5029.3  407.68
  5035.7  408.36  5047.1  408.29  5102.4  407.84  5123.6  409.01  5166.1  413.45
  5212.0  414.29  5260.4  416.45  5283.4  416.45  5427.8  419.94  5472.1  421.67
#Mann=4,-1,0
  4745.4    0.05       0  4995.5    0.05       0  5000.1    0.05       0
  5047.1    0.07       0
Bank Sta=4995.5,5000.1
Exp/Cntr=0.3,0.1

Type RM Length L Ch R = 1,2314,445,445,445
BEGIN DESCRIPTION:
StreamM021 5.0
END DESCRIPTION:
XS GIS Cut Line= 3
      2494975.00     13832925.05      2494975.00     13832275.00
      2494725.00     13832075.00
#Sta/Elev= 30
  4349.7  427.47  4389.7  426.40  4429.7  423.76  4509.7  420.95  4567.6  416.89
  4609.7  413.97  4619.7  413.72  4649.7  415.25  4669.7  415.47  4739.7  413.39
  4819.7  410.06  4839.7  410.37  4889.7  408.83  4909.7  406.81  4929.7  406.91
  4979.7  404.32  4994.9  402.39  4995.2  401.89  4999.2  401.89  4999.6  402.39
  5027.8  403.72  5042.2  405.22  5052.3  405.24  5063.8  406.38  5085.4  406.89
  5184.6  414.59  5263.1  416.29  5291.9  417.41  5298.3  418.26  5319.9  418.47
#Mann=5,-1,0
  4349.7    0.05       0  4567.6   0.035       0  4994.9   0.035       0
  4999.6   0.035       0  5052.3    0.07       0
Bank Sta=4994.9,4999.6
Exp/Cntr=0.3,0.1

Type RM Length L Ch R = 1,1869,447,447,447
BEGIN DESCRIPTION:
StreamM021 4.0
END DESCRIPTION:
XS GIS Cut Line= 3
      2495345.43     13832499.21      2495325.00     13832175.00
      2495232.77     13831575.40
#Sta/Elev= 30
  4670.2  412.80  4694.5  413.05  4764.6  412.06  4944.8  407.13  4955.0  406.21
  4975.0  403.12  4992.5  396.84  4997.6  396.84  5002.7  395.13  5003.1  394.63
  5007.3  394.63  5007.6  395.13  5015.3  396.08  5024.1  400.30  5029.2  396.86
  5035.5  400.21  5044.2  400.30  5055.8  402.59  5092.4  404.54  5097.5  404.03
  5144.2  405.58  5177.2  406.93  5224.0  407.15  5248.0  408.03  5268.2  407.89
  5298.6  408.93  5328.9  408.97  5423.8  410.94  5477.2  413.01  5601.7  416.48
#Mann=7,-1,0
  4670.2    0.05       0  4944.8    0.07       0  5002.7    0.05       0
  5007.6    0.07       0  5044.2    0.05       0  5144.2    0.07       0
  5477.2    0.05       0
Bank Sta=5002.7,5007.6
Exp/Cntr=0.3,0.1

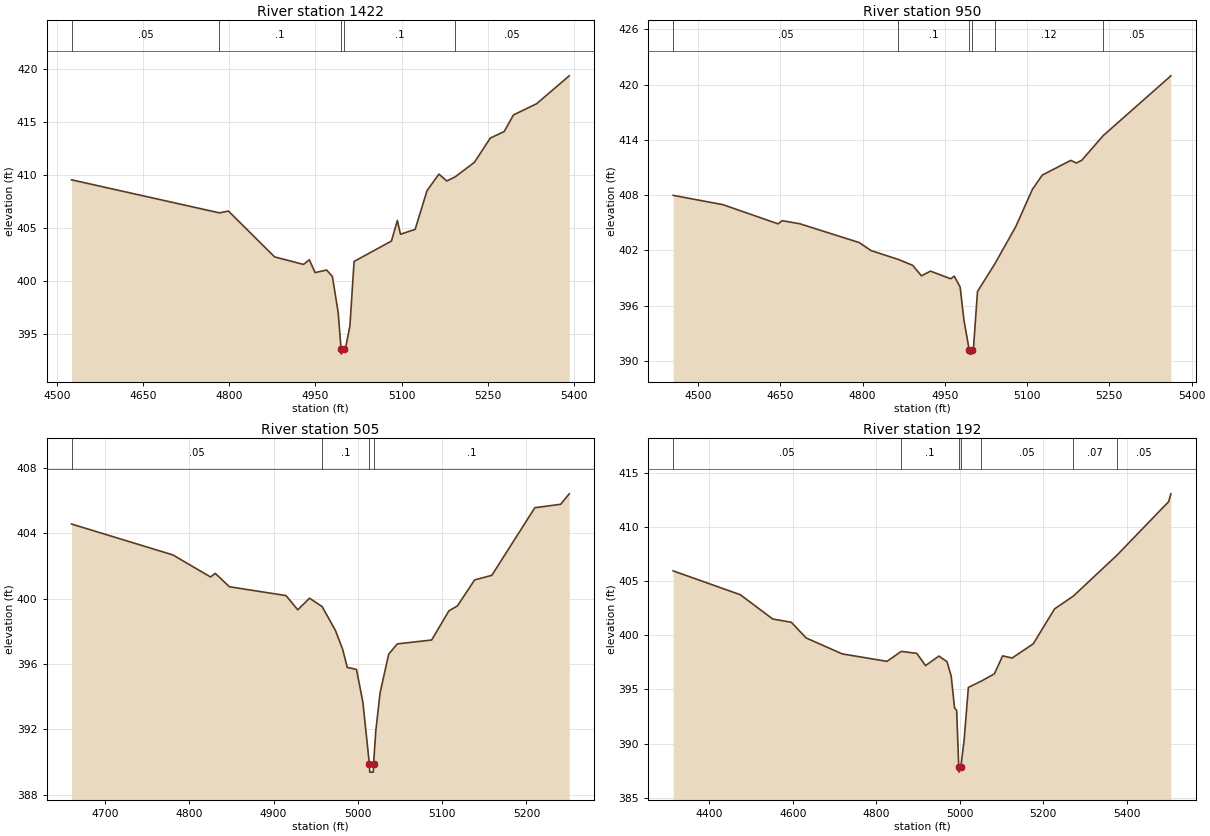
Type RM Length L Ch R = 1,1422,472,472,472
BEGIN DESCRIPTION:
StreamM021 3.0
END DESCRIPTION:
XS GIS Cut Line= 3
      2495578.26     13832396.56      2495525.00     13831925.00
      2495425.55     13831545.37
#Sta/Elev= 30
  4525.1  409.58  4782.5  406.46  4798.4  406.63  4878.9  402.30  4929.2  401.59
  4939.3  402.03  4949.3  400.82  4969.5  401.06  4979.5  400.45  4989.6  397.05
  4994.6  393.62  4995.0  393.12  4999.6  393.62  5002.2  393.62  5010.0  395.77
  5017.3  401.87  5082.4  403.80  5092.7  405.74  5098.1  404.44  5123.7  404.90
  5144.4  408.56  5165.1  410.12  5178.9  409.47  5193.7  409.87  5227.1  411.24
  5254.5  413.52  5278.8  414.14  5294.9  415.70  5335.4  416.77  5392.1  419.40
#Mann=5,-1,0
  4525.1    0.05       0  4782.5     0.1       0  4994.6    0.05       0
  4999.6     0.1       0  5193.7    0.05       0
Bank Sta=4994.6,4999.6
Exp/Cntr=0.3,0.1

Type RM Length L Ch R = 1,950,445,445,445
BEGIN DESCRIPTION:
StreamM021 2.0
END DESCRIPTION:
XS GIS Cut Line= 3
      2495668.40     13832328.96      2495875.00     13831825.00
      2495861.17     13831462.73
#Sta/Elev= 30
  4454.9  407.97  4545.6  406.96  4646.0  404.88  4653.7  405.22  4686.1  404.88
  4794.2  402.84  4815.8  401.97  4865.4  401.01  4891.5  400.37  4907.5  399.23
  4923.9  399.74  4960.9  398.91  4967.1  399.20  4978.0  398.01  4984.9  394.43
  4994.4  391.23  4994.8  390.73  4999.0  390.73  4999.4  391.23  5002.1  391.23
  5009.6  397.53  5041.5  400.56  5079.6  404.60  5109.6  408.61  5127.7  410.17
  5179.7  411.77  5189.7  411.48  5199.7  411.78  5238.8  414.46  5362.1  420.95
#Mann=6,-1,0
  4454.9    0.05       0  4865.4     0.1       0  4994.4    0.05       0
  4999.4     0.1       0  5041.5    0.12       0  5238.8    0.05       0
Bank Sta=4994.4,4999.4
Exp/Cntr=0.3,0.1

Type RM Length L Ch R = 1,505,313,313,313
BEGIN DESCRIPTION:
StreamM021 1.0
END DESCRIPTION:
XS GIS Cut Line= 3
      2495874.96     13832275.02      2496175.00     13832125.00
      2496225.00     13831875.00
#Sta/Elev= 30
  4660.3  404.57  4780.5  402.68  4825.2  401.33  4830.8  401.55  4847.6  400.73
  4914.7  400.19  4928.7  399.32  4942.6  400.03  4957.5  399.52  4973.4  398.05
  4981.8  396.92  4987.4  395.79  4998.3  395.67  5005.9  393.67  5013.6  389.88
  5014.0  389.38  5018.3  389.38  5018.6  389.88  5021.2  391.89  5026.3  394.23
  5036.5  396.60  5046.7  397.23  5087.5  397.47  5107.9  399.25  5118.1  399.56
  5138.5  401.15  5158.9  401.43  5209.9  405.57  5240.5  405.78  5250.7  406.42
#Mann=4,-1,0
  4660.3    0.05       0  4957.5     0.1       0  5013.6    0.05       0
  5018.6     0.1       0
Bank Sta=5013.6,5018.6
Exp/Cntr=0.3,0.1

Type RM Length L Ch R = 1,192,0,0,0
BEGIN DESCRIPTION:
H21208
END DESCRIPTION:
XS GIS Cut Line= 4
      2496001.39     13832694.49      2496409.46     13832409.09
      2496492.08     13832053.57      2496390.02     13831739.92
#Sta/Elev= 30
  4313.1  405.94  4474.0  403.74  4551.6  401.50  4596.1  401.20  4631.8  399.75
  4718.2  398.28  4825.5  397.59  4859.7  398.51  4897.0  398.33  4917.9  397.20
  4949.9  398.08  4969.3  397.56  4979.5  396.23  4987.4  393.30  4992.5  393.07
  4997.5  387.87  4997.9  387.37  5002.6  387.87  5010.3  390.29  5020.6  395.19
  5051.1  395.76  5082.9  396.44  5102.7  398.10  5125.5  397.90  5176.1  399.21
  5227.1  402.43  5272.3  403.62  5376.8  407.39  5500.6  412.33  5505.9  413.05
#Mann=7,-1,0
  4313.1    0.05       0  4859.7     0.1       0  4997.5    0.05       0
  5002.6     0.1       0  5051.1    0.05       0  5272.3    0.07       0
  5376.8    0.05       0
Bank Sta=4997.5,5002.6
Exp/Cntr=0.3,0.1

Chan Stop Cuts=-1