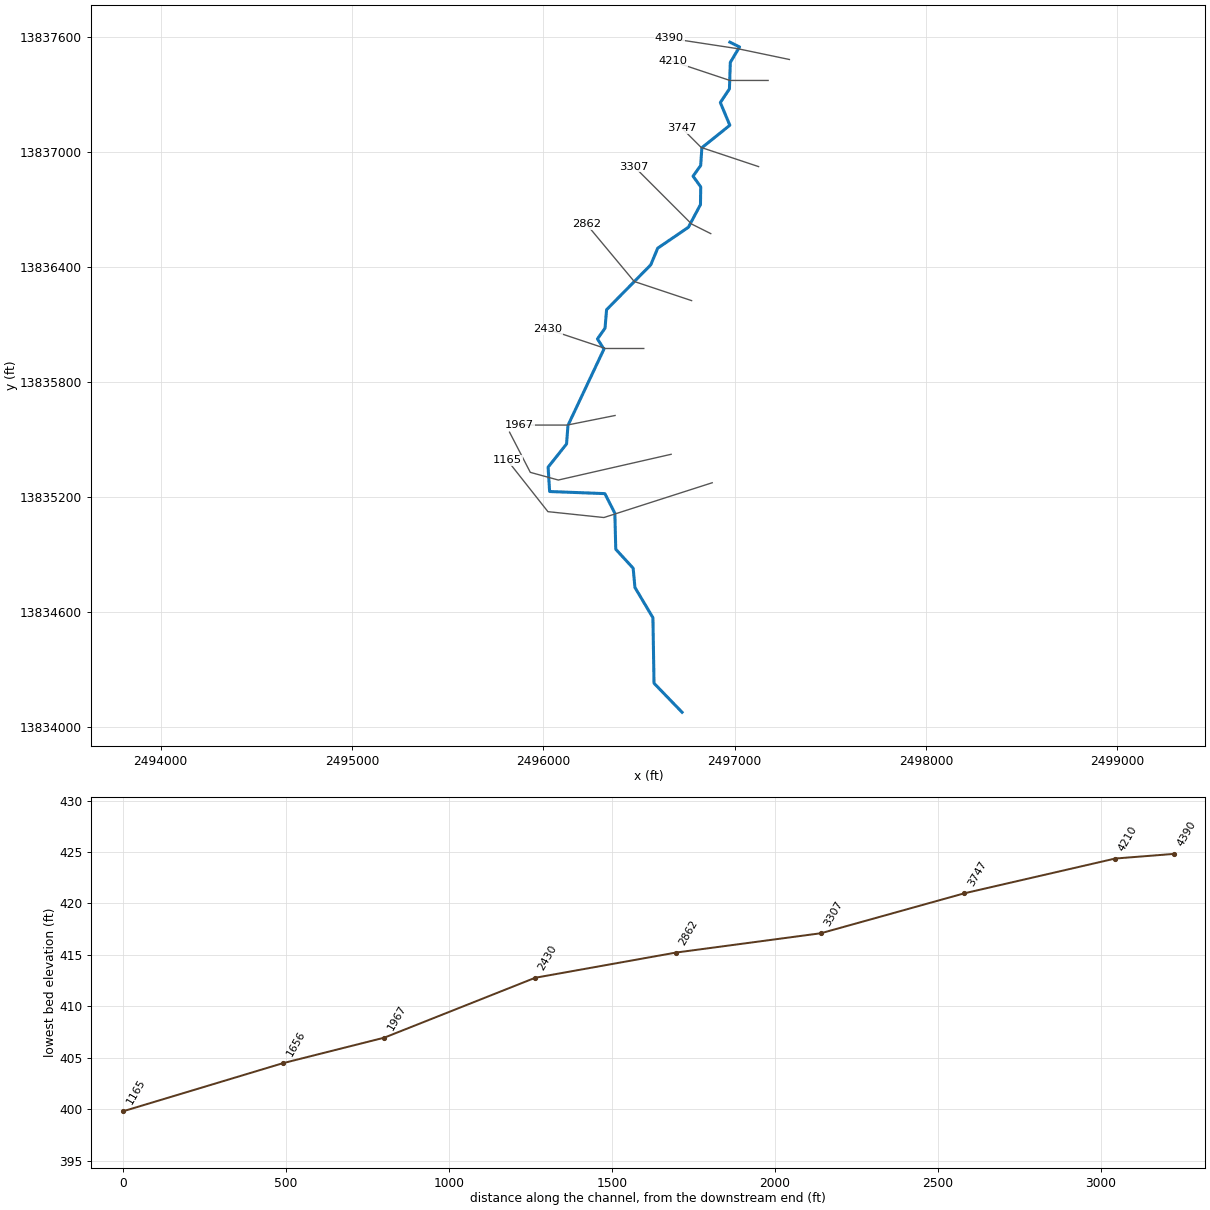
--- StreamM022.prj (project) ---

Proj Title=StreamM022 Base Level Engineering
Current Plan=p01
Default Exp/Contr=0.3,0.1
English Units
Geom File=g01
Flow File=f01
Plan File=p01
BEGIN DESCRIPTION:
StreamM022
END DESCRIPTION:

--- StreamM022.p01 (plan) ---

Plan Title=Multiple Run
Short Identifier=Multiple
Geom File=g01
Flow File=f01
Subcritical Flow
K Sum by GR= 0
Std Step Tol= 0.01
Critical Tol= 0.01
Num of Std Step Trials= 20
Max Error Tol= 0.3
Flow Tol Ratio= 0.001
Split Flow NTrial= 30
Split Flow Tol= 0.02
Split Flow Ratio= 0.02
Log Output Level= 0
Friction Slope Method= 1
Unsteady Friction Slope Method= 2
Unsteady Bridges Friction Slope Method= 1
Parabolic Critical Depth
Global Vel Dist=  1 , 1 , 1
Global Log Level= 0
CheckData=True
Encroach Param= -1, 0, 0, 0
BEGIN DESCRIPTION:
Multiple Run
END DESCRIPTION:

--- StreamM022.f01 (steady flow) ---

Flow Title=Multiple
Number of Profiles=7
Profile Names=10-year,25-year,50-year,1pct_min,100-year,1pct_plu,500-year
River Rch & RM= StreamM022,Reach-1,4390
     508     805    1068     688    1373    2740    2244
Boundary for River Rch & Prof#=StreamM022,Reach-1,1
Up Type=0
Dn Type=3
Dn Slope=0.005
Boundary for River Rch & Prof#=StreamM022,Reach-1,2
Up Type=0
Dn Type=3
Dn Slope=0.005
Boundary for River Rch & Prof#=StreamM022,Reach-1,3
Up Type=0
Dn Type=3
Dn Slope=0.005
Boundary for River Rch & Prof#=StreamM022,Reach-1,4
Up Type=0
Dn Type=3
Dn Slope=0.005
Boundary for River Rch & Prof#=StreamM022,Reach-1,5
Up Type=0
Dn Type=3
Dn Slope=0.005
Boundary for River Rch & Prof#=StreamM022,Reach-1,6
Up Type=0
Dn Type=3
Dn Slope=0.005
Boundary for River Rch & Prof#=StreamM022,Reach-1,7
Up Type=0
Dn Type=3
Dn Slope=0.005

--- StreamM022.g01 (geometry) ---

Geom Title=Existing Conditions

River Reach=StreamM022,Reach-1
Reach XY= 30
      2496975.00     13837575.00      2497025.67     13837550.00
      2496977.27     13837469.09      2496972.70     13837330.93
      2496925.10     13837259.60      2496974.76     13837141.02
      2496828.61     13837023.51      2496822.44     13836930.90
      2496782.56     13836875.00      2496822.64     13836819.11
      2496821.32     13836726.59      2496758.37     13836608.29
      2496597.86     13836498.84      2496561.36     13836411.80
      2496330.52     13836177.43      2496322.45     13836080.89
      2496282.79     13836024.90      2496316.76     13835971.77
      2496128.83     13835573.41      2496121.38     13835476.50
      2496024.93     13835354.99      2496032.90     13835227.91
      2496321.65     13835216.91      2496373.81     13835114.52
      2496378.55     13834926.47      2496469.46     13834827.42
      2496478.83     13834726.59      2496572.76     13834569.07
      2496578.53     13834226.46      2496725.00     13834075.00

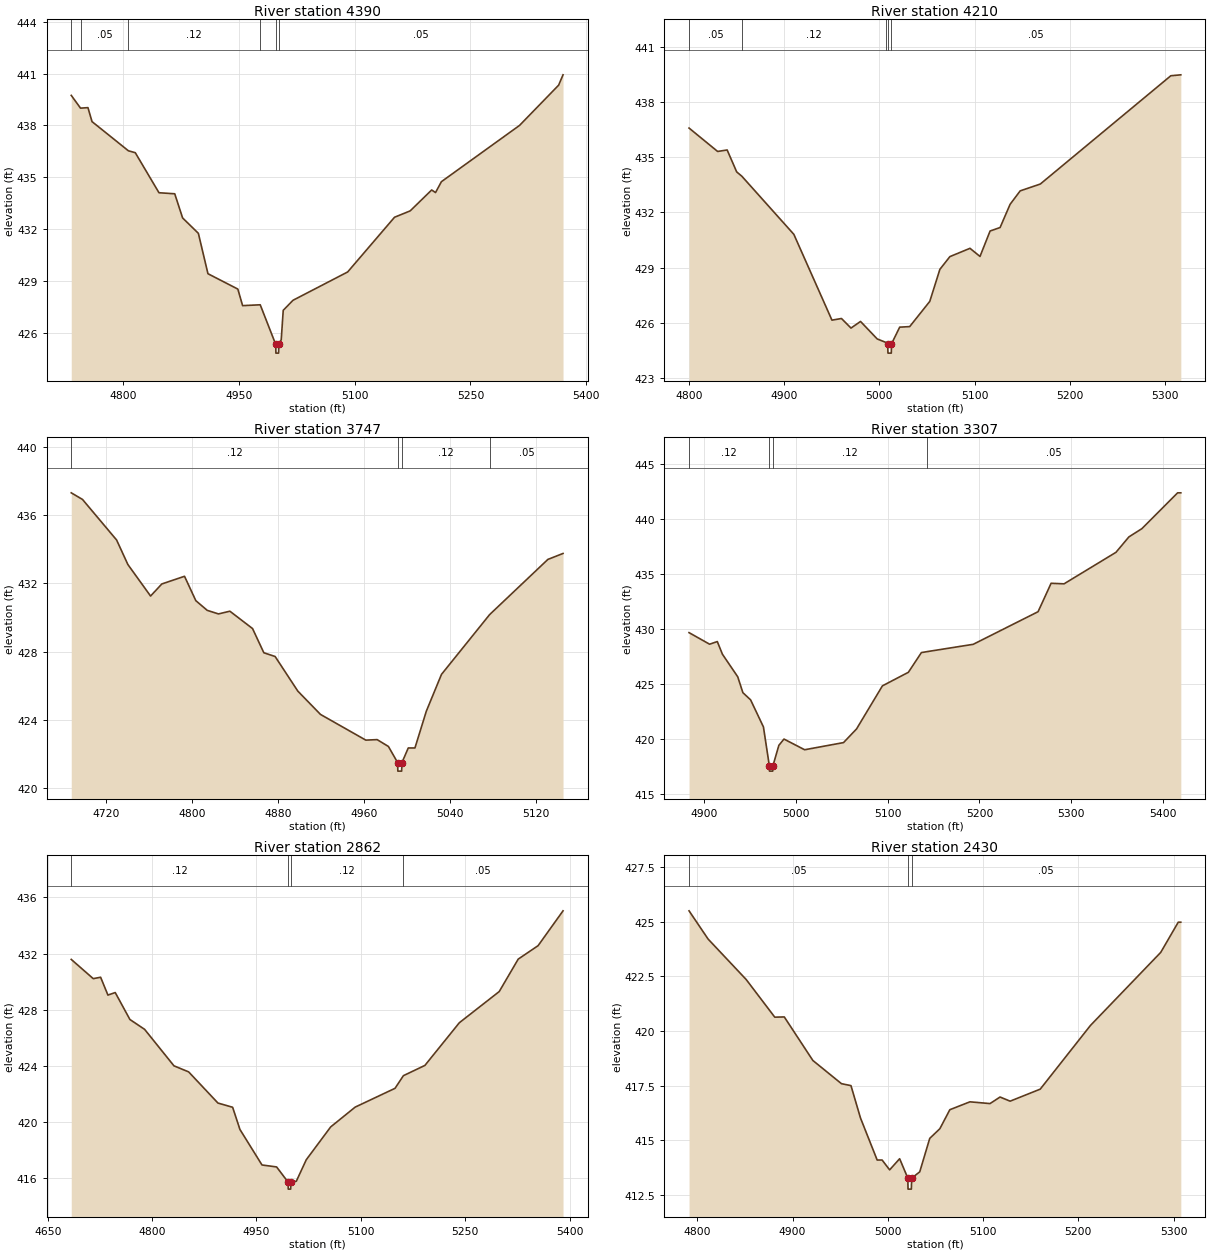
Type RM Length L Ch R = 1,4390,180,180,180
BEGIN DESCRIPTION:
H21211
END DESCRIPTION:
XS GIS Cut Line= 3
      2497286.17     13837484.46      2497014.88     13837541.08
      2496659.32     13837595.24
#Sta/Elev= 30
  4733.1  439.74  4745.1  439.00  4754.7  439.03  4760.0  438.22  4807.1  436.53
  4816.0  436.42  4846.7  434.10  4867.1  434.04  4877.3  432.64  4897.7  431.75
  4910.1  429.41  4948.8  428.52  4955.0  427.56  4977.8  427.61  4997.9  425.31
  4998.1  424.81  5001.6  424.81  5001.9  425.31  5005.0  425.59  5007.6  427.29
  5020.2  427.87  5091.0  429.51  5151.7  432.68  5172.0  433.05  5199.8  434.26
  5204.8  434.11  5212.4  434.74  5313.6  438.00  5364.2  440.33  5369.9  440.93
#Mann=6,-1,0
  4733.1    0.12       0  4745.1    0.05       0  4807.1    0.12       0
  4977.8    0.05       0  4997.9    0.05       0  5001.9    0.05       0
Bank Sta=4997.9,5001.9
Exp/Cntr=0.3,0.1

Type RM Length L Ch R = 1,4210,463,463,463
BEGIN DESCRIPTION:
StreamM022 8.0
END DESCRIPTION:
XS GIS Cut Line= 3
      2497175.01     13837375.00      2496975.00     13837375.00
      2496675.03     13837474.99
#Sta/Elev= 30
  4800.3  436.58  4830.3  435.31  4840.3  435.39  4850.3  434.20  4855.8  433.96
  4910.3  430.81  4950.3  426.15  4960.3  426.24  4970.3  425.72  4980.3  426.08
  4997.8  425.13  5007.0  424.94  5008.8  424.86  5009.1  424.36  5012.6  424.36
  5012.8  424.86  5021.4  425.77  5031.9  425.80  5053.0  427.17  5063.6  428.91
  5074.1  429.60  5095.2  430.05  5105.7  429.61  5116.3  430.99  5126.8  431.18
  5137.3  432.44  5147.9  433.17  5169.0  433.54  5306.0  439.42  5316.5  439.47
#Mann=5,-1,0
  4800.3    0.05       0  4855.8    0.12       0  5007.0    0.05       0
  5008.8    0.05       0  5012.8    0.05       0
Bank Sta=5008.8,5012.8
Exp/Cntr=0.3,0.1

Type RM Length L Ch R = 1,3747,440,440,440
BEGIN DESCRIPTION:
StreamM022 7.0
END DESCRIPTION:
XS GIS Cut Line= 3
      2497125.00     13836925.00      2496825.00     13837025.00
      2496725.03     13837124.97
#Sta/Elev= 30
  4687.7  437.32  4698.2  436.93  4729.9  434.55  4740.4  433.11  4761.5  431.26
  4772.0  431.97  4793.1  432.42  4803.6  430.99  4814.2  430.42  4824.7  430.21
  4835.3  430.37  4856.4  429.35  4866.9  427.93  4877.4  427.71  4898.5  425.68
  4919.6  424.31  4961.8  422.80  4972.3  422.83  4982.8  422.43  4991.4  421.48
  4991.6  420.98  4995.1  420.98  4995.4  421.48  5001.3  422.34  5007.5  422.34
  5018.1  424.50  5032.2  426.66  5077.0  430.17  5131.2  433.41  5145.3  433.76
#Mann=4,-1,0
  4687.7    0.12       0  4991.4    0.05       0  4995.4    0.12       0
  5077.0    0.05       0
Bank Sta=4991.4,4995.4
Exp/Cntr=0.3,0.1

Type RM Length L Ch R = 1,3307,445,445,445
BEGIN DESCRIPTION:
StreamM022 6.0
END DESCRIPTION:
XS GIS Cut Line= 3
      2496875.03     13836574.98      2496775.00     13836625.00
      2496475.00     13836925.00
#Sta/Elev= 30
  4883.4  429.67  4905.8  428.62  4914.2  428.86  4919.8  427.71  4936.5  425.66
  4942.1  424.22  4950.5  423.57  4964.5  421.11  4970.9  417.60  4971.1  417.10
  4974.6  417.10  4974.9  417.60  4981.3  419.44  4986.9  420.01  5009.4  419.04
  5051.8  419.69  5066.0  420.93  5094.2  424.84  5122.5  426.07  5136.7  427.86
  5143.2  427.95  5193.2  428.61  5263.9  431.57  5278.1  434.15  5292.2  434.10
  5348.8  436.96  5362.9  438.36  5377.1  439.11  5416.0  442.36  5419.5  442.36
#Mann=4,-1,0
  4883.4    0.12       0  4970.9    0.05       0  4974.9    0.12       0
  5143.2    0.05       0
Bank Sta=4970.9,4974.9
Exp/Cntr=0.3,0.1

Type RM Length L Ch R = 1,2862,432,432,432
BEGIN DESCRIPTION:
StreamM022 5.0
END DESCRIPTION:
XS GIS Cut Line= 3
      2496775.00     13836225.00      2496475.00     13836325.00
      2496225.02     13836624.97
#Sta/Elev= 30
  4683.8  431.58  4715.4  430.21  4726.0  430.31  4736.5  429.04  4747.0  429.22
  4768.1  427.30  4789.2  426.60  4831.4  424.00  4852.5  423.57  4894.6  421.35
  4915.7  421.05  4926.2  419.47  4957.9  416.94  4978.9  416.80  4995.4  415.72
  4995.6  415.22  4999.1  415.22  4999.4  415.72  5007.2  415.78  5021.5  417.31
  5056.6  419.65  5091.8  421.06  5149.1  422.40  5161.1  423.30  5192.0  424.03
  5241.5  427.07  5298.8  429.29  5326.1  431.60  5354.7  432.56  5390.5  435.04
#Mann=4,-1,0
  4683.8    0.12       0  4995.4    0.05       0  4999.4    0.12       0
  5161.1    0.05       0
Bank Sta=4995.4,4999.4
Exp/Cntr=0.3,0.1

Type RM Length L Ch R = 1,2430,463,463,463
BEGIN DESCRIPTION:
StreamM022 4.0
END DESCRIPTION:
XS GIS Cut Line= 3
      2496525.04     13835975.00      2496325.00     13835975.00
      2496024.97     13836075.01
#Sta/Elev= 30
  4791.3  425.49  4811.3  424.20  4851.3  422.35  4881.3  420.63  4891.3  420.64
  4921.3  418.65  4951.3  417.59  4961.3  417.50  4971.3  416.02  4988.8  414.10
  4994.0  414.10  5001.9  413.65  5012.4  414.16  5021.0  413.27  5021.2  412.77
  5024.7  412.77  5025.0  413.27  5033.5  413.56  5044.0  415.09  5054.6  415.53
  5065.1  416.40  5086.2  416.76  5107.3  416.68  5117.8  416.98  5128.4  416.79
  5160.0  417.34  5212.7  420.25  5286.5  423.59  5304.9  424.97  5307.6  424.97
#Mann=3,-1,0
  4791.3    0.05       0  5021.0    0.05       0  5025.0    0.05       0
Bank Sta=5021,5025
Exp/Cntr=0.3,0.1

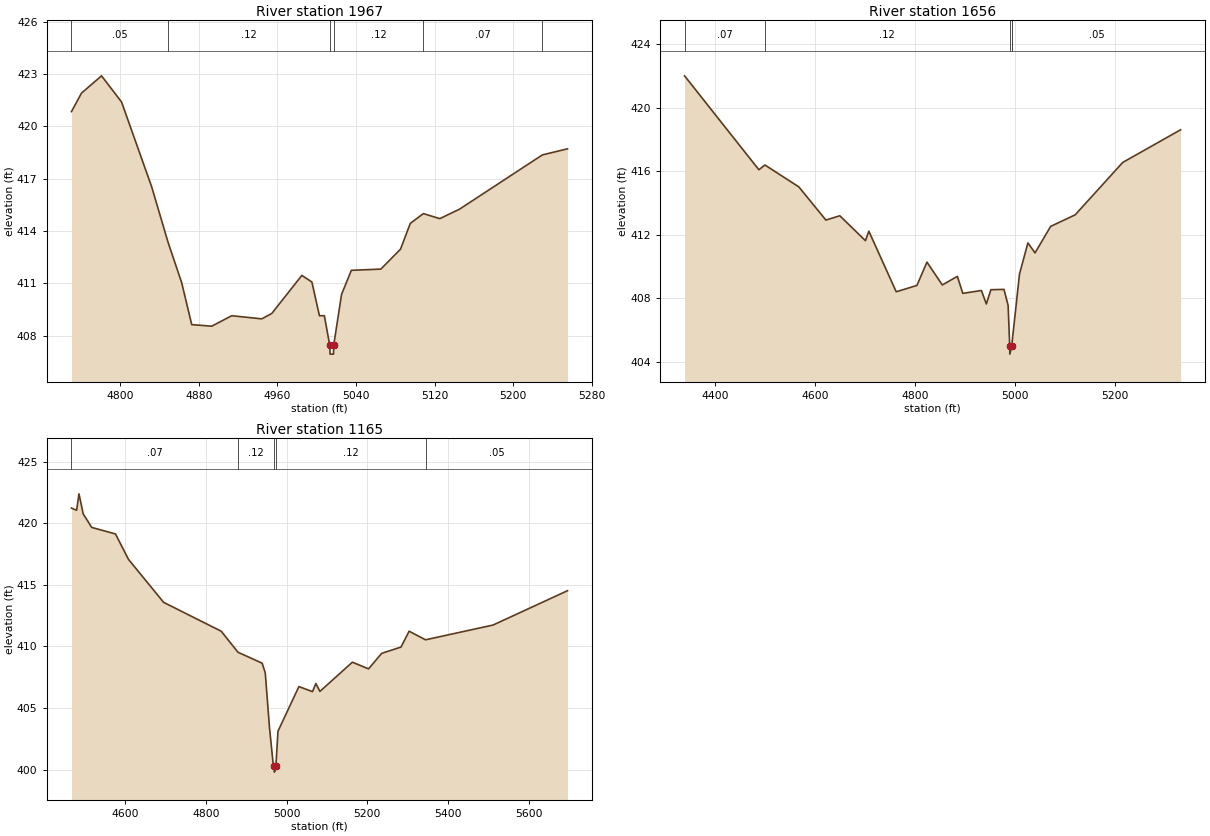
Type RM Length L Ch R = 1,1967,311,311,311
BEGIN DESCRIPTION:
StreamM022 3.0
END DESCRIPTION:
XS GIS Cut Line= 3
      2496374.98     13835625.00      2496125.00     13835575.00
      2495875.03     13835575.00
#Sta/Elev= 30
  4750.3  420.84  4760.5  421.90  4780.9  422.89  4801.3  421.39  4831.9  416.54
  4848.7  413.34  4862.5  411.04  4872.7  408.64  4893.1  408.55  4913.4  409.15
  4944.0  408.97  4954.2  409.28  4984.8  411.46  4995.0  411.08  5002.7  409.15
  5007.7  409.15  5013.2  407.45  5013.5  406.95  5017.0  406.95  5017.2  407.45
  5025.2  410.37  5035.2  411.75  5065.2  411.82  5085.2  412.96  5095.2  414.44
  5108.5  415.00  5125.2  414.71  5145.2  415.25  5229.6  418.36  5255.2  418.71
#Mann=6,-1,0
  4750.3    0.05       0  4848.7    0.12       0  5013.2    0.05       0
  5017.2    0.12       0  5108.5    0.07       0  5229.6    0.05       0
Bank Sta=5013.2,5017.2
Exp/Cntr=0.3,0.1

Type RM Length L Ch R = 1,1656,491,491,491
BEGIN DESCRIPTION:
H21210
END DESCRIPTION:
XS GIS Cut Line= 4
      2496668.07     13835422.38      2496078.21     13835287.89
      2495931.93     13835328.00      2495823.42     13835537.95
#Sta/Elev= 30
  4339.3  422.01  4488.1  416.09  4500.2  416.39  4568.1  415.01  4622.2  412.92
  4650.1  413.19  4701.4  411.62  4708.2  412.22  4763.0  408.40  4804.5  408.80
  4824.5  410.27  4855.3  408.83  4885.4  409.37  4896.3  408.30  4933.5  408.48
  4943.4  407.63  4952.5  408.53  4978.7  408.55  4987.0  407.54  4990.2  404.97
  4990.4  404.47  4994.2  404.97  4994.8  405.17  5009.8  409.52  5026.6  411.48
  5040.9  410.85  5072.1  412.52  5121.3  413.25  5216.4  416.55  5332.3  418.61
#Mann=5,-1,0
  4339.3    0.07       0  4500.2    0.12       0  4990.2    0.05       0
  4994.2    0.12       0  4994.8    0.05       0
Bank Sta=4990.2,4994.2
Exp/Cntr=0.3,0.1

Type RM Length L Ch R = 1,1165,0,0,0
BEGIN DESCRIPTION:
H21209
END DESCRIPTION:
XS GIS Cut Line= 4
      2496882.75     13835273.73      2496316.51     13835092.06
      2496023.95     13835122.73      2495812.30     13835390.82
#Sta/Elev= 30
  4466.1  421.24  4478.9  421.07  4484.7  422.40  4495.2  420.77  4516.3  419.67
  4575.3  419.14  4607.4  417.08  4694.8  413.58  4837.5  411.24  4879.1  409.53
  4939.1  408.64  4946.8  407.85  4957.3  403.40  4966.0  400.58  4969.2  400.29
  4969.5  399.79  4973.2  400.29  4978.3  403.11  5030.2  406.74  5064.0  406.33
  5072.3  406.99  5082.4  406.35  5162.8  408.72  5203.1  408.18  5235.5  409.44
  5283.5  409.95  5303.6  411.24  5344.3  410.54  5511.8  411.74  5696.5  414.53
#Mann=5,-1,0
  4466.1    0.07       0  4879.1    0.12       0  4969.2    0.05       0
  4973.2    0.12       0  5344.3    0.05       0
Bank Sta=4969.2,4973.2
Exp/Cntr=0.3,0.1

Chan Stop Cuts=-1