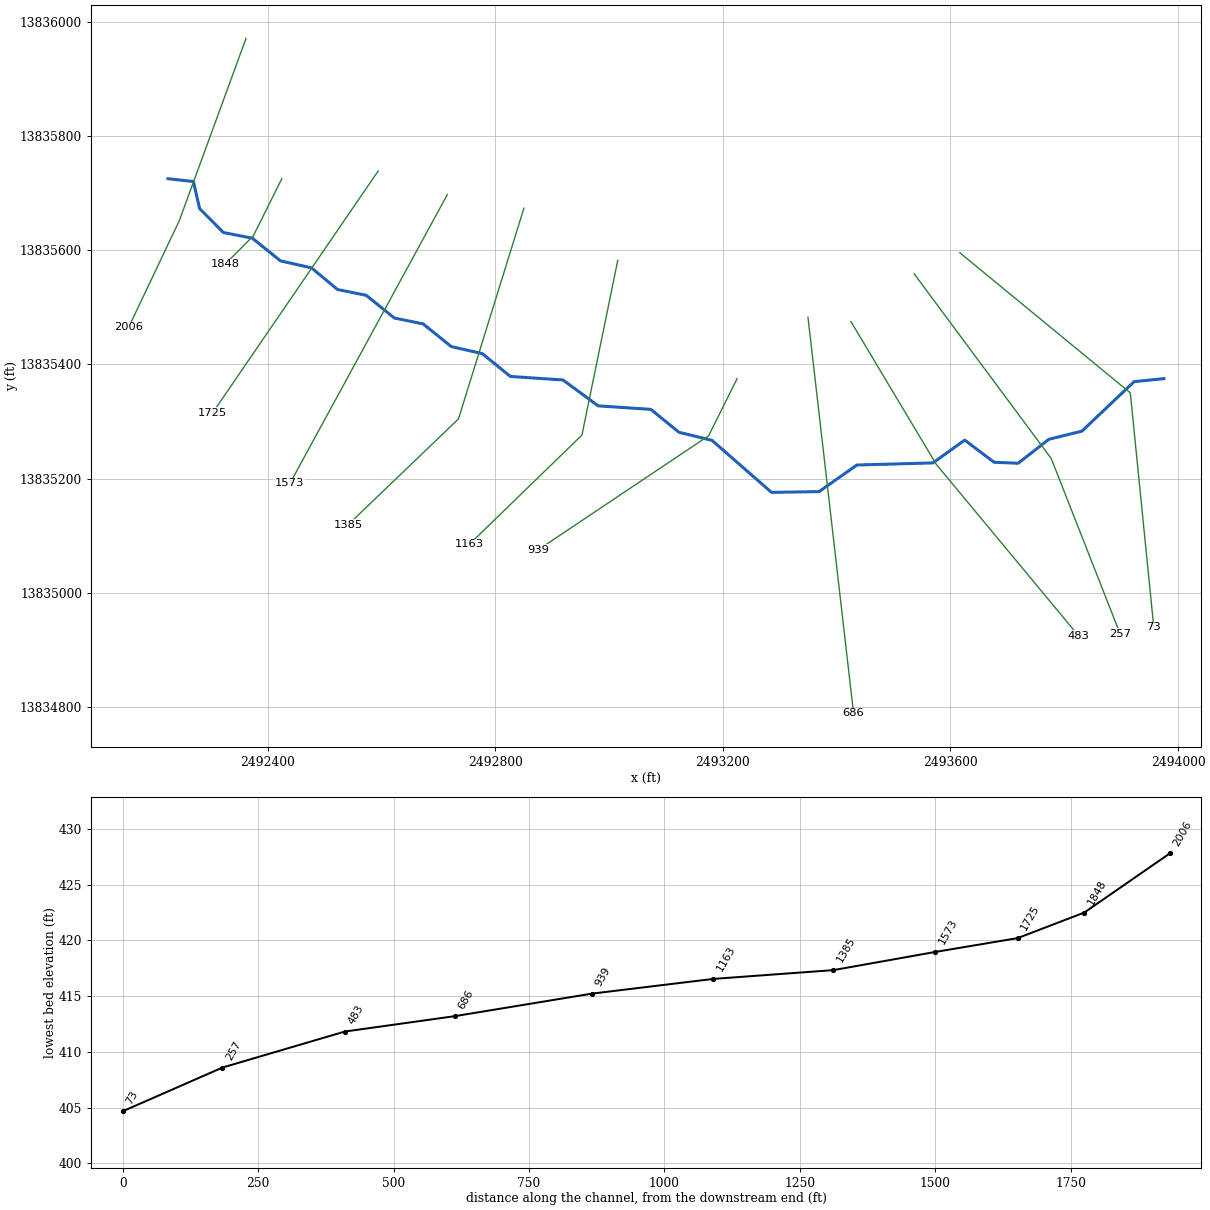
--- StreamM023.prj (project) ---

Proj Title=StreamM023 Base Level Engineering
Current Plan=p01
Default Exp/Contr=0.3,0.1
English Units
Geom File=g01
Flow File=f01
Plan File=p01
BEGIN DESCRIPTION:
StreamM023
END DESCRIPTION:

--- StreamM023.p01 (plan) ---

Plan Title=Multiple Run
Short Identifier=Multiple
Geom File=g01
Flow File=f01
Subcritical Flow
K Sum by GR= 0
Std Step Tol= 0.01
Critical Tol= 0.01
Num of Std Step Trials= 20
Max Error Tol= 0.3
Flow Tol Ratio= 0.001
Split Flow NTrial= 30
Split Flow Tol= 0.02
Split Flow Ratio= 0.02
Log Output Level= 0
Friction Slope Method= 1
Unsteady Friction Slope Method= 2
Unsteady Bridges Friction Slope Method= 1
Parabolic Critical Depth
Global Vel Dist=  1 , 1 , 1
Global Log Level= 0
CheckData=True
Encroach Param= -1, 0, 0, 0
BEGIN DESCRIPTION:
Multiple Run
END DESCRIPTION:

--- StreamM023.f01 (steady flow) ---

Flow Title=Multiple
Number of Profiles=7
Profile Names=10-year,25-year,50-year,1pct_min,100-year,1pct_plu,500-year
River Rch & RM= StreamM023,Reach-1,2006
     453     719     957     620    1237    2469    2041
Boundary for River Rch & Prof#=StreamM023,Reach-1,1
Up Type=0
Dn Type=3
Dn Slope=0.005
Boundary for River Rch & Prof#=StreamM023,Reach-1,2
Up Type=0
Dn Type=3
Dn Slope=0.005
Boundary for River Rch & Prof#=StreamM023,Reach-1,3
Up Type=0
Dn Type=3
Dn Slope=0.005
Boundary for River Rch & Prof#=StreamM023,Reach-1,4
Up Type=0
Dn Type=3
Dn Slope=0.005
Boundary for River Rch & Prof#=StreamM023,Reach-1,5
Up Type=0
Dn Type=3
Dn Slope=0.005
Boundary for River Rch & Prof#=StreamM023,Reach-1,6
Up Type=0
Dn Type=3
Dn Slope=0.005
Boundary for River Rch & Prof#=StreamM023,Reach-1,7
Up Type=0
Dn Type=3
Dn Slope=0.005

--- StreamM023.g01 (geometry) ---

Geom Title=Existing Conditions

River Reach=StreamM023,Reach-1
Reach XY= 30
      2492225.00     13835725.00      2492269.66     13835720.04
      2492280.60     13835672.58      2492322.46     13835630.74
      2492373.24     13835620.80      2492422.80     13835581.08
      2492477.20     13835568.92      2492522.80     13835531.08
      2492573.28     13835520.84      2492622.80     13835481.08
      2492673.28     13835470.84      2492722.80     13835431.08
      2492777.18     13835418.88      2492826.58     13835378.83
      2492919.03     13835372.65      2492980.97     13835327.35
      2493073.42     13835321.17      2493122.83     13835281.14
      2493181.05     13835266.84      2493285.48     13835175.94
      2493369.02     13835177.16      2493435.51     13835223.77
      2493569.14     13835227.47      2493625.01     13835267.41
      2493676.64     13835228.60      2493718.88     13835226.84
      2493772.81     13835268.82      2493831.05     13835283.14
      2493922.49     13835369.67      2493975.00     13835375.00

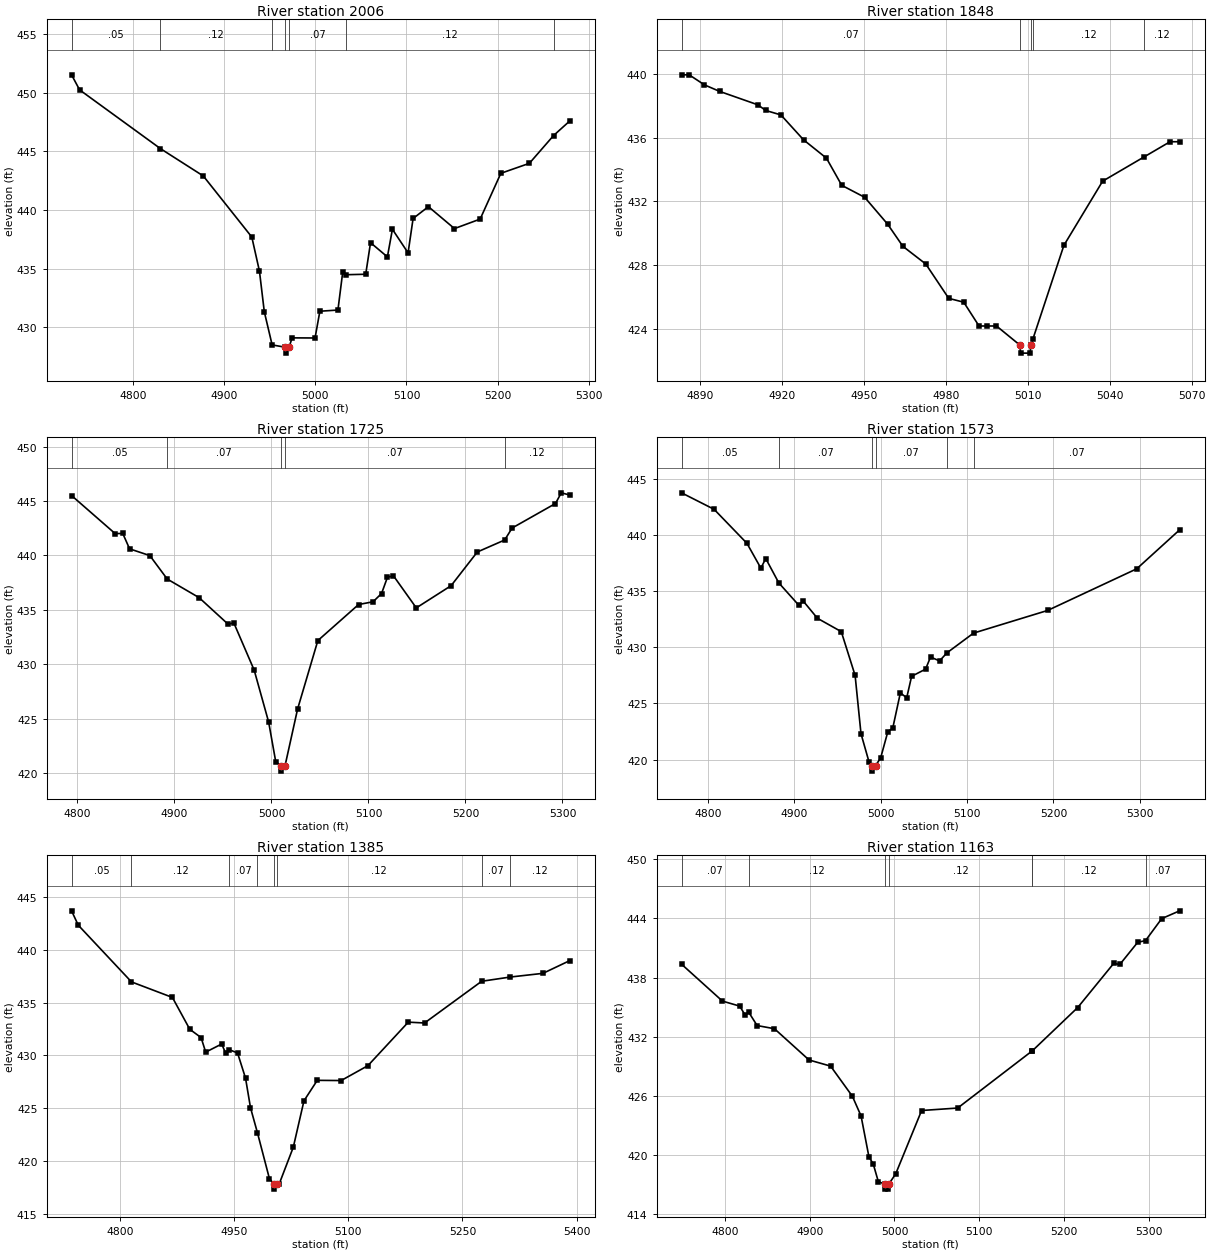
Type RM Length L Ch R = 1,2006,158,158,158
BEGIN DESCRIPTION:
H21219
END DESCRIPTION:
XS GIS Cut Line= 3
      2492362.15     13835970.71      2492244.97     13835651.71
      2492155.99     13835465.08
#Sta/Elev= 30
  4732.5  451.52  4741.3  450.24  4829.9  445.24  4877.1  442.90  4930.3  437.70
  4938.7  434.79  4944.0  431.34  4952.6  428.51  4967.2  428.31  4967.4  427.81
  4971.2  428.31  4974.5  429.11  4999.7  429.10  5005.0  431.38  5024.8  431.48
  5030.1  434.73  5033.8  434.49  5055.3  434.53  5060.6  437.22  5079.1  436.01
  5084.6  438.36  5101.8  436.35  5107.3  439.28  5124.1  440.29  5152.7  438.42
  5180.9  439.23  5203.6  443.13  5234.9  443.98  5261.5  446.35  5279.1  447.58
#Mann=7,-1,0
  4732.5    0.05       0  4829.9    0.12       0  4952.6    0.07       0
  4967.2    0.05       0  4971.2    0.07       0  5033.8    0.12       0
  5261.5    0.12       0
Bank Sta=4967.2,4971.2
Exp/Cntr=0.3,0.1

Type RM Length L Ch R = 1,1848,123,123,123
BEGIN DESCRIPTION:
StreamM023 4.0
END DESCRIPTION:
XS GIS Cut Line= 3
      2492425.01     13835725.02      2492375.00     13835625.00
      2492325.03     13835575.03
#Sta/Elev= 29
  4883.1  439.93  4885.9  439.93  4891.5  439.30  4897.1  438.89  4911.1  438.05
  4913.9  437.70  4919.5  437.42  4927.8  435.86  4936.2  434.71  4941.8  433.01
  4950.2  432.26  4958.6  430.58  4964.2  429.19  4972.6  428.08  4981.0  425.93
  4986.5  425.69  4992.1  424.20  4994.9  424.20  4998.5  424.20  5007.1  423.00
  5007.3  422.50  5010.8  422.50  5011.1  423.00  5011.8  423.36  5023.2  429.25
  5037.4  433.27  5052.6  434.79  5062.1  435.74  5065.6  435.74
#Mann=5,-1,0
  4883.1    0.07       0  5007.1    0.05       0  5011.1    0.07       0
  5011.8    0.12       0  5052.6    0.12       0
Bank Sta=5007.1,5011.1
Exp/Cntr=0.3,0.1

Type RM Length L Ch R = 1,1725,152,152,152
BEGIN DESCRIPTION:
H21218
END DESCRIPTION:
XS GIS Cut Line= 2
      2492594.35     13835738.51      2492303.53     13835315.30
#Sta/Elev= 30
  4793.9  445.50  4838.8  442.01  4846.7  442.02  4853.7  440.61  4874.6  439.99
  4892.5  437.84  4925.4  436.13  4955.2  433.70  4961.2  433.81  4982.2  429.47
  4997.1  424.71  5004.4  421.07  5010.0  420.71  5010.2  420.21  5014.0  420.71
  5026.9  425.90  5047.8  432.19  5089.8  435.50  5104.7  435.75  5113.5  436.51
  5119.6  438.01  5125.8  438.13  5149.3  435.19  5185.2  437.23  5212.2  440.32
  5240.4  441.42  5248.1  442.52  5292.8  444.77  5298.8  445.75  5307.4  445.55
#Mann=5,-1,0
  4793.9    0.05       0  4892.5    0.07       0  5010.0    0.05       0
  5014.0    0.07       0  5240.4    0.12       0
Bank Sta=5010,5014
Exp/Cntr=0.3,0.1

Type RM Length L Ch R = 1,1573,188,188,188
BEGIN DESCRIPTION:
H21217
END DESCRIPTION:
XS GIS Cut Line= 2
      2492715.86     13835697.24      2492439.20     13835191.46
#Sta/Elev= 30
  4769.5  443.77  4807.2  442.30  4845.2  439.27  4861.3  437.06  4867.0  437.91
  4882.1  435.74  4904.9  433.78  4910.6  434.10  4926.8  432.59  4954.4  431.40
  4970.4  427.50  4977.2  422.31  4986.5  419.79  4990.2  419.47  4990.5  418.97
  4994.2  419.47  5000.0  420.16  5008.3  422.49  5014.0  422.81  5022.8  425.95
  5030.1  425.50  5035.8  427.42  5052.0  428.06  5057.7  429.14  5068.1  428.79
  5076.7  429.51  5107.5  431.27  5193.3  433.29  5296.4  437.00  5346.0  440.47
#Mann=6,-1,0
  4769.5    0.05       0  4882.1    0.07       0  4990.2    0.05       0
  4994.2    0.07       0  5076.7    0.12       0  5107.5    0.07       0
Bank Sta=4990.2,4994.2
Exp/Cntr=0.3,0.1

Type RM Length L Ch R = 1,1385,222,222,222
BEGIN DESCRIPTION:
H21216
END DESCRIPTION:
XS GIS Cut Line= 3
      2492850.44     13835673.43      2492735.42     13835304.48
      2492541.26     13835118.96
#Sta/Elev= 30
  4735.9  443.69  4744.7  442.33  4814.7  436.96  4868.5  435.49  4891.4  432.47
  4906.2  431.69  4912.3  430.31  4933.3  431.08  4938.7  430.19  4943.4  430.54
  4954.2  430.23  4964.7  427.84  4971.2  425.05  4980.4  422.66  4996.1  418.33
  5001.8  417.84  5002.0  417.34  5005.8  417.84  5009.0  417.84  5027.5  421.31
  5041.5  425.70  5059.0  427.64  5090.4  427.62  5125.6  429.03  5178.7  433.15
  5200.1  433.07  5275.2  437.02  5312.7  437.42  5355.8  437.77  5390.9  438.97
#Mann=8,-1,0
  4735.9    0.05       0  4814.7    0.12       0  4943.4    0.07       0
  4980.4    0.12       0  5001.8    0.05       0  5005.8    0.12       0
  5275.2    0.07       0  5312.7    0.12       0
Bank Sta=5001.8,5005.8
Exp/Cntr=0.3,0.1

Type RM Length L Ch R = 1,1163,224,224,224
BEGIN DESCRIPTION:
H21215
END DESCRIPTION:
XS GIS Cut Line= 3
      2493015.36     13835582.23      2492952.43     13835276.27
      2492754.93     13835085.28
#Sta/Elev= 30
  4749.0  439.35  4797.2  435.61  4817.6  435.10  4824.0  434.18  4828.2  434.48
  4838.1  433.13  4858.5  432.81  4899.3  429.64  4924.7  429.02  4950.4  425.96
  4960.6  423.97  4969.9  419.82  4975.0  419.09  4981.0  417.30  4989.2  417.05
  4989.4  416.55  4992.9  416.55  4993.2  417.05  5001.4  418.09  5032.0  424.52
  5074.5  424.77  5162.3  430.56  5162.5  430.57  5216.0  434.96  5258.4  439.43
  5265.6  439.32  5286.7  441.57  5295.9  441.74  5315.0  443.97  5336.1  444.76
#Mann=7,-1,0
  4749.0    0.07       0  4828.2    0.12       0  4989.2    0.05       0
  4993.2    0.12       0  5162.3    0.07       0  5162.5    0.12       0
  5295.9    0.07       0
Bank Sta=4989.2,4993.2
Exp/Cntr=0.3,0.1

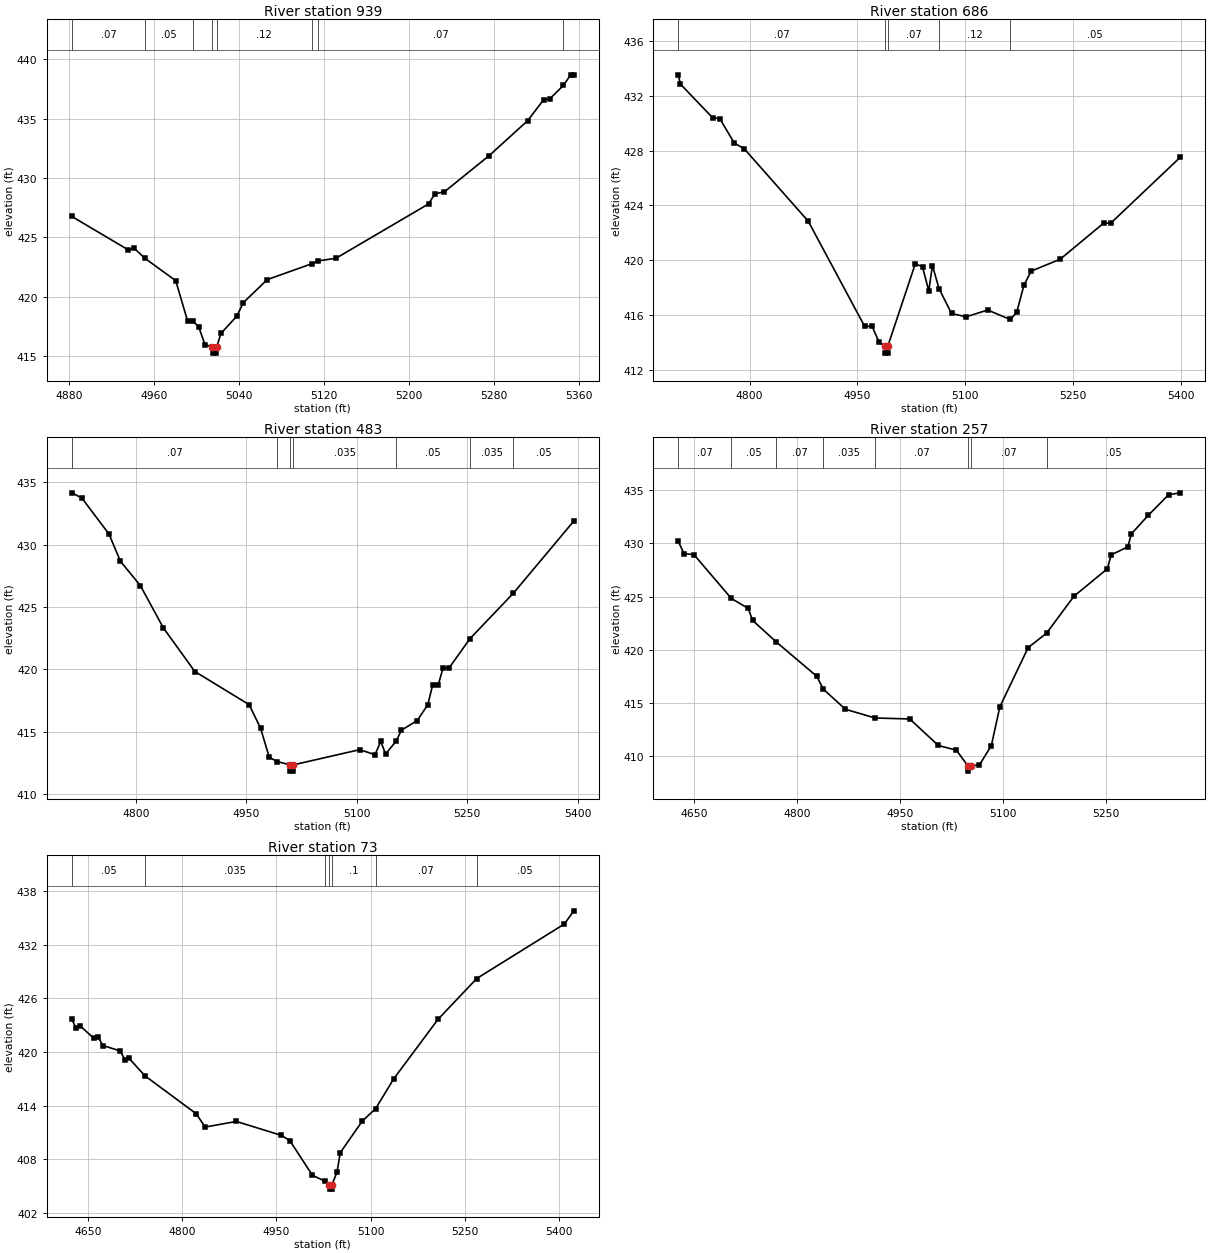
Type RM Length L Ch R = 1,939,253,253,253
BEGIN DESCRIPTION:
StreamM023 2.0
END DESCRIPTION:
XS GIS Cut Line= 3
      2493224.99     13835374.98      2493175.00     13835275.00
      2492875.03     13835075.02
#Sta/Elev= 30
  4882.8  426.76  4935.9  423.94  4941.5  424.07  4951.7  423.22  4980.6  421.34
  4991.8  417.92  4996.6  417.92  5002.1  417.47  5008.1  415.95  5015.1  415.73
  5015.4  415.23  5018.9  415.23  5019.1  415.73  5023.1  416.89  5038.1  418.35
  5044.2  419.49  5066.7  421.43  5108.6  422.77  5114.7  423.01  5131.3  423.23
  5218.4  427.81  5224.4  428.66  5233.4  428.84  5275.5  431.89  5311.6  434.83
  5326.6  436.59  5332.6  436.69  5345.2  437.80  5352.1  438.70  5355.1  438.70
#Mann=8,-1,0
  4882.8    0.07       0  4951.7    0.05       0  4996.6    0.12       0
  5015.1    0.05       0  5019.1    0.12       0  5108.6    0.05       0
  5114.7    0.07       0  5345.2    0.05       0
Bank Sta=5015.1,5019.1
Exp/Cntr=0.3,0.1

Type RM Length L Ch R = 1,686,203,203,203
BEGIN DESCRIPTION:
H21214
END DESCRIPTION:
XS GIS Cut Line= 2
      2493349.57     13835482.40      2493429.74     13834789.02
#Sta/Elev= 30
  4700.9  433.54  4704.0  432.86  4748.6  430.41  4758.7  430.34  4778.8  428.56
  4792.8  428.13  4881.6  422.85  4960.0  415.17  4970.5  415.16  4980.1  414.01
  4988.2  413.71  4988.5  413.21  4992.0  413.21  4992.2  413.71  5030.5  419.74
  5040.5  419.51  5049.2  417.76  5054.3  419.61  5063.5  417.92  5080.8  416.11
  5100.9  415.86  5131.1  416.36  5162.3  415.67  5171.4  416.18  5181.5  418.17
  5191.5  419.20  5231.9  420.07  5292.2  422.70  5302.3  422.71  5398.9  427.52
#Mann=5,-1,0
  4700.9    0.07       0  4988.2    0.05       0  4992.2    0.07       0
  5063.5    0.12       0  5162.3    0.05       0
Bank Sta=4988.2,4992.2
Exp/Cntr=0.3,0.1

Type RM Length L Ch R = 1,483,226,226,226
BEGIN DESCRIPTION:
StreamM023 1.0
END DESCRIPTION:
XS GIS Cut Line= 3
      2493424.99     13835475.02      2493575.00     13835225.00
      2493825.01     13834924.99
#Sta/Elev= 30
  4712.8  434.15  4726.4  433.74  4763.4  430.84  4778.9  428.66  4806.1  426.70
  4837.2  423.32  4880.0  419.82  4953.8  417.16  4969.4  415.26  4981.0  412.95
  4991.7  412.60  5009.5  412.33  5009.8  411.83  5013.3  411.83  5013.5  412.33
  5103.9  413.55  5124.8  413.15  5132.6  414.22  5139.1  413.20  5153.6  414.24
  5160.6  415.11  5182.1  415.89  5196.4  417.14  5202.9  418.70  5210.7  418.75
  5217.2  420.10  5225.0  420.07  5253.7  422.45  5312.9  426.11  5394.9  431.89
#Mann=7,-1,0
  4712.8    0.07       0  4991.7   0.035       0  5009.5   0.035       0
  5013.5   0.035       0  5153.6    0.05       0  5253.7   0.035       0
  5312.9    0.05       0
Bank Sta=5009.5,5013.5
Exp/Cntr=0.3,0.1

Type RM Length L Ch R = 1,257,184,184,184
BEGIN DESCRIPTION:
H21213
END DESCRIPTION:
XS GIS Cut Line= 3
      2493536.22     13835558.37      2493777.08     13835235.04
      2493898.01     13834928.41
#Sta/Elev= 30
  4626.3  430.18  4634.7  429.04  4649.3  428.93  4703.8  424.82  4728.5  423.88
  4734.8  422.76  4769.1  420.75  4828.6  417.50  4838.0  416.30  4870.3  414.41
  4913.7  413.59  4964.2  413.50  5005.9  411.01  5032.2  410.57  5049.0  409.10
  5049.3  408.60  5053.0  409.10  5065.9  409.18  5083.3  411.00  5095.7  414.64
  5137.0  420.20  5163.9  421.56  5203.9  425.03  5252.7  427.61  5258.1  428.91
  5282.4  429.66  5287.8  430.89  5312.2  432.62  5342.0  434.56  5359.1  434.74
#Mann=8,-1,0
  4626.3    0.07       0  4703.8    0.05       0  4769.1    0.07       0
  4838.0   0.035       0  4913.7    0.07       0  5049.0    0.05       0
  5053.0    0.07       0  5163.9    0.05       0
Bank Sta=5049,5053
Exp/Cntr=0.3,0.1

Type RM Length L Ch R = 1,73,0,0,0
BEGIN DESCRIPTION:
H21212
END DESCRIPTION:
XS GIS Cut Line= 3
      2493616.48     13835595.29      2493915.97     13835350.06
      2493957.20     13834939.91
#Sta/Elev= 30
  4624.3  423.71  4630.8  422.71  4637.2  422.97  4659.5  421.53  4665.9  421.72
  4673.8  420.74  4701.1  420.14  4709.0  419.17  4715.4  419.31  4740.8  417.35
  4822.4  413.11  4836.7  411.62  4886.3  412.25  4958.0  410.69  4971.4  410.11
  5007.5  406.22  5027.7  405.56  5034.6  405.18  5034.8  404.68  5038.3  404.68
  5038.6  405.18  5046.6  406.59  5051.7  408.75  5086.8  412.29  5107.9  413.67
  5137.1  417.04  5207.4  423.67  5269.0  428.23  5408.4  434.32  5423.6  435.80
#Mann=7,-1,0
  4624.3    0.05       0  4740.8   0.035       0  5027.7     0.1       0
  5034.6   0.035       0  5038.6     0.1       0  5107.9    0.07       0
  5269.0    0.05       0
Bank Sta=5034.6,5038.6
Exp/Cntr=0.3,0.1

Chan Stop Cuts=-1