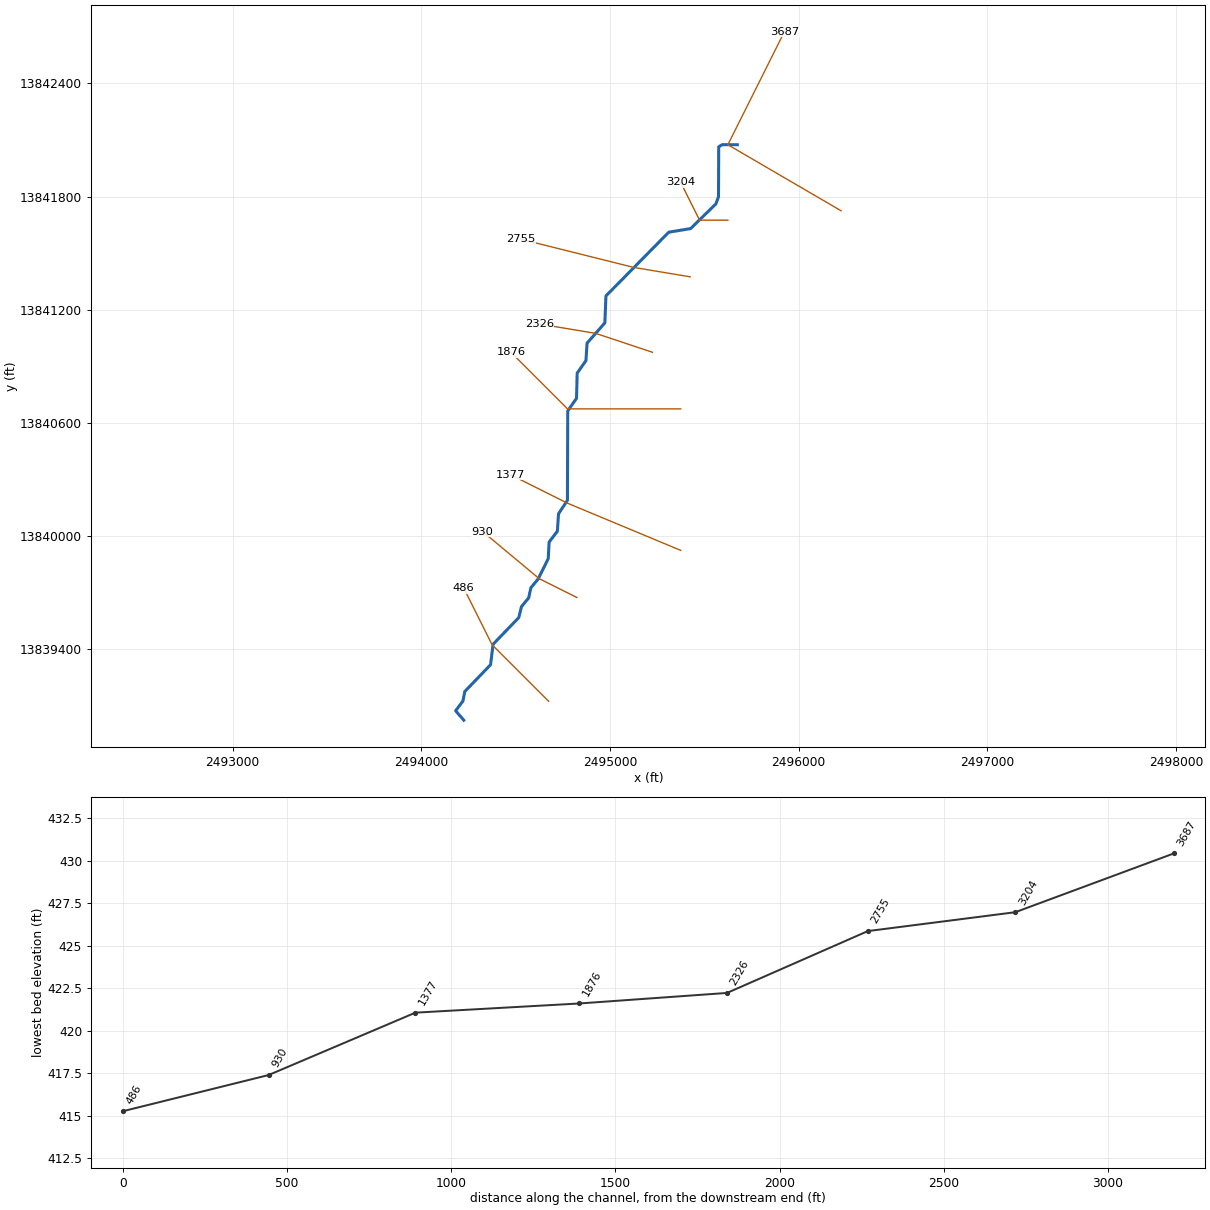
--- StreamM024.prj (project) ---

Proj Title=StreamM024 Base Level Engineering
Current Plan=p01
Default Exp/Contr=0.3,0.1
English Units
Geom File=g01
Flow File=f01
Plan File=p01
BEGIN DESCRIPTION:
StreamM024
END DESCRIPTION:

--- StreamM024.p01 (plan) ---

Plan Title=Multiple Run
Short Identifier=Multiple
Geom File=g01
Flow File=f01
Subcritical Flow
K Sum by GR= 0
Std Step Tol= 0.01
Critical Tol= 0.01
Num of Std Step Trials= 20
Max Error Tol= 0.3
Flow Tol Ratio= 0.001
Split Flow NTrial= 30
Split Flow Tol= 0.02
Split Flow Ratio= 0.02
Log Output Level= 0
Friction Slope Method= 1
Unsteady Friction Slope Method= 2
Unsteady Bridges Friction Slope Method= 1
Parabolic Critical Depth
Global Vel Dist=  1 , 1 , 1
Global Log Level= 0
CheckData=True
Encroach Param= -1, 0, 0, 0
BEGIN DESCRIPTION:
Multiple Run
END DESCRIPTION:

--- StreamM024.f01 (steady flow) ---

Flow Title=Multiple
Number of Profiles=7
Profile Names=10-year,25-year,50-year,1pct_min,100-year,1pct_plu,500-year
River Rch & RM= StreamM024,Reach-1,3687
     647    1042    1399     910    1817    3625    3031
Boundary for River Rch & Prof#=StreamM024,Reach-1,1
Up Type=0
Dn Type=3
Dn Slope=0.005
Boundary for River Rch & Prof#=StreamM024,Reach-1,2
Up Type=0
Dn Type=3
Dn Slope=0.005
Boundary for River Rch & Prof#=StreamM024,Reach-1,3
Up Type=0
Dn Type=3
Dn Slope=0.005
Boundary for River Rch & Prof#=StreamM024,Reach-1,4
Up Type=0
Dn Type=3
Dn Slope=0.005
Boundary for River Rch & Prof#=StreamM024,Reach-1,5
Up Type=0
Dn Type=3
Dn Slope=0.005
Boundary for River Rch & Prof#=StreamM024,Reach-1,6
Up Type=0
Dn Type=3
Dn Slope=0.005
Boundary for River Rch & Prof#=StreamM024,Reach-1,7
Up Type=0
Dn Type=3
Dn Slope=0.005

--- StreamM024.g01 (geometry) ---

Geom Title=Existing Conditions

River Reach=StreamM024,Reach-1
Reach XY= 30
      2495675.00     13842075.00      2495594.54     13842075.46
      2495576.38     13842063.62      2495575.30     13841799.88
      2495561.63     13841761.68      2495427.43     13841630.52
      2495311.70     13841611.60      2494978.54     13841273.53
      2494972.92     13841130.86      2494878.62     13841023.50
      2494872.64     13840930.98      2494826.23     13840864.49
      2494822.73     13840730.94      2494776.22     13840664.50
      2494774.48     13840190.22      2494727.36     13840119.02
      2494721.15     13840026.60      2494677.35     13839969.03
      2494672.67     13839880.97      2494618.92     13839772.80
      2494581.08     13839727.20      2494568.92     13839672.80
      2494531.10     13839627.19      2494516.86     13839568.94
      2494380.52     13839427.43      2494367.14     13839318.83
      2494230.80     13839177.29      2494220.64     13839126.64
      2494181.87     13839074.88      2494225.00     13839025.00

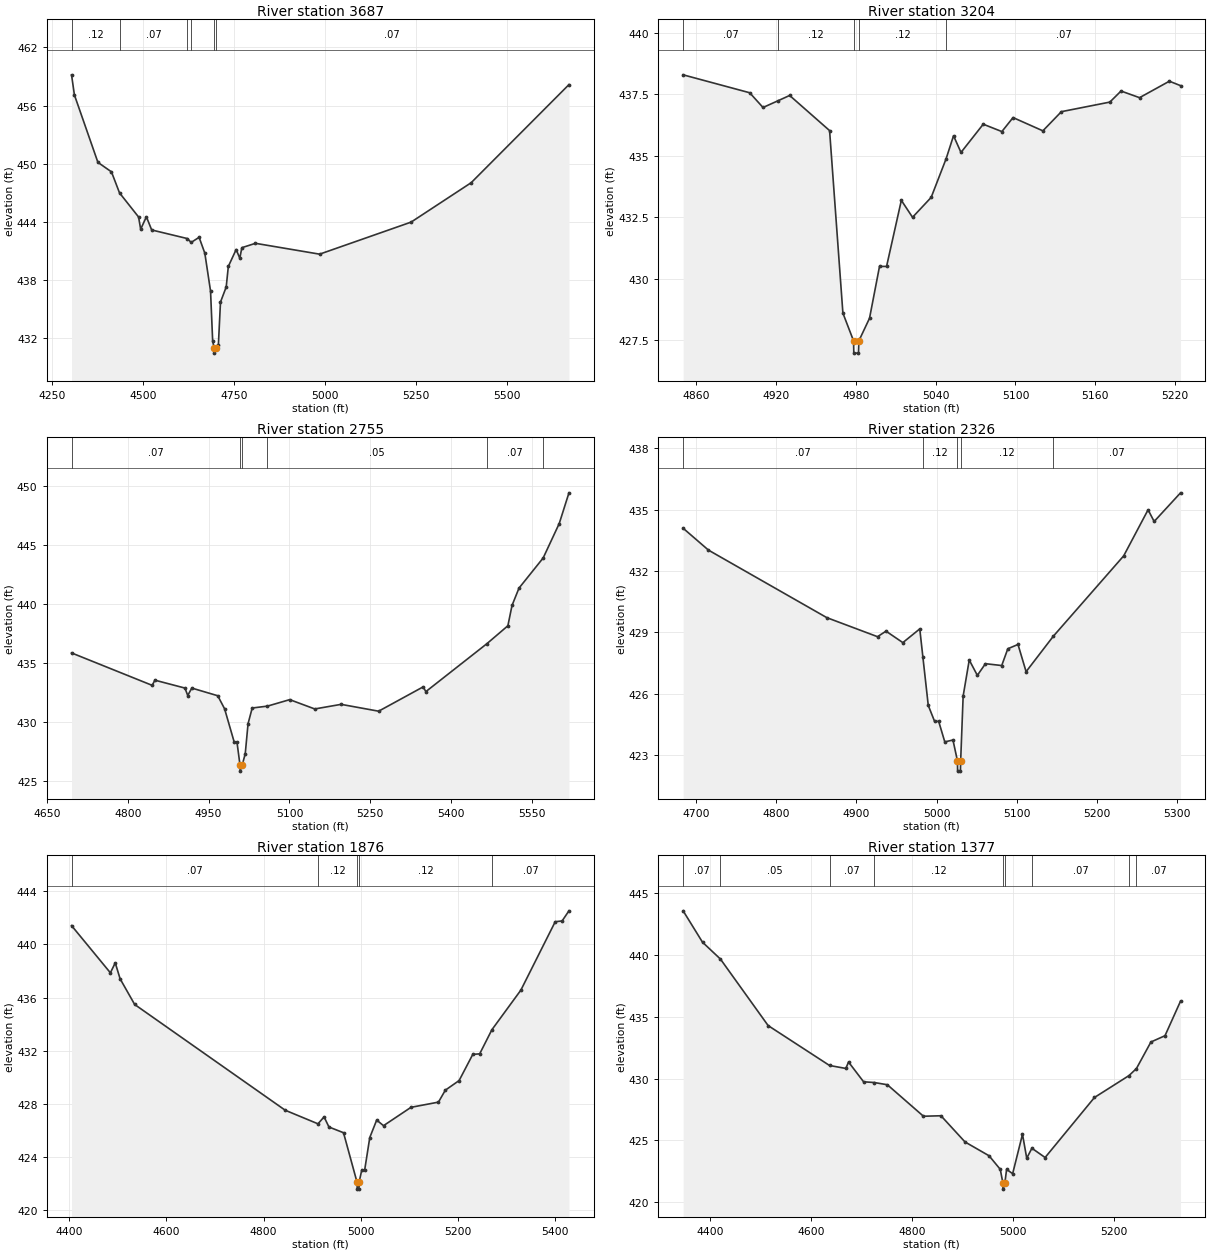
Type RM Length L Ch R = 1,3687,483,483,483
BEGIN DESCRIPTION:
StreamM024 8.0
END DESCRIPTION:
XS GIS Cut Line= 3
      2496225.01     13841725.00      2495625.00     13842075.00
      2495925.02     13842675.04
#Sta/Elev= 30
  4304.3  459.17  4312.2  457.09  4376.7  450.13  4413.9  449.15  4436.0  446.98
  4488.3  444.49  4494.1  443.23  4509.8  444.51  4524.3  443.15  4622.3  442.26
  4632.6  441.86  4654.5  442.39  4670.2  440.75  4685.9  436.84  4691.7  431.70
  4695.9  430.93  4696.2  430.43  4699.9  430.93  4707.4  431.26  4713.2  435.70
  4728.9  437.26  4734.7  439.38  4756.2  441.13  4766.2  440.23  4771.9  441.32
  4809.2  441.77  4985.3  440.65  5236.5  443.96  5401.4  448.03  5669.8  458.16
#Mann=6,-1,0
  4304.3    0.12       0  4436.0    0.07       0  4622.3    0.12       0
  4632.6    0.07       0  4695.9    0.05       0  4699.9    0.07       0
Bank Sta=4695.9,4699.9
Exp/Cntr=0.3,0.1

Type RM Length L Ch R = 1,3204,449,449,449
BEGIN DESCRIPTION:
StreamM024 7.0
END DESCRIPTION:
XS GIS Cut Line= 3
      2495624.97     13841675.00      2495475.00     13841675.00
      2495374.99     13841875.02
#Sta/Elev= 30
  4850.4  438.30  4900.4  437.57  4910.4  436.97  4921.9  437.25  4930.4  437.46
  4960.4  436.03  4970.4  428.60  4978.4  427.47  4978.6  426.97  4982.1  426.97
  4982.4  427.47  4990.4  428.39  4997.9  430.50  5003.2  430.50  5014.3  433.19
  5022.7  432.50  5036.7  433.31  5047.9  434.88  5053.5  435.82  5059.1  435.14
  5075.8  436.29  5089.8  435.99  5098.2  436.56  5120.6  436.02  5134.5  436.80
  5170.9  437.19  5179.3  437.64  5193.2  437.37  5215.6  438.04  5224.0  437.86
#Mann=5,-1,0
  4850.4    0.07       0  4921.9    0.12       0  4978.4    0.05       0
  4982.4    0.12       0  5047.9    0.07       0
Bank Sta=4978.4,4982.4
Exp/Cntr=0.3,0.1

Type RM Length L Ch R = 1,2755,429,429,429
BEGIN DESCRIPTION:
StreamM024 6.0
END DESCRIPTION:
XS GIS Cut Line= 3
      2495425.04     13841374.99      2495125.00     13841425.00
      2494525.04     13841574.99
#Sta/Elev= 30
  4695.8  435.88  4845.4  433.13  4850.4  433.57  4906.2  432.90  4911.3  432.27
  4918.9  432.90  4967.0  432.25  4979.7  431.14  4997.4  428.34  5002.6  428.34
  5008.3  426.36  5008.5  425.86  5012.3  426.36  5018.0  427.34  5023.2  429.88
  5030.9  431.21  5059.2  431.37  5100.5  431.92  5146.9  431.13  5195.8  431.52
  5265.4  430.94  5347.9  433.00  5353.0  432.60  5466.4  436.67  5505.1  438.18
  5512.8  439.90  5525.7  441.37  5570.6  443.93  5600.4  446.85  5618.4  449.45
#Mann=6,-1,0
  4695.8    0.07       0  5008.3    0.05       0  5012.3    0.07       0
  5059.2    0.05       0  5466.4    0.07       0  5570.6    0.12       0
Bank Sta=5008.3,5012.3
Exp/Cntr=0.3,0.1

Type RM Length L Ch R = 1,2326,450,450,450
BEGIN DESCRIPTION:
StreamM024 5.0
END DESCRIPTION:
XS GIS Cut Line= 3
      2495224.98     13840975.01      2494925.00     13841075.00
      2494625.05     13841124.99
#Sta/Elev= 30
  4683.8  434.09  4715.4  433.02  4863.0  429.72  4926.2  428.79  4936.8  429.06
  4957.8  428.50  4978.9  429.17  4982.8  427.79  4989.5  425.43  4997.4  424.65
  5002.5  424.65  5010.1  423.65  5020.3  423.74  5025.9  422.72  5026.1  422.22
  5029.6  422.22  5029.9  422.72  5033.0  425.89  5040.6  427.65  5050.7  426.90
  5060.8  427.47  5081.1  427.38  5088.7  428.20  5101.4  428.41  5111.5  427.08
  5145.4  428.81  5233.2  432.74  5263.6  434.99  5271.2  434.42  5304.1  435.82
#Mann=5,-1,0
  4683.8    0.07       0  4982.8    0.12       0  5025.9    0.05       0
  5029.9    0.12       0  5145.4    0.07       0
Bank Sta=5025.9,5029.9
Exp/Cntr=0.3,0.1

Type RM Length L Ch R = 1,1876,499,499,499
BEGIN DESCRIPTION:
StreamM024 4.0
END DESCRIPTION:
XS GIS Cut Line= 3
      2495374.97     13840675.00      2494775.00     13840675.00
      2494475.02     13840974.98
#Sta/Elev= 30
  4404.6  441.41  4484.6  437.86  4494.6  438.61  4504.6  437.41  4534.6  435.48
  4844.6  427.53  4912.0  426.51  4924.6  427.03  4934.6  426.27  4964.6  425.84
  4992.6  422.10  4992.8  421.60  4996.3  421.60  4996.6  422.10  5002.1  423.02
  5008.1  423.02  5018.7  425.48  5032.9  426.79  5047.0  426.37  5103.6  427.75
  5160.1  428.14  5174.3  429.04  5202.6  429.76  5230.8  431.73  5245.0  431.77
  5270.1  433.58  5329.8  436.56  5400.5  441.70  5414.7  441.76  5428.8  442.52
#Mann=5,-1,0
  4404.6    0.07       0  4912.0    0.12       0  4992.6    0.05       0
  4996.6    0.12       0  5270.1    0.07       0
Bank Sta=4992.6,4996.6
Exp/Cntr=0.3,0.1

Type RM Length L Ch R = 1,1377,447,447,447
BEGIN DESCRIPTION:
StreamM024 3.0
END DESCRIPTION:
XS GIS Cut Line= 3
      2495374.98     13839925.01      2494775.00     13840175.00
      2494474.99     13840325.00
#Sta/Elev= 30
  4345.9  443.59  4384.3  441.05  4419.9  439.68  4514.3  434.30  4635.9  431.07
  4668.2  430.83  4673.6  431.35  4703.4  429.75  4724.6  429.69  4750.5  429.51
  4822.0  426.96  4856.7  427.00  4904.3  424.88  4952.0  423.76  4974.2  422.66
  4979.3  421.56  4979.5  421.06  4983.3  421.56  4986.7  422.66  4998.7  422.31
  5018.2  425.50  5026.6  423.56  5036.8  424.37  5063.0  423.62  5160.8  428.48
  5229.1  430.25  5243.9  430.82  5272.6  432.97  5300.5  433.48  5331.3  436.28
#Mann=9,-1,0
  4345.9    0.07       0  4419.9    0.05       0  4635.9    0.07       0
  4724.6    0.12       0  4979.3    0.05       0  4983.3    0.12       0
  5036.8    0.07       0  5229.1    0.05       0  5243.9    0.07       0
Bank Sta=4979.3,4983.3
Exp/Cntr=0.3,0.1

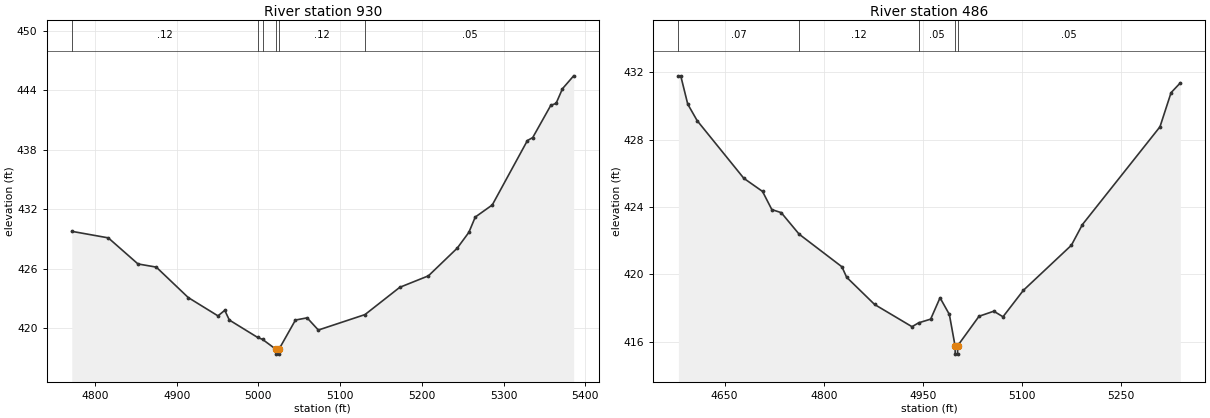
Type RM Length L Ch R = 1,930,444,444,444
BEGIN DESCRIPTION:
StreamM024 2.0
END DESCRIPTION:
XS GIS Cut Line= 3
      2494824.98     13839675.01      2494625.00     13839775.00
      2494325.00     13840025.00
#Sta/Elev= 30
  4771.6  429.78  4816.3  429.12  4852.6  426.49  4875.0  426.17  4914.1  423.10
  4950.5  421.25  4958.8  421.81  4964.4  420.83  4999.1  419.07  5005.0  418.88
  5021.2  417.89  5021.4  417.39  5024.9  417.39  5025.2  417.89  5045.3  420.83
  5059.6  421.05  5073.3  419.82  5130.4  421.38  5172.9  424.13  5208.0  425.29
  5243.2  428.08  5257.5  429.68  5265.3  431.22  5286.1  432.44  5329.1  438.94
  5335.6  439.24  5357.7  442.49  5364.2  442.69  5372.0  444.17  5385.7  445.47
#Mann=6,-1,0
  4771.6    0.12       0  4999.1    0.05       0  5005.0    0.12       0
  5021.2    0.05       0  5025.2    0.12       0  5130.4    0.05       0
Bank Sta=5021.2,5025.2
Exp/Cntr=0.3,0.1

Type RM Length L Ch R = 1,486,0,0,0
BEGIN DESCRIPTION:
StreamM024 1.0
END DESCRIPTION:
XS GIS Cut Line= 3
      2494675.00     13839125.00      2494375.00     13839425.00
      2494224.99     13839725.02
#Sta/Elev= 30
  4580.1  431.80  4583.6  431.80  4594.2  430.12  4608.4  429.14  4679.1  425.71
  4707.4  424.93  4721.5  423.85  4735.7  423.67  4762.8  422.39  4827.6  420.45
  4834.7  419.83  4877.1  418.21  4933.7  416.89  4943.7  417.12  4961.9  417.34
  4976.1  418.61  4990.2  417.62  4998.8  415.76  4999.1  415.26  5002.6  415.26
  5002.8  415.76  5035.1  417.51  5057.5  417.81  5071.4  417.48  5102.2  419.05
  5174.9  421.73  5191.6  422.96  5309.0  428.77  5325.8  430.80  5339.8  431.38
#Mann=5,-1,0
  4580.1    0.07       0  4762.8    0.12       0  4943.7    0.05       0
  4998.8    0.05       0  5002.8    0.05       0
Bank Sta=4998.8,5002.8
Exp/Cntr=0.3,0.1

Chan Stop Cuts=-1