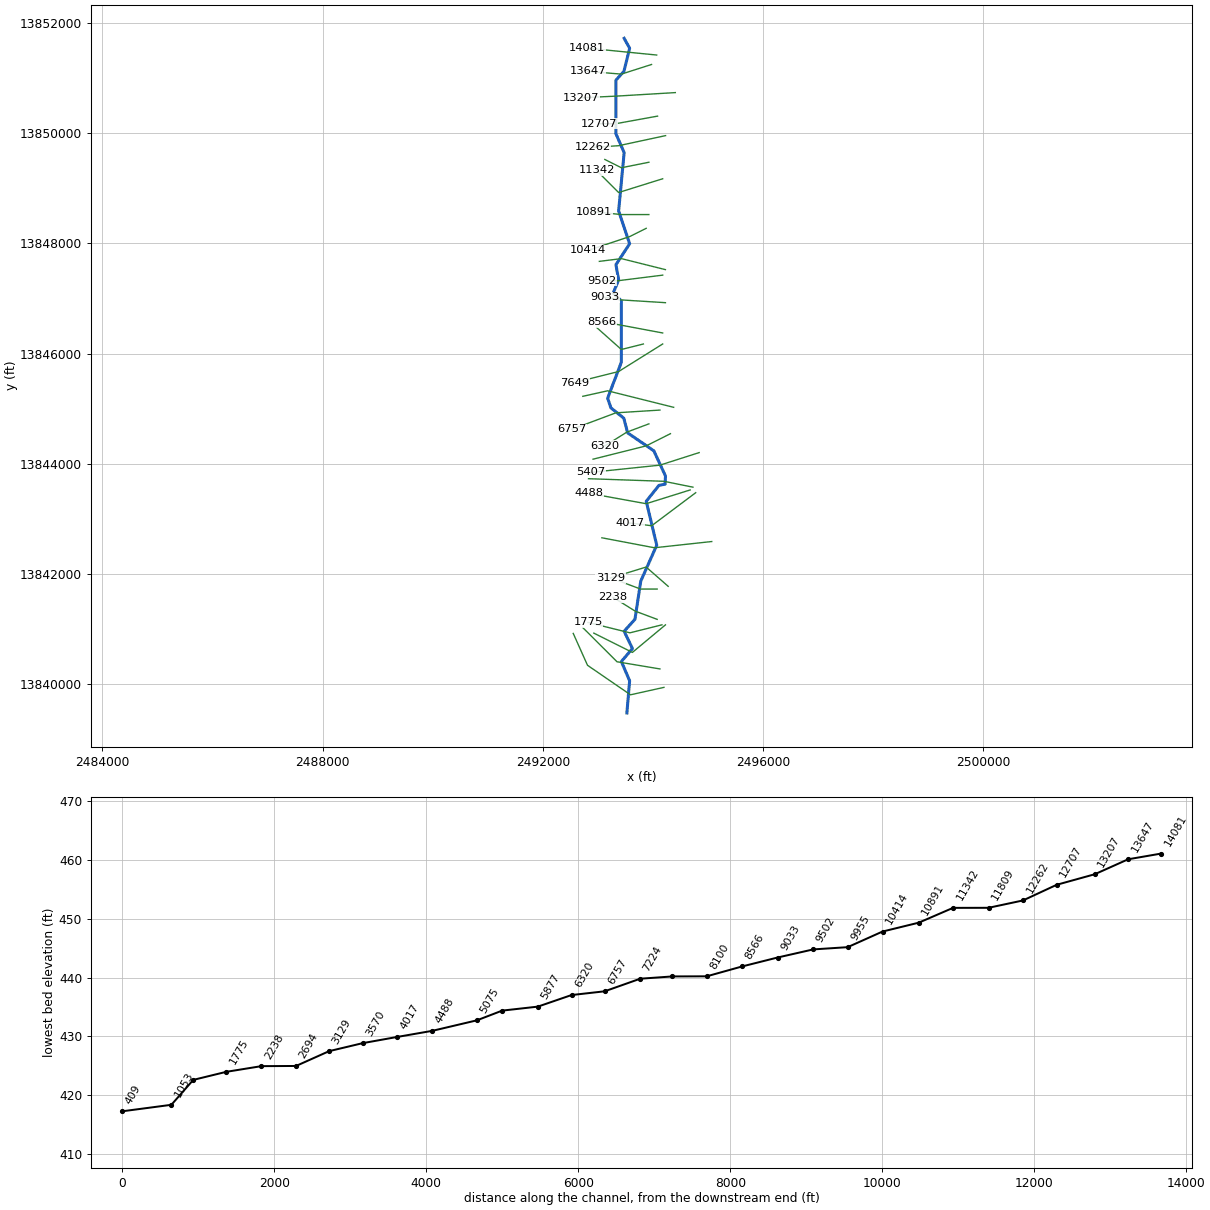
--- StreamM025.prj (project) ---

Proj Title=StreamM025 Base Level Engineering
Current Plan=p01
Default Exp/Contr=0.3,0.1
English Units
Geom File=g01
Flow File=f01
Plan File=p01
BEGIN DESCRIPTION:
StreamM025
END DESCRIPTION:

--- StreamM025.p01 (plan) ---

Plan Title=Multiple Run
Short Identifier=Multiple
Geom File=g01
Flow File=f01
Subcritical Flow
K Sum by GR= 0
Std Step Tol= 0.01
Critical Tol= 0.01
Num of Std Step Trials= 20
Max Error Tol= 0.3
Flow Tol Ratio= 0.001
Split Flow NTrial= 30
Split Flow Tol= 0.02
Split Flow Ratio= 0.02
Log Output Level= 0
Friction Slope Method= 1
Unsteady Friction Slope Method= 2
Unsteady Bridges Friction Slope Method= 1
Parabolic Critical Depth
Global Vel Dist=  1 , 1 , 1
Global Log Level= 0
CheckData=True
Encroach Param= -1, 0, 0, 0
BEGIN DESCRIPTION:
Multiple Run
END DESCRIPTION:

--- StreamM025.f01 (steady flow) ---

Flow Title=Multiple
Number of Profiles=7
Profile Names=10-year,25-year,50-year,1pct_min,100-year,1pct_plu,500-year
River Rch & RM= StreamM025,Reach-1,14081
     822    1345    1826    1201    2397    4783    4088
River Rch & RM= StreamM025,Reach-1,12262
     885    1449    1968    1294    2582    5151    4397
River Rch & RM= StreamM025,Reach-1,9955
    1068    1762    2402    1585    3162    6309    5424
River Rch & RM= StreamM025,Reach-1,7649
    1156    1912    2612    1725    3442    6869    5923
River Rch & RM= StreamM025,Reach-1,6320
    1226    2018    2748    1807    3606    7195    6153
Boundary for River Rch & Prof#=StreamM025,Reach-1,1
Up Type=0
Dn Type=3
Dn Slope=0.005
Boundary for River Rch & Prof#=StreamM025,Reach-1,2
Up Type=0
Dn Type=3
Dn Slope=0.005
Boundary for River Rch & Prof#=StreamM025,Reach-1,3
Up Type=0
Dn Type=3
Dn Slope=0.005
Boundary for River Rch & Prof#=StreamM025,Reach-1,4
Up Type=0
Dn Type=3
Dn Slope=0.005
Boundary for River Rch & Prof#=StreamM025,Reach-1,5
Up Type=0
Dn Type=3
Dn Slope=0.005
Boundary for River Rch & Prof#=StreamM025,Reach-1,6
Up Type=0
Dn Type=3
Dn Slope=0.005
Boundary for River Rch & Prof#=StreamM025,Reach-1,7
Up Type=0
Dn Type=3
Dn Slope=0.005

--- StreamM025.g01 (geometry) ---

Geom Title=Existing Conditions

River Reach=StreamM025,Reach-1
Reach XY= 30
      2493475.00     13851725.00      2493575.10     13851545.10
      2493471.46     13851126.46      2493326.05     13850964.57
      2493324.79     13849995.21      2493475.49     13849650.04
      2493374.96     13848590.34      2493575.02     13847995.00
      2493326.05     13847614.56      2493375.04     13847340.34
      2493274.89     13847094.89      2493424.67     13846959.97
      2493425.02     13845844.99      2493175.50     13845190.22
      2493235.51     13845015.19      2493469.48     13844827.44
      2493538.39     13844561.67      2494014.35     13844235.00
      2494225.45     13843780.17      2494219.97     13843630.08
      2494108.24     13843608.54      2493876.58     13843318.95
      2494067.18     13842521.58      2493777.07     13841869.14
      2493671.45     13841176.47      2493475.25     13840958.98
      2493625.69     13840645.06      2493424.89     13840409.64
      2493574.75     13840059.78      2493525.00     13839475.00

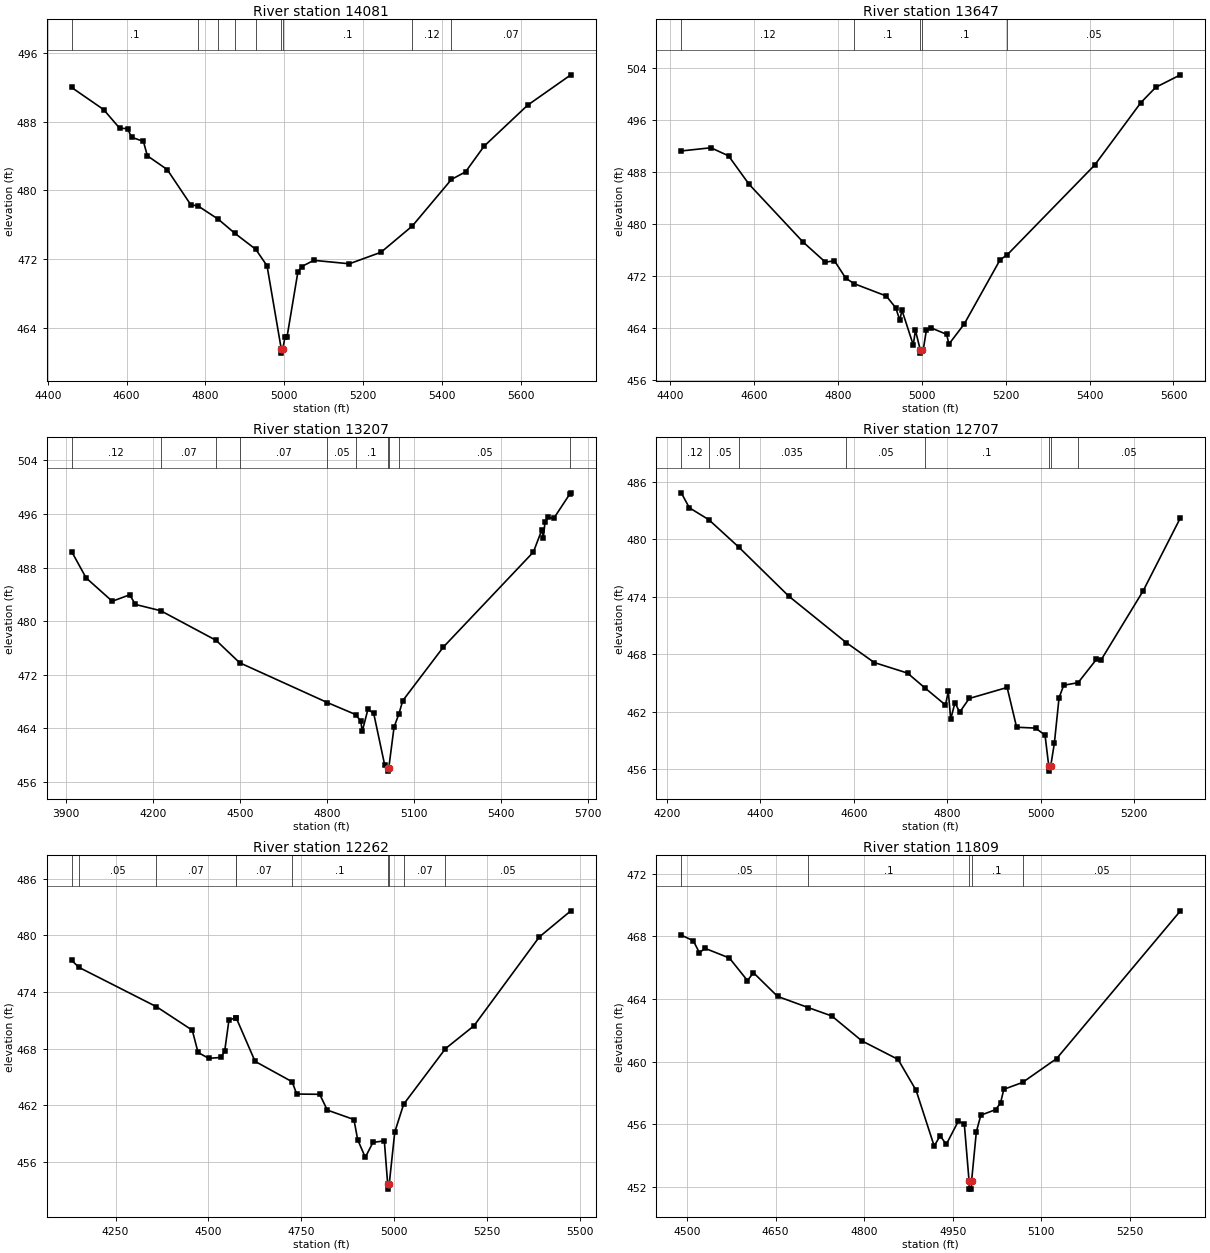
Type RM Length L Ch R = 1,14081,434,434,434
BEGIN DESCRIPTION:
StreamM025 29.0
END DESCRIPTION:
XS GIS Cut Line= 3
      2494066.24     13851421.63      2493525.00     13851475.00
      2492805.82     13851546.63
#Sta/Elev= 30
  4460.6  491.96  4541.6  489.40  4582.4  487.23  4602.5  487.18  4612.6  486.18
  4642.7  485.70  4652.8  484.02  4703.0  482.43  4763.3  478.31  4780.6  478.22
  4832.8  476.65  4874.7  475.02  4927.8  473.16  4956.4  471.24  4992.4  461.60
  4992.7  461.10  4996.4  461.60  5001.9  462.95  5007.0  462.95  5034.6  470.51
  5044.7  471.16  5074.8  471.88  5165.3  471.48  5245.6  472.82  5325.0  475.87
  5424.3  481.28  5460.1  482.16  5506.9  485.13  5617.5  489.90  5727.2  493.43
#Mann=9,-1,0
  4460.6     0.1       0  4780.6    0.12       0  4832.8     0.1       0
  4874.7    0.12       0  4927.8     0.1       0  4992.4    0.05       0
  4996.4     0.1       0  5325.0    0.12       0  5424.3    0.07       0
Bank Sta=4992.4,4996.4
Exp/Cntr=0.3,0.1

Type RM Length L Ch R = 1,13647,440,440,440
BEGIN DESCRIPTION:
StreamM025 28.0
END DESCRIPTION:
XS GIS Cut Line= 3
      2493972.48     13851249.77      2493425.00     13851075.00
      2492811.01     13851124.75
#Sta/Elev= 30
  4425.9  491.20  4496.7  491.69  4538.7  490.45  4587.8  486.07  4716.5  477.20
  4769.7  474.11  4791.4  474.32  4818.3  471.64  4838.8  470.79  4914.9  468.91
  4937.6  467.09  4947.1  465.20  4952.3  466.73  4979.3  461.39  4984.5  463.63
  4996.0  460.63  4996.2  460.13  5000.0  460.63  5003.1  460.63  5010.6  463.66
  5020.7  464.04  5059.1  463.01  5064.2  461.50  5100.9  464.61  5186.3  474.46
  5203.9  475.27  5411.9  489.02  5522.3  498.64  5557.6  500.98  5616.6  502.90
#Mann=5,-1,0
  4425.9    0.12       0  4838.8     0.1       0  4996.0    0.05       0
  5000.0     0.1       0  5203.9    0.05       0
Bank Sta=4996,5000
Exp/Cntr=0.3,0.1

Type RM Length L Ch R = 1,13207,500,500,500
BEGIN DESCRIPTION:
StreamM025 27.0
END DESCRIPTION:
XS GIS Cut Line= 3
      2494404.77     13850739.34      2493325.00     13850675.00
      2492685.97     13850645.59
#Sta/Elev= 30
  3918.3  490.39  3968.2  486.45  4058.3  482.96  4118.4  483.92  4138.5  482.48
  4225.3  481.55  4416.4  477.12  4497.7  473.77  4799.8  467.83  4898.3  466.02
  4915.4  465.03  4920.4  463.52  4939.9  466.80  4959.9  466.21  4997.5  458.55
  5008.0  458.08  5008.2  457.58  5012.0  458.08  5030.0  464.13  5047.1  466.17
  5060.1  468.11  5200.2  476.12  5510.5  490.31  5539.7  493.62  5544.7  492.39
  5550.6  494.78  5560.6  495.49  5580.6  495.33  5635.8  498.96  5639.7  499.16
#Mann=10,-1,0
  3918.3    0.12       0  4225.3    0.07       0  4416.4    0.12       0
  4497.7    0.07       0  4799.8    0.05       0  4898.3     0.1       0
  5008.0    0.05       0  5012.0     0.1       0  5047.1    0.05       0
  5635.8    0.12       0
Bank Sta=5008,5012
Exp/Cntr=0.3,0.1

Type RM Length L Ch R = 1,12707,445,445,445
BEGIN DESCRIPTION:
StreamM025 26.0
END DESCRIPTION:
XS GIS Cut Line= 3
      2494081.81     13850312.26      2493325.00     13850175.00
      2493024.96     13850175.00
#Sta/Elev= 30
  4230.5  484.83  4247.9  483.27  4289.7  482.02  4353.4  479.18  4461.0  474.04
  4583.7  469.21  4643.9  467.12  4715.1  466.02  4752.5  464.47  4796.4  462.69
  4802.5  464.11  4807.6  461.21  4816.7  462.92  4826.9  461.95  4847.2  463.37
  4928.5  464.52  4948.8  460.37  4989.5  460.28  5009.7  459.54  5017.7  456.29
  5017.9  455.79  5021.7  456.29  5029.7  458.72  5039.7  463.45  5049.7  464.75
  5080.5  465.02  5119.7  467.45  5129.7  467.39  5219.7  474.59  5299.7  482.23
#Mann=8,-1,0
  4230.5    0.12       0  4289.7    0.05       0  4353.4   0.035       0
  4583.7    0.05       0  4752.5     0.1       0  5017.7    0.05       0
  5021.7     0.1       0  5080.5    0.05       0
Bank Sta=5017.7,5021.7
Exp/Cntr=0.3,0.1

Type RM Length L Ch R = 1,12262,453,453,453
BEGIN DESCRIPTION:
StreamM025 25.0
END DESCRIPTION:
XS GIS Cut Line= 3
      2494227.62     13849958.08      2493375.00     13849775.00
      2492904.74     13849744.55
#Sta/Elev= 30
  4131.9  477.35  4151.2  476.61  4360.0  472.44  4456.5  469.95  4472.1  467.59
  4500.8  466.97  4533.5  467.06  4543.7  467.73  4555.3  471.04  4574.7  471.26
  4575.2  471.22  4625.5  466.65  4725.2  464.49  4737.5  463.19  4799.4  463.16
  4819.9  461.49  4891.5  460.49  4901.7  458.34  4922.1  456.49  4942.6  458.06
  4973.3  458.24  4982.4  453.62  4982.6  453.12  4986.4  453.62  5001.4  459.16
  5025.3  462.11  5137.9  468.00  5214.4  470.41  5390.3  479.82  5475.2  482.59
#Mann=10,-1,0
  4131.9    0.07       0  4151.2    0.05       0  4360.0    0.07       0
  4574.7    0.05       0  4575.2    0.07       0  4725.2     0.1       0
  4982.4    0.05       0  4986.4     0.1       0  5025.3    0.07       0
  5137.9    0.05       0
Bank Sta=4982.4,4986.4
Exp/Cntr=0.3,0.1

Type RM Length L Ch R = 1,11809,467,467,467
BEGIN DESCRIPTION:
StreamM025 24.0
END DESCRIPTION:
XS GIS Cut Line= 3
      2493924.96     13849474.99      2493425.00     13849375.00
      2493124.97     13849525.01
#Sta/Elev= 30
  4490.1  468.08  4510.5  467.72  4520.7  466.97  4530.8  467.23  4571.6  466.62
  4602.2  465.18  4612.4  465.68  4653.2  464.17  4705.5  463.45  4745.0  462.92
  4796.0  461.33  4857.2  460.15  4887.8  458.17  4918.4  454.62  4928.6  455.28
  4938.8  454.72  4959.2  456.20  4969.4  456.03  4977.5  452.37  4977.8  451.87
  4981.4  451.87  4981.7  452.37  4989.8  455.53  4997.4  456.59  5022.3  456.94
  5030.7  457.36  5036.3  458.24  5068.1  458.68  5125.7  460.20  5335.4  469.63
#Mann=5,-1,0
  4490.1    0.05       0  4705.5     0.1       0  4977.5    0.05       0
  4981.7     0.1       0  5068.1    0.05       0
Bank Sta=4977.5,4981.7
Exp/Cntr=0.3,0.1

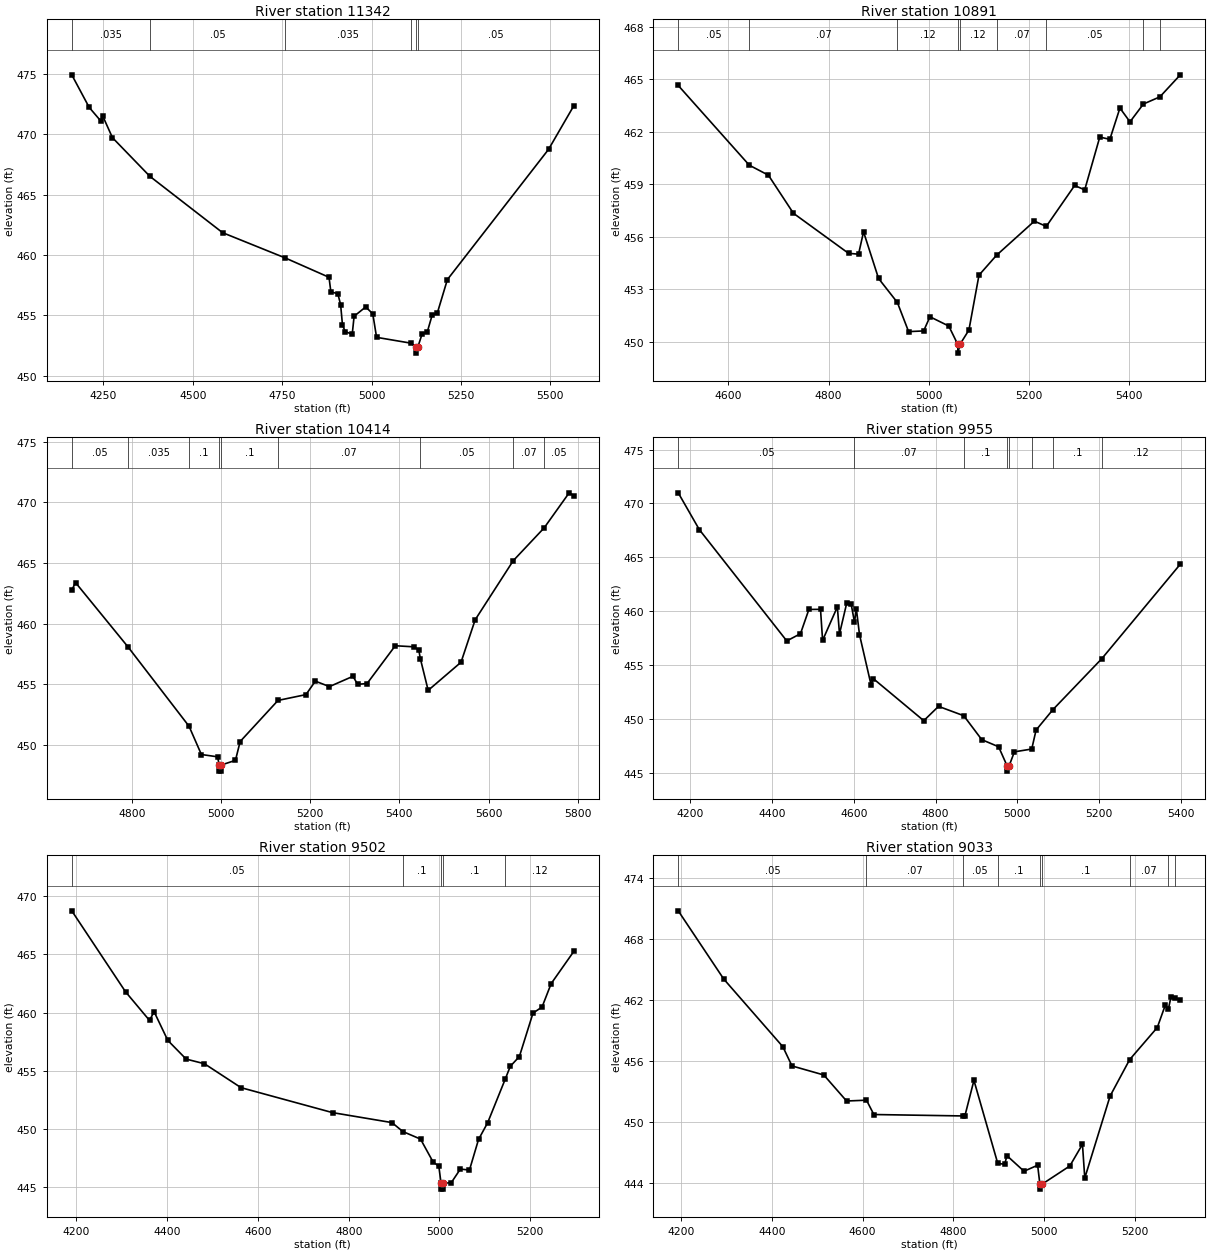
Type RM Length L Ch R = 1,11342,451,451,451
BEGIN DESCRIPTION:
StreamM025 23.0
END DESCRIPTION:
XS GIS Cut Line= 3
      2494175.02     13849175.01      2493375.00     13848925.00
      2492974.97     13849325.03
#Sta/Elev= 30
  4161.8  474.94  4210.5  472.24  4243.0  471.11  4248.3  471.53  4275.5  469.73
  4380.3  466.52  4583.5  461.85  4758.2  459.76  4881.1  458.15  4886.3  456.94
  4905.7  456.79  4913.5  455.89  4918.8  454.18  4926.6  453.64  4946.0  453.43
  4951.3  454.92  4983.7  455.69  5003.5  455.12  5014.1  453.17  5109.4  452.69
  5125.1  452.36  5125.4  451.86  5129.4  452.36  5141.4  453.45  5155.5  453.58
  5169.7  455.03  5183.8  455.17  5212.1  457.96  5495.0  468.76  5565.7  472.38
#Mann=6,-1,0
  4161.8   0.035       0  4380.3    0.05       0  4758.2   0.035       0
  5109.4    0.05       0  5125.1   0.035       0  5129.4    0.05       0
Bank Sta=5125.1,5129.4
Exp/Cntr=0.3,0.1

Type RM Length L Ch R = 1,10891,477,477,477
BEGIN DESCRIPTION:
StreamM025 22.0
END DESCRIPTION:
XS GIS Cut Line= 3
      2493925.05     13848525.00      2493425.00     13848525.00
      2492925.04     13848575.00
#Sta/Elev= 30
  4499.9  464.65  4641.8  460.09  4679.9  459.52  4729.9  457.34  4839.9  455.05
  4859.9  455.00  4869.9  456.28  4899.9  453.61  4937.4  452.24  4959.9  450.57
  4989.9  450.61  5002.5  451.42  5040.1  450.89  5058.0  449.84  5058.3  449.34
  5062.4  449.84  5080.3  450.66  5100.4  453.80  5135.5  454.94  5211.0  456.89
  5234.8  456.59  5291.4  458.93  5311.5  458.68  5341.6  461.70  5361.7  461.57
  5381.8  463.36  5401.9  462.57  5428.7  463.59  5461.6  464.00  5502.4  465.26
#Mann=9,-1,0
  4499.9    0.05       0  4641.8    0.07       0  4937.4    0.12       0
  5058.0    0.05       0  5062.4    0.12       0  5135.5    0.07       0
  5234.8    0.05       0  5428.7    0.07       0  5461.6    0.05       0
Bank Sta=5058,5062.4
Exp/Cntr=0.3,0.1

Type RM Length L Ch R = 1,10414,459,459,459
BEGIN DESCRIPTION:
StreamM025 21.0
END DESCRIPTION:
XS GIS Cut Line= 3
      2493875.04     13848275.02      2493575.00     13848125.00
      2492825.02     13847875.01
#Sta/Elev= 30
  4665.2  462.75  4673.6  463.38  4791.4  458.07  4928.2  451.53  4955.9  449.20
  4992.3  449.01  4995.7  448.33  4996.0  447.83  4999.8  447.83  5000.1  448.33
  5032.3  448.72  5042.8  450.27  5127.7  453.66  5190.4  454.14  5211.5  455.25
  5243.1  454.80  5295.8  455.65  5306.3  454.99  5327.4  455.05  5390.7  458.17
  5432.8  458.08  5443.4  457.82  5447.0  457.10  5464.5  454.49  5538.2  456.81
  5569.9  460.31  5655.2  465.18  5724.6  467.89  5780.7  470.78  5791.2  470.55
#Mann=9,-1,0
  4665.2    0.05       0  4791.4   0.035       0  4928.2     0.1       0
  4995.7    0.05       0  5000.1     0.1       0  5127.7    0.07       0
  5447.0    0.05       0  5655.2    0.07       0  5724.6    0.05       0
Bank Sta=4995.7,5000.1
Exp/Cntr=0.3,0.1

Type RM Length L Ch R = 1,9955,453,453,453
BEGIN DESCRIPTION:
StreamM025 20.0
END DESCRIPTION:
XS GIS Cut Line= 3
      2494225.00     13847525.00      2493425.00     13847725.00
      2493025.04     13847675.00
#Sta/Elev= 30
  4170.7  470.99  4222.2  467.58  4436.1  457.25  4469.6  457.92  4490.2  460.17
  4518.6  460.18  4523.7  457.30  4559.8  460.41  4565.0  457.90  4583.0  460.81
  4593.3  460.71  4601.7  458.99  4606.2  460.24  4613.9  457.84  4642.3  453.16
  4647.4  453.76  4771.1  449.85  4807.2  451.18  4868.9  450.31  4912.9  448.09
  4954.1  447.43  4974.7  445.67  4975.1  445.17  4979.9  445.67  4992.7  446.96
  5035.1  447.22  5045.7  448.98  5087.0  450.88  5206.6  455.61  5398.4  464.37
#Mann=8,-1,0
  4170.7    0.05       0  4601.7    0.07       0  4868.9     0.1       0
  4974.7    0.05       0  4979.9     0.1       0  5035.1    0.07       0
  5087.0     0.1       0  5206.6    0.12       0
Bank Sta=4974.7,4979.9
Exp/Cntr=0.3,0.1

Type RM Length L Ch R = 1,9502,469,469,469
BEGIN DESCRIPTION:
StreamM025 19.0
END DESCRIPTION:
XS GIS Cut Line= 3
      2494175.02     13847425.00      2493375.00     13847325.00
      2493075.04     13847325.00
#Sta/Elev= 30
  4189.8  468.76  4308.2  461.79  4361.1  459.32  4371.2  460.07  4401.4  457.60
  4441.8  455.99  4482.1  455.59  4562.7  453.53  4764.3  451.38  4895.3  450.52
  4919.2  449.75  4958.2  449.10  4986.0  447.12  4998.5  446.77  5003.4  445.29
  5003.8  444.79  5008.3  444.79  5008.7  445.29  5026.0  445.35  5046.0  446.52
  5066.0  446.43  5086.0  449.07  5106.0  450.50  5145.1  454.29  5156.0  455.37
  5176.0  456.21  5206.0  459.95  5226.0  460.48  5246.0  462.49  5296.0  465.27
#Mann=5,-1,0
  4189.8    0.05       0  4919.2     0.1       0  5003.4    0.05       0
  5008.7     0.1       0  5145.1    0.12       0
Bank Sta=5003.4,5008.7
Exp/Cntr=0.3,0.1

Type RM Length L Ch R = 1,9033,467,467,467
BEGIN DESCRIPTION:
StreamM025 18.0
END DESCRIPTION:
XS GIS Cut Line= 3
      2494224.97     13846925.00      2493425.00     13846975.00
      2493124.97     13847025.01
#Sta/Elev= 30
  4194.0  470.79  4294.2  464.08  4424.4  457.42  4444.5  455.53  4514.6  454.64
  4564.7  452.08  4608.6  452.16  4624.8  450.75  4820.5  450.61  4825.2  450.60
  4845.2  454.11  4897.6  445.95  4912.9  445.85  4917.9  446.70  4955.5  445.17
  4985.5  445.76  4990.4  443.91  4990.8  443.41  4995.7  443.91  5056.4  445.69
  5084.2  447.82  5089.3  444.50  5145.1  452.57  5188.1  456.15  5249.0  459.31
  5266.7  461.52  5273.2  461.09  5279.4  462.36  5288.5  462.26  5299.7  461.97
#Mann=9,-1,0
  4194.0    0.05       0  4608.6    0.07       0  4820.5    0.05       0
  4897.6     0.1       0  4990.4    0.05       0  4995.7     0.1       0
  5188.1    0.07       0  5273.2    0.12       0  5288.5    0.07       0
Bank Sta=4990.4,4995.7
Exp/Cntr=0.3,0.1

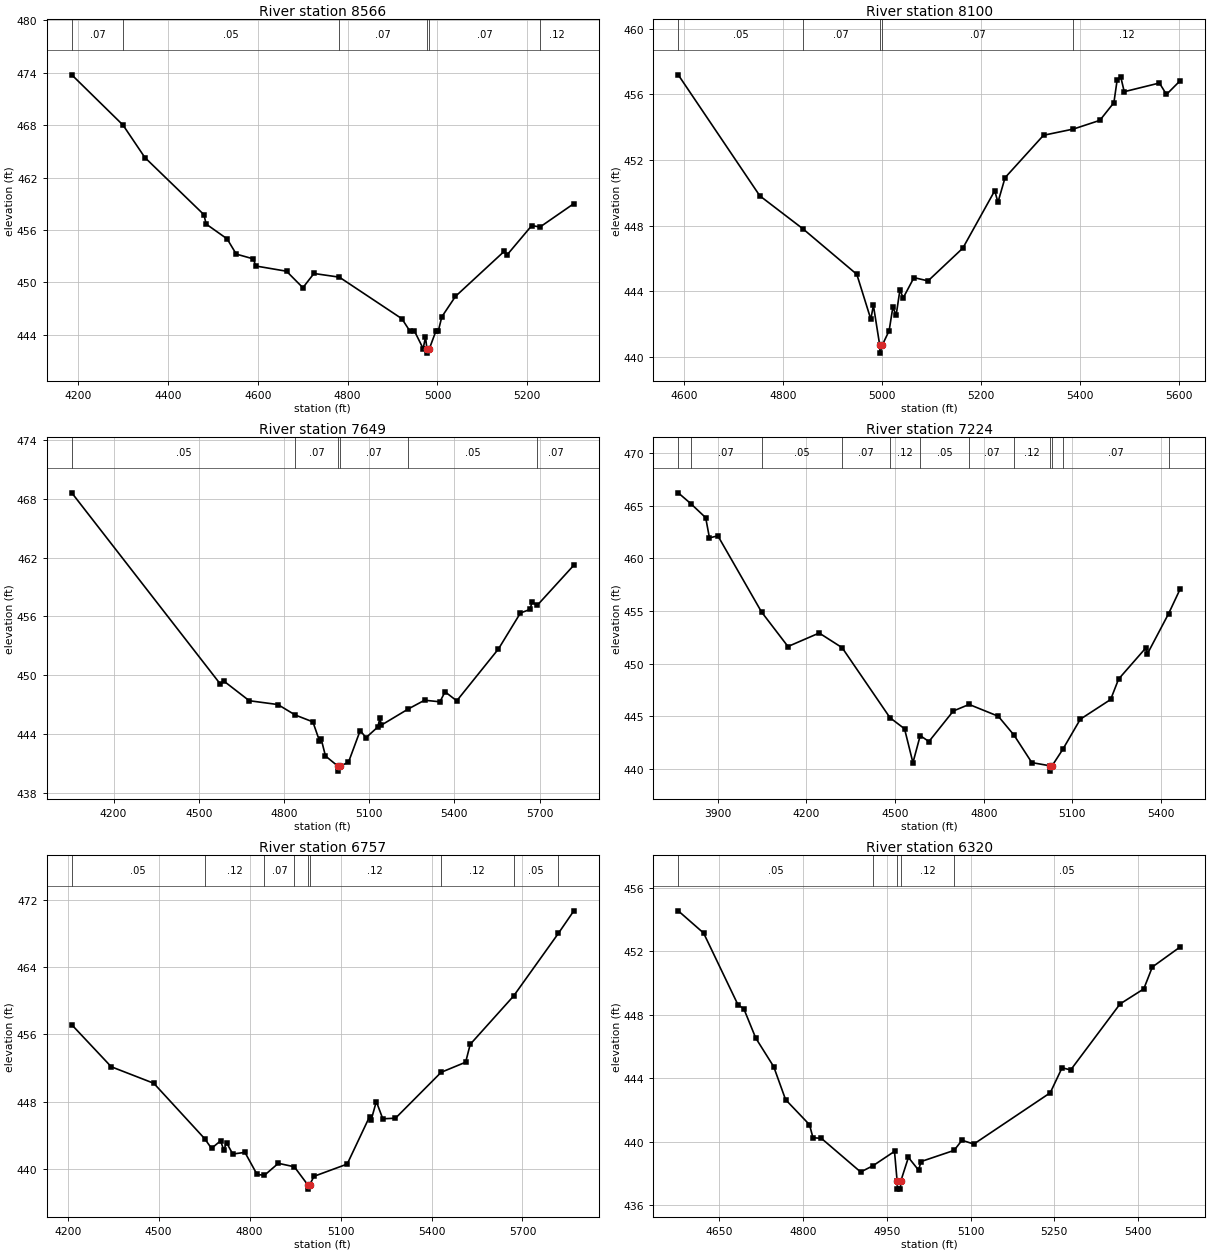
Type RM Length L Ch R = 1,8566,466,466,466
BEGIN DESCRIPTION:
StreamM025 17.0
END DESCRIPTION:
XS GIS Cut Line= 3
      2494175.04     13846374.99      2493375.00     13846525.00
      2493075.02     13846575.00
#Sta/Elev= 30
  4185.6  473.76  4299.8  468.00  4348.4  464.29  4479.8  457.75  4484.9  456.67
  4531.6  454.97  4551.9  453.23  4590.1  452.68  4595.2  451.87  4663.8  451.27
  4700.3  449.38  4724.9  451.01  4781.5  450.59  4920.7  445.83  4938.5  444.42
  4948.7  444.42  4968.2  442.40  4973.3  443.75  4976.5  442.39  4977.0  441.89
  4981.9  442.39  4997.0  444.48  5002.1  444.48  5009.7  446.05  5040.1  448.39
  5149.1  453.57  5154.2  453.09  5209.9  456.49  5228.6  456.34  5303.7  459.01
#Mann=6,-1,0
  4185.6    0.07       0  4299.8    0.05       0  4781.5    0.07       0
  4976.5    0.05       0  4981.9    0.07       0  5228.6    0.12       0
Bank Sta=4976.5,4981.9
Exp/Cntr=0.3,0.1

Type RM Length L Ch R = 1,8100,451,451,451
BEGIN DESCRIPTION:
StreamM025 16.0
END DESCRIPTION:
XS GIS Cut Line= 3
      2493825.01     13846175.00      2493425.00     13846075.00
      2492975.00     13846475.00
#Sta/Elev= 30
  4587.7  457.20  4752.6  449.81  4839.6  447.80  4948.5  445.02  4976.8  442.28
  4982.0  443.13  4994.7  440.71  4995.2  440.21  5000.1  440.71  5013.8  441.58
  5021.3  443.01  5028.0  442.53  5035.6  444.07  5042.2  443.58  5064.0  444.82
  5092.4  444.62  5162.7  446.62  5227.1  450.12  5233.7  449.42  5248.0  450.92
  5325.7  453.51  5386.1  453.89  5439.5  454.42  5467.9  455.50  5474.6  456.91
  5481.7  457.08  5488.8  456.17  5559.9  456.70  5574.1  456.00  5602.1  456.85
#Mann=5,-1,0
  4587.7    0.05       0  4839.6    0.07       0  4994.7    0.05       0
  5000.1    0.07       0  5386.1    0.12       0
Bank Sta=4994.7,5000.1
Exp/Cntr=0.3,0.1

Type RM Length L Ch R = 1,7649,425,425,425
BEGIN DESCRIPTION:
StreamM025 15.0
END DESCRIPTION:
XS GIS Cut Line= 3
      2494175.00     13846175.00      2493375.00     13845675.00
      2492575.02     13845475.00
#Sta/Elev= 30
  4052.7  468.61  4574.5  449.13  4589.8  449.35  4677.7  447.38  4778.5  446.99
  4839.6  445.92  4901.8  445.22  4924.8  443.29  4930.6  443.52  4946.0  441.74
  4990.2  440.69  4990.7  440.19  4996.0  440.69  5027.0  441.09  5068.3  444.33
  5088.9  443.61  5130.1  444.69  5137.8  445.59  5143.0  444.89  5238.4  446.55
  5295.0  447.43  5349.1  447.27  5367.2  448.29  5408.4  447.37  5555.3  452.67
  5632.6  456.34  5666.1  456.70  5673.8  457.46  5691.4  457.11  5820.7  461.22
#Mann=6,-1,0
  4052.7    0.05       0  4839.6    0.07       0  4990.2    0.05       0
  4996.0    0.07       0  5238.4    0.05       0  5691.4    0.07       0
Bank Sta=4990.2,4996
Exp/Cntr=0.3,0.1

Type RM Length L Ch R = 1,7224,467,467,467
BEGIN DESCRIPTION:
StreamM025 14.0
END DESCRIPTION:
XS GIS Cut Line= 3
      2494374.98     13845025.00      2493175.00     13845325.00
      2492724.99     13845225.00
#Sta/Elev= 30
  3767.0  466.22  3809.6  465.19  3859.8  463.86  3872.6  461.94  3901.0  462.14
  4048.7  454.91  4138.1  451.63  4243.7  452.91  4321.2  451.52  4483.1  444.87
  4532.3  443.82  4560.7  440.60  4585.3  443.17  4614.8  442.61  4697.3  445.51
  4750.7  446.13  4849.3  445.01  4902.7  443.21  4962.7  440.61  5025.3  440.30
  5025.8  439.80  5031.1  440.30  5067.3  441.86  5126.8  444.73  5229.3  446.60
  5256.2  448.54  5348.4  451.50  5353.5  450.93  5425.1  454.74  5464.9  457.12
#Mann=12,-1,0
  3767.0    0.05       0  3809.6    0.07       0  4048.7    0.05       0
  4321.2    0.07       0  4483.1    0.12       0  4585.3    0.05       0
  4750.7    0.07       0  4902.7    0.12       0  5025.3    0.05       0
  5031.1    0.12       0  5067.3    0.07       0  5425.1    0.12       0
Bank Sta=5025.3,5031.1
Exp/Cntr=0.3,0.1

Type RM Length L Ch R = 1,6757,437,437,437
BEGIN DESCRIPTION:
StreamM025 13.0
END DESCRIPTION:
XS GIS Cut Line= 3
      2494124.99     13844975.00      2493325.00     13844925.00
      2492524.96     13844624.98
#Sta/Elev= 30
  4213.4  457.15  4343.6  452.17  4483.9  450.21  4651.8  443.64  4674.3  442.49
  4704.3  443.39  4714.4  442.33  4724.4  443.13  4744.4  441.82  4784.5  442.02
  4824.6  439.40  4848.9  439.30  4894.7  440.72  4947.4  440.31  4992.0  438.16
  4992.5  437.66  4997.9  438.16  5012.4  439.18  5121.8  440.63  5195.6  446.25
  5201.0  445.87  5217.9  448.05  5239.2  446.00  5281.1  446.07  5431.6  451.51
  5512.5  452.71  5527.6  454.83  5670.5  460.55  5818.2  467.98  5869.4  470.66
#Mann=9,-1,0
  4213.4    0.05       0  4651.8    0.12       0  4848.9    0.07       0
  4947.4    0.12       0  4992.0    0.05       0  4997.9    0.12       0
  5431.6    0.12       0  5670.5    0.05       0  5818.2    0.07       0
Bank Sta=4992,4997.9
Exp/Cntr=0.3,0.1

Type RM Length L Ch R = 1,6320,443,443,443
BEGIN DESCRIPTION:
StreamM025 12.0
END DESCRIPTION:
XS GIS Cut Line= 3
      2493925.01     13844725.00      2493525.00     13844575.00
      2493125.01     13844325.00
#Sta/Elev= 30
  4576.7  454.56  4622.1  453.16  4683.5  448.65  4694.2  448.38  4715.5  446.54
  4747.6  444.74  4768.9  442.66  4811.7  441.08  4817.9  440.26  4833.0  440.22
  4903.3  438.10  4925.2  438.49  4963.9  439.40  4968.6  437.52  4969.1  437.02
  4974.6  437.02  4975.1  437.52  4988.8  439.02  5006.9  438.22  5011.6  438.76
  5070.5  439.46  5084.7  440.10  5105.9  439.86  5242.7  443.09  5263.9  444.67
  5279.3  444.53  5367.7  448.69  5410.2  449.64  5425.5  451.02  5475.6  452.29
#Mann=5,-1,0
  4576.7    0.05       0  4925.2    0.12       0  4968.6    0.05       0
  4975.1    0.12       0  5070.5    0.05       0
Bank Sta=4968.6,4975.1
Exp/Cntr=0.3,0.1

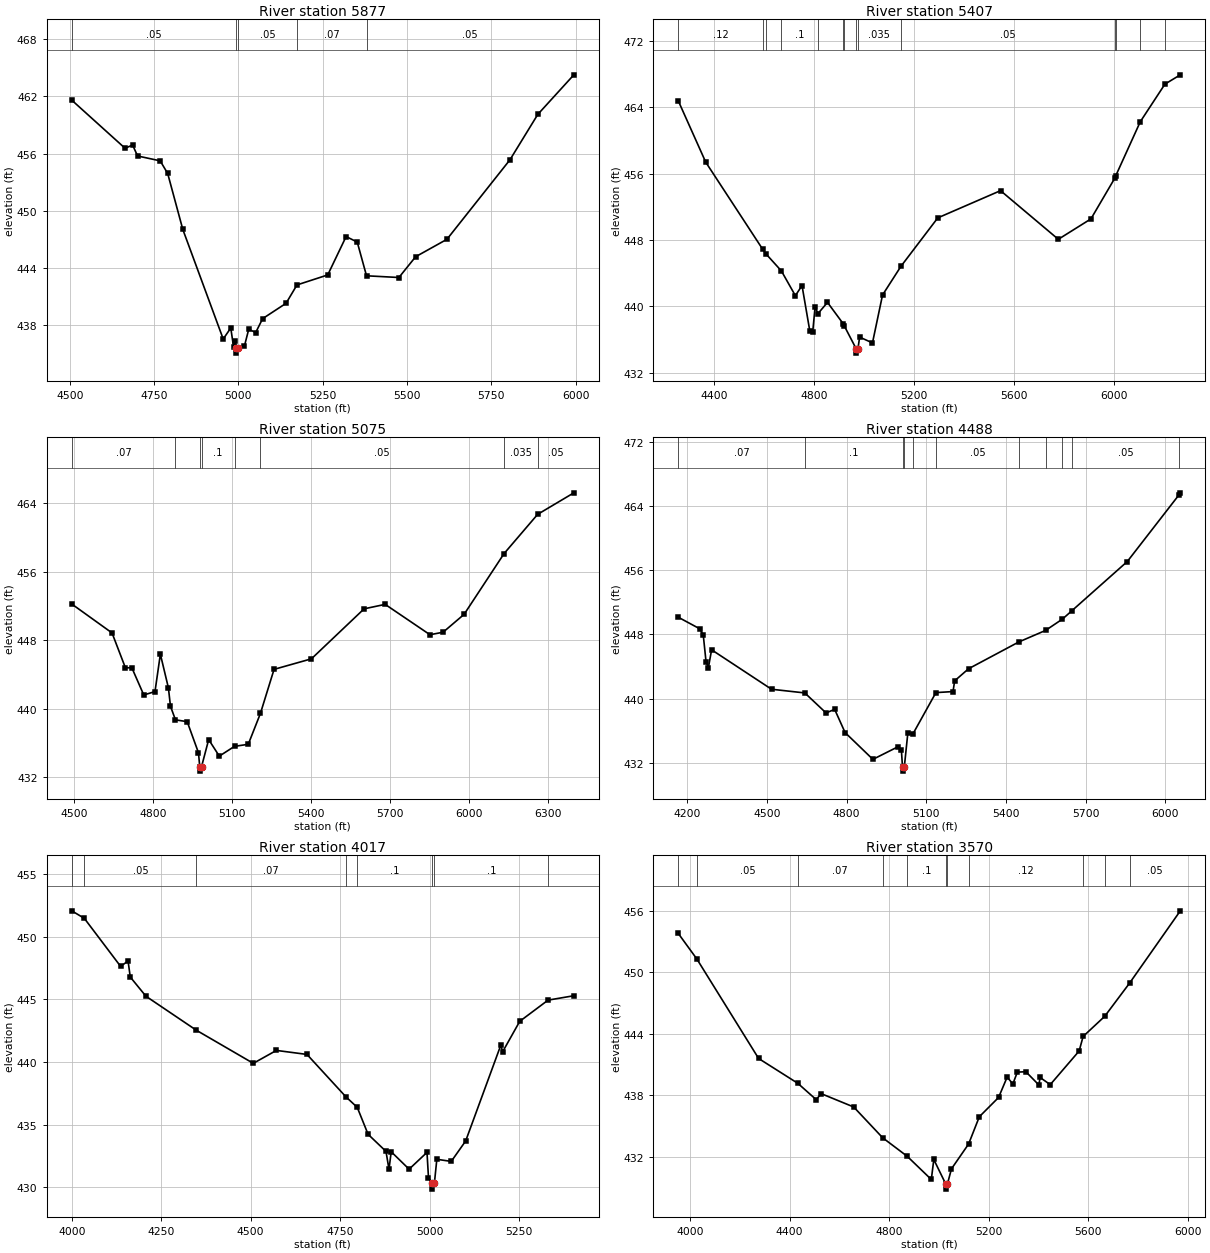
Type RM Length L Ch R = 1,5877,470,470,470
BEGIN DESCRIPTION:
StreamM025 11.0
END DESCRIPTION:
XS GIS Cut Line= 3
      2494316.22     13844546.65      2493875.00     13844325.00
      2492910.02     13844083.11
#Sta/Elev= 30
  4506.0  461.61  4664.0  456.56  4686.4  456.90  4701.1  455.75  4768.1  455.24
  4790.4  453.91  4835.1  448.05  4955.0  436.53  4977.4  437.69  4985.8  435.69
  4991.4  436.37  4993.7  435.55  4994.2  435.05  5000.3  435.55  5017.8  435.78
  5030.7  437.56  5051.3  437.21  5071.9  438.67  5141.3  440.28  5173.7  442.21
  5264.9  443.26  5319.4  447.29  5352.4  446.71  5379.9  443.17  5475.9  442.99
  5525.5  445.17  5618.3  447.00  5805.4  455.36  5887.8  460.12  5994.6  464.27
#Mann=5,-1,0
  4506.0    0.05       0  4993.7    0.05       0  5000.3    0.05       0
  5173.7    0.07       0  5379.9    0.05       0
Bank Sta=4993.7,5000.3
Exp/Cntr=0.3,0.1

Type RM Length L Ch R = 1,5407,332,332,332
BEGIN DESCRIPTION:
StreamM025 10.0
END DESCRIPTION:
XS GIS Cut Line= 3
      2494837.01     13844202.88      2494125.00     13843975.00
      2492869.14     13843843.60
#Sta/Elev= 30
  4256.6  464.77  4366.7  457.37  4594.5  446.89  4608.3  446.31  4669.6  444.27
  4725.6  441.29  4752.2  442.51  4783.7  436.99  4795.2  436.96  4804.7  439.97
  4815.8  439.12  4854.2  440.48  4918.3  437.86  4920.8  437.69  4969.4  434.87
  4969.9  434.37  4976.0  434.87  4982.9  436.30  5034.3  435.60  5074.6  441.37
  5148.4  444.83  5295.8  450.66  5547.1  453.94  5778.4  448.08  5909.1  450.54
  6005.7  455.50  6007.8  455.69  6106.6  462.24  6205.3  466.77  6266.9  467.89
#Mann=14,-1,0
  4256.6    0.12       0  4594.5    0.07       0  4608.3    0.12       0
  4669.6     0.1       0  4815.8    0.07       0  4918.3    0.05       0
  4920.8   0.035       0  4969.4   0.035       0  4976.0   0.035       0
  5148.4    0.05       0  6005.7   0.035       0  6007.8    0.05       0
  6106.6   0.035       0  6205.3    0.07       0
Bank Sta=4969.4,4976
Exp/Cntr=0.3,0.1

Type RM Length L Ch R = 1,5075,587,587,587
BEGIN DESCRIPTION:
StreamM025 9.0
END DESCRIPTION:
XS GIS Cut Line= 3
      2494724.96     13843575.01      2494196.40     13843682.05
      2492828.29     13843728.87
#Sta/Elev= 30
  4490.5  452.21  4643.5  448.84  4694.5  444.76  4718.6  444.79  4764.2  441.60
  4806.8  442.00  4827.2  446.36  4857.8  442.43  4865.6  440.29  4884.6  438.70
  4929.2  438.49  4972.1  434.86  4976.9  433.22  4977.4  432.72  4983.6  433.22
  5010.8  436.40  5051.2  434.47  5109.0  435.61  5161.3  435.85  5207.6  439.46
  5259.3  444.59  5401.4  445.82  5601.5  451.65  5681.6  452.17  5851.9  448.63
  5901.7  448.92  5981.7  451.01  6133.4  458.09  6261.1  462.67  6398.7  465.18
#Mann=8,-1,0
  4490.5    0.07       0  4884.6     0.1       0  4976.9    0.05       0
  4983.6     0.1       0  5109.0    0.07       0  5207.6    0.05       0
  6133.4   0.035       0  6261.1    0.05       0
Bank Sta=4976.9,4983.6
Exp/Cntr=0.3,0.1

Type RM Length L Ch R = 1,4488,471,471,471
BEGIN DESCRIPTION:
StreamM025 8.0
END DESCRIPTION:
XS GIS Cut Line= 3
      2494675.01     13843525.00      2493875.00     13843275.00
      2492838.48     13843463.03
#Sta/Elev= 30
  4165.4  450.16  4246.6  448.71  4259.7  447.93  4270.2  444.58  4279.1  443.87
  4291.1  446.09  4516.9  441.16  4642.3  440.70  4722.3  438.20  4754.7  438.65
  4794.0  435.75  4898.8  432.40  4993.1  433.97  5006.1  433.58  5010.4  431.43
  5010.9  430.93  5017.1  431.43  5030.3  435.65  5049.8  435.59  5136.2  440.74
  5200.7  440.87  5206.8  442.21  5259.2  443.72  5448.7  447.07  5549.4  448.51
  5613.1  449.93  5647.2  450.93  5857.3  457.12  6052.6  465.47  6057.0  465.70
#Mann=11,-1,0
  4165.4    0.07       0  4642.3     0.1       0  5010.4    0.05       0
  5017.1     0.1       0  5049.8    0.12       0  5136.2    0.05       0
  5448.7   0.035       0  5549.4    0.05       0  5613.1   0.035       0
  5647.2    0.05       0  6052.6    0.12       0
Bank Sta=5010.4,5017.1
Exp/Cntr=0.3,0.1

Type RM Length L Ch R = 1,4017,447,447,447
BEGIN DESCRIPTION:
StreamM025 7.0
END DESCRIPTION:
XS GIS Cut Line= 3
      2494775.00     13843475.00      2493975.00     13842875.00
      2493575.01     13842925.00
#Sta/Elev= 30
  4000.0  452.06  4035.1  451.46  4136.5  447.63  4157.3  448.06  4163.5  446.78
  4207.3  445.25  4348.1  442.54  4507.3  439.90  4571.9  440.93  4657.3  440.61
  4766.1  437.23  4797.8  436.39  4828.1  434.24  4878.1  432.88  4886.5  431.45
  4892.7  432.85  4942.7  431.46  4992.7  432.80  4996.9  430.79  5006.7  430.37
  5007.2  429.87  5013.5  430.37  5020.2  432.25  5060.5  432.08  5100.8  433.71
  5199.0  441.35  5204.1  440.82  5251.9  443.25  5331.1  444.94  5403.1  445.29
#Mann=8,-1,0
  4000.0    0.07       0  4035.1    0.05       0  4348.1    0.07       0
  4766.1    0.12       0  4797.8     0.1       0  5006.7    0.05       0
  5013.5     0.1       0  5331.1   0.035       0
Bank Sta=5006.7,5013.5
Exp/Cntr=0.3,0.1

Type RM Length L Ch R = 1,3570,441,441,441
BEGIN DESCRIPTION:
StreamM025 6.0
END DESCRIPTION:
XS GIS Cut Line= 3
      2495066.18     13842588.30      2494025.00     13842475.00
      2493071.36     13842656.02
#Sta/Elev= 30
  3952.7  453.77  4027.6  451.27  4275.8  441.57  4433.3  439.15  4507.1  437.56
  4527.3  438.14  4658.0  436.84  4774.3  433.84  4873.1  432.03  4969.9  429.77
  4979.9  431.72  5027.8  429.33  5028.3  428.83  5034.7  429.33  5050.9  430.81
  5119.8  433.23  5162.9  435.89  5240.3  437.77  5274.8  439.76  5297.6  439.08
  5315.6  440.24  5349.9  440.28  5402.1  438.99  5407.2  439.72  5447.9  439.02
  5564.0  442.30  5580.1  443.72  5666.8  445.68  5766.8  448.92  5970.7  455.97
#Mann=11,-1,0
  3952.7   0.035       0  4027.6    0.05       0  4433.3    0.07       0
  4774.3    0.12       0  4873.1     0.1       0  5027.8    0.05       0
  5034.7     0.1       0  5119.8    0.12       0  5580.1    0.05       0
  5666.8   0.035       0  5766.8    0.05       0
Bank Sta=5027.8,5034.7
Exp/Cntr=0.3,0.1

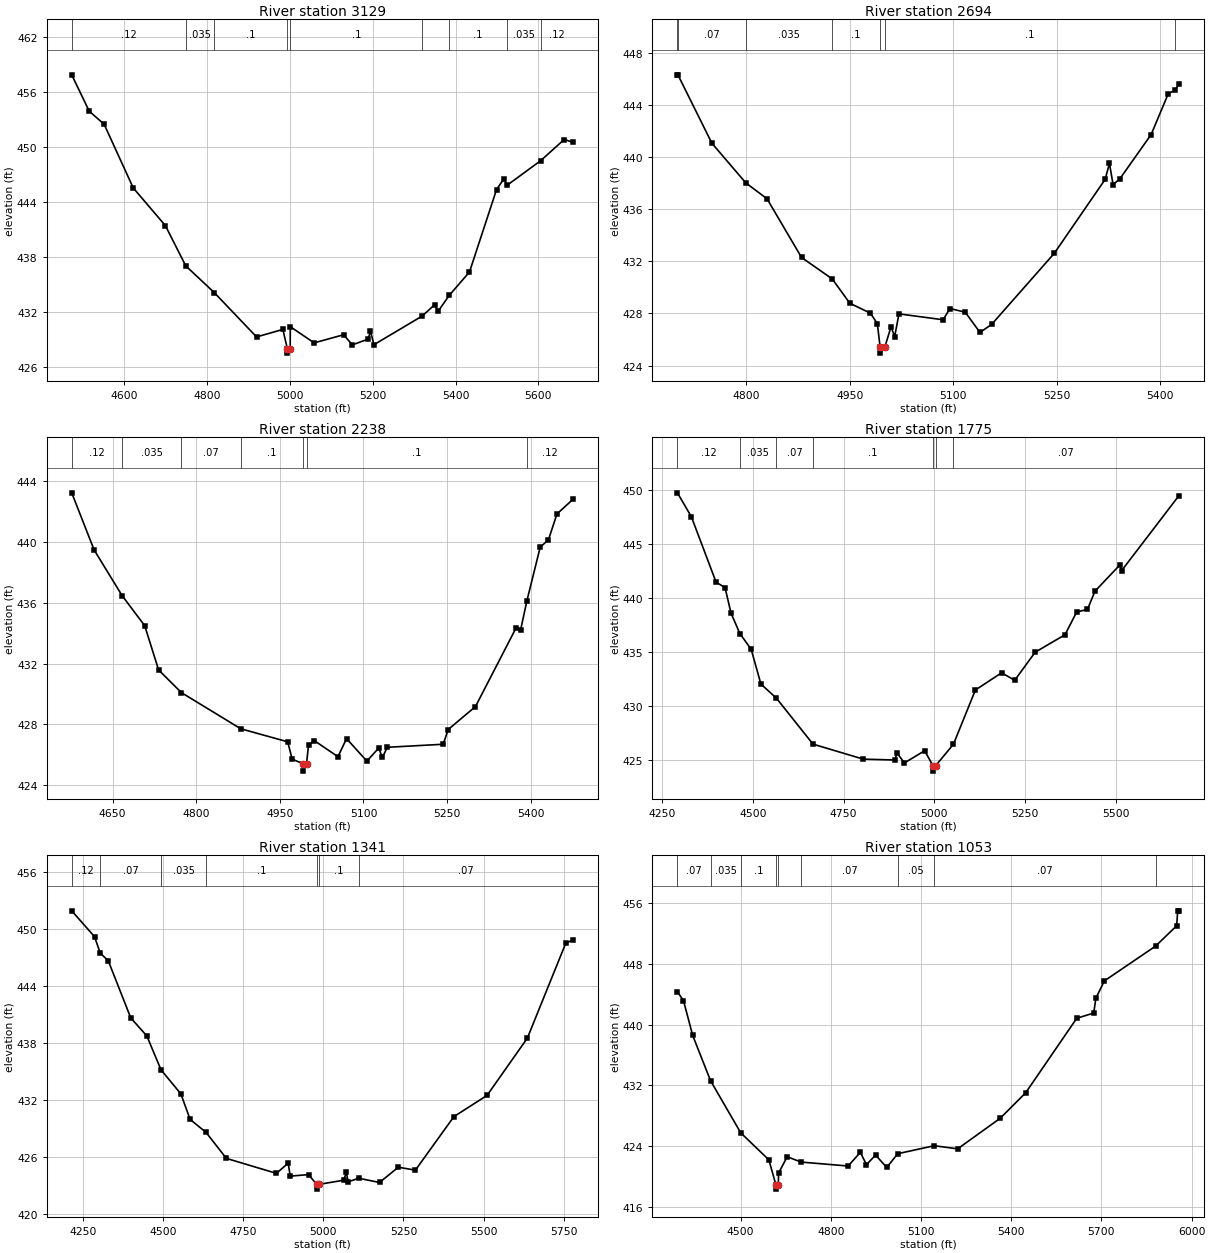
Type RM Length L Ch R = 1,3129,435,435,435
BEGIN DESCRIPTION:
StreamM025 5.0
END DESCRIPTION:
XS GIS Cut Line= 3
      2494275.03     13841774.98      2493875.00     13842125.00
      2493225.02     13841925.01
#Sta/Elev= 30
  4472.6  457.89  4514.9  453.91  4550.9  452.49  4621.2  445.53  4699.0  441.40
  4748.1  437.01  4817.4  434.07  4919.2  429.24  4982.8  430.06  4993.5  427.97
  4994.0  427.47  5000.5  427.97  5000.8  430.36  5058.4  428.59  5129.7  429.48
  5150.6  428.37  5189.2  429.01  5194.4  429.90  5202.9  428.39  5320.1  431.54
  5349.4  432.76  5357.9  432.04  5385.0  433.79  5433.8  436.34  5499.2  445.35
  5516.8  446.52  5524.5  445.81  5606.2  448.52  5662.6  450.82  5684.2  450.52
#Mann=9,-1,0
  4472.6    0.12       0  4748.1   0.035       0  4817.4     0.1       0
  4993.5    0.05       0  5000.5     0.1       0  5320.1   0.035       0
  5385.0     0.1       0  5524.5   0.035       0  5606.2    0.12       0
Bank Sta=4993.5,5000.5
Exp/Cntr=0.3,0.1

Type RM Length L Ch R = 1,2694,456,456,456
BEGIN DESCRIPTION:
StreamM025 4.0
END DESCRIPTION:
XS GIS Cut Line= 3
      2494074.97     13841725.00      2493775.00     13841725.00
      2493374.98     13841875.01
#Sta/Elev= 30
  4700.1  446.30  4700.8  446.30  4750.1  441.05  4799.3  438.01  4830.1  436.79
  4880.1  432.29  4924.7  430.64  4950.1  428.78  4980.1  428.01  4990.1  427.21
  4994.0  425.45  4994.5  424.95  5001.1  425.45  5009.9  426.97  5015.2  426.22
  5021.4  427.96  5085.5  427.51  5095.3  428.37  5117.6  428.09  5138.9  426.54
  5155.8  427.15  5246.6  432.60  5320.5  438.28  5326.7  439.51  5332.0  437.88
  5341.8  438.32  5387.2  441.72  5412.1  444.86  5421.5  445.10  5427.3  445.56
#Mann=7,-1,0
  4700.1    0.12       0  4700.8    0.07       0  4799.3   0.035       0
  4924.7     0.1       0  4994.0    0.05       0  5001.1     0.1       0
  5421.5    0.12       0
Bank Sta=4994,5001.1
Exp/Cntr=0.3,0.1

Type RM Length L Ch R = 1,2238,463,463,463
BEGIN DESCRIPTION:
StreamM025 3.0
END DESCRIPTION:
XS GIS Cut Line= 3
      2494075.01     13841175.00      2493675.00     13841325.00
      2493275.01     13841574.99
#Sta/Elev= 30
  4576.9  443.25  4617.0  439.49  4667.2  436.48  4707.7  434.50  4732.7  431.58
  4773.6  430.09  4879.9  427.71  4964.1  426.85  4972.1  425.71  4990.8  425.42
  4991.3  424.92  4997.9  425.42  5001.4  426.63  5011.8  426.93  5054.2  425.87
  5069.6  427.06  5106.1  425.58  5127.3  426.44  5133.8  425.82  5142.7  426.49
  5242.9  426.69  5251.8  427.66  5300.7  429.17  5373.8  434.37  5381.5  434.19
  5392.9  436.13  5416.8  439.67  5431.6  440.16  5446.9  441.86  5475.8  442.83
#Mann=7,-1,0
  4576.9    0.12       0  4667.2   0.035       0  4773.6    0.07       0
  4879.9     0.1       0  4990.8    0.05       0  4997.9     0.1       0
  5392.9    0.12       0
Bank Sta=4990.8,4997.9
Exp/Cntr=0.3,0.1

Type RM Length L Ch R = 1,1775,434,434,434
BEGIN DESCRIPTION:
H21221
END DESCRIPTION:
XS GIS Cut Line= 3
      2494162.35     13841076.10      2493580.22     13840930.56
      2492820.52     13841118.71
#Sta/Elev= 30
  4291.5  449.74  4330.0  447.52  4398.1  441.46  4422.8  440.96  4439.3  438.59
  4463.7  436.70  4494.9  435.24  4521.7  432.02  4564.5  430.71  4665.4  426.45
  4804.2  425.06  4891.6  424.98  4896.9  425.64  4917.5  424.71  4973.3  425.84
  4996.3  424.45  4996.8  423.95  5003.5  424.45  5052.7  426.44  5113.3  431.47
  5185.5  433.06  5221.7  432.37  5278.1  434.97  5360.5  436.59  5392.5  438.70
  5422.3  438.93  5442.9  440.62  5511.5  443.05  5516.7  442.54  5674.2  449.46
#Mann=7,-1,0
  4291.5    0.12       0  4463.7   0.035       0  4564.5    0.07       0
  4665.4     0.1       0  4996.3    0.05       0  5003.5     0.1       0
  5052.7    0.07       0
Bank Sta=4996.3,5003.5
Exp/Cntr=0.3,0.1

Type RM Length L Ch R = 1,1341,288,288,288
BEGIN DESCRIPTION:
StreamM025 2.0
END DESCRIPTION:
XS GIS Cut Line= 3
      2494225.03     13841075.02      2493625.00     13840575.00
      2492924.99     13840925.01
#Sta/Elev= 30
  4215.3  451.91  4286.3  449.19  4304.4  447.44  4329.2  446.65  4399.5  440.62
  4449.6  438.72  4493.8  435.15  4555.7  432.62  4584.4  429.93  4634.2  428.56
  4697.6  425.82  4853.8  424.24  4890.3  425.32  4896.8  423.95  4954.1  424.11
  4979.0  423.08  4979.5  422.58  4986.3  423.08  5063.4  423.52  5071.8  424.36
  5077.4  423.35  5110.4  423.73  5175.2  423.28  5233.9  424.89  5287.1  424.58
  5407.2  430.22  5510.7  432.46  5636.4  438.50  5756.6  448.54  5779.0  448.81
#Mann=7,-1,0
  4215.3    0.12       0  4304.4    0.07       0  4493.8   0.035       0
  4634.2     0.1       0  4979.0    0.05       0  4986.3     0.1       0
  5110.4    0.07       0
Bank Sta=4979,4986.3
Exp/Cntr=0.3,0.1

Type RM Length L Ch R = 1,1053,644,644,644
BEGIN DESCRIPTION:
StreamM025 1.0
END DESCRIPTION:
XS GIS Cut Line= 3
      2494124.96     13840275.01      2493345.93     13840405.19
      2492724.98     13841025.02
#Sta/Elev= 30
  4290.1  444.31  4310.3  443.14  4340.8  438.57  4400.3  432.60  4500.6  425.75
  4594.2  422.19  4618.0  418.84  4618.5  418.34  4625.3  418.84  4626.7  420.47
  4655.1  422.60  4701.4  421.90  4857.8  421.38  4898.4  423.18  4918.7  421.56
  4949.1  422.82  4986.2  421.19  5022.6  423.00  5144.0  424.05  5221.9  423.64
  5363.3  427.66  5448.2  431.02  5617.9  440.82  5674.4  441.51  5681.5  443.46
  5709.8  445.74  5879.9  450.31  5950.2  452.99  5953.7  454.96  5957.3  454.96
#Mann=9,-1,0
  4290.1    0.07       0  4400.3   0.035       0  4500.6     0.1       0
  4618.0    0.05       0  4625.3     0.1       0  4701.4    0.07       0
  5022.6    0.05       0  5144.0    0.07       0  5879.9    0.12       0
Bank Sta=4618,4625.3
Exp/Cntr=0.3,0.1

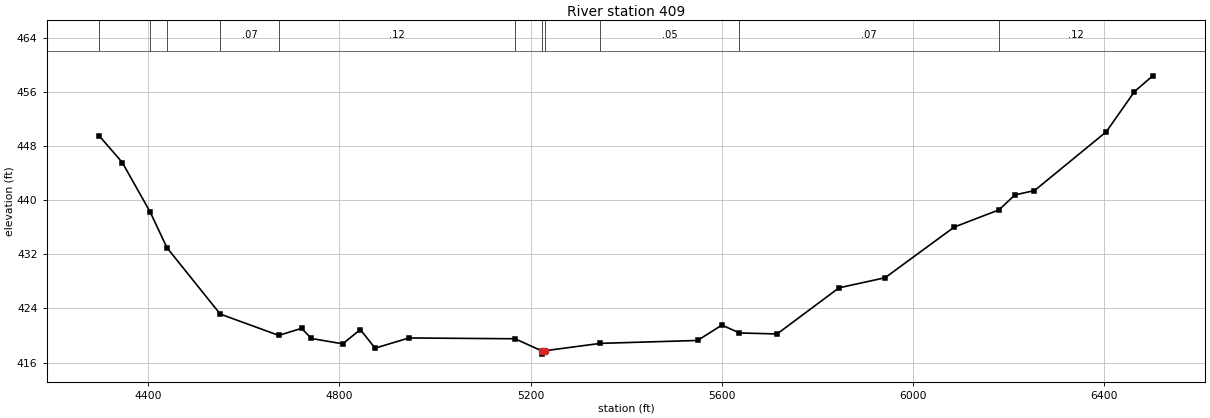
Type RM Length L Ch R = 1,409,0,0,0
BEGIN DESCRIPTION:
H21220
END DESCRIPTION:
XS GIS Cut Line= 4
      2494197.89     13839940.17      2493590.87     13839805.27
      2492809.91     13840341.30      2492550.79     13840919.87
#Sta/Elev= 30
  4298.0  449.48  4346.0  445.56  4404.1  438.27  4439.5  432.96  4550.8  423.16
  4673.2  420.01  4721.0  421.05  4741.5  419.55  4806.9  418.76  4843.9  420.87
  4874.6  418.12  4945.5  419.63  5167.3  419.51  5222.7  417.74  5223.2  417.24
  5230.0  417.74  5345.8  418.83  5549.1  419.26  5599.9  421.53  5636.7  420.37
  5715.3  420.22  5844.9  427.04  5941.3  428.53  6085.9  436.02  6179.4  438.56
  6212.8  440.77  6253.7  441.41  6403.8  450.10  6462.8  456.04  6501.0  458.37
#Mann=11,-1,0
  4298.0    0.05       0  4404.1   0.035       0  4439.5    0.05       0
  4550.8    0.07       0  4673.2    0.12       0  5167.3    0.07       0
  5222.7    0.05       0  5230.0    0.07       0  5345.8    0.05       0
  5636.7    0.07       0  6179.4    0.12       0
Bank Sta=5222.7,5230
Exp/Cntr=0.3,0.1

Chan Stop Cuts=-1