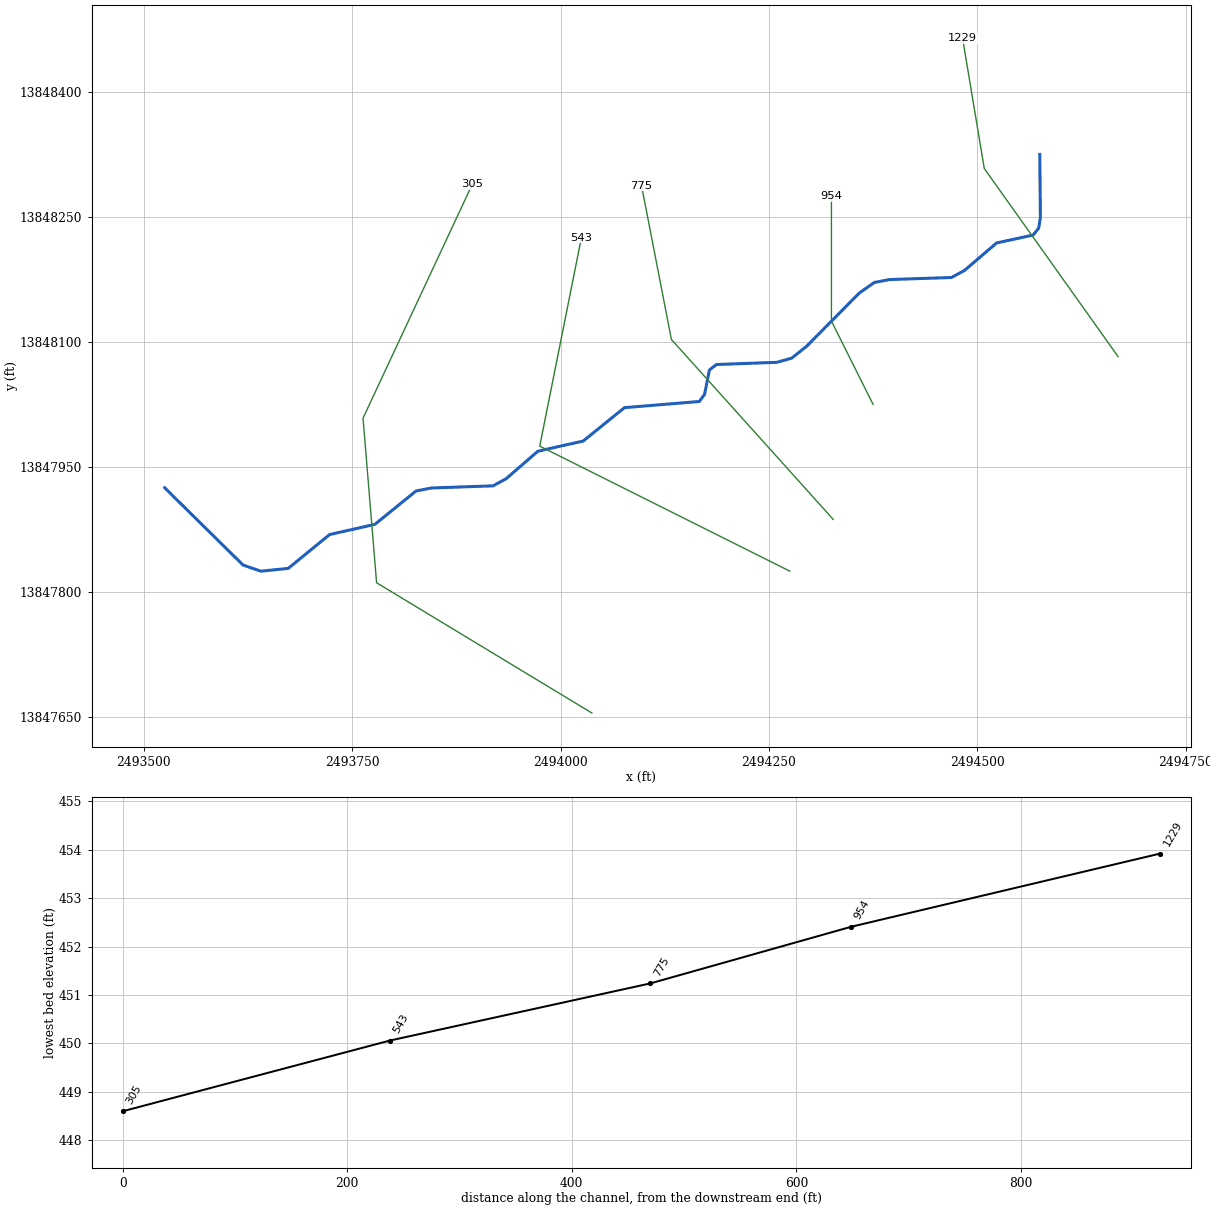
--- StreamM026.prj (project) ---

Proj Title=StreamM026 Base Level Engineering
Current Plan=p01
Default Exp/Contr=0.3,0.1
English Units
Geom File=g01
Flow File=f01
Plan File=p01
BEGIN DESCRIPTION:
StreamM026
END DESCRIPTION:

--- StreamM026.p01 (plan) ---

Plan Title=Multiple Run
Short Identifier=Multiple
Geom File=g01
Flow File=f01
Subcritical Flow
K Sum by GR= 0
Std Step Tol= 0.01
Critical Tol= 0.01
Num of Std Step Trials= 20
Max Error Tol= 0.3
Flow Tol Ratio= 0.001
Split Flow NTrial= 30
Split Flow Tol= 0.02
Split Flow Ratio= 0.02
Log Output Level= 0
Friction Slope Method= 1
Unsteady Friction Slope Method= 2
Unsteady Bridges Friction Slope Method= 1
Parabolic Critical Depth
Global Vel Dist=  1 , 1 , 1
Global Log Level= 0
CheckData=True
Encroach Param= -1, 0, 0, 0
BEGIN DESCRIPTION:
Multiple Run
END DESCRIPTION:

--- StreamM026.f01 (steady flow) ---

Flow Title=Multiple
Number of Profiles=7
Profile Names=10-year,25-year,50-year,1pct_min,100-year,1pct_plu,500-year
River Rch & RM= StreamM026,Reach-1,1229
     394     614     807     516    1029    2054    1652
Boundary for River Rch & Prof#=StreamM026,Reach-1,1
Up Type=0
Dn Type=3
Dn Slope=0.005
Boundary for River Rch & Prof#=StreamM026,Reach-1,2
Up Type=0
Dn Type=3
Dn Slope=0.005
Boundary for River Rch & Prof#=StreamM026,Reach-1,3
Up Type=0
Dn Type=3
Dn Slope=0.005
Boundary for River Rch & Prof#=StreamM026,Reach-1,4
Up Type=0
Dn Type=3
Dn Slope=0.005
Boundary for River Rch & Prof#=StreamM026,Reach-1,5
Up Type=0
Dn Type=3
Dn Slope=0.005
Boundary for River Rch & Prof#=StreamM026,Reach-1,6
Up Type=0
Dn Type=3
Dn Slope=0.005
Boundary for River Rch & Prof#=StreamM026,Reach-1,7
Up Type=0
Dn Type=3
Dn Slope=0.005

--- StreamM026.g01 (geometry) ---

Geom Title=Existing Conditions

River Reach=StreamM026,Reach-1
Reach XY= 30
      2494575.00     13848325.00      2494575.73     13848249.42
      2494573.68     13848236.55      2494567.03     13848228.27
      2494523.19     13848218.75      2494484.71     13848185.81
      2494469.06     13848177.32      2494395.05     13848174.87
      2494376.50     13848171.38      2494358.26     13848158.51
      2494295.12     13848094.68      2494277.36     13848080.56
      2494259.66     13848075.57      2494187.02     13848072.92
      2494178.61     13848066.36      2494172.80     13848037.23
      2494166.50     13848028.55      2494076.65     13848021.15
      2494027.19     13847981.11      2493972.82     13847968.89
      2493934.65     13847935.84      2493919.03     13847927.33
      2493845.10     13847924.77      2493826.58     13847921.17
      2493777.18     13847881.11      2493722.80     13847868.84
      2493673.27     13847828.31      2493640.34     13847824.91
      2493618.92     13847832.38      2493525.00     13847925.00

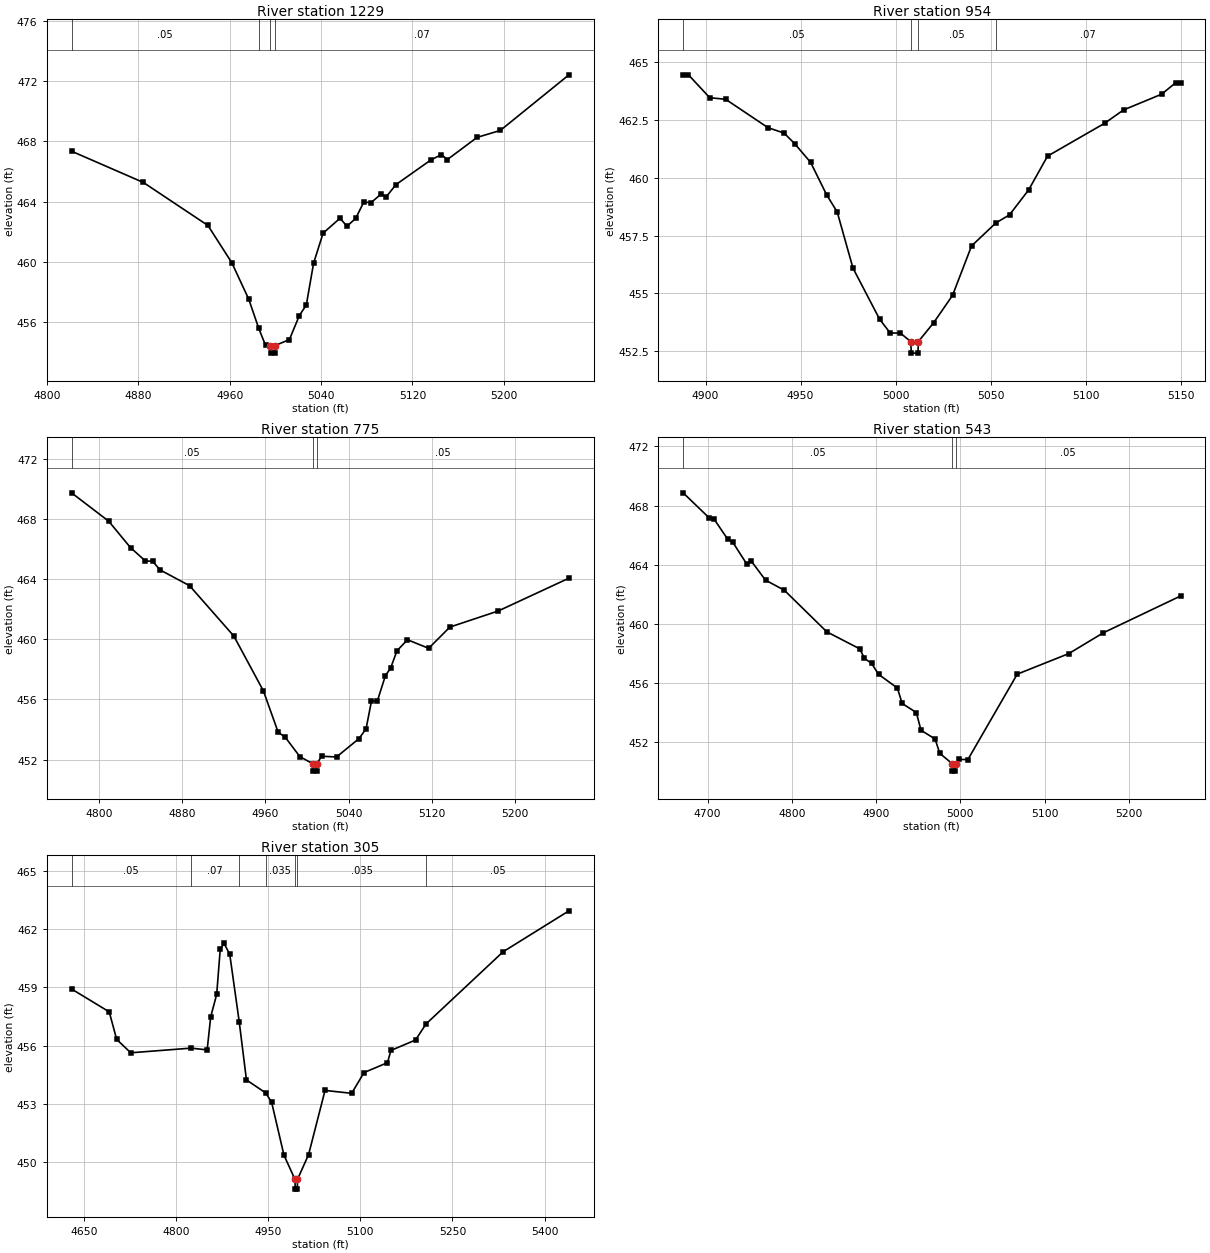
Type RM Length L Ch R = 1,1229,275,275,275
BEGIN DESCRIPTION:
H21224
END DESCRIPTION:
XS GIS Cut Line= 3
      2494668.99     13848082.37      2494508.42     13848308.03
      2494482.37     13848464.31
#Sta/Elev= 30
  4821.6  467.35  4884.5  465.27  4941.0  462.41  4961.9  459.93  4976.7  457.51
  4985.5  455.56  4991.4  454.44  4995.6  454.42  4995.8  453.92  4999.3  453.92
  4999.6  454.42  5012.3  454.82  5021.0  456.42  5027.1  457.12  5033.5  459.91
  5041.8  461.90  5056.6  462.89  5062.7  462.36  5070.3  462.88  5077.5  463.98
  5083.6  463.92  5092.3  464.48  5097.2  464.33  5105.6  465.13  5136.0  466.76
  5145.4  467.13  5150.5  466.79  5176.6  468.27  5196.9  468.73  5257.0  472.43
#Mann=4,-1,0
  4821.6    0.05       0  4985.5    0.07       0  4995.6    0.05       0
  4999.6    0.07       0
Bank Sta=4995.6,4999.6
Exp/Cntr=0.3,0.1

Type RM Length L Ch R = 1,954,179,179,179
BEGIN DESCRIPTION:
StreamM026 2.0
END DESCRIPTION:
XS GIS Cut Line= 3
      2494375.00     13848025.00      2494325.00     13848125.00
      2494325.00     13848274.99
#Sta/Elev= 30
  4888.2  464.46  4891.0  464.46  4902.2  463.47  4910.6  463.40  4932.9  462.17
  4941.3  461.94  4946.9  461.48  4955.3  460.67  4963.7  459.27  4969.3  458.52
  4977.6  456.09  4991.6  453.88  4997.2  453.28  5002.5  453.28  5008.0  452.91
  5008.3  452.41  5011.8  452.41  5012.0  452.91  5020.0  453.72  5030.0  454.91
  5040.0  457.05  5052.7  458.04  5060.0  458.40  5070.0  459.47  5080.0  460.94
  5110.0  462.36  5120.0  462.94  5140.0  463.62  5147.5  464.12  5150.0  464.12
#Mann=4,-1,0
  4888.2    0.05       0  5008.0    0.05       0  5012.0    0.05       0
  5052.7    0.07       0
Bank Sta=5008,5012
Exp/Cntr=0.3,0.1

Type RM Length L Ch R = 1,775,232,232,232
BEGIN DESCRIPTION:
H21223
END DESCRIPTION:
XS GIS Cut Line= 3
      2494327.19     13847887.04      2494132.99     13848102.95
      2494097.18     13848287.41
#Sta/Elev= 30
  4773.5  469.73  4809.3  467.84  4830.2  466.09  4844.4  465.21  4851.5  465.18
  4858.6  464.61  4887.0  463.56  4929.6  460.21  4958.0  456.57  4972.2  453.82
  4978.9  453.50  4993.1  452.20  5005.3  451.74  5005.6  451.24  5009.1  451.24
  5009.3  451.74  5014.1  452.23  5028.3  452.18  5049.9  453.40  5056.7  454.05
  5061.9  455.89  5067.5  455.89  5075.3  457.58  5080.4  458.10  5086.4  459.23
  5096.5  459.97  5116.9  459.40  5137.3  460.81  5183.8  461.88  5251.8  464.06
#Mann=3,-1,0
  4773.5    0.05       0  5005.3    0.05       0  5009.3    0.05       0
Bank Sta=5005.3,5009.3
Exp/Cntr=0.3,0.1

Type RM Length L Ch R = 1,543,238,238,238
BEGIN DESCRIPTION:
StreamM026 1.0
END DESCRIPTION:
XS GIS Cut Line= 3
      2494274.96     13847825.02      2493975.00     13847975.00
      2494025.00     13848224.99
#Sta/Elev= 30
  4671.0  468.86  4701.7  467.18  4707.3  467.12  4724.1  465.71  4729.6  465.55
  4746.4  464.06  4752.0  464.24  4768.8  462.96  4791.1  462.28  4841.5  459.47
  4880.6  458.32  4886.2  457.68  4894.6  457.34  4902.9  456.60  4925.3  455.67
  4930.9  454.63  4947.7  454.02  4953.3  452.82  4970.0  452.23  4975.6  451.26
  4990.4  450.56  4990.6  450.06  4994.1  450.06  4994.4  450.56  4998.0  450.85
  5008.9  450.84  5067.5  456.61  5128.7  458.00  5169.5  459.40  5261.3  461.89
#Mann=3,-1,0
  4671.0    0.05       0  4990.4    0.05       0  4994.4    0.05       0
Bank Sta=4990.4,4994.4
Exp/Cntr=0.3,0.1

Type RM Length L Ch R = 1,305,0,0,0
BEGIN DESCRIPTION:
H21222
END DESCRIPTION:
XS GIS Cut Line= 4
      2494037.53     13847654.80      2493779.25     13847811.06
      2493762.98     13848008.55      2493894.27     13848289.57
#Sta/Elev= 30
  4629.6  458.92  4691.0  457.74  4703.1  456.32  4726.1  455.63  4824.2  455.87
  4850.5  455.78  4856.3  457.49  4866.0  458.64  4871.8  460.97  4878.0  461.27
  4887.3  460.71  4902.8  457.21  4914.5  454.23  4945.9  453.56  4955.5  453.08
  4975.6  450.35  4993.6  449.10  4993.9  448.60  4997.4  448.60  4997.6  449.10
  5015.7  450.38  5042.5  453.69  5085.9  453.54  5106.0  454.61  5144.2  455.12
  5149.8  455.75  5189.9  456.29  5207.1  457.12  5332.6  460.84  5439.8  462.95
#Mann=7,-1,0
  4629.6    0.05       0  4824.2    0.07       0  4902.8    0.05       0
  4945.9   0.035       0  4993.6   0.035       0  4997.6   0.035       0
  5207.1    0.05       0
Bank Sta=4993.6,4997.6
Exp/Cntr=0.3,0.1

Chan Stop Cuts=-1