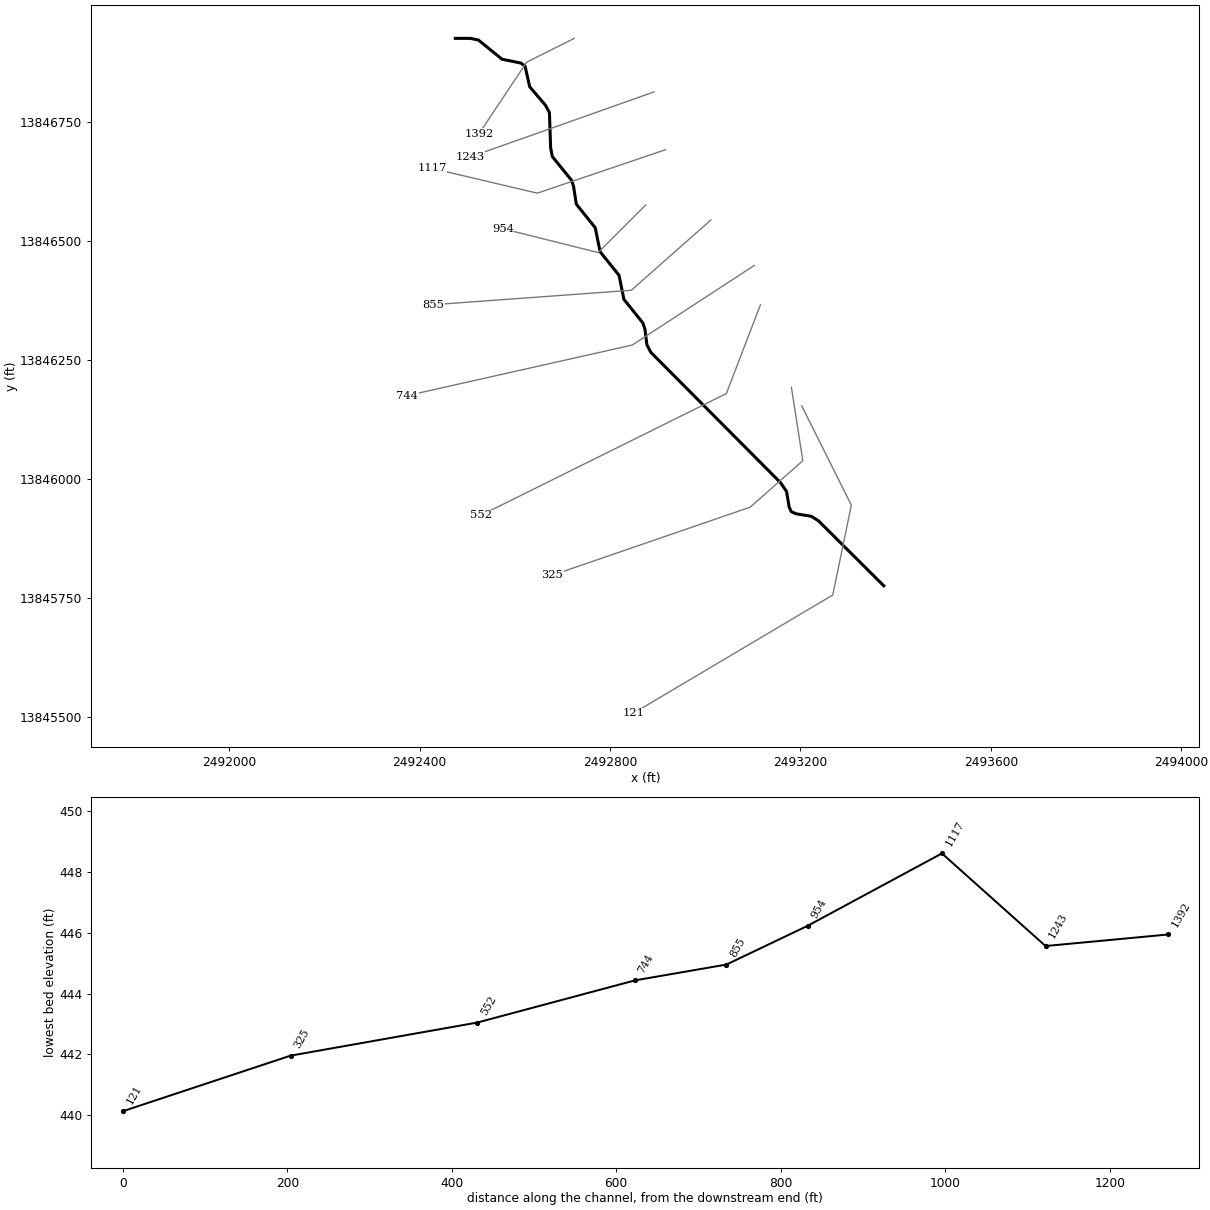
--- StreamM027.prj (project) ---

Proj Title=StreamM027 Base Level Engineering
Current Plan=p01
Default Exp/Contr=0.3,0.1
English Units
Geom File=g01
Flow File=f01
Plan File=p01
BEGIN DESCRIPTION:
StreamM027
END DESCRIPTION:

--- StreamM027.p01 (plan) ---

Plan Title=Multiple Run
Short Identifier=Multiple
Geom File=g01
Flow File=f01
Subcritical Flow
K Sum by GR= 0
Std Step Tol= 0.01
Critical Tol= 0.01
Num of Std Step Trials= 20
Max Error Tol= 0.3
Flow Tol Ratio= 0.001
Split Flow NTrial= 30
Split Flow Tol= 0.02
Split Flow Ratio= 0.02
Log Output Level= 0
Friction Slope Method= 1
Unsteady Friction Slope Method= 2
Unsteady Bridges Friction Slope Method= 1
Parabolic Critical Depth
Global Vel Dist=  1 , 1 , 1
Global Log Level= 0
CheckData=True
Encroach Param= -1, 0, 0, 0
BEGIN DESCRIPTION:
Multiple Run
END DESCRIPTION:

--- StreamM027.f01 (steady flow) ---

Flow Title=Multiple
Number of Profiles=7
Profile Names=10-year,25-year,50-year,1pct_min,100-year,1pct_plu,500-year
River Rch & RM= StreamM027,Reach-1,1392
     213     317     405     252     503    1003     762
Boundary for River Rch & Prof#=StreamM027,Reach-1,1
Up Type=0
Dn Type=3
Dn Slope=0.005
Boundary for River Rch & Prof#=StreamM027,Reach-1,2
Up Type=0
Dn Type=3
Dn Slope=0.005
Boundary for River Rch & Prof#=StreamM027,Reach-1,3
Up Type=0
Dn Type=3
Dn Slope=0.005
Boundary for River Rch & Prof#=StreamM027,Reach-1,4
Up Type=0
Dn Type=3
Dn Slope=0.005
Boundary for River Rch & Prof#=StreamM027,Reach-1,5
Up Type=0
Dn Type=3
Dn Slope=0.005
Boundary for River Rch & Prof#=StreamM027,Reach-1,6
Up Type=0
Dn Type=3
Dn Slope=0.005
Boundary for River Rch & Prof#=StreamM027,Reach-1,7
Up Type=0
Dn Type=3
Dn Slope=0.005

--- StreamM027.g01 (geometry) ---

Geom Title=Existing Conditions

River Reach=StreamM027,Reach-1
Reach XY= 30
      2492475.00     13846925.00      2492506.83     13846924.91
      2492523.55     13846921.42      2492573.13     13846881.13
      2492613.04     13846872.96      2492621.51     13846866.56
      2492631.27     13846823.16      2492664.19     13846784.71
      2492672.68     13846769.06      2492675.23     13846695.10
      2492678.83     13846676.59      2492718.88     13846627.18
      2492723.33     13846614.31      2492729.16     13846576.72
      2492768.92     13846527.20      2492779.16     13846476.72
      2492818.92     13846427.20      2492829.16     13846376.72
      2492868.90     13846327.19      2492873.30     13846314.30
      2492877.50     13846281.03      2492885.76     13846265.32
      2493158.27     13845991.48      2493170.87     13845972.99
      2493176.15     13845941.04      2493180.62     13845930.62
      2493191.04     13845926.15      2493222.99     13845920.88
      2493237.98     13845911.28      2493375.00     13845775.00

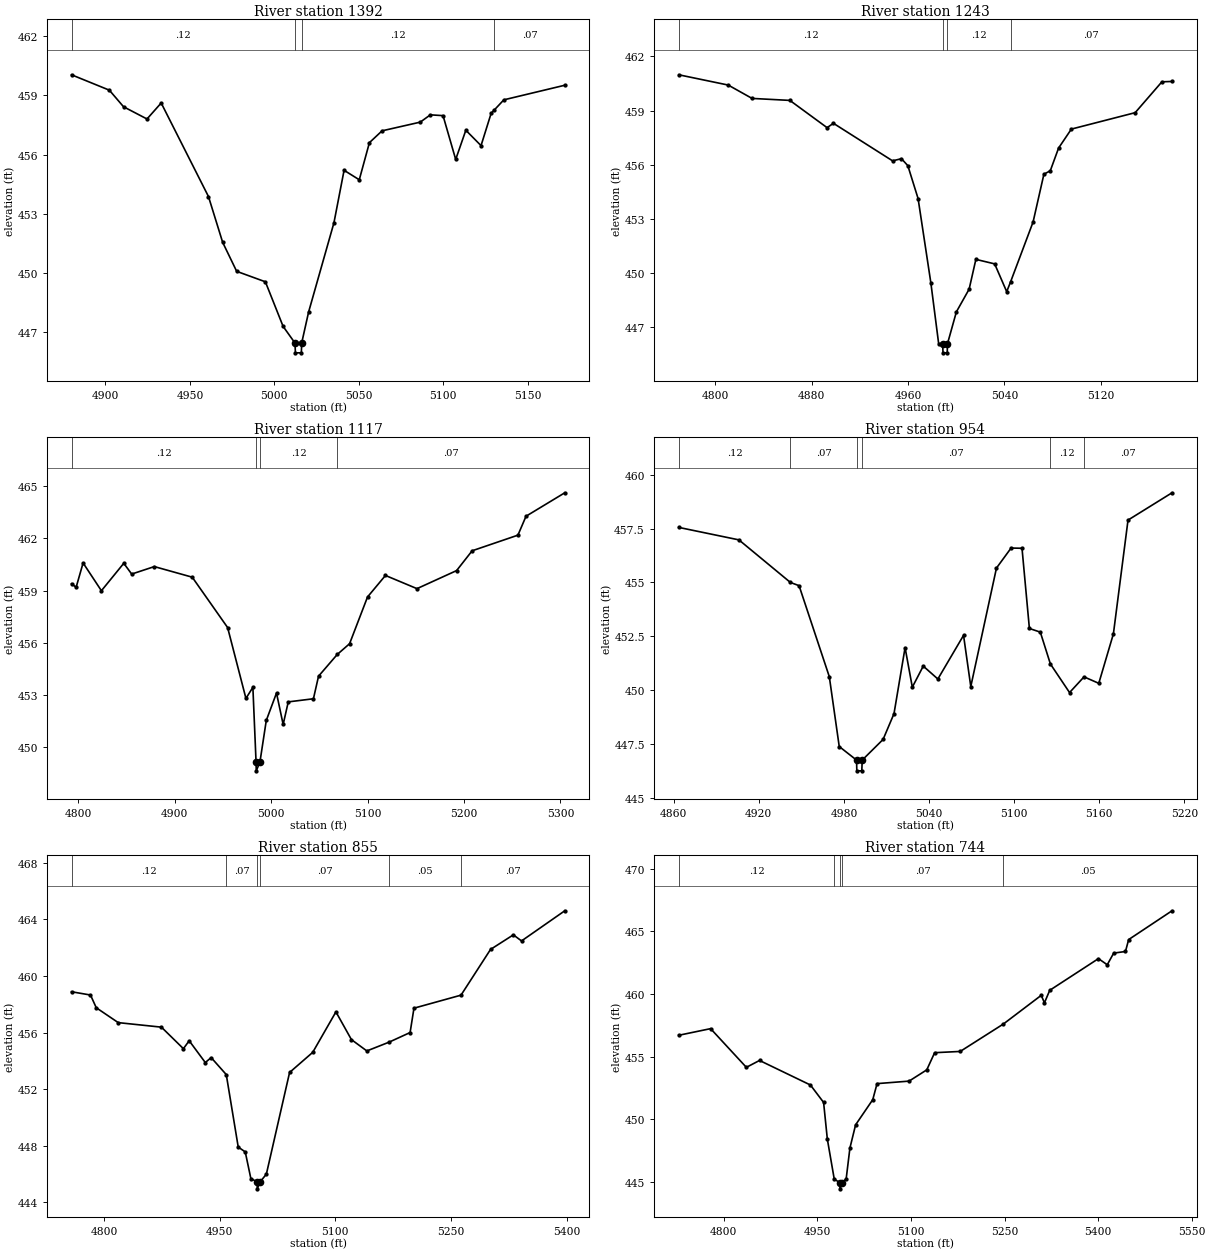
Type RM Length L Ch R = 1,1392,149,149,149
BEGIN DESCRIPTION:
StreamM027 2.0
END DESCRIPTION:
XS GIS Cut Line= 3
      2492725.01     13846925.00      2492625.00     13846875.00
      2492525.00     13846724.99
#Sta/Elev= 30
  4879.9  460.04  4902.3  459.26  4910.7  458.42  4924.6  457.80  4933.0  458.61
  4961.0  453.87  4969.4  451.55  4977.7  450.08  4994.7  449.55  5005.2  447.29
  5012.2  446.45  5012.5  445.95  5016.0  445.95  5016.2  446.45  5020.3  448.02
  5035.3  452.54  5041.3  455.20  5050.3  454.72  5056.3  456.60  5063.8  457.20
  5086.4  457.64  5092.4  458.01  5099.9  457.97  5107.4  455.75  5113.4  457.23
  5122.4  456.45  5128.4  458.09  5130.3  458.26  5135.9  458.77  5172.0  459.51
#Mann=4,-1,0
  4879.9    0.12       0  5012.2    0.05       0  5016.2    0.12       0
  5130.3    0.07       0
Bank Sta=5012.2,5016.2
Exp/Cntr=0.3,0.1

Type RM Length L Ch R = 1,1243,126,126,126
BEGIN DESCRIPTION:
H21231
END DESCRIPTION:
XS GIS Cut Line= 2
      2492892.40     13846812.43      2492506.18     13846675.74
#Sta/Elev= 30
  4769.5  460.98  4810.6  460.41  4830.4  459.67  4861.8  459.56  4892.7  458.05
  4898.0  458.29  4947.1  456.21  4954.5  456.33  4959.8  455.94  4968.3  454.12
  4978.9  449.45  4985.4  446.07  4988.7  446.07  4989.0  445.57  4992.5  445.57
  4992.7  446.07  5000.1  447.84  5010.7  449.10  5016.3  450.75  5031.9  450.50
  5041.9  448.96  5045.1  449.50  5063.8  452.82  5072.8  455.47  5078.1  455.66
  5085.0  456.92  5095.6  457.97  5148.6  458.88  5170.8  460.59  5179.2  460.61
#Mann=4,-1,0
  4769.5    0.12       0  4988.7    0.05       0  4992.7    0.12       0
  5045.1    0.07       0
Bank Sta=4988.7,4992.7
Exp/Cntr=0.3,0.1

Type RM Length L Ch R = 1,1117,163,163,163
BEGIN DESCRIPTION:
H21230
END DESCRIPTION:
XS GIS Cut Line= 3
      2492916.36     13846690.94      2492647.22     13846599.78
      2492425.82     13846651.87
#Sta/Elev= 30
  4792.9  459.39  4797.7  459.19  4804.9  460.59  4823.9  458.99  4847.1  460.57
  4855.3  459.95  4878.8  460.38  4918.1  459.77  4954.8  456.87  4973.8  452.79
  4981.0  453.43  4984.3  449.12  4984.5  448.62  4988.3  449.12  4994.9  451.52
  5005.5  453.10  5012.4  451.29  5017.7  452.59  5043.8  452.77  5049.1  454.07
  5068.5  455.32  5081.3  455.94  5099.9  458.63  5118.5  459.87  5151.2  459.11
  5192.3  460.15  5208.4  461.29  5255.9  462.19  5264.3  463.28  5304.5  464.63
#Mann=4,-1,0
  4792.9    0.12       0  4984.3    0.05       0  4988.3    0.12       0
  5068.5    0.07       0
Bank Sta=4984.3,4988.3
Exp/Cntr=0.3,0.1

Type RM Length L Ch R = 1,954,99,99,99
BEGIN DESCRIPTION:
StreamM027 1.0
END DESCRIPTION:
XS GIS Cut Line= 3
      2492875.00     13846575.00      2492775.00     13846475.00
      2492574.97     13846525.01
#Sta/Elev= 30
  4863.6  457.56  4906.0  456.98  4942.3  455.00  4948.4  454.85  4969.7  450.62
  4976.7  447.37  4988.9  446.74  4989.1  446.24  4992.6  446.24  4992.9  446.74
  5007.6  447.70  5015.3  448.90  5023.1  451.97  5028.2  450.13  5035.9  451.11
  5046.2  450.51  5064.3  452.54  5069.4  450.16  5087.5  455.67  5097.8  456.60
  5105.5  456.59  5110.7  452.86  5118.4  452.69  5125.5  451.21  5139.0  449.88
  5149.2  450.61  5159.6  450.31  5169.9  452.61  5180.2  457.90  5211.2  459.17
#Mann=6,-1,0
  4863.6    0.12       0  4942.3    0.07       0  4988.9    0.05       0
  4992.9    0.07       0  5125.5    0.12       0  5149.2    0.07       0
Bank Sta=4988.9,4992.9
Exp/Cntr=0.3,0.1

Type RM Length L Ch R = 1,855,111,111,111
BEGIN DESCRIPTION:
H21229
END DESCRIPTION:
XS GIS Cut Line= 3
      2493011.78     13846543.33      2492844.70     13846395.78
      2492429.00     13846365.47
#Sta/Elev= 30
  4757.9  458.88  4782.5  458.65  4790.0  457.75  4818.5  456.70  4874.5  456.38
  4903.0  454.86  4910.5  455.42  4931.4  453.88  4939.0  454.23  4958.6  453.03
  4974.1  447.91  4983.2  447.57  4990.5  445.68  4998.6  445.46  4998.8  444.96
  5002.6  445.46  5010.6  446.00  5040.7  453.18  5070.7  454.60  5100.8  457.46
  5120.9  455.50  5140.9  454.70  5169.7  455.32  5197.0  456.00  5202.0  457.72
  5263.0  458.64  5301.3  461.87  5330.9  462.90  5341.5  462.47  5397.6  464.60
#Mann=6,-1,0
  4757.9    0.12       0  4958.6    0.07       0  4998.6    0.05       0
  5002.6    0.07       0  5169.7    0.05       0  5263.0    0.07       0
Bank Sta=4998.6,5002.6
Exp/Cntr=0.3,0.1

Type RM Length L Ch R = 1,744,192,192,192
BEGIN DESCRIPTION:
H21228
END DESCRIPTION:
XS GIS Cut Line= 3
      2493102.94     13846447.86      2492846.88     13846280.77
      2492373.75     13846174.42
#Sta/Elev= 30
  4727.8  456.70  4778.9  457.23  4836.2  454.14  4857.3  454.69  4938.9  452.73
  4960.0  451.34  4966.0  448.41  4977.1  445.21  4986.0  444.94  4986.3  444.44
  4990.0  444.94  4996.2  445.24  5002.2  447.70  5011.3  449.55  5038.8  451.56
  5045.7  452.84  5097.0  453.04  5125.4  453.94  5138.0  455.31  5179.0  455.41
  5248.2  457.60  5308.9  459.89  5314.0  459.29  5322.5  460.29  5400.6  462.82
  5414.7  462.33  5425.0  463.26  5443.9  463.39  5449.0  464.34  5518.5  466.64
#Mann=5,-1,0
  4727.8    0.12       0  4977.1    0.07       0  4986.0    0.05       0
  4990.0    0.07       0  5248.2    0.05       0
Bank Sta=4986,4990
Exp/Cntr=0.3,0.1

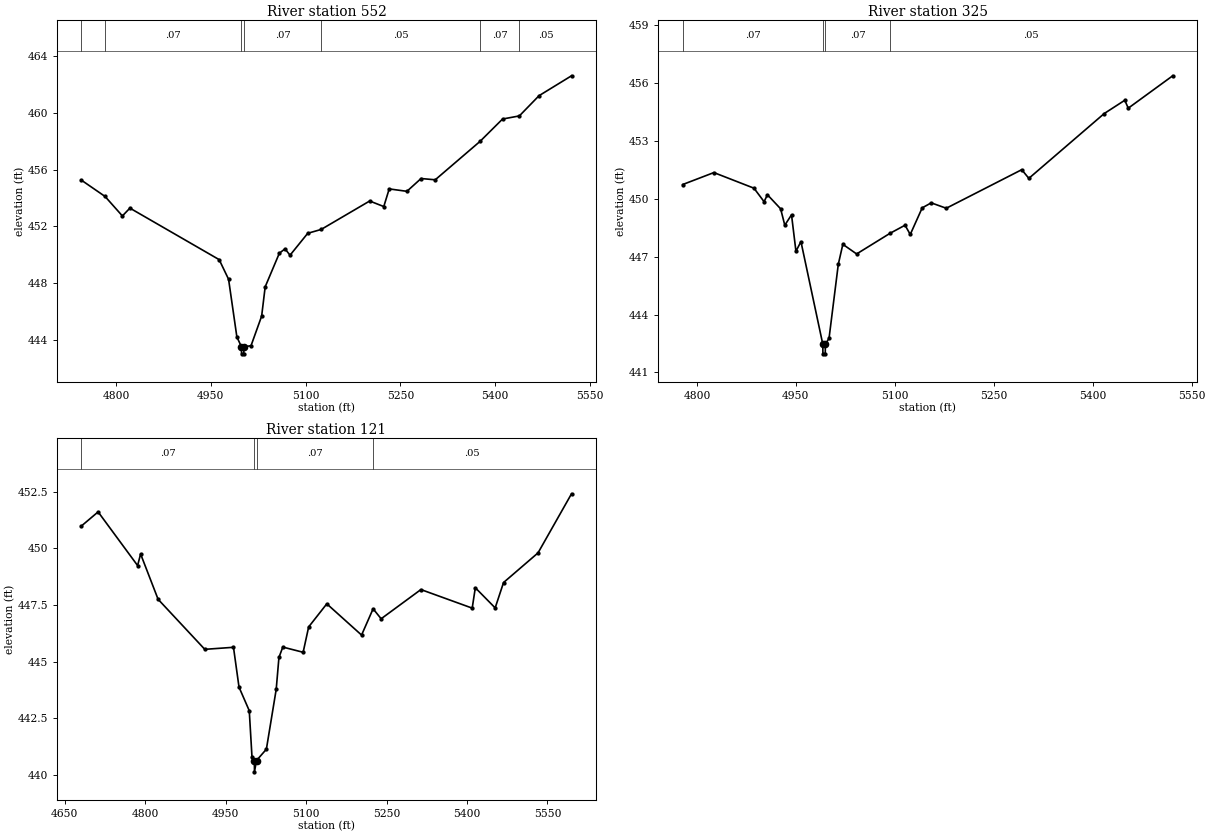
Type RM Length L Ch R = 1,552,227,227,227
BEGIN DESCRIPTION:
H21227
END DESCRIPTION:
XS GIS Cut Line= 3
      2493115.97     13846365.41      2493044.36     13846178.77
      2492528.94     13845923.22
#Sta/Elev= 30
  4745.5  455.25  4782.8  454.11  4810.2  452.74  4822.1  453.29  4963.3  449.67
  4978.2  448.29  4991.3  444.24  4998.5  443.55  4998.7  443.05  5002.2  443.05
  5002.5  443.55  5013.7  443.62  5030.5  445.70  5036.1  447.76  5058.5  450.12
  5067.5  450.43  5075.4  449.98  5103.4  451.52  5124.6  451.79  5201.4  453.79
  5223.7  453.40  5232.3  454.64  5260.3  454.47  5282.7  455.37  5305.1  455.28
  5376.0  457.98  5411.6  459.55  5438.2  459.77  5469.3  461.19  5520.7  462.59
#Mann=7,-1,0
  4745.5    0.12       0  4782.8    0.07       0  4998.5    0.05       0
  5002.5    0.07       0  5124.6    0.05       0  5376.0    0.07       0
  5438.2    0.05       0
Bank Sta=4998.5,5002.5
Exp/Cntr=0.3,0.1

Type RM Length L Ch R = 1,325,204,204,204
BEGIN DESCRIPTION:
H21226
END DESCRIPTION:
XS GIS Cut Line= 4
      2493181.08     13846191.79      2493204.95     13846037.71
      2493094.27     13845940.05      2492678.76     13845797.22
#Sta/Elev= 30
  4778.4  450.74  4825.7  451.36  4886.5  450.55  4901.8  449.85  4906.9  450.21
  4926.9  449.48  4933.2  448.63  4943.4  449.17  4950.1  447.28  4957.7  447.78
  4990.8  442.46  4991.0  441.96  4994.5  441.96  4994.8  442.46  5000.3  442.77
  5014.3  446.60  5021.2  447.64  5042.1  447.14  5092.7  448.21  5115.5  448.63
  5123.4  448.15  5141.5  449.53  5155.2  449.79  5178.0  449.51  5292.4  451.51
  5303.2  451.06  5417.4  454.42  5448.6  455.11  5453.9  454.70  5521.3  456.38
#Mann=4,-1,0
  4778.4    0.07       0  4990.8    0.05       0  4994.8    0.07       0
  5092.7    0.05       0
Bank Sta=4990.8,4994.8
Exp/Cntr=0.3,0.1

Type RM Length L Ch R = 1,121,0,0,0
BEGIN DESCRIPTION:
H21225
END DESCRIPTION:
XS GIS Cut Line= 4
      2493202.79     13846152.71      2493306.94     13845944.39
      2493267.88     13845755.59      2492848.44     13845506.95
#Sta/Elev= 30
  4681.5  450.99  4712.5  451.61  4786.1  449.24  4791.7  449.75  4824.3  447.75
  4911.3  445.54  4964.8  445.63  4975.1  443.87  4994.2  442.83  4999.3  440.78
  5003.7  440.63  5003.9  440.13  5007.7  440.63  5026.1  441.13  5044.4  443.77
  5049.5  445.18  5056.7  445.64  5094.6  445.41  5104.9  446.53  5138.7  447.55
  5203.5  446.17  5225.0  447.33  5240.0  446.89  5314.1  448.18  5409.7  447.36
  5415.5  448.26  5452.5  447.37  5468.1  448.49  5532.4  449.80  5594.8  452.41
#Mann=4,-1,0
  4681.5    0.07       0  5003.7    0.05       0  5007.7    0.07       0
  5225.0    0.05       0
Bank Sta=5003.7,5007.7
Exp/Cntr=0.3,0.1

Chan Stop Cuts=-1