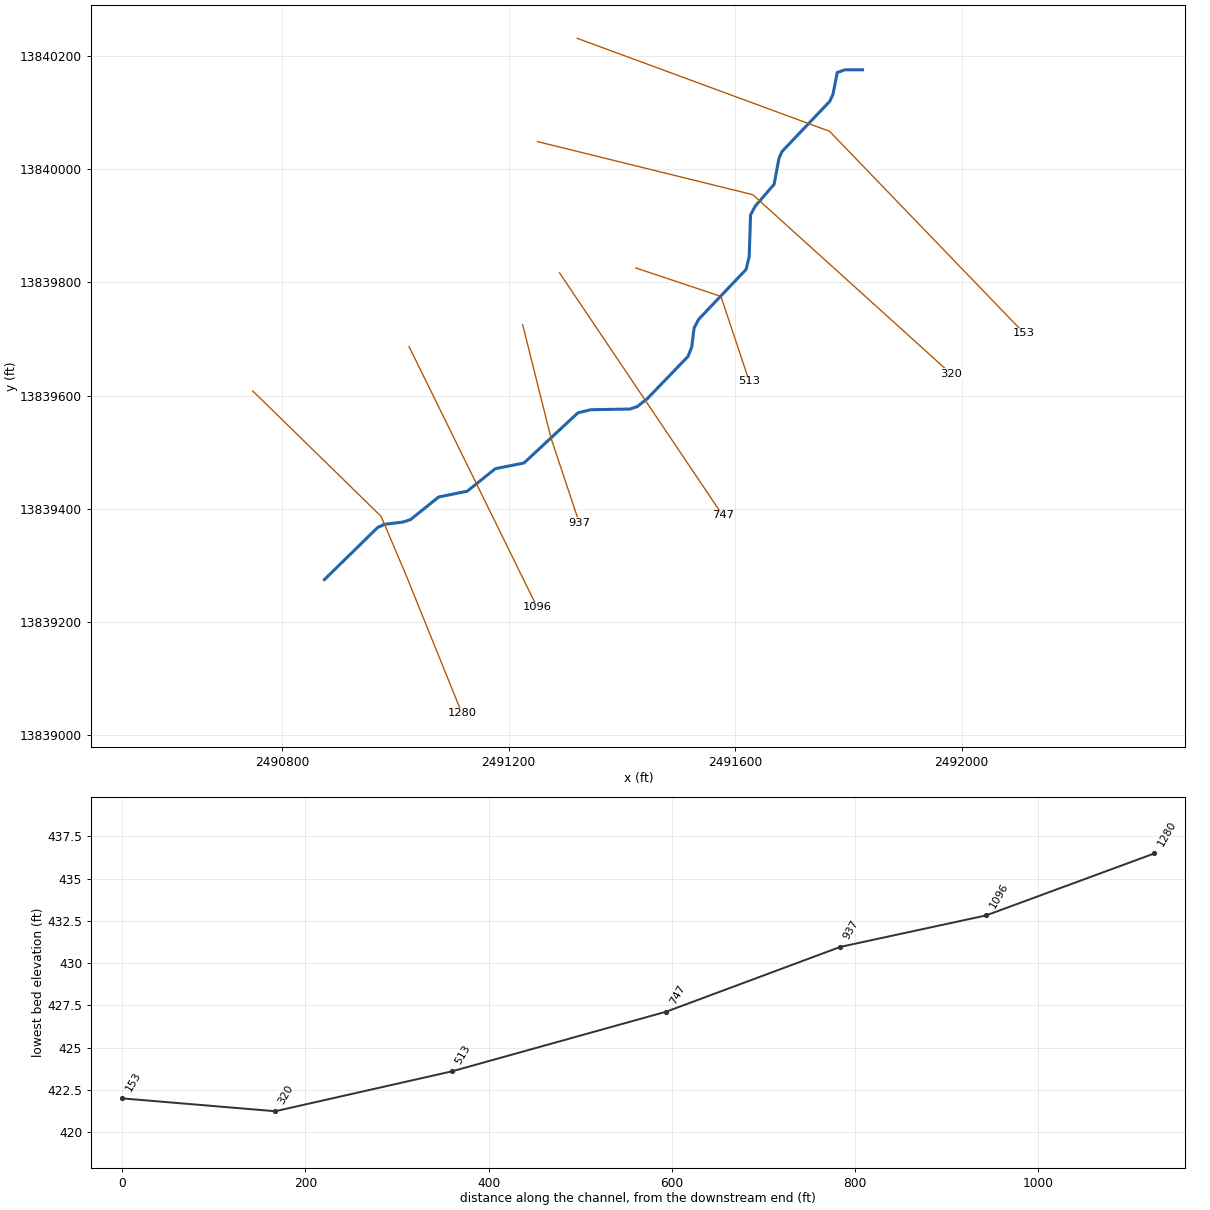
--- StreamM028.prj (project) ---

Proj Title=StreamM028 Base Level Engineering
Current Plan=p01
Default Exp/Contr=0.3,0.1
English Units
Geom File=g01
Flow File=f01
Plan File=p01
BEGIN DESCRIPTION:
StreamM028
END DESCRIPTION:

--- StreamM028.p01 (plan) ---

Plan Title=Multiple Run
Short Identifier=Multiple
Geom File=g01
Flow File=f01
Subcritical Flow
K Sum by GR= 0
Std Step Tol= 0.01
Critical Tol= 0.01
Num of Std Step Trials= 20
Max Error Tol= 0.3
Flow Tol Ratio= 0.001
Split Flow NTrial= 30
Split Flow Tol= 0.02
Split Flow Ratio= 0.02
Log Output Level= 0
Friction Slope Method= 1
Unsteady Friction Slope Method= 2
Unsteady Bridges Friction Slope Method= 1
Parabolic Critical Depth
Global Vel Dist=  1 , 1 , 1
Global Log Level= 0
CheckData=True
Encroach Param= -1, 0, 0, 0
BEGIN DESCRIPTION:
Multiple Run
END DESCRIPTION:

--- StreamM028.f01 (steady flow) ---

Flow Title=Multiple
Number of Profiles=7
Profile Names=10-year,25-year,50-year,1pct_min,100-year,1pct_plu,500-year
River Rch & RM= StreamM028,Reach-1,1280
     278     425     553     351     700    1397    1103
Boundary for River Rch & Prof#=StreamM028,Reach-1,1
Up Type=0
Dn Type=3
Dn Slope=0.005
Boundary for River Rch & Prof#=StreamM028,Reach-1,2
Up Type=0
Dn Type=3
Dn Slope=0.005
Boundary for River Rch & Prof#=StreamM028,Reach-1,3
Up Type=0
Dn Type=3
Dn Slope=0.005
Boundary for River Rch & Prof#=StreamM028,Reach-1,4
Up Type=0
Dn Type=3
Dn Slope=0.005
Boundary for River Rch & Prof#=StreamM028,Reach-1,5
Up Type=0
Dn Type=3
Dn Slope=0.005
Boundary for River Rch & Prof#=StreamM028,Reach-1,6
Up Type=0
Dn Type=3
Dn Slope=0.005
Boundary for River Rch & Prof#=StreamM028,Reach-1,7
Up Type=0
Dn Type=3
Dn Slope=0.005

--- StreamM028.g01 (geometry) ---

Geom Title=Existing Conditions

River Reach=StreamM028,Reach-1
Reach XY= 30
      2490875.00     13839275.00      2490968.92     13839366.91
      2490981.03     13839372.52      2491014.30     13839376.68
      2491027.19     13839381.10      2491076.72     13839420.84
      2491127.20     13839431.08      2491176.74     13839470.81
      2491227.29     13839480.85      2491322.58     13839569.46
      2491345.06     13839574.86      2491414.52     13839576.16
      2491427.44     13839580.52      2491445.20     13839594.61
      2491516.85     13839668.93      2491523.46     13839685.63
      2491527.54     13839718.94      2491535.80     13839734.67
      2491619.46     13839822.58      2491624.87     13839845.05
      2491627.33     13839919.03      2491635.84     13839934.65
      2491668.86     13839972.83      2491677.50     13840018.96
      2491683.15     13840031.05      2491766.92     13840119.11
      2491772.69     13840131.21      2491780.32     13840170.08
      2491793.46     13840174.93      2491825.00     13840175.00

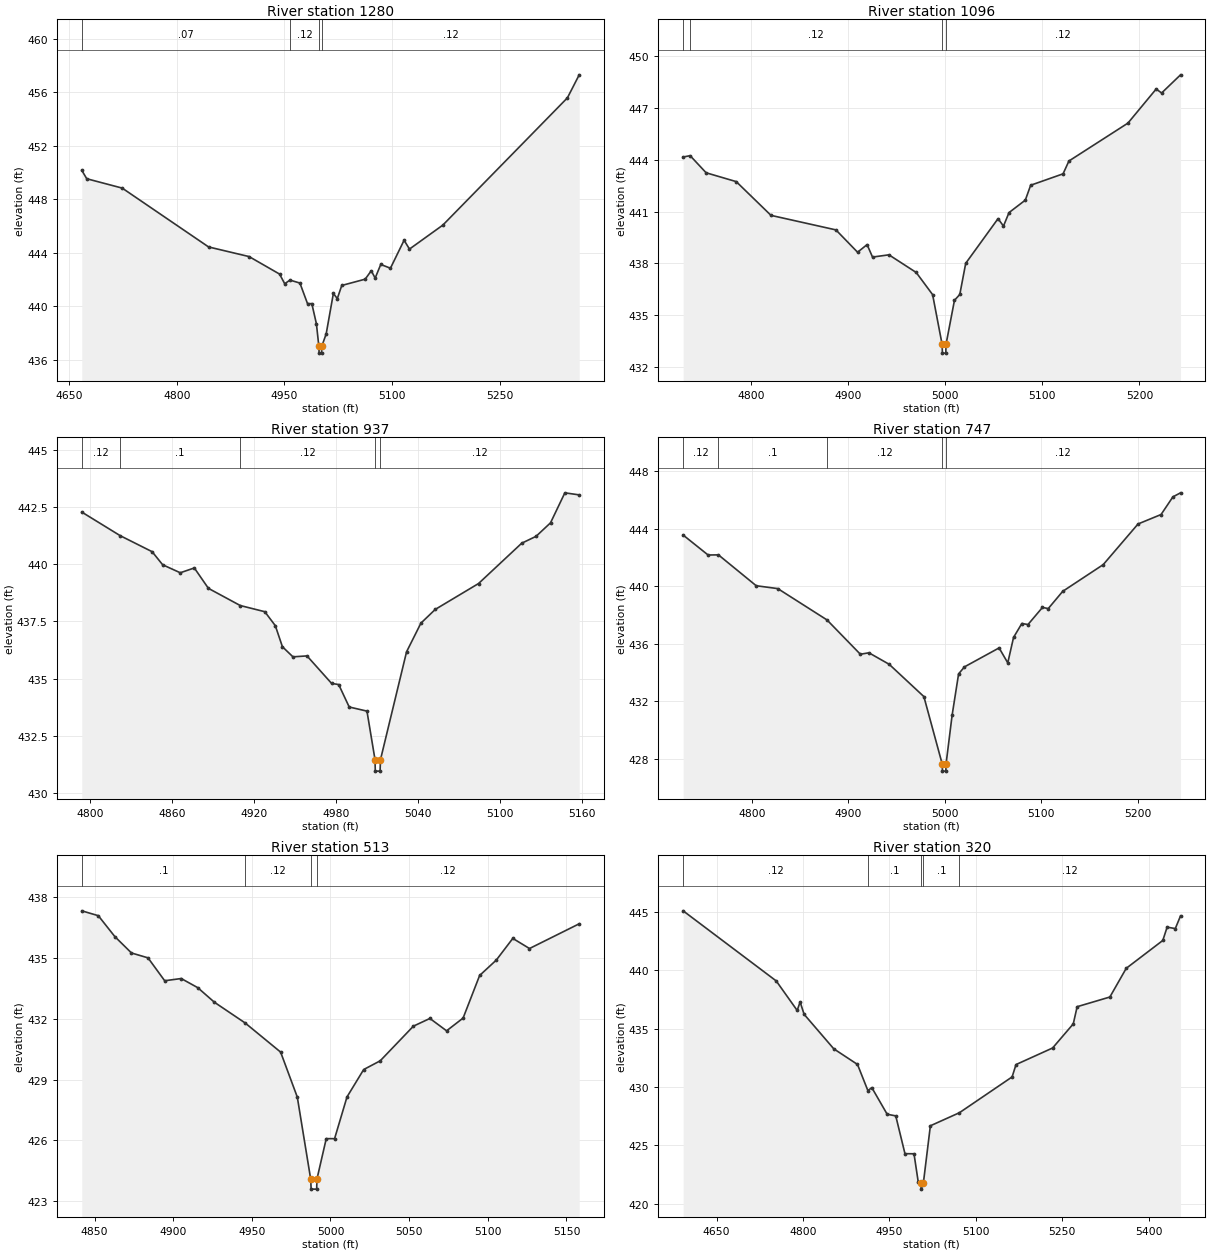
Type RM Length L Ch R = 1,1280,184,184,184
BEGIN DESCRIPTION:
H21236
END DESCRIPTION:
XS GIS Cut Line= 4
      2490748.46     13839608.10      2490975.00     13839386.77
      2491019.27     13839282.60      2491117.80     13839038.87
#Sta/Elev= 30
  4667.8  450.16  4674.7  449.53  4724.1  448.83  4844.4  444.43  4900.8  443.71
  4943.3  442.40  4950.4  441.68  4957.8  441.95  4971.6  441.73  4982.2  440.19
  4988.2  440.19  4994.6  438.68  4998.0  436.99  4998.3  436.49  5001.8  436.49
  5002.0  436.99  5008.2  437.93  5018.2  440.95  5023.7  440.57  5029.9  441.55
  5062.5  442.02  5071.0  442.65  5076.4  442.10  5084.2  443.12  5097.7  442.84
  5116.7  444.93  5124.2  444.27  5170.6  446.06  5344.2  455.58  5360.6  457.30
#Mann=4,-1,0
  4667.8    0.07       0  4957.8    0.12       0  4998.0    0.05       0
  5002.0    0.12       0
Bank Sta=4998,5002
Exp/Cntr=0.3,0.1

Type RM Length L Ch R = 1,1096,159,159,159
BEGIN DESCRIPTION:
H21235
END DESCRIPTION:
XS GIS Cut Line= 2
      2491024.48     13839686.24      2491250.51     13839226.38
#Sta/Elev= 30
  4730.0  444.15  4737.2  444.23  4753.7  443.24  4784.7  442.73  4820.5  440.78
  4887.4  439.94  4909.7  438.65  4919.5  439.09  4925.1  438.37  4942.0  438.50
  4970.1  437.48  4987.0  436.20  4996.8  433.32  4997.1  432.82  5000.6  432.82
  5000.8  433.32  5009.5  435.87  5015.0  436.21  5021.1  438.01  5054.4  440.59
  5060.0  440.16  5065.7  440.94  5082.5  441.66  5088.0  442.52  5121.4  443.18
  5127.4  443.92  5188.2  446.11  5217.3  448.08  5222.9  447.85  5242.4  448.90
#Mann=4,-1,0
  4730.0    0.07       0  4737.2    0.12       0  4996.8    0.05       0
  5000.8    0.12       0
Bank Sta=4996.8,5000.8
Exp/Cntr=0.3,0.1

Type RM Length L Ch R = 1,937,190,190,190
BEGIN DESCRIPTION:
StreamM028 2.0
END DESCRIPTION:
XS GIS Cut Line= 3
      2491225.01     13839724.98      2491275.00     13839525.00
      2491324.99     13839375.04
#Sta/Elev= 30
  4793.9  442.27  4822.0  441.24  4845.4  440.54  4853.1  439.97  4866.0  439.62
  4876.3  439.83  4886.6  438.94  4909.9  438.19  4927.9  437.92  4935.6  437.31
  4940.8  436.39  4948.5  435.95  4958.8  435.99  4976.8  434.79  4982.0  434.74
  4989.7  433.76  5002.7  433.58  5008.6  431.46  5008.8  430.96  5012.3  430.96
  5012.6  431.46  5031.7  436.17  5042.2  437.42  5052.7  438.02  5084.4  439.15
  5116.0  440.91  5126.5  441.21  5137.1  441.80  5147.6  443.11  5158.1  443.02
#Mann=5,-1,0
  4793.9    0.12       0  4822.0     0.1       0  4909.9    0.12       0
  5008.6    0.05       0  5012.6    0.12       0
Bank Sta=5008.6,5012.6
Exp/Cntr=0.3,0.1

Type RM Length L Ch R = 1,747,234,234,234
BEGIN DESCRIPTION:
H21234
END DESCRIPTION:
XS GIS Cut Line= 2
      2491290.10     13839816.46      2491578.07     13839388.40
#Sta/Elev= 30
  4728.6  443.57  4754.5  442.18  4765.2  442.19  4804.4  440.04  4826.8  439.84
  4877.8  437.66  4912.4  435.27  4921.3  435.37  4942.3  434.57  4978.3  432.32
  4997.3  427.63  4997.6  427.13  5001.1  427.13  5001.3  427.63  5007.6  431.03
  5014.3  433.90  5020.4  434.39  5056.3  435.71  5065.3  434.67  5071.3  436.44
  5079.9  437.41  5086.3  437.34  5101.3  438.53  5107.3  438.45  5122.3  439.65
  5164.3  441.51  5200.4  444.34  5224.3  445.00  5236.6  446.23  5244.5  446.51
#Mann=5,-1,0
  4728.6    0.12       0  4765.2     0.1       0  4877.8    0.12       0
  4997.3    0.05       0  5001.3    0.12       0
Bank Sta=4997.3,5001.3
Exp/Cntr=0.3,0.1

Type RM Length L Ch R = 1,513,193,193,193
BEGIN DESCRIPTION:
StreamM028 1.0
END DESCRIPTION:
XS GIS Cut Line= 3
      2491425.04     13839824.99      2491575.00     13839775.00
      2491625.00     13839624.99
#Sta/Elev= 30
  4841.9  437.33  4852.4  437.09  4862.9  436.06  4873.5  435.25  4884.0  435.01
  4894.6  433.88  4905.1  433.99  4915.6  433.54  4926.2  432.82  4945.7  431.80
  4968.3  430.36  4978.9  428.14  4987.4  424.10  4987.7  423.60  4991.2  423.60
  4991.4  424.10  4997.3  426.09  5002.6  426.09  5010.5  428.15  5021.1  429.50
  5031.6  429.93  5052.7  431.64  5063.2  432.02  5073.8  431.41  5084.3  432.04
  5094.8  434.14  5105.4  434.90  5115.9  435.97  5126.5  435.47  5158.1  436.69
#Mann=4,-1,0
  4841.9     0.1       0  4945.7    0.12       0  4987.4    0.05       0
  4991.4    0.12       0
Bank Sta=4987.4,4991.4
Exp/Cntr=0.3,0.1

Type RM Length L Ch R = 1,320,167,167,167
BEGIN DESCRIPTION:
H21233
END DESCRIPTION:
XS GIS Cut Line= 3
      2491251.09     13840048.22      2491631.25     13839954.48
      2491981.40     13839638.04
#Sta/Elev= 30
  4591.9  445.10  4753.5  439.09  4789.9  436.56  4795.0  437.29  4801.9  436.23
  4853.4  433.27  4894.6  431.93  4912.6  429.69  4919.5  429.94  4946.1  427.66
  4961.0  427.52  4977.0  424.28  4992.7  424.27  5000.1  421.83  5004.9  421.74
  5005.1  421.24  5008.9  421.74  5021.1  426.67  5071.5  427.79  5163.0  430.86
  5169.8  431.92  5233.3  433.34  5269.2  435.41  5275.9  436.88  5332.7  437.71
  5361.1  440.17  5424.6  442.56  5432.1  443.70  5446.3  443.58  5455.4  444.67
#Mann=5,-1,0
  4591.9    0.12       0  4912.6     0.1       0  5004.9    0.05       0
  5008.9     0.1       0  5071.5    0.12       0
Bank Sta=5004.9,5008.9
Exp/Cntr=0.3,0.1

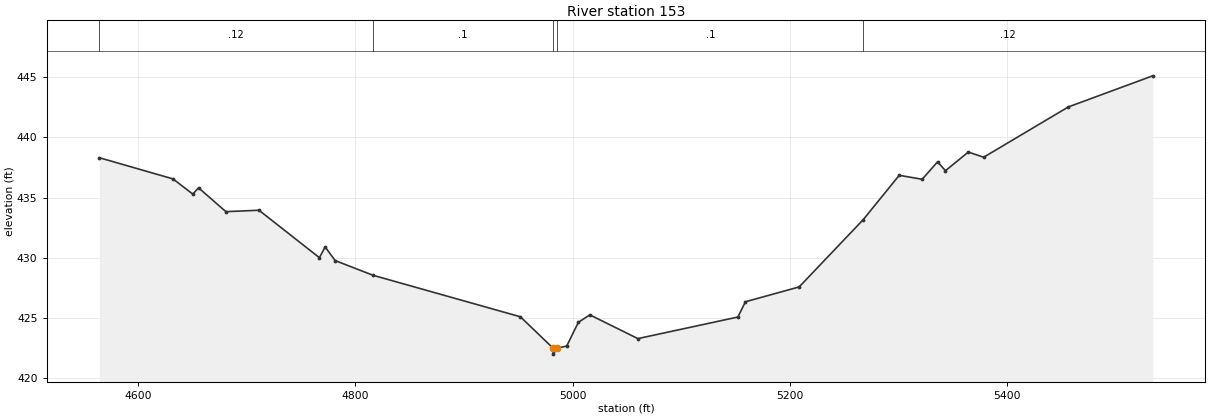
Type RM Length L Ch R = 1,153,0,0,0
BEGIN DESCRIPTION:
H21232
END DESCRIPTION:
XS GIS Cut Line= 3
      2491321.39     13840230.51      2491766.67     13840066.46
      2492110.02     13839710.09
#Sta/Elev= 30
  4564.5  438.31  4632.3  436.55  4650.5  435.29  4655.8  435.81  4681.0  433.83
  4711.4  433.95  4767.0  430.01  4772.3  430.90  4781.5  429.77  4816.3  428.55
  4952.0  425.10  4982.0  422.50  4982.2  422.00  4986.0  422.50  4994.6  422.67
  5005.3  424.64  5015.9  425.26  5060.1  423.29  5152.1  425.08  5159.1  426.35
  5208.5  427.58  5267.5  433.17  5300.6  436.85  5321.7  436.52  5335.9  437.97
  5343.1  437.23  5364.2  438.78  5378.3  438.35  5456.3  442.53  5533.9  445.11
#Mann=5,-1,0
  4564.5    0.12       0  4816.3     0.1       0  4982.0    0.05       0
  4986.0     0.1       0  5267.5    0.12       0
Bank Sta=4982,4986
Exp/Cntr=0.3,0.1

Chan Stop Cuts=-1