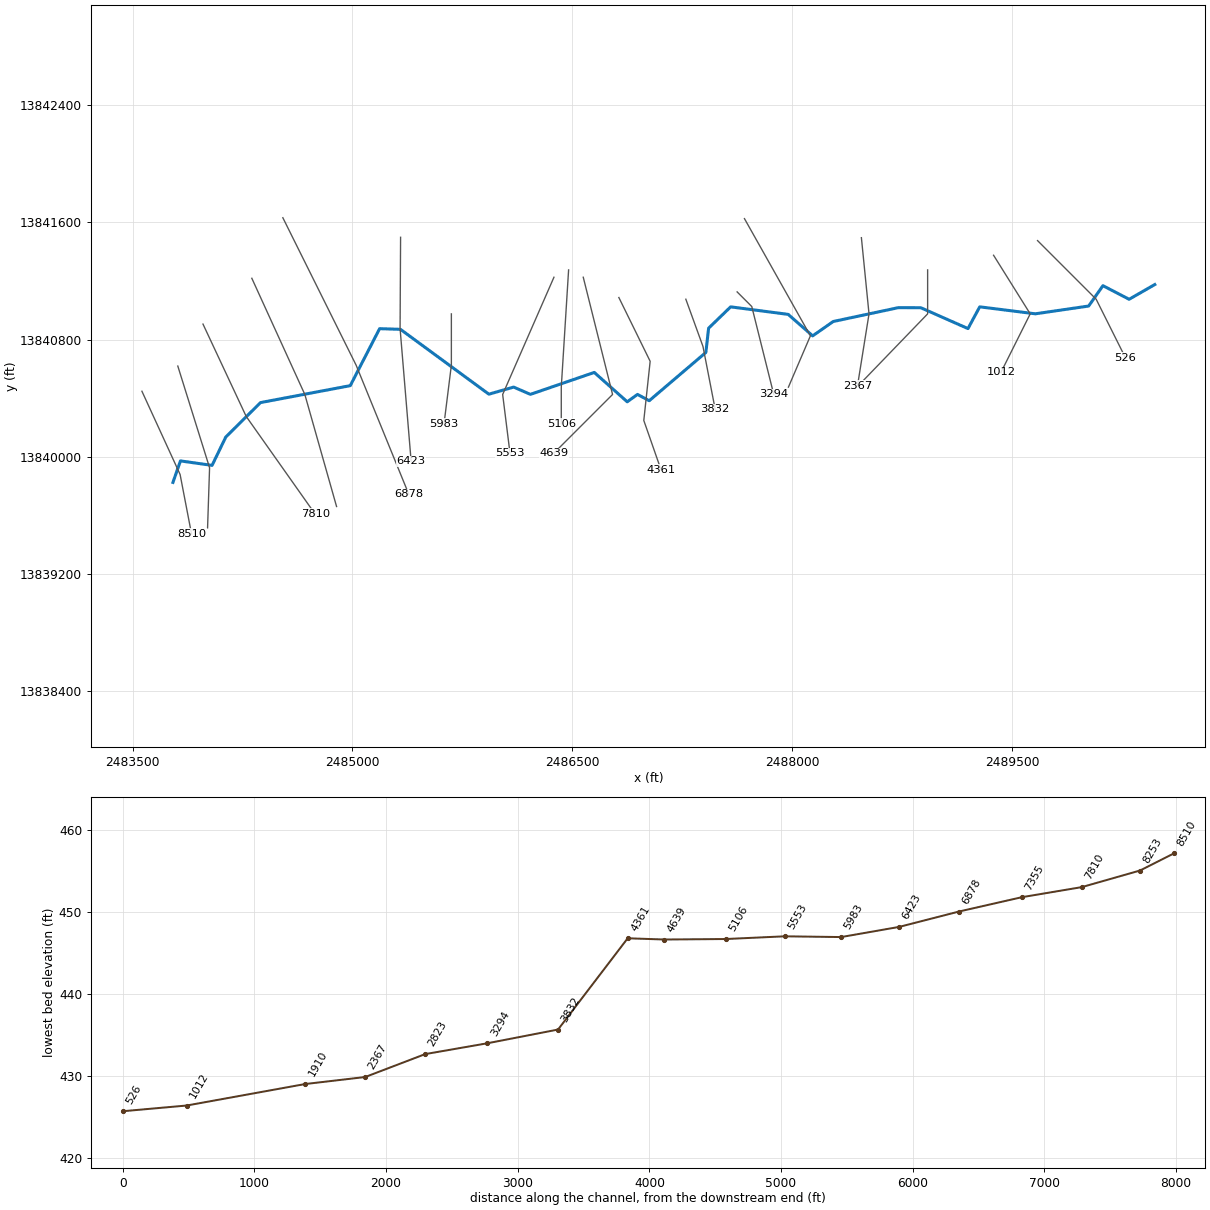
--- StreamM029.prj (project) ---

Proj Title=StreamM029 Base Level Engineering
Current Plan=p01
Default Exp/Contr=0.3,0.1
English Units
Geom File=g01
Flow File=f01
Plan File=p01
BEGIN DESCRIPTION:
StreamM029
END DESCRIPTION:

--- StreamM029.p01 (plan) ---

Plan Title=Multiple Run
Short Identifier=Multiple
Geom File=g01
Flow File=f01
Subcritical Flow
K Sum by GR= 0
Std Step Tol= 0.01
Critical Tol= 0.01
Num of Std Step Trials= 20
Max Error Tol= 0.3
Flow Tol Ratio= 0.001
Split Flow NTrial= 30
Split Flow Tol= 0.02
Split Flow Ratio= 0.02
Log Output Level= 0
Friction Slope Method= 1
Unsteady Friction Slope Method= 2
Unsteady Bridges Friction Slope Method= 1
Parabolic Critical Depth
Global Vel Dist=  1 , 1 , 1
Global Log Level= 0
CheckData=True
Encroach Param= -1, 0, 0, 0
BEGIN DESCRIPTION:
Multiple Run
END DESCRIPTION:

--- StreamM029.f01 (steady flow) ---

Flow Title=Multiple
Number of Profiles=7
Profile Names=10-year,25-year,50-year,1pct_min,100-year,1pct_plu,500-year
River Rch & RM= StreamM029,Reach-1,8510
     599     955    1273     823    1642    3276    2701
River Rch & RM= StreamM029,Reach-1,7810
     717    1152    1543    1001    1996    3983    3308
River Rch & RM= StreamM029,Reach-1,4361
     973    1589    2153    1410    2814    5615    4761
River Rch & RM= StreamM029,Reach-1,1012
    1289    2136    2920    1929    3850    7681    6626
Boundary for River Rch & Prof#=StreamM029,Reach-1,1
Up Type=0
Dn Type=3
Dn Slope=0.005
Boundary for River Rch & Prof#=StreamM029,Reach-1,2
Up Type=0
Dn Type=3
Dn Slope=0.005
Boundary for River Rch & Prof#=StreamM029,Reach-1,3
Up Type=0
Dn Type=3
Dn Slope=0.005
Boundary for River Rch & Prof#=StreamM029,Reach-1,4
Up Type=0
Dn Type=3
Dn Slope=0.005
Boundary for River Rch & Prof#=StreamM029,Reach-1,5
Up Type=0
Dn Type=3
Dn Slope=0.005
Boundary for River Rch & Prof#=StreamM029,Reach-1,6
Up Type=0
Dn Type=3
Dn Slope=0.005
Boundary for River Rch & Prof#=StreamM029,Reach-1,7
Up Type=0
Dn Type=3
Dn Slope=0.005

--- StreamM029.g01 (geometry) ---

Geom Title=Existing Conditions

River Reach=StreamM029,Reach-1
Reach XY= 30
      2483775.00     13839825.00      2483826.26     13839971.66
      2484042.06     13839941.06      2484135.70     13840134.71
      2484372.55     13840369.54      2484985.17     13840485.32
      2485185.29     13840874.03      2485327.44     13840869.53
      2485930.89     13840426.97      2486100.00     13840475.39
      2486214.31     13840425.77      2486650.20     13840575.36
      2486875.00     13840375.00      2486945.25     13840425.46
      2487025.09     13840382.32      2487411.64     13840711.66
      2487430.47     13840877.45      2487580.85     13841022.94
      2487973.53     13840971.46      2488140.36     13840824.89
      2488280.86     13840922.93      2488725.01     13841017.41
      2488878.31     13841016.94      2489200.35     13840874.62
      2489280.46     13841022.94      2489659.73     13840975.38
      2490023.75     13841028.45      2490121.34     13841167.33
      2490300.00     13841074.57      2490475.00     13841175.00

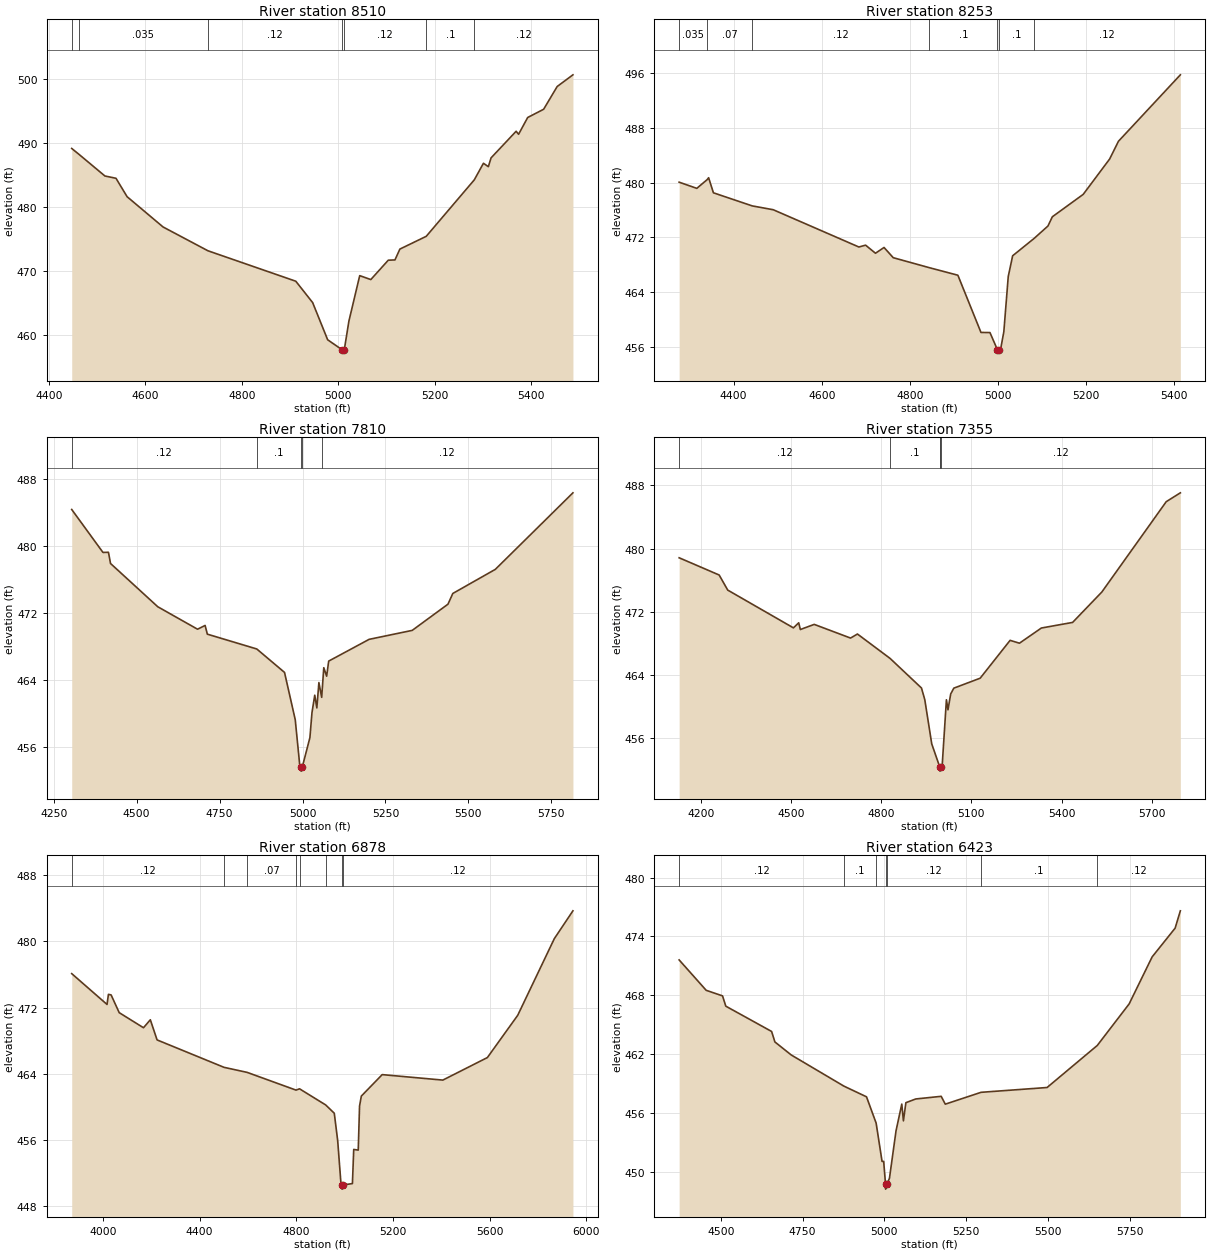
Type RM Length L Ch R = 1,8510,257,257,257
BEGIN DESCRIPTION:
H21237
END DESCRIPTION:
XS GIS Cut Line= 3
      2483563.41     13840446.94      2483823.82     13839879.24
      2483901.95     13839472.97
#Sta/Elev= 30
  4447.7  489.10  4462.3  488.21  4516.4  484.81  4539.4  484.45  4562.4  481.58
  4636.9  476.86  4729.8  473.15  4911.9  468.40  4946.8  465.07  4977.9  459.27
  5008.3  457.69  5008.5  457.19  5012.3  457.69  5021.9  462.18  5044.3  469.27
  5067.3  468.66  5103.5  471.68  5117.3  471.72  5127.5  473.41  5182.1  475.40
  5281.7  484.21  5300.6  486.79  5310.8  486.26  5316.4  487.63  5368.3  491.78
  5373.4  491.31  5392.3  493.93  5425.3  495.21  5453.4  498.76  5486.0  500.58
#Mann=7,-1,0
  4447.7    0.07       0  4462.3   0.035       0  4729.8    0.12       0
  5008.3    0.05       0  5012.3    0.12       0  5182.1     0.1       0
  5281.7    0.12       0
Bank Sta=5008.3,5012.3
Exp/Cntr=0.3,0.1

Type RM Length L Ch R = 1,8253,443,443,443
BEGIN DESCRIPTION:
StreamM029 17.0
END DESCRIPTION:
XS GIS Cut Line= 3
      2483808.20     13840618.81      2484025.00     13839925.00
      2484011.32     13839514.62
#Sta/Elev= 30
  4276.5  480.05  4316.6  479.15  4340.2  480.43  4343.4  480.70  4354.3  478.50
  4442.3  476.59  4490.0  476.03  4684.4  470.59  4699.6  470.86  4722.1  469.68
  4741.5  470.52  4762.4  469.03  4843.8  467.58  4909.1  466.47  4961.5  458.12
  4981.9  458.10  4998.8  455.60  4999.0  455.10  5002.8  455.60  5005.9  455.60
  5013.4  458.23  5023.4  466.28  5033.4  469.31  5081.7  471.82  5113.5  473.65
  5123.5  475.00  5193.5  478.27  5253.5  483.43  5273.5  486.02  5414.0  495.72
#Mann=7,-1,0
  4276.5   0.035       0  4340.2    0.07       0  4442.3    0.12       0
  4843.8     0.1       0  4998.8    0.05       0  5002.8     0.1       0
  5081.7    0.12       0
Bank Sta=4998.8,5002.8
Exp/Cntr=0.3,0.1

Type RM Length L Ch R = 1,7810,455,455,455
BEGIN DESCRIPTION:
StreamM029 16.0
END DESCRIPTION:
XS GIS Cut Line= 3
      2483980.08     13840905.26      2484275.00     13840275.00
      2484745.14     13839609.20
#Sta/Elev= 30
  4304.2  484.32  4398.4  479.19  4414.9  479.21  4421.2  477.87  4563.7  472.70
  4683.5  470.02  4706.3  470.47  4713.0  469.43  4862.0  467.66  4945.7  464.86
  4978.0  459.21  4991.4  453.85  4995.3  453.57  4995.5  453.07  4999.3  453.57
  5022.2  457.07  5028.4  460.04  5036.8  462.14  5043.1  460.62  5049.3  463.65
  5057.7  461.88  5064.0  465.42  5072.7  464.41  5078.8  466.21  5200.7  468.81
  5330.6  469.88  5438.4  473.01  5453.0  474.29  5581.2  477.17  5815.1  486.31
#Mann=5,-1,0
  4304.2    0.12       0  4862.0     0.1       0  4995.3    0.05       0
  4999.3     0.1       0  5057.7    0.12       0
Bank Sta=4995.3,4999.3
Exp/Cntr=0.3,0.1

Type RM Length L Ch R = 1,7355,477,477,477
BEGIN DESCRIPTION:
StreamM029 15.0
END DESCRIPTION:
XS GIS Cut Line= 3
      2484313.38     13841217.83      2484675.00     13840425.00
      2484891.53     13839660.47
#Sta/Elev= 30
  4128.6  478.84  4261.6  476.66  4290.1  474.75  4508.5  469.97  4526.0  470.61
  4531.5  469.76  4577.6  470.41  4698.3  468.68  4721.3  469.19  4829.6  466.11
  4934.1  462.36  4945.1  460.89  4968.2  455.29  4995.0  452.35  4995.3  452.34
  4995.5  451.84  4999.3  452.34  5002.6  452.34  5017.0  460.87  5022.2  459.60
  5031.2  461.60  5041.6  462.34  5129.2  463.60  5228.7  468.39  5259.8  468.03
  5332.6  469.95  5436.5  470.66  5533.7  474.51  5747.7  485.94  5794.6  487.06
#Mann=5,-1,0
  4128.6    0.12       0  4829.6     0.1       0  4995.0    0.12       0
  4995.3    0.05       0  4999.3    0.12       0
Bank Sta=4995.3,4999.3
Exp/Cntr=0.3,0.1

Type RM Length L Ch R = 1,6878,455,455,455
BEGIN DESCRIPTION:
StreamM029 14.0
END DESCRIPTION:
XS GIS Cut Line= 3
      2484524.98     13841631.09      2485025.00     13840625.00
      2485384.53     13839743.82
#Sta/Elev= 30
  3870.2  476.10  4016.4  472.38  4022.2  473.60  4033.3  473.53  4066.8  471.39
  4167.3  469.57  4195.7  470.53  4223.6  468.10  4500.8  464.79  4596.6  464.18
  4799.0  462.04  4813.3  462.20  4921.7  460.25  4957.3  459.25  4971.4  455.94
  4985.3  450.62  4988.9  450.59  4989.2  450.09  4992.9  450.59  5032.4  450.76
  5037.8  454.88  5056.5  454.80  5061.9  460.12  5069.3  461.32  5155.7  463.91
  5406.8  463.25  5591.2  465.97  5716.8  471.07  5868.5  480.33  5945.4  483.68
#Mann=8,-1,0
  3870.2    0.12       0  4500.8     0.1       0  4596.6    0.07       0
  4799.0    0.12       0  4813.3     0.1       0  4921.7    0.12       0
  4988.9    0.05       0  4992.9    0.12       0
Bank Sta=4988.9,4992.9
Exp/Cntr=0.3,0.1

Type RM Length L Ch R = 1,6423,440,440,440
BEGIN DESCRIPTION:
StreamM029 13.0
END DESCRIPTION:
XS GIS Cut Line= 3
      2485328.45     13841497.63      2485325.00     13840875.00
      2485400.45     13839969.07
#Sta/Elev= 30
  4372.9  471.60  4455.5  468.50  4505.5  467.93  4515.5  466.88  4655.5  464.30
  4665.5  463.23  4715.5  461.90  4876.5  458.72  4945.5  457.63  4974.9  454.95
  4993.0  451.04  4998.0  451.04  5003.6  448.71  5003.8  448.21  5007.6  448.71
  5015.6  449.31  5035.7  454.16  5053.3  456.89  5058.3  455.18  5065.8  457.03
  5095.9  457.41  5173.7  457.68  5186.2  456.88  5295.7  458.09  5497.3  458.58
  5650.7  462.87  5748.1  467.11  5818.4  471.91  5888.6  474.84  5904.6  476.61
#Mann=7,-1,0
  4372.9    0.12       0  4876.5     0.1       0  4974.9    0.12       0
  5003.6    0.05       0  5007.6    0.12       0  5295.7     0.1       0
  5650.7    0.12       0
Bank Sta=5003.6,5007.6
Exp/Cntr=0.3,0.1

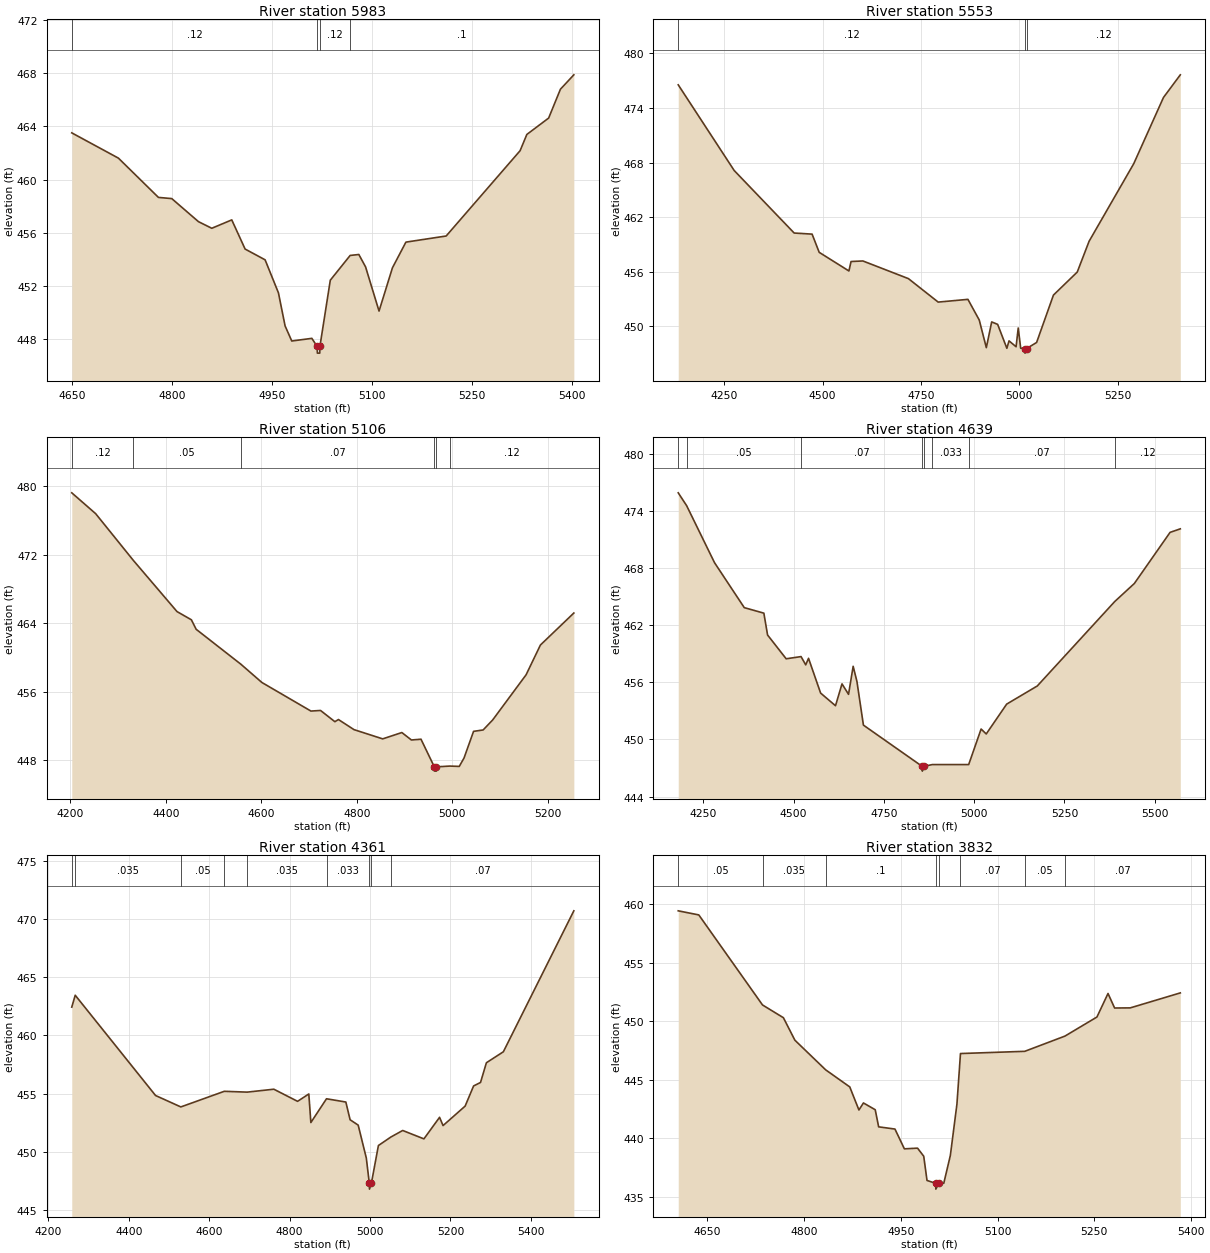
Type RM Length L Ch R = 1,5983,430,430,430
BEGIN DESCRIPTION:
StreamM029 12.0
END DESCRIPTION:
XS GIS Cut Line= 3
      2485675.00     13840975.00      2485675.00     13840625.00
      2485625.00     13840225.01
#Sta/Elev= 30
  4650.0  463.52  4720.0  461.62  4780.0  458.67  4800.0  458.58  4840.0  456.85
  4860.0  456.35  4890.0  456.98  4910.0  454.79  4940.0  453.98  4960.0  451.50
  4970.0  449.01  4980.0  447.88  5010.1  448.08  5018.1  447.47  5018.4  446.97
  5022.0  446.97  5022.2  447.47  5037.8  452.45  5067.6  454.31  5080.6  454.38
  5090.7  453.45  5110.9  450.13  5131.0  453.38  5151.2  455.31  5211.6  455.77
  5322.5  462.18  5332.6  463.40  5365.3  464.63  5383.0  466.80  5403.1  467.88
#Mann=4,-1,0
  4650.0    0.12       0  5018.1    0.05       0  5022.2    0.12       0
  5067.6     0.1       0
Bank Sta=5018.1,5022.2
Exp/Cntr=0.3,0.1

Type RM Length L Ch R = 1,5553,447,447,447
BEGIN DESCRIPTION:
StreamM029 11.0
END DESCRIPTION:
XS GIS Cut Line= 3
      2486375.00     13841225.01      2486025.00     13840425.00
      2486075.00     13840025.03
#Sta/Elev= 30
  4133.2  476.55  4275.5  467.13  4427.9  460.26  4473.5  460.14  4491.5  458.14
  4567.1  456.09  4572.5  457.13  4602.6  457.19  4718.3  455.25  4794.0  452.67
  4869.6  452.97  4898.4  450.70  4916.4  447.66  4930.0  450.49  4945.2  450.22
  4968.6  447.59  4974.1  448.41  4992.0  447.76  4997.5  449.82  5003.7  447.60
  5014.4  447.56  5014.7  447.06  5018.6  447.56  5044.2  448.23  5087.0  453.44
  5147.5  455.97  5177.7  459.36  5291.1  467.88  5366.7  475.16  5409.5  477.65
#Mann=3,-1,0
  4133.2    0.12       0  5014.4    0.05       0  5018.6    0.12       0
Bank Sta=5014.4,5018.6
Exp/Cntr=0.3,0.1

Type RM Length L Ch R = 1,5106,467,467,467
BEGIN DESCRIPTION:
StreamM029 10.0
END DESCRIPTION:
XS GIS Cut Line= 3
      2486475.00     13841274.96      2486425.00     13840475.00
      2486425.00     13840225.02
#Sta/Elev= 30
  4202.9  479.26  4253.0  476.82  4331.9  471.36  4423.3  465.38  4453.4  464.42
  4463.4  463.31  4557.2  459.22  4601.1  457.09  4703.8  453.75  4723.9  453.82
  4753.9  452.51  4761.4  452.76  4794.0  451.58  4854.1  450.50  4894.2  451.24
  4914.2  450.37  4934.3  450.46  4962.2  447.23  4962.5  446.73  4966.1  446.73
  4966.4  447.23  4994.7  447.32  5014.4  447.28  5024.4  448.26  5044.4  451.38
  5064.4  451.54  5084.4  452.71  5154.4  457.99  5184.4  461.47  5254.4  465.21
#Mann=6,-1,0
  4202.9    0.12       0  4331.9    0.05       0  4557.2    0.07       0
  4962.2    0.05       0  4966.4    0.07       0  4994.7    0.12       0
Bank Sta=4962.2,4966.4
Exp/Cntr=0.3,0.1

Type RM Length L Ch R = 1,4639,278,278,278
BEGIN DESCRIPTION:
StreamM029 9.0
END DESCRIPTION:
XS GIS Cut Line= 3
      2486575.00     13841224.98      2486775.00     13840425.00
      2486374.99     13840024.99
#Sta/Elev= 30
  4180.5  475.95  4203.9  474.59  4281.0  468.60  4363.4  463.87  4417.6  463.29
  4427.9  460.99  4479.4  458.49  4520.6  458.72  4533.5  457.85  4541.3  458.54
  4574.8  454.88  4616.0  453.55  4634.0  455.85  4652.1  454.75  4664.9  457.70
  4675.3  456.11  4693.3  451.51  4856.1  447.17  4856.4  446.67  4860.3  447.17
  4884.1  447.36  4984.8  447.36  5019.2  451.10  5033.4  450.58  5090.0  453.72
  5174.8  455.63  5389.4  464.52  5443.5  466.41  5542.5  471.79  5570.8  472.16
#Mann=8,-1,0
  4180.5    0.12       0  4203.9    0.05       0  4520.6    0.07       0
  4856.1    0.05       0  4860.3    0.07       0  4884.1   0.033       0
  4984.8    0.07       0  5389.4    0.12       0
Bank Sta=4856.1,4860.3
Exp/Cntr=0.3,0.1

Type RM Length L Ch R = 1,4361,529,529,529
BEGIN DESCRIPTION:
StreamM029 8.0
END DESCRIPTION:
XS GIS Cut Line= 4
      2486817.96     13841086.56      2487031.52     13840651.44
      2486988.13     13840247.58      2487106.15     13839909.68
#Sta/Elev= 30
  4258.2  462.43  4266.8  463.45  4466.6  454.85  4529.5  453.87  4637.6  455.21
  4694.5  455.14  4760.8  455.39  4819.8  454.35  4847.8  454.98  4852.9  452.53
  4891.8  454.57  4939.9  454.29  4950.5  452.77  4970.6  452.31  4990.8  449.49
  4998.3  447.32  4998.7  446.82  5003.4  447.32  5020.9  450.56  5052.0  451.29
  5081.3  451.85  5134.1  451.13  5173.0  452.98  5181.7  452.27  5236.6  453.94
  5257.7  455.67  5274.9  455.97  5289.5  457.66  5331.7  458.60  5507.0  470.69
#Mann=9,-1,0
  4258.2    0.05       0  4266.8   0.035       0  4529.5    0.05       0
  4637.6    0.07       0  4694.5   0.035       0  4891.8   0.033       0
  4998.3   0.033       0  5003.4   0.033       0  5052.0    0.07       0
Bank Sta=4998.3,5003.4
Exp/Cntr=0.3,0.1

Type RM Length L Ch R = 1,3832,538,538,538
BEGIN DESCRIPTION:
StreamM029 7.0
END DESCRIPTION:
XS GIS Cut Line= 3
      2487274.99     13841075.02      2487391.89     13840752.88
      2487475.01     13840324.97
#Sta/Elev= 30
  4604.7  459.44  4636.6  459.09  4735.4  451.40  4767.8  450.31  4785.6  448.39
  4833.3  445.86  4870.7  444.40  4884.9  442.43  4891.9  443.03  4910.2  442.45
  4915.5  440.99  4940.8  440.80  4955.4  439.11  4975.8  439.17  4985.4  438.48
  4990.5  436.41  5003.8  436.17  5004.2  435.67  5008.9  436.17  5016.5  436.17
  5026.7  438.55  5036.9  442.93  5042.4  447.25  5142.1  447.44  5204.4  448.74
  5254.0  450.37  5271.2  452.38  5281.4  451.14  5305.7  451.15  5383.3  452.43
#Mann=8,-1,0
  4604.7    0.05       0  4735.4   0.035       0  4833.3     0.1       0
  5003.8    0.05       0  5008.9     0.1       0  5042.4    0.07       0
  5142.1    0.05       0  5204.4    0.07       0
Bank Sta=5003.8,5008.9
Exp/Cntr=0.3,0.1

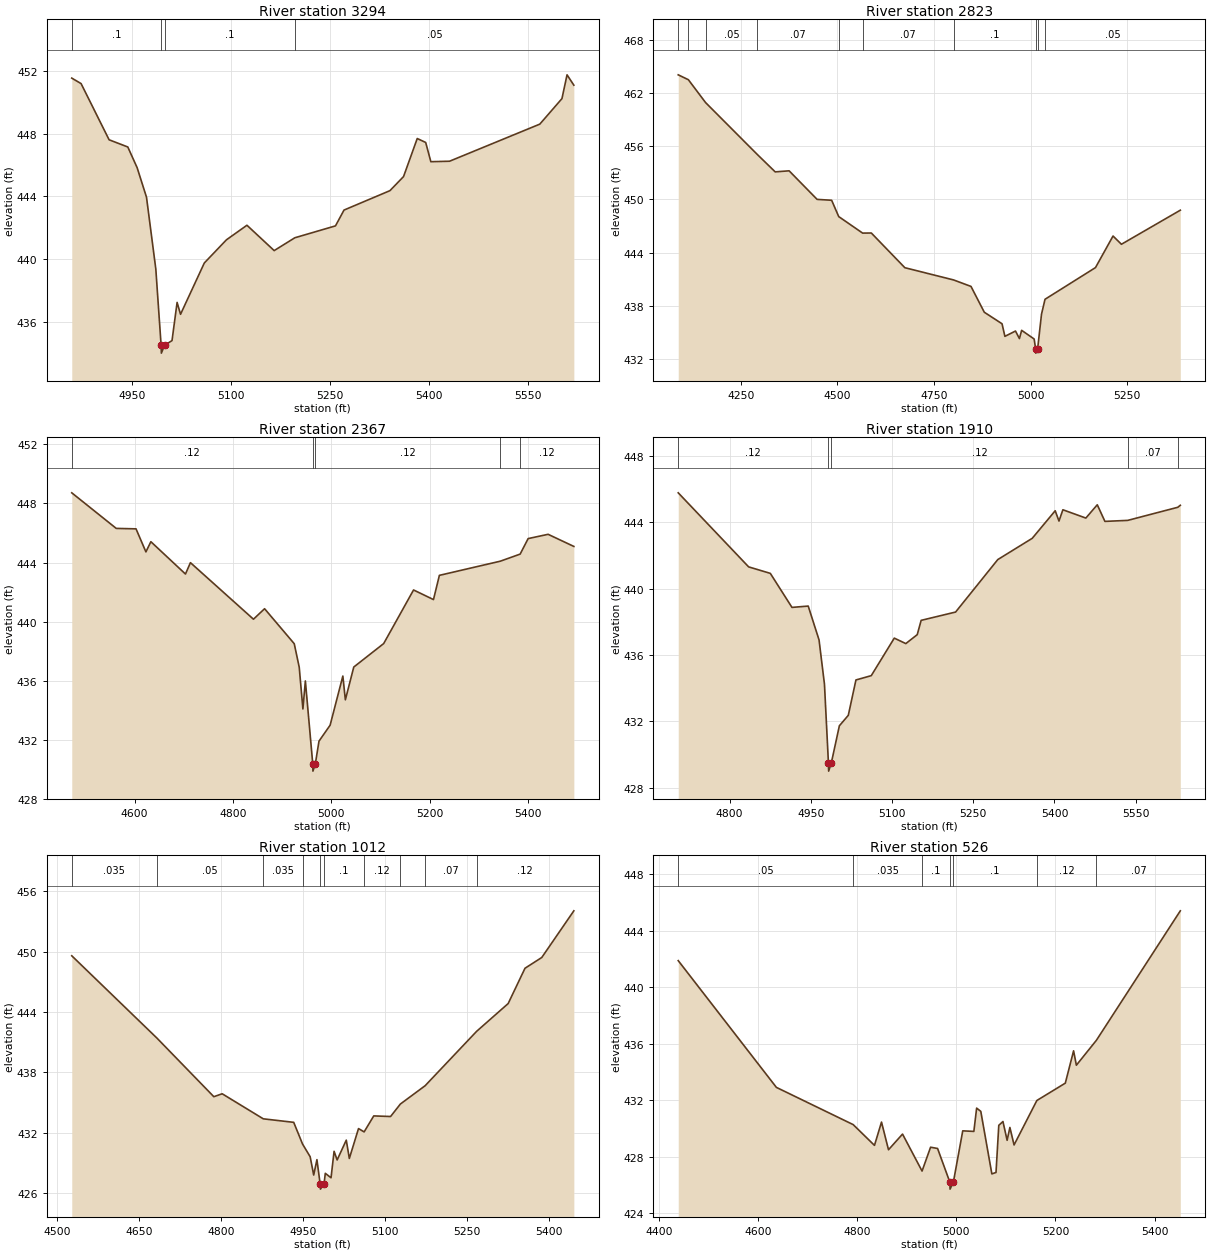
Type RM Length L Ch R = 1,3294,471,471,471
BEGIN DESCRIPTION:
StreamM029 6.0
END DESCRIPTION:
XS GIS Cut Line= 3
      2487625.03     13841124.97      2487725.00     13841025.00
      2487874.99     13840425.04
#Sta/Elev= 30
  4859.2  451.56  4873.3  451.21  4915.7  447.62  4944.0  447.16  4958.1  445.84
  4972.3  443.95  4986.4  439.36  4994.4  434.49  4994.8  433.99  4999.6  434.49
  5010.9  434.79  5018.6  437.23  5023.8  436.47  5059.8  439.75  5093.3  441.23
  5124.3  442.16  5165.5  440.54  5196.8  441.36  5258.3  442.12  5271.2  443.13
  5340.7  444.37  5361.3  445.27  5382.0  447.70  5394.8  447.45  5402.6  446.22
  5430.9  446.25  5567.5  448.62  5601.0  450.25  5608.7  451.77  5619.0  451.11
#Mann=4,-1,0
  4859.2     0.1       0  4994.4    0.05       0  4999.6     0.1       0
  5196.8    0.05       0
Bank Sta=4994.4,4999.6
Exp/Cntr=0.3,0.1

Type RM Length L Ch R = 1,2823,456,456,456
BEGIN DESCRIPTION:
StreamM029 5.0
END DESCRIPTION:
XS GIS Cut Line= 3
      2487675.01     13841624.98      2488125.00     13840825.00
      2487975.02     13840475.04
#Sta/Elev= 30
  4088.6  464.04  4114.8  463.49  4159.4  460.91  4292.7  455.08  4339.4  453.10
  4375.4  453.22  4447.8  450.00  4485.4  449.90  4503.7  448.06  4565.5  446.20
  4588.0  446.21  4674.7  442.30  4800.7  440.92  4845.8  440.19  4880.2  437.28
  4926.1  435.98  4933.5  434.56  4960.9  435.16  4971.1  434.31  4976.8  435.24
  5009.2  434.26  5012.9  433.17  5013.3  432.67  5018.2  433.17  5028.2  437.06
  5037.3  438.74  5167.8  442.31  5213.2  445.87  5234.9  444.94  5387.2  448.78
#Mann=10,-1,0
  4088.6    0.05       0  4114.8    0.07       0  4159.4    0.05       0
  4292.7    0.07       0  4503.7     0.1       0  4565.5    0.07       0
  4800.7     0.1       0  5012.9    0.05       0  5018.2     0.1       0
  5037.3    0.05       0
Bank Sta=5012.9,5018.2
Exp/Cntr=0.3,0.1

Type RM Length L Ch R = 1,2367,457,457,457
BEGIN DESCRIPTION:
StreamM029 4.0
END DESCRIPTION:
XS GIS Cut Line= 3
      2488472.99     13841494.96      2488525.00     13840975.00
      2488446.30     13840483.32
#Sta/Elev= 30
  4472.4  448.72  4562.8  446.31  4603.0  446.28  4623.1  444.72  4633.2  445.41
  4703.5  443.22  4713.6  443.99  4841.7  440.16  4864.3  440.87  4924.6  438.50
  4934.7  436.91  4942.2  434.08  4947.2  435.98  4962.2  430.37  4962.6  429.87
  4967.5  430.37  4974.9  431.90  4997.5  432.98  5023.4  436.31  5028.5  434.70
  5045.6  436.92  5106.4  438.51  5167.1  442.14  5207.6  441.49  5219.6  443.13
  5343.5  444.09  5383.8  444.57  5400.0  445.62  5440.6  445.91  5492.9  445.09
#Mann=5,-1,0
  4472.4    0.12       0  4962.2    0.05       0  4967.5    0.12       0
  5343.5    0.07       0  5383.8    0.12       0
Bank Sta=4962.2,4967.5
Exp/Cntr=0.3,0.1

Type RM Length L Ch R = 1,1910,898,898,898
BEGIN DESCRIPTION:
StreamM029 3.0
END DESCRIPTION:
XS GIS Cut Line= 3
      2488925.00     13841274.97      2488925.00     13840975.00
      2488489.52     13840523.85
#Sta/Elev= 30
  4705.3  445.77  4835.3  441.31  4875.3  440.92  4915.3  438.87  4945.3  438.95
  4965.3  436.91  4975.3  434.24  4982.6  429.51  4983.0  429.01  4988.0  429.51
  5002.8  431.74  5019.3  432.37  5033.4  434.50  5061.7  434.76  5104.2  437.02
  5125.5  436.69  5146.6  437.23  5153.8  438.09  5217.4  438.59  5295.3  441.75
  5358.9  443.03  5401.3  444.69  5408.3  444.07  5415.5  444.75  5457.9  444.25
  5479.0  445.05  5493.1  444.05  5535.2  444.11  5627.7  444.90  5632.3  445.02
#Mann=5,-1,0
  4705.3    0.12       0  4982.6    0.05       0  4988.0    0.12       0
  5535.2    0.07       0  5627.7    0.12       0
Bank Sta=4982.6,4988
Exp/Cntr=0.3,0.1

Type RM Length L Ch R = 1,1012,486,486,486
BEGIN DESCRIPTION:
StreamM029 2.0
END DESCRIPTION:
XS GIS Cut Line= 3
      2489375.00     13841374.99      2489625.00     13840975.00
      2489425.00     13840575.00
#Sta/Elev= 30
  4527.4  449.59  4683.2  441.41  4787.4  435.58  4802.7  435.87  4877.9  433.38
  4933.6  433.03  4949.8  430.87  4963.7  429.61  4970.2  427.79  4976.1  429.32
  4982.0  426.89  4982.5  426.39  4989.1  426.89  4991.4  427.96  5001.9  427.52
  5007.5  430.15  5013.1  429.29  5029.8  431.26  5035.4  429.44  5052.2  432.41
  5062.5  432.08  5080.1  433.67  5110.9  433.61  5128.8  434.85  5174.1  436.67
  5268.4  442.08  5326.1  444.84  5356.9  448.35  5387.6  449.42  5446.3  454.06
#Mann=10,-1,0
  4527.4   0.035       0  4683.2    0.05       0  4877.9   0.035       0
  4949.8     0.1       0  4982.0    0.05       0  4989.1     0.1       0
  5062.5    0.12       0  5128.8     0.1       0  5174.1    0.07       0
  5268.4    0.12       0
Bank Sta=4982,4989.1
Exp/Cntr=0.3,0.1

Type RM Length L Ch R = 1,526,0,0,0
BEGIN DESCRIPTION:
StreamM029 1.0
END DESCRIPTION:
XS GIS Cut Line= 3
      2489675.02     13841474.98      2490075.00     13841075.00
      2490275.01     13840674.97
#Sta/Elev= 30
  4439.0  441.88  4637.0  432.90  4792.0  430.26  4834.9  428.79  4849.1  430.44
  4863.2  428.48  4891.5  429.59  4930.9  426.97  4948.1  428.66  4962.2  428.57
  4986.9  426.19  4987.4  425.69  4994.1  426.19  5013.0  429.82  5035.4  429.78
  5041.0  431.43  5049.4  431.20  5071.7  426.77  5080.1  426.87  5085.7  430.21
  5094.1  430.48  5102.5  429.15  5108.1  430.06  5116.5  428.82  5162.5  431.97
  5219.9  433.20  5236.6  435.49  5242.2  434.47  5282.7  436.24  5451.9  445.41
#Mann=7,-1,0
  4439.0    0.05       0  4792.0   0.035       0  4930.9     0.1       0
  4986.9    0.05       0  4994.1     0.1       0  5162.5    0.12       0
  5282.7    0.07       0
Bank Sta=4986.9,4994.1
Exp/Cntr=0.3,0.1

Chan Stop Cuts=-1