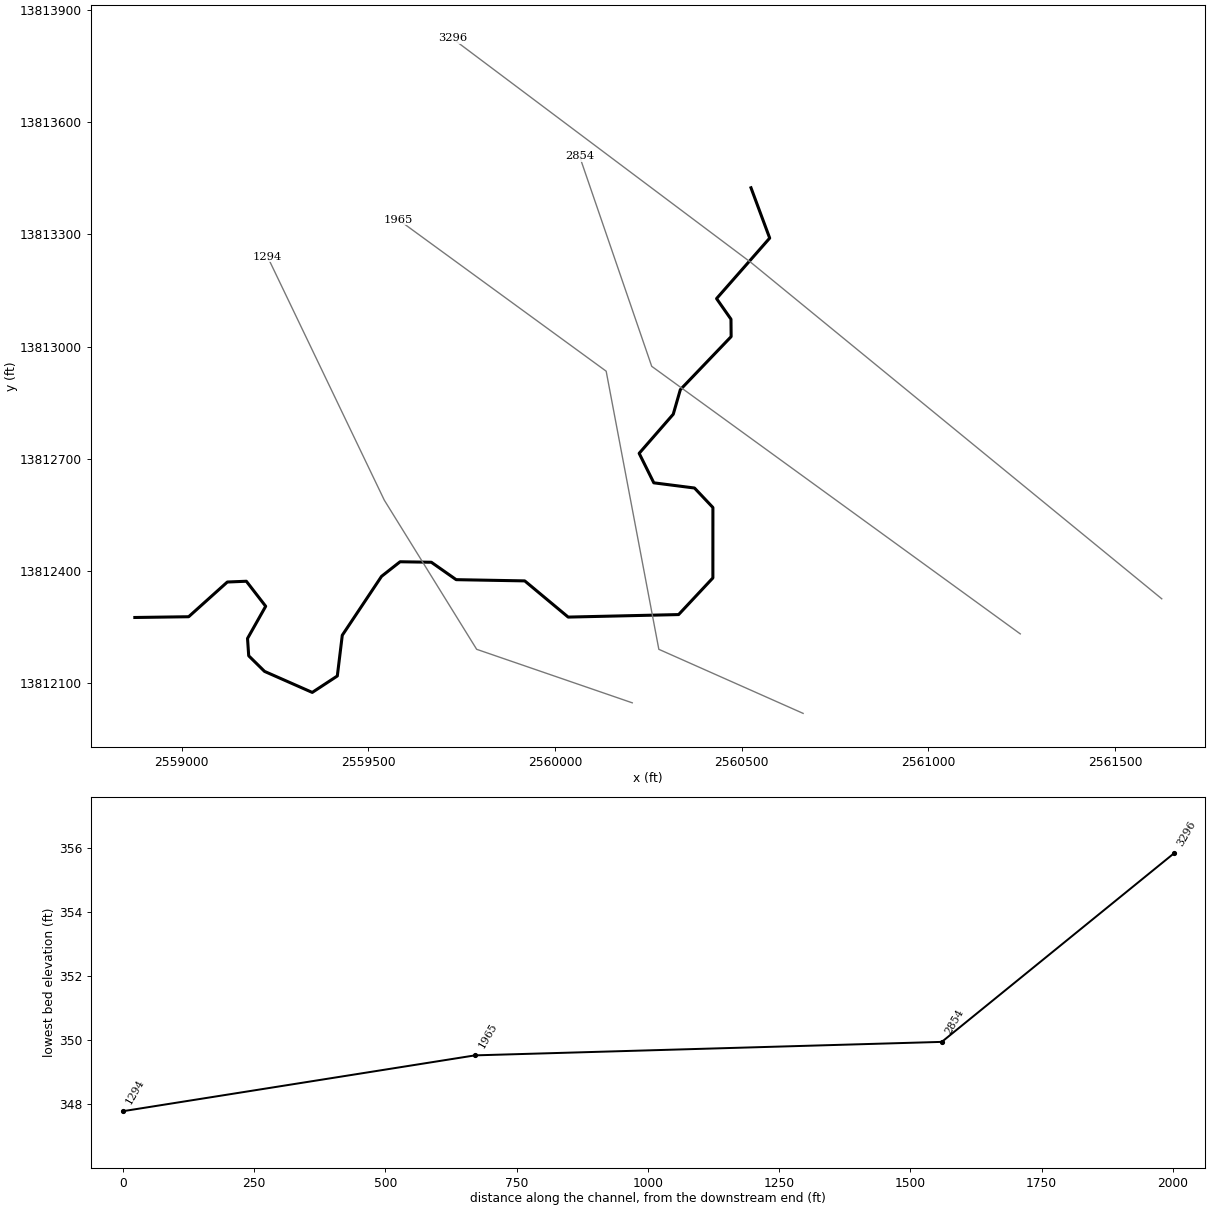
--- StreamM03.prj (project) ---

Proj Title=StreamM03 Base Level Engineering
Current Plan=p01
Default Exp/Contr=0.3,0.1
English Units
Geom File=g01
Flow File=f01
Plan File=p01
BEGIN DESCRIPTION:
StreamM03
END DESCRIPTION:

--- StreamM03.p01 (plan) ---

Plan Title=Multiple Run
Short Identifier=Multiple
Geom File=g01
Flow File=f01
Subcritical Flow
K Sum by GR= 0
Std Step Tol= 0.01
Critical Tol= 0.01
Num of Std Step Trials= 20
Max Error Tol= 0.3
Flow Tol Ratio= 0.001
Split Flow NTrial= 30
Split Flow Tol= 0.02
Split Flow Ratio= 0.02
Log Output Level= 0
Friction Slope Method= 1
Unsteady Friction Slope Method= 2
Unsteady Bridges Friction Slope Method= 1
Parabolic Critical Depth
Global Vel Dist=  1 , 1 , 1
Global Log Level= 0
CheckData=True
Encroach Param= -1, 0, 0, 0
BEGIN DESCRIPTION:
Multiple Run
END DESCRIPTION:

--- StreamM03.f01 (steady flow) ---

Flow Title=Multiple
Number of Profiles=7
Profile Names=10-year,25-year,50-year,1pct_min,100-year,1pct_plu,500-year
River Rch & RM= StreamM03,Reach-1,3296
     669    1061    1410     907    1810    3611    2949
River Rch & RM= StreamM03,Reach-1,1965
     941    1521    2047    1332    2658    5303    4433
Boundary for River Rch & Prof#=StreamM03,Reach-1,1
Up Type=0
Dn Type=3
Dn Slope=0.005
Boundary for River Rch & Prof#=StreamM03,Reach-1,2
Up Type=0
Dn Type=3
Dn Slope=0.005
Boundary for River Rch & Prof#=StreamM03,Reach-1,3
Up Type=0
Dn Type=3
Dn Slope=0.005
Boundary for River Rch & Prof#=StreamM03,Reach-1,4
Up Type=0
Dn Type=3
Dn Slope=0.005
Boundary for River Rch & Prof#=StreamM03,Reach-1,5
Up Type=0
Dn Type=3
Dn Slope=0.005
Boundary for River Rch & Prof#=StreamM03,Reach-1,6
Up Type=0
Dn Type=3
Dn Slope=0.005
Boundary for River Rch & Prof#=StreamM03,Reach-1,7
Up Type=0
Dn Type=3
Dn Slope=0.005

--- StreamM03.g01 (geometry) ---

Geom Title=Existing Conditions

River Reach=StreamM03,Reach-1
Reach XY= 30
      2560525.00     13813425.00      2560575.09     13813290.33
      2560432.82     13813128.41      2560471.41     13813073.35
      2560471.84     13813026.65      2560335.78     13812884.68
      2560316.82     13812818.96      2560225.53     13812714.31
      2560264.78     13812635.39      2560373.75     13812621.49
      2560423.03     13812569.35      2560422.95     13812380.84
      2560331.21     13812282.80      2560035.44     13812276.06
      2559919.14     13812372.93      2559735.50     13812376.22
      2559669.02     13812422.84      2559585.33     13812424.13
      2559535.63     13812385.06      2559430.54     13812227.42
      2559417.25     13812118.45      2559350.13     13812074.45
      2559222.38     13812130.72      2559179.99     13812172.45
      2559176.79     13812218.84      2559225.43     13812305.00
      2559173.63     13812371.99      2559122.75     13812369.93
      2559019.17     13812277.02      2558875.00     13812275.00

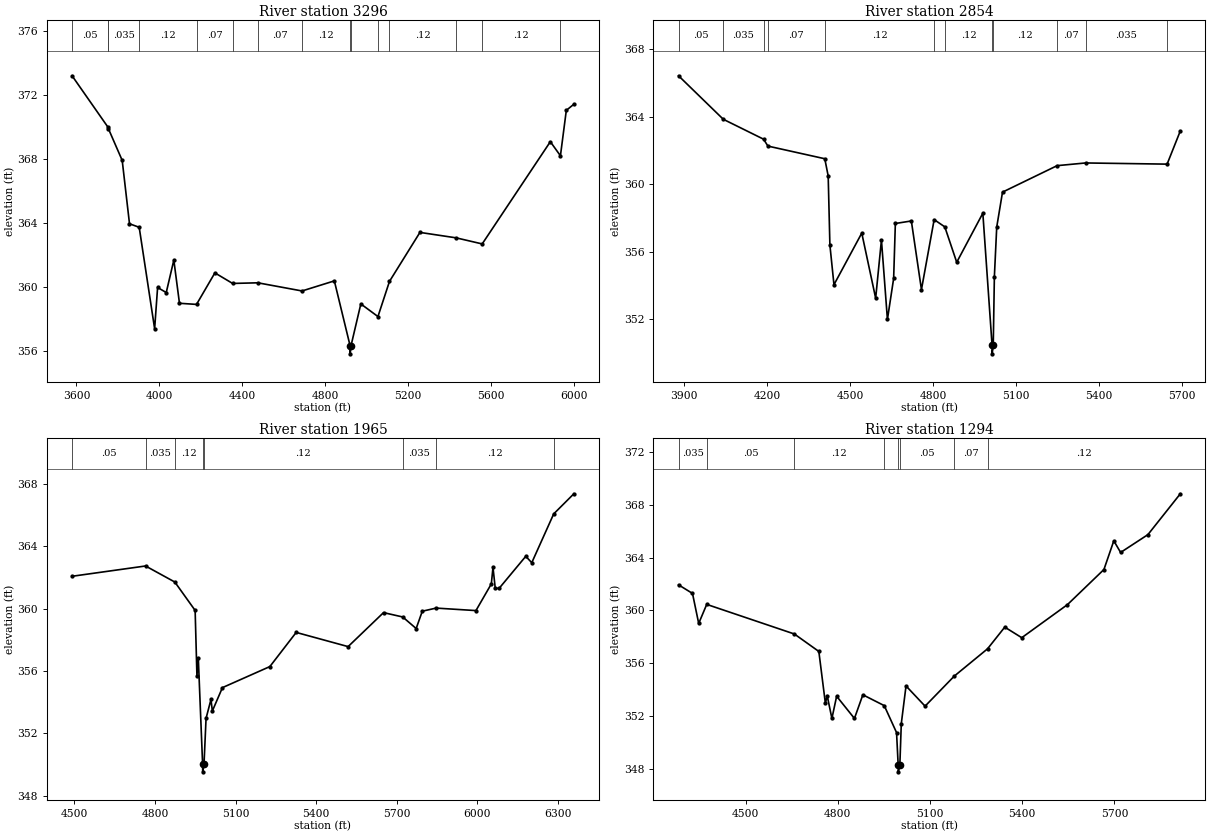
Type RM Length L Ch R = 1,3296,442,442,442
BEGIN DESCRIPTION:
StreamM03 3.0
END DESCRIPTION:
XS GIS Cut Line= 3
      2561624.99     13812325.01      2560525.00     13813225.00
      2559725.04     13813824.97
#Sta/Elev= 30
  3579.0  373.20  3752.6  369.98  3754.4  369.89  3820.9  367.91  3856.1  363.95
  3902.9  363.73  3977.4  357.39  3991.7  359.97  4033.4  359.65  4070.0  361.68
  4097.2  358.98  4179.5  358.91  4268.1  360.88  4353.7  360.22  4475.4  360.26
  4688.6  359.75  4844.5  360.38  4920.6  356.32  4920.9  355.82  4924.8  356.32
  4972.3  358.94  5054.9  358.15  5110.6  360.35  5257.5  363.41  5432.2  363.07
  5557.9  362.69  5886.7  369.08  5935.4  368.20  5963.8  371.04  6000.2  371.42
#Mann=15,-1,0
  3579.0    0.05       0  3752.6    0.07       0  3754.4   0.035       0
  3902.9    0.12       0  4179.5    0.07       0  4353.7    0.05       0
  4475.4    0.07       0  4688.6    0.12       0  4920.6    0.05       0
  4924.8    0.12       0  5054.9    0.07       0  5110.6    0.12       0
  5432.2   0.035       0  5557.9    0.12       0  5935.4    0.05       0
Bank Sta=4920.6,4924.8
Exp/Cntr=0.3,0.1

Type RM Length L Ch R = 1,2854,889,889,889
BEGIN DESCRIPTION:
StreamM03 2.0
END DESCRIPTION:
XS GIS Cut Line= 3
      2561246.09     13812231.09      2560259.14     13812947.21
      2560066.00     13813509.27
#Sta/Elev= 30
  3879.7  366.44  4041.5  363.86  4187.0  362.68  4202.8  362.27  4408.3  361.52
  4420.6  360.50  4426.8  356.40  4441.5  354.05  4542.0  357.11  4592.2  353.25
  4613.1  356.70  4634.7  351.99  4657.2  354.42  4663.4  357.68  4721.2  357.83
  4757.7  353.76  4803.6  357.91  4842.1  357.48  4885.2  355.38  4979.6  358.29
  5013.0  350.45  5013.3  349.95  5017.2  350.45  5021.3  354.53  5029.8  357.47
  5050.7  359.54  5248.1  361.11  5351.1  361.27  5645.6  361.20  5693.4  363.17
#Mann=12,-1,0
  3879.7    0.05       0  4041.5   0.035       0  4187.0    0.05       0
  4202.8    0.07       0  4408.3    0.12       0  4803.6    0.07       0
  4842.1    0.12       0  5013.0    0.05       0  5017.2    0.12       0
  5248.1    0.07       0  5351.1   0.035       0  5645.6    0.12       0
Bank Sta=5013,5017.2
Exp/Cntr=0.3,0.1

Type RM Length L Ch R = 1,1965,671,671,671
BEGIN DESCRIPTION:
StreamM03 1.0
END DESCRIPTION:
XS GIS Cut Line= 4
      2560664.57     13812018.37      2560278.24     13812189.83
      2560137.18     13812934.19      2559580.15     13813340.08
#Sta/Elev= 30
  4491.0  362.07  4764.8  362.73  4873.9  361.70  4949.5  359.88  4956.2  355.69
  4961.3  356.84  4977.3  350.03  4977.7  349.53  4982.6  350.03  4990.2  352.96
  5008.5  354.17  5013.6  353.43  5051.2  354.93  5227.9  356.28  5326.0  358.47
  5519.4  357.56  5651.4  359.74  5722.9  359.46  5773.0  358.72  5795.8  359.83
  5847.3  360.03  5995.7  359.87  6053.0  361.58  6059.2  362.64  6067.7  361.29
  6082.3  361.30  6181.3  363.35  6203.7  362.94  6285.4  366.07  6360.5  367.36
#Mann=8,-1,0
  4491.0    0.05       0  4764.8   0.035       0  4873.9    0.12       0
  4977.3    0.05       0  4982.6    0.12       0  5722.9   0.035       0
  5847.3    0.12       0  6285.4    0.07       0
Bank Sta=4977.3,4982.6
Exp/Cntr=0.3,0.1

Type RM Length L Ch R = 1,1294,0,0,0
BEGIN DESCRIPTION:
H21238
END DESCRIPTION:
XS GIS Cut Line= 4
      2560207.01     13812046.62      2559790.39     13812189.83
      2559542.99     13812589.14      2559230.56     13813240.05
#Sta/Elev= 30
  4282.1  361.94  4327.5  361.29  4347.7  359.02  4373.8  360.46  4658.9  358.22
  4738.5  356.90  4759.8  352.97  4765.6  353.56  4781.0  351.83  4796.4  353.51
  4854.3  351.83  4881.7  353.62  4951.3  352.80  4991.3  350.76  4996.6  348.29
  4997.0  347.79  5002.0  348.29  5006.7  351.43  5022.1  354.29  5084.1  352.76
  5178.9  355.03  5287.3  357.10  5343.3  358.74  5398.6  357.94  5547.1  360.44
  5665.9  363.10  5698.0  365.27  5720.2  364.39  5809.0  365.74  5914.4  368.83
#Mann=8,-1,0
  4282.1   0.035       0  4373.8    0.05       0  4658.9    0.12       0
  4951.3    0.05       0  4996.6    0.05       0  5002.0    0.05       0
  5178.9    0.07       0  5287.3    0.12       0
Bank Sta=4996.6,5002
Exp/Cntr=0.3,0.1

Chan Stop Cuts=-1