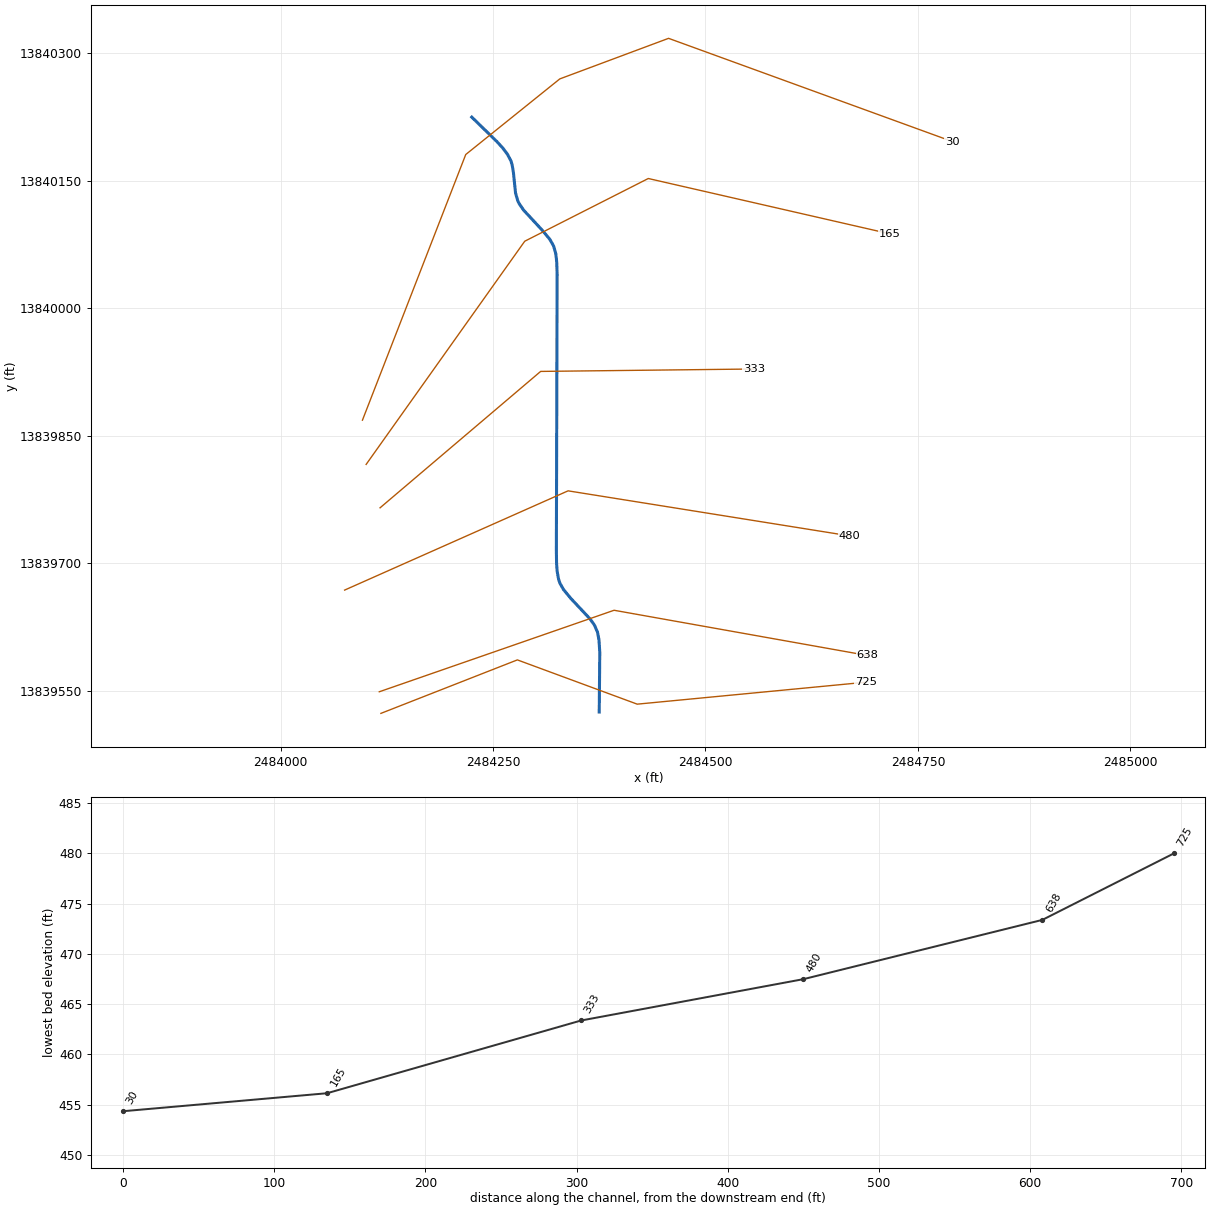
--- StreamM030.prj (project) ---

Proj Title=StreamM030 Base Level Engineering
Current Plan=p01
Default Exp/Contr=0.3,0.1
English Units
Geom File=g01
Flow File=f01
Plan File=p01
BEGIN DESCRIPTION:
StreamM030
END DESCRIPTION:

--- StreamM030.p01 (plan) ---

Plan Title=Multiple Run
Short Identifier=Multiple
Geom File=g01
Flow File=f01
Subcritical Flow
K Sum by GR= 0
Std Step Tol= 0.01
Critical Tol= 0.01
Num of Std Step Trials= 20
Max Error Tol= 0.3
Flow Tol Ratio= 0.001
Split Flow NTrial= 30
Split Flow Tol= 0.02
Split Flow Ratio= 0.02
Log Output Level= 0
Friction Slope Method= 1
Unsteady Friction Slope Method= 2
Unsteady Bridges Friction Slope Method= 1
Parabolic Critical Depth
Global Vel Dist=  1 , 1 , 1
Global Log Level= 0
CheckData=True
Encroach Param= -1, 0, 0, 0
BEGIN DESCRIPTION:
Multiple Run
END DESCRIPTION:

--- StreamM030.f01 (steady flow) ---

Flow Title=Multiple
Number of Profiles=7
Profile Names=10-year,25-year,50-year,1pct_min,100-year,1pct_plu,500-year
River Rch & RM= StreamM030,Reach-1,725
     132     191     238     145     290     578     422
River Rch & RM= StreamM030,Reach-1,30
     717    1152    1543    1001    1996    3983    3308
Boundary for River Rch & Prof#=StreamM030,Reach-1,1
Up Type=0
Dn Type=3
Dn Slope=0.005
Boundary for River Rch & Prof#=StreamM030,Reach-1,2
Up Type=0
Dn Type=3
Dn Slope=0.005
Boundary for River Rch & Prof#=StreamM030,Reach-1,3
Up Type=0
Dn Type=3
Dn Slope=0.005
Boundary for River Rch & Prof#=StreamM030,Reach-1,4
Up Type=0
Dn Type=3
Dn Slope=0.005
Boundary for River Rch & Prof#=StreamM030,Reach-1,5
Up Type=0
Dn Type=3
Dn Slope=0.005
Boundary for River Rch & Prof#=StreamM030,Reach-1,6
Up Type=0
Dn Type=3
Dn Slope=0.005
Boundary for River Rch & Prof#=StreamM030,Reach-1,7
Up Type=0
Dn Type=3
Dn Slope=0.005

--- StreamM030.g01 (geometry) ---

Geom Title=Existing Conditions

River Reach=StreamM030,Reach-1
Reach XY= 30
      2484375.00     13839525.00      2484375.63     13839595.26
      2484374.71     13839609.88      2484372.90     13839619.13
      2484369.32     13839627.36      2484364.14     13839634.64
      2484341.83     13839658.40      2484333.10     13839668.93
      2484328.75     13839676.55      2484327.24     13839680.93
      2484325.51     13839690.21      2484324.79     13839699.91
      2484324.55     13839714.81      2484325.44     13840040.18
      2484324.94     13840054.98      2484323.81     13840064.51
      2484321.26     13840073.45      2484316.92     13840081.08
      2484308.21     13840091.62      2484286.10     13840115.46
      2484281.03     13840122.78      2484279.08     13840126.69
      2484276.52     13840135.63      2484274.03     13840159.60
      2484272.49     13840168.96      2484271.13     13840173.40
      2484267.09     13840181.15      2484261.71     13840188.35
      2484254.86     13840195.92      2484225.00     13840225.00

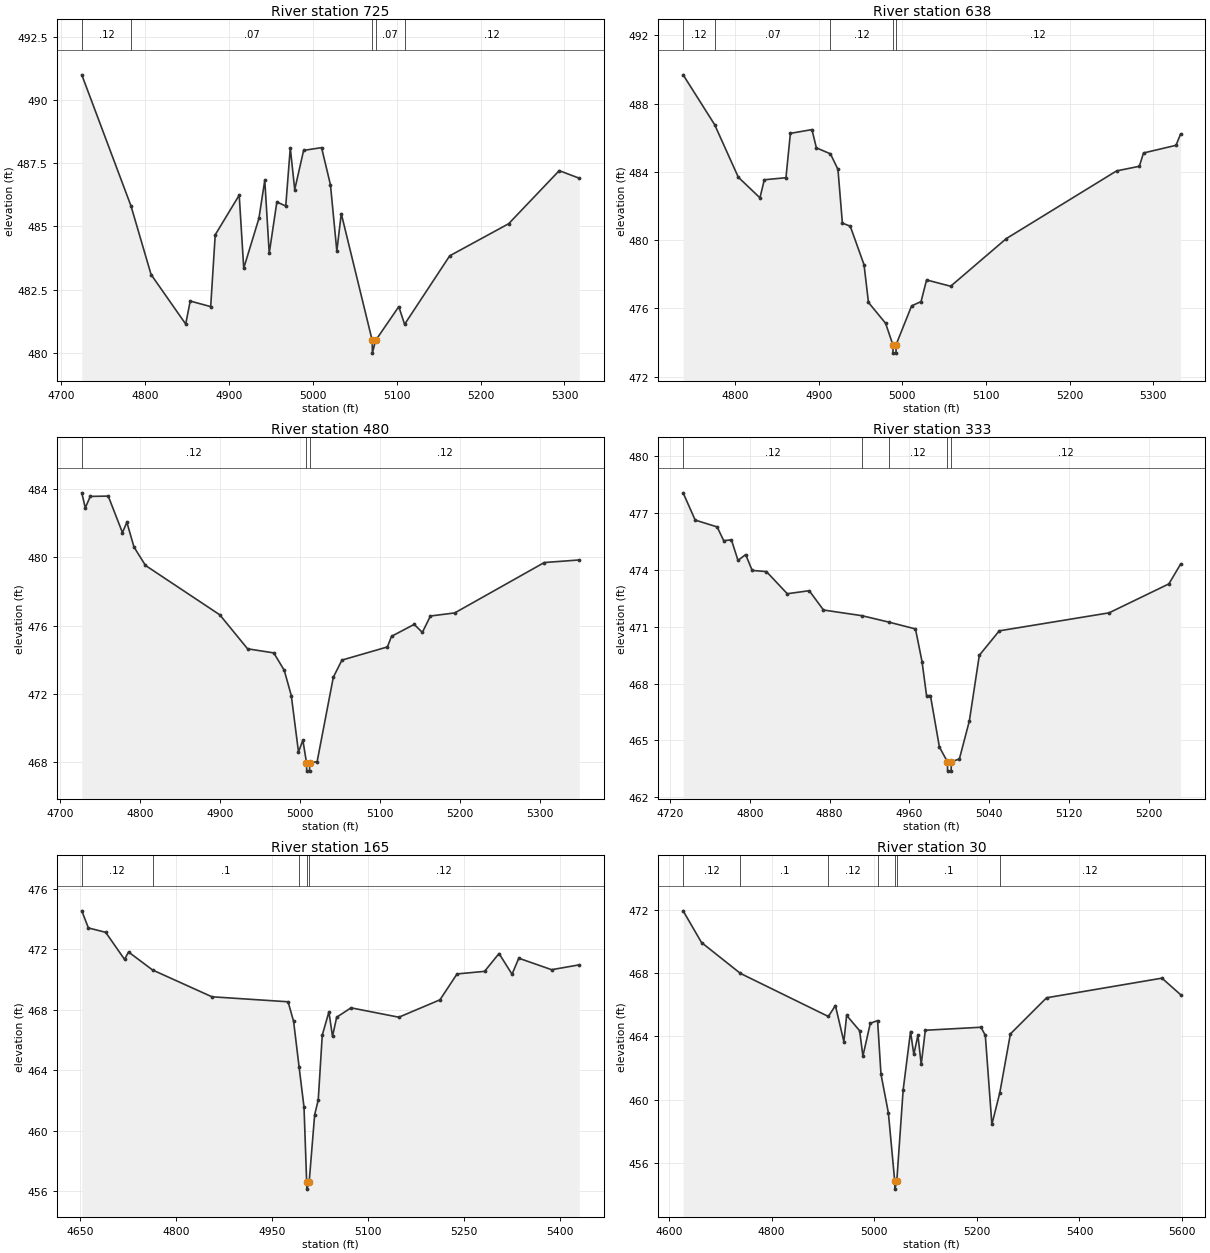
Type RM Length L Ch R = 1,725,87,87,87
BEGIN DESCRIPTION:
H21241
END DESCRIPTION:
XS GIS Cut Line= 4
      2484118.06     13839523.44      2484278.65     13839586.37
      2484419.71     13839534.29      2484688.72     13839560.11
#Sta/Elev= 30
  4724.5  491.00  4783.2  485.81  4807.1  483.10  4848.4  481.14  4853.8  482.05
  4878.2  481.83  4883.6  484.67  4912.2  486.24  4917.6  483.35  4935.7  485.32
  4942.7  486.83  4948.0  483.94  4957.1  485.97  4967.7  485.81  4973.1  488.11
  4978.4  486.46  4989.0  488.01  5010.4  488.12  5021.0  486.65  5028.6  484.03
  5033.9  485.51  5070.8  480.49  5071.0  479.99  5074.8  480.49  5102.5  481.83
  5109.4  481.13  5163.2  483.84  5233.5  485.11  5293.8  487.21  5317.6  486.91
#Mann=5,-1,0
  4724.5    0.12       0  4783.2    0.07       0  5070.8    0.05       0
  5074.8    0.07       0  5109.4    0.12       0
Bank Sta=5070.8,5074.8
Exp/Cntr=0.3,0.1

Type RM Length L Ch R = 1,638,158,158,158
BEGIN DESCRIPTION:
MXS18478
END DESCRIPTION:
XS GIS Cut Line= 3
      2484116.15     13839548.86      2484392.45     13839644.76
      2484690.29     13839591.64
#Sta/Elev= 30
  4737.7  489.69  4775.4  486.77  4803.7  483.69  4829.6  482.48  4834.8  483.54
  4860.7  483.66  4866.0  486.26  4891.8  486.48  4897.1  485.41  4913.9  485.06
  4922.9  484.15  4928.2  481.00  4937.6  480.82  4954.1  478.56  4959.4  476.35
  4979.9  475.13  4988.5  473.88  4988.8  473.38  4992.3  473.38  4992.5  473.88
  5011.0  476.15  5022.3  476.40  5028.9  477.67  5057.7  477.30  5124.2  480.09
  5256.2  484.06  5283.4  484.33  5288.4  485.11  5327.3  485.56  5332.7  486.22
#Mann=5,-1,0
  4737.7    0.12       0  4775.4    0.07       0  4913.9    0.12       0
  4988.5    0.05       0  4992.5    0.12       0
Bank Sta=4988.5,4992.5
Exp/Cntr=0.3,0.1

Type RM Length L Ch R = 1,480,147,147,147
BEGIN DESCRIPTION:
StreamM030 1.0
END DESCRIPTION:
XS GIS Cut Line= 3
      2484075.34     13839668.50      2484338.33     13839785.28
      2484668.87     13839732.42
#Sta/Elev= 30
  4726.9  483.78  4731.3  482.90  4737.5  483.57  4760.0  483.59  4777.8  481.45
  4783.3  482.06  4792.2  480.61  4806.6  479.53  4899.6  476.64  4934.4  474.65
  4967.2  474.41  4980.3  473.39  4989.1  471.91  4998.1  468.61  5003.6  469.30
  5008.1  467.99  5008.4  467.49  5011.9  467.49  5012.1  467.99  5021.4  468.04
  5041.7  472.99  5052.5  473.99  5109.4  474.76  5114.5  475.38  5142.9  476.08
  5153.1  475.61  5163.2  476.57  5193.6  476.75  5305.7  479.70  5349.4  479.85
#Mann=3,-1,0
  4726.9    0.12       0  5008.1    0.05       0  5012.1    0.12       0
Bank Sta=5008.1,5012.1
Exp/Cntr=0.3,0.1

Type RM Length L Ch R = 1,333,168,168,168
BEGIN DESCRIPTION:
MXS18477
END DESCRIPTION:
XS GIS Cut Line= 3
      2484117.07     13839765.31      2484306.05     13839925.80
      2484556.71     13839928.64
#Sta/Elev= 30
  4733.1  478.08  4745.2  476.64  4767.2  476.28  4773.8  475.55  4781.5  475.60
  4788.1  474.51  4795.8  474.82  4802.3  473.98  4816.6  473.92  4837.5  472.75
  4859.5  472.91  4873.8  471.89  4912.4  471.59  4939.4  471.25  4966.0  470.89
  4972.6  469.16  4977.1  467.37  4981.0  467.37  4990.0  464.65  4998.0  463.88
  4998.2  463.38  5001.7  463.38  5002.0  463.88  5010.0  464.02  5020.0  466.03
  5030.0  469.50  5050.0  470.79  5160.0  471.74  5220.0  473.27  5231.7  474.31
#Mann=5,-1,0
  4733.1    0.12       0  4912.4     0.1       0  4939.4    0.12       0
  4998.0    0.05       0  5002.0    0.12       0
Bank Sta=4998,5002
Exp/Cntr=0.3,0.1

Type RM Length L Ch R = 1,165,135,135,135
BEGIN DESCRIPTION:
H21240
END DESCRIPTION:
XS GIS Cut Line= 4
      2484100.68     13839816.38      2484287.33     13840078.99
      2484432.73     13840152.78      2484717.04     13840087.67
#Sta/Elev= 30
  4653.0  474.54  4663.3  473.41  4690.3  473.12  4719.8  471.33  4726.0  471.82
  4763.6  470.63  4856.3  468.86  4975.2  468.53  4983.8  467.24  4992.5  464.19
  5000.1  461.56  5004.2  456.65  5004.5  456.15  5008.2  456.65  5016.7  461.06
  5022.3  462.04  5028.6  466.33  5039.0  467.86  5044.6  466.24  5051.1  467.51
  5073.5  468.13  5148.2  467.51  5212.4  468.66  5239.1  470.37  5282.1  470.54
  5304.7  471.72  5325.0  470.35  5335.5  471.41  5386.8  470.65  5429.9  470.97
#Mann=5,-1,0
  4653.0    0.12       0  4763.6     0.1       0  4992.5    0.12       0
  5004.2    0.05       0  5008.2    0.12       0
Bank Sta=5004.2,5008.2
Exp/Cntr=0.3,0.1

Type RM Length L Ch R = 1,30,0,0,0
BEGIN DESCRIPTION:
H21239
END DESCRIPTION:
XS GIS Cut Line= 5
      2484096.34     13839868.44      2484217.89     13840180.99
      2484328.57     13840269.97      2484456.60     13840317.71
      2484790.41     13840196.32
#Sta/Elev= 30
  4627.7  471.93  4663.5  469.93  4739.3  467.98  4910.7  465.26  4924.4  465.95
  4940.9  463.67  4946.3  465.33  4971.6  464.36  4978.0  462.76  4992.4  464.83
  5006.6  465.00  5013.2  461.62  5027.6  459.18  5040.0  454.86  5040.3  454.36
  5044.0  454.86  5056.4  460.62  5070.8  464.31  5077.2  462.86  5085.2  464.08
  5091.6  462.23  5099.6  464.39  5208.0  464.58  5216.5  464.07  5229.3  458.45
  5244.7  460.44  5265.4  464.16  5335.8  466.44  5560.7  467.68  5596.9  466.64
#Mann=7,-1,0
  4627.7    0.12       0  4739.3     0.1       0  4910.7    0.12       0
  5006.6     0.1       0  5040.0    0.05       0  5044.0     0.1       0
  5244.7    0.12       0
Bank Sta=5040,5044
Exp/Cntr=0.3,0.1

Chan Stop Cuts=-1