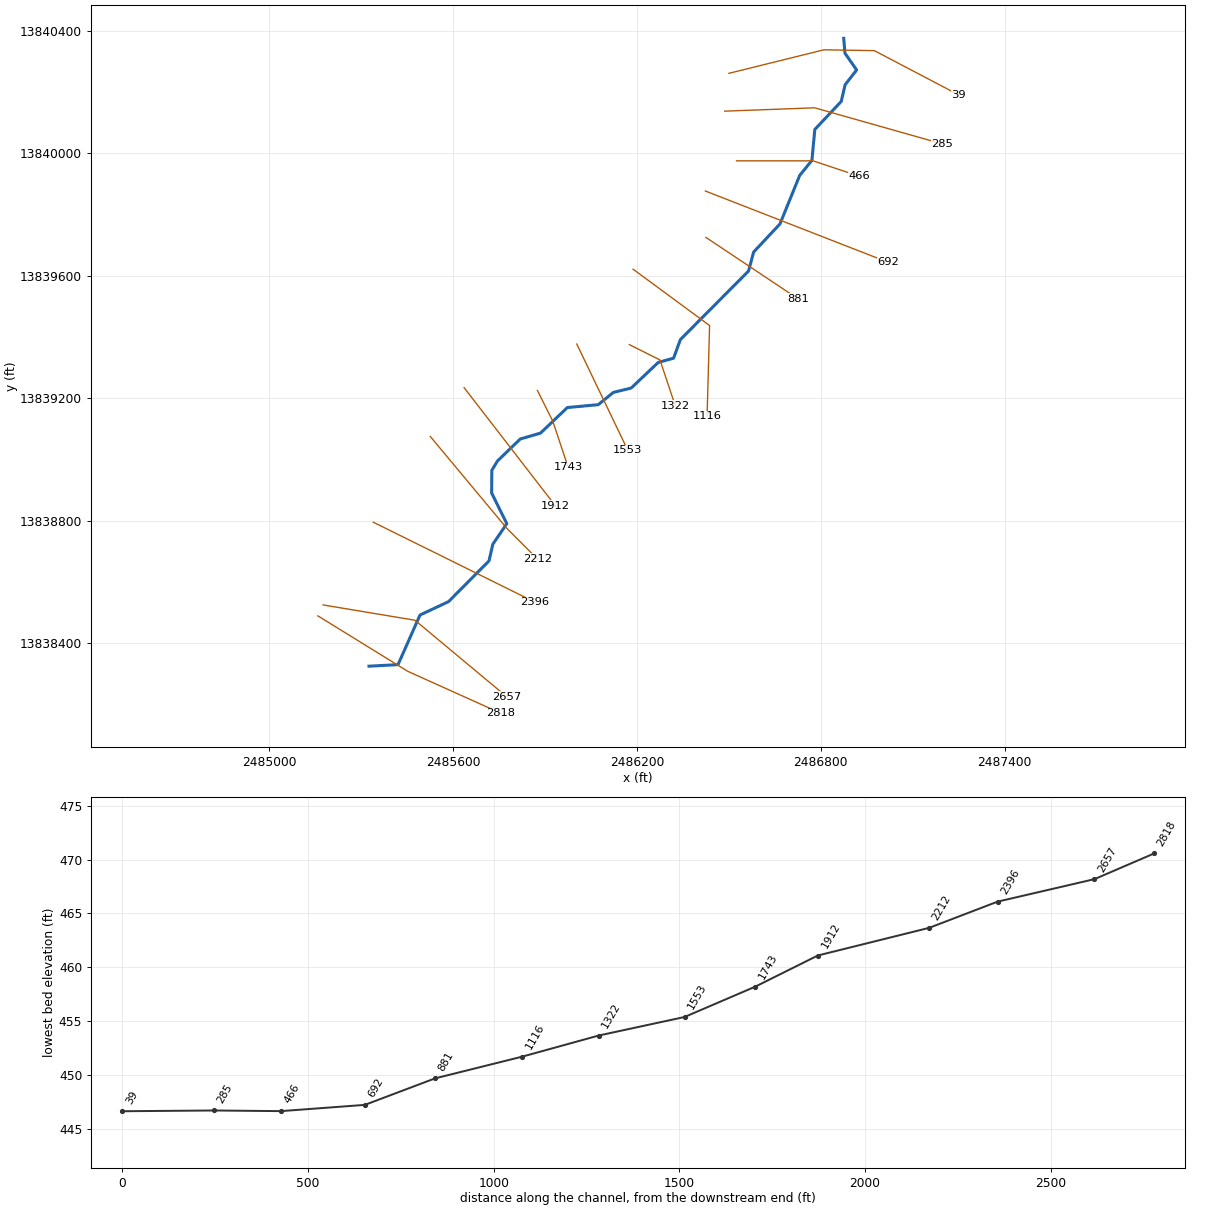
--- StreamM031.prj (project) ---

Proj Title=StreamM031 Base Level Engineering
Current Plan=p01
Default Exp/Contr=0.3,0.1
English Units
Geom File=g01
Flow File=f01
Plan File=p01
Y Axis Title=Elevation
X Axis Title(PF)=Main Channel Distance
X Axis Title(XS)=Station
BEGIN DESCRIPTION:
StreamM031
END DESCRIPTION:
DSS Export Rating Curves= 0
DSS Export Rating Curve Sorted= 0
DSS Export Volume Flow Curves= 0
DXF OffsetX= 0
DXF OffsetY= 0
DXF ScaleX= 1
DXF ScaleY= 10

--- StreamM031.p01 (plan) ---

Plan Title=Multiple Run
Short Identifier=Multiple
Geom File=g01
Flow File=f01
Subcritical Flow
K Sum by GR= 0
Std Step Tol= 0.01
Critical Tol= 0.01
Num of Std Step Trials= 20
Max Error Tol= 0.3
Flow Tol Ratio= 0.001
Split Flow NTrial= 30
Split Flow Tol= 0.02
Split Flow Ratio= 0.02
Log Output Level= 0
Friction Slope Method= 1
Unsteady Friction Slope Method= 2
Unsteady Bridges Friction Slope Method= 1
Parabolic Critical Depth
Global Vel Dist=  1 , 1 , 1
Global Log Level= 0
CheckData=True
Encroach Param= -1, 0, 0, 0
BEGIN DESCRIPTION:
Multiple Run
END DESCRIPTION:

--- StreamM031.f01 (steady flow) ---

Flow Title=Multiple
Number of Profiles=7
Profile Names=10-year,25-year,50-year,1pct_min,100-year,1pct_plu,500-year
River Rch & RM= StreamM031,Reach-1,2818
     390     606     795     507    1012    2018    1616
Boundary for River Rch & Prof#=StreamM031,Reach-1,1
Up Type=0
Dn Type=3
Dn Slope=0.005
Boundary for River Rch & Prof#=StreamM031,Reach-1,2
Up Type=0
Dn Type=3
Dn Slope=0.005
Boundary for River Rch & Prof#=StreamM031,Reach-1,3
Up Type=0
Dn Type=3
Dn Slope=0.005
Boundary for River Rch & Prof#=StreamM031,Reach-1,4
Up Type=0
Dn Type=3
Dn Slope=0.005
Boundary for River Rch & Prof#=StreamM031,Reach-1,5
Up Type=0
Dn Type=3
Dn Slope=0.005
Boundary for River Rch & Prof#=StreamM031,Reach-1,6
Up Type=0
Dn Type=3
Dn Slope=0.005
Boundary for River Rch & Prof#=StreamM031,Reach-1,7
Up Type=0
Dn Type=3
Dn Slope=0.005

--- StreamM031.g01 (geometry) ---

Geom Title=Existing Conditions
Program Version=4.10

River Reach=StreamM031      ,Reach-1
Reach XY= 30
        2485325.       13838325.      2485419.73     13838329.99
      2485491.49     13838492.05      2485584.66     13838535.79
      2485716.86     13838668.94      2485729.25     13838723.26
      2485774.92     13838790.39      2485725.39     13838890.27
      2485725.93     13838964.53      2485744.57      13838995.2
      2485818.93     13839066.85      2485884.67      13839085.8
      2485972.58     13839169.46      2486073.41     13839178.83
      2486122.83     13839218.86      2486181.05     13839233.16
      2486269.26      13839316.7      2486319.38     13839330.62
      2486341.73     13839391.48      2486564.22     13839615.32
      2486580.87     13839677.28      2486666.84     13839768.95
      2486731.12     13839927.18      2486771.17     13839976.59
      2486780.54     13840077.42      2486866.86     13840168.96
      2486879.44     13840223.35      2486917.15     13840271.72
        2486879.     13840326.36        2486875.       13840375.

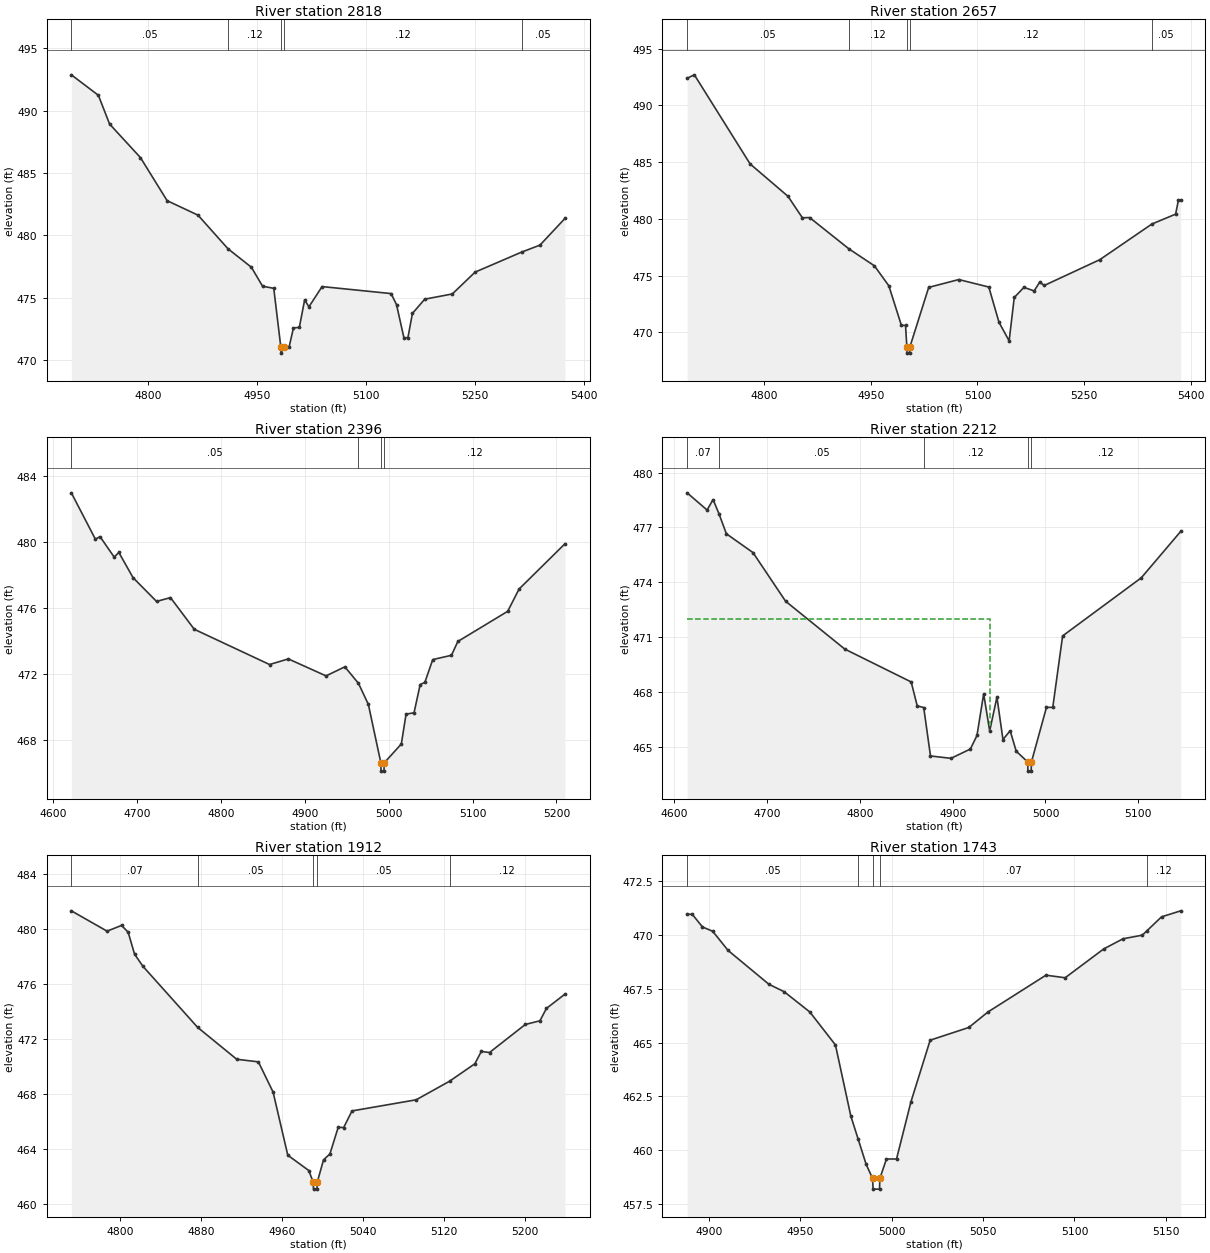
Type RM Length L Ch R = 1 ,2818    ,161,161,161
BEGIN DESCRIPTION:
H21249
END DESCRIPTION:
XS GIS Cut Line= 3
      2485157.99     13838489.27      2485451.65     13838308.14
      2485756.34     13838170.89
#Sta/Elev= 30
  4694.3  492.86  4731.5  491.22  4746.9  488.92  4789.4  486.23  4826.1  482.78
  4868.6  481.62  4909.8  478.93    4942  477.45  4957.4  475.93  4972.8  475.76
  4982.5  471.07  4982.8  470.57  4986.5  471.07    4994  471.08  4999.9  472.59
    5008  472.63  5015.3  474.83  5021.2  474.28  5039.3   475.9  5134.2  475.34
  5141.7  474.46  5151.9   471.8  5157.4  471.81  5163.6  473.75  5180.5  474.89
  5218.5  475.31  5249.9  477.06  5313.8  478.66  5339.1  479.22  5373.5  481.36
#Mann= 5 ,-1 , 0
  4694.3     .05       0  4909.8     .12       0  4982.5     .05       0
  4986.5     .12       0  5313.8     .05       0
Bank Sta=4982.5,4986.5
XS Rating Curve= 0 ,0
Exp/Cntr=0.3,0.1

Type RM Length L Ch R = 1 ,2657    ,261,261,261
BEGIN DESCRIPTION:
StreamM031 6.0
END DESCRIPTION:
XS GIS Cut Line= 3
      2485174.97     13838525.01        2485475.       13838475.
      2485775.01     13838224.99
#Sta/Elev= 30
  4691.4  492.39  4701.6  492.69  4780.1  484.84  4833.4  481.99  4853.6   480.1
  4863.8  480.12  4919.2  477.36    4955  475.87  4975.3  474.11    4993  470.62
  4998.8  470.62  5000.7  468.68    5001  468.18  5004.5  468.18  5004.7  468.68
  5031.4  473.97  5073.7  474.66    5116     474  5130.3   470.9  5144.6  469.26
  5151.8  473.08  5165.4  473.97  5179.8  473.66  5187.6  474.43  5194.1  474.14
  5272.2  476.41  5345.5  479.55  5378.9  480.42  5382.8  481.64  5386.1  481.64
#Mann= 5 ,-1 , 0
  4691.4     .05       0  4919.2     .12       0  5000.7     .05       0
  5004.7     .12       0  5345.5     .05       0
Bank Sta=5000.7,5004.7
XS Rating Curve= 0 ,0
Exp/Cntr=0.3,0.1

Type RM Length L Ch R = 1 ,2396    ,184,184,184
BEGIN DESCRIPTION:
H21248
END DESCRIPTION:
XS GIS Cut Line= 2
      2485339.12     13838795.05      2485866.14     13838534.29
#Sta/Elev= 30
  4622.1  482.98  4650.7  480.17  4656.3  480.32  4673.1  479.08  4678.7  479.36
  4695.6  477.83  4723.6  476.39  4740.2  476.62  4768.5   474.7  4858.2  472.56
  4880.6   472.9  4925.5  471.87  4947.9  472.42  4964.1  471.42  4975.9  470.14
  4990.8  466.59    4991  466.09  4994.5  466.09  4994.8  466.59  5015.2  467.74
  5020.8  469.55  5030.3  469.63  5037.6  471.34  5043.2  471.48  5052.6  472.86
  5074.9  473.12  5082.5  473.96  5141.9  475.79  5155.4  477.14  5210.1  479.89
#Mann= 4 ,-1 , 0
  4622.1     .05       0  4964.1     .12       0  4990.8     .05       0
  4994.8     .12       0
Bank Sta=4990.8,4994.8
XS Rating Curve= 0 ,0
Exp/Cntr=0.3,0.1

Type RM Length L Ch R = 1 ,2212    ,300,300,300
BEGIN DESCRIPTION:
StreamM031 5.0
END DESCRIPTION:
XS GIS Cut Line= 3
      2485524.99     13839075.02        2485775.       13838775.
      2485875.03     13838674.97
#Sta/Elev= 30
  4613.8  478.89  4635.3  477.95  4641.8  478.52  4648.1  477.75  4656.1  476.65
  4684.8  475.62  4719.9  472.96  4783.7  470.34  4855.3  468.54  4861.8  467.23
  4868.8  467.14  4876.1  464.49  4898.2  464.36  4919.1  464.87  4926.2  465.61
  4933.4  467.89  4939.9  465.86  4947.7  467.71  4954.2  465.39    4962  465.87
  4968.5  464.75  4980.9  464.16  4981.1  463.66  4984.6  463.66  4984.9  464.16
  5001.1  467.15  5007.9  467.15  5018.5  471.06  5103.3  474.24  5145.8  476.78
#Mann= 5 ,-1 , 0
  4613.8     .07       0  4648.1     .05       0  4868.8     .12       0
  4980.9     .05       0  4984.9     .12       0
#XS Ineff= 2 , 0
       0    4940     472               0
Permanent Ineff=
       F       F
Bank Sta=4980.9,4984.9
XS Rating Curve= 0 ,0
Exp/Cntr=0.3,0.1

Type RM Length L Ch R = 1 ,1912    ,169,169,169
BEGIN DESCRIPTION:
H21247
END DESCRIPTION:
XS GIS Cut Line= 2
      2485635.53     13839234.22      2485933.63     13838848.61
#Sta/Elev= 30
  4751.9  481.34  4787.2  479.86  4801.5  480.28    4808  479.78  4814.3  478.19
  4822.5  477.31  4876.6  472.86  4915.2  470.54  4936.6  470.35  4951.1  468.15
  4965.6  463.56  4986.4  462.44  4990.7  461.59    4991  461.09  4994.5  461.09
  4994.7  461.59  5000.9  463.22  5007.2  463.65  5015.4  465.59  5020.8  465.57
    5029  466.78  5092.4  467.59  5125.3  468.94  5150.3  470.21  5156.7  471.11
  5164.8  471.03  5200.1  473.07  5214.6  473.34    5221  474.24  5239.3  475.28
#Mann= 5 ,-1 , 0
  4751.9     .07       0  4876.6     .05       0  4990.7     .05       0
  4994.7     .05       0  5125.3     .12       0
Bank Sta=4990.7,4994.7
XS Rating Curve= 0 ,0
Exp/Cntr=0.3,0.1

Type RM Length L Ch R = 1 ,1743    ,190,190,190
BEGIN DESCRIPTION:
StreamM031 4.0
END DESCRIPTION:
XS GIS Cut Line= 3
      2485874.99     13839225.02        2485925.       13839125.
      2485974.99     13838975.04
#Sta/Elev= 30
  4888.2  470.96    4891  470.96  4896.6  470.37  4902.2  470.17  4910.6  469.28
  4932.9  467.71  4941.3  467.36  4955.3  466.42  4969.3  464.89  4977.7  461.59
  4981.7  460.52  4986.1  459.34  4989.6  458.69  4989.9  458.19  4993.4  458.19
  4993.6  458.69  4997.2  459.59  5002.7  459.59  5010.6  462.25  5021.1  465.11
  5042.2   465.7  5052.7  466.42  5084.4  468.13  5094.9  468.01    5116  469.35
  5126.5  469.82  5137.1  469.99  5139.7   470.2  5147.6  470.84  5158.1  471.12
#Mann= 5 ,-1 , 0
  4888.2     .05       0  4981.7     .07       0  4989.6     .05       0
  4993.6     .07       0  5139.7     .12       0
Bank Sta=4989.6,4993.6
XS Rating Curve= 0 ,0
Exp/Cntr=0.3,0.1

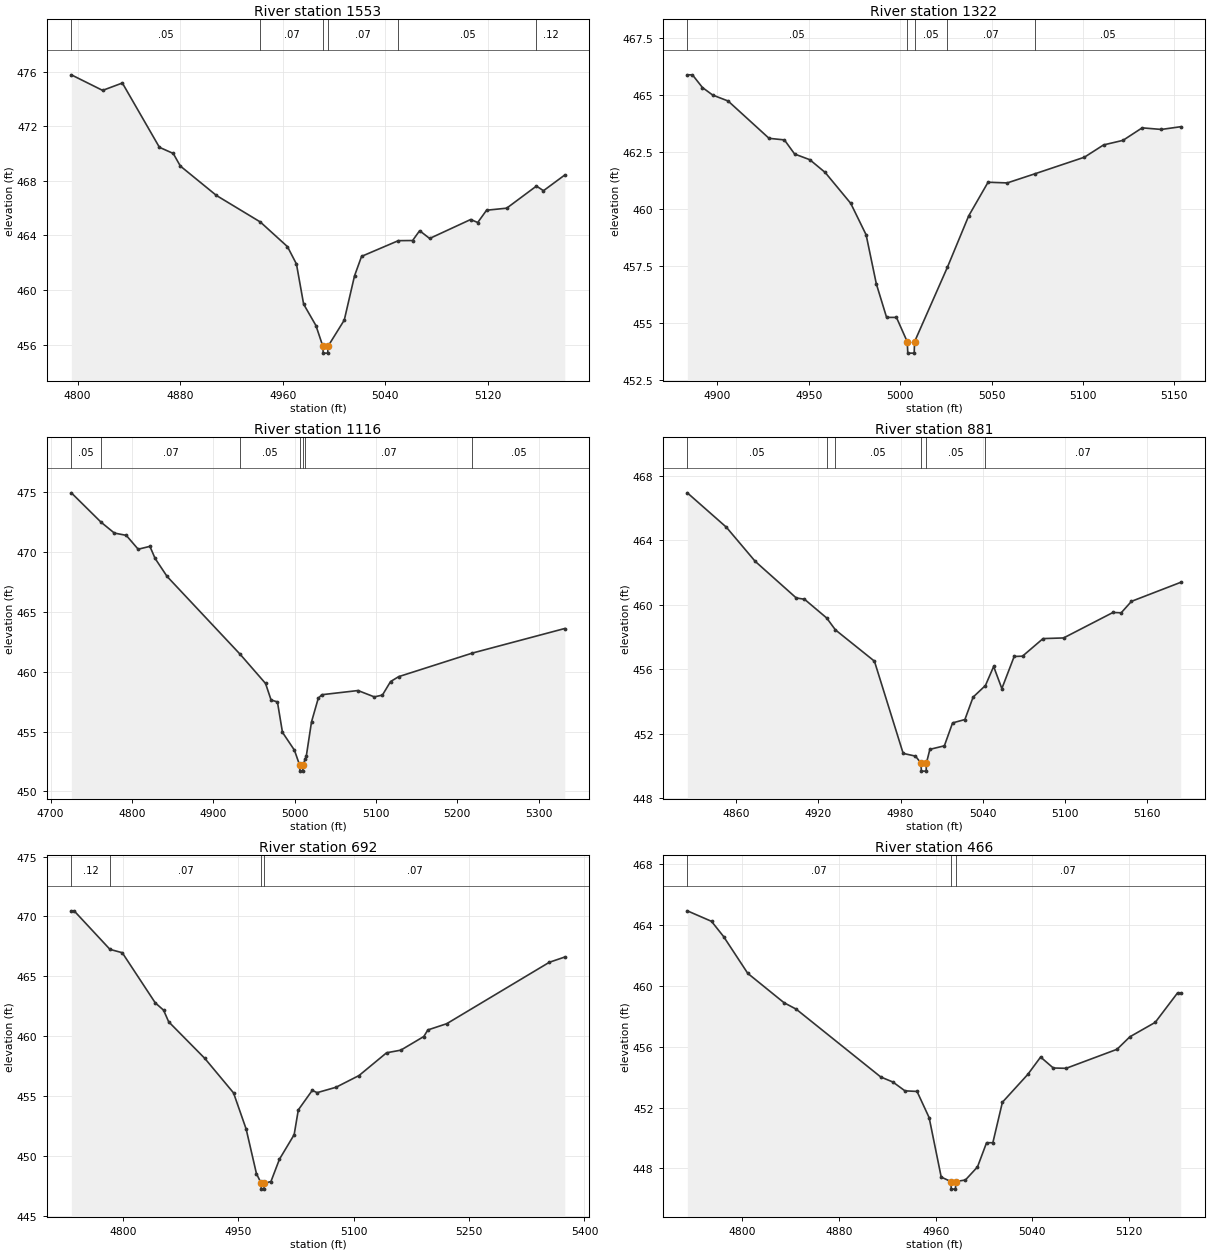
Type RM Length L Ch R = 1 ,1553    ,231,231,231
BEGIN DESCRIPTION:
H21246
END DESCRIPTION:
XS GIS Cut Line= 2
      2486003.33     13839376.95      2486169.97       13839030.
#Sta/Elev= 30
  4795.1  475.77  4819.5  474.63  4834.9  475.17  4863.8  470.46  4874.6  470.01
  4880.1  469.09  4908.3  466.93  4942.5  464.99  4963.7  463.18  4970.7  461.91
  4976.3  458.97  4985.9   457.4  4991.3  455.88  4991.6  455.38  4995.1  455.38
  4995.3  455.88    5008   457.8    5016  461.04  5021.5  462.47  5050.2  463.62
  5061.3  463.63  5066.8  464.35  5074.6  463.78  5106.6  465.17  5112.1  464.95
    5119  465.85  5134.7     466  5157.9  467.62  5163.4  467.28    5180  468.43
#Mann= 6 ,-1 , 0
  4795.1     .05       0  4942.5     .07       0  4991.3     .05       0
  4995.3     .07       0  5050.2     .05       0  5157.9     .12       0
Bank Sta=4991.3,4995.3
XS Rating Curve= 0 ,0
Exp/Cntr=0.3,0.1

Type RM Length L Ch R = 1 ,1322    ,206,206,206
BEGIN DESCRIPTION:
StreamM031 3.0
END DESCRIPTION:
XS GIS Cut Line= 3
      2486175.03     13839374.98        2486275.       13839325.
      2486325.01     13839174.98
#Sta/Elev= 30
  4883.6  465.89  4886.4  465.89  4891.9  465.33  4897.5     465  4905.9  464.74
  4928.3   463.1  4936.7  463.03  4942.3  462.41  4950.6  462.16    4959   461.6
    4973  460.24  4981.4  458.86    4987   456.7  4992.6  455.23    4998  455.23
  5003.9  454.16  5004.2  453.66  5007.7  453.66  5007.9  454.16  5025.9  457.44
  5037.5  459.69  5048.1  461.17  5058.6  461.14  5073.7  461.54  5100.8  462.27
  5111.3  462.81  5121.9  463.01  5132.4  463.56  5142.9  463.49  5153.5  463.61
#Mann= 5 ,-1 , 0
  4883.6     .05       0  5003.9     .05       0  5007.9     .05       0
  5025.9     .07       0  5073.7     .05       0
Bank Sta=5003.9,5007.9
XS Rating Curve= 0 ,0
Exp/Cntr=0.3,0.1

Type RM Length L Ch R = 1 ,1116    ,235,235,235
BEGIN DESCRIPTION:
H21245
END DESCRIPTION:
XS GIS Cut Line= 3
      2486187.22     13839621.21        2486437.     13839437.31
      2486428.77      13839140.9
#Sta/Elev= 30
  4725.4  474.94  4761.9  472.49  4778.3  471.58  4792.9  471.39  4807.6  470.23
    4822  470.47  4828.4  469.46  4843.1  467.96  4933.2  461.44  4964.2  459.02
    4971  457.64  4978.8  457.48    4985  454.94  4999.7  453.45  5006.1   452.2
  5006.4   451.7  5009.9   451.7  5010.1   452.2  5012.8  452.68  5014.3  452.95
  5020.7  455.81    5029  457.78  5033.3  458.08  5077.9  458.43  5097.9   457.9
  5107.9  458.05  5117.9  459.18  5127.9  459.59  5218.6  461.56  5332.1  463.61
#Mann= 7 ,-1 , 0
  4725.4     .05       0  4761.9     .07       0  4933.2     .05       0
  5006.1     .05       0  5010.1     .05       0  5012.8     .07       0
  5218.6     .05       0
Bank Sta=5006.1,5010.1
XS Rating Curve= 0 ,0
Exp/Cntr=0.3,0.1

Type RM Length L Ch R = 1 ,881     ,189,189,189
BEGIN DESCRIPTION:
StreamM031 2.0
END DESCRIPTION:
XS GIS Cut Line= 3
      2486425.02     13839724.99        2486575.       13839625.
      2486724.97     13839525.02
#Sta/Elev= 30
  4824.2  466.94  4852.7  464.81  4873.8  462.69  4903.8  460.42  4909.8  460.34
    4926  459.18  4932.4  458.44  4960.9   456.5  4981.9  450.78  4990.9  450.61
  4994.9  450.18  4995.2  449.68  4998.7  449.68  4998.9  450.18  5001.4  451.03
    5012  451.25    5018  452.67    5027  452.88    5033  454.27    5042  454.99
    5048  456.17    5054   454.8    5063  456.79  5069.1  456.81  5084.1   457.9
  5099.1  457.94  5135.2  459.52  5141.2   459.5  5148.7  460.21  5184.7  461.39
#Mann= 6 ,-1 , 0
  4824.2     .05       0    4926     .07       0  4932.4     .05       0
  4994.9     .05       0  4998.9     .05       0    5042     .07       0
Bank Sta=4994.9,4998.9
XS Rating Curve= 0 ,0
Exp/Cntr=0.3,0.1

Type RM Length L Ch R = 1 ,692     ,226,226,226
BEGIN DESCRIPTION:
H21244
END DESCRIPTION:
XS GIS Cut Line= 2
      2486423.32     13839876.45       2487020.8     13839643.48
#Sta/Elev= 30
  4733.1  470.47  4736.7  470.47  4783.3  467.25  4799.3  466.97  4842.2  462.78
    4853  462.17  4859.6   461.2  4906.6  458.14  4943.9  455.26  4960.3  452.24
  4973.7  448.51  4979.8  447.72    4980  447.22  4983.5  447.22  4983.8  447.72
  4992.5  447.85  5003.6  449.72  5022.7  451.77  5028.1  453.84  5046.2  455.47
  5052.6  455.28  5077.1  455.73    5107  456.71  5142.8  458.61  5161.3  458.83
  5191.2  459.97  5196.5  460.52    5221  461.04  5354.3  466.17  5374.4  466.61
#Mann= 4 ,-1 , 0
  4733.1     .12       0  4783.3     .07       0  4979.8     .05       0
  4983.8     .07       0
Bank Sta=4979.8,4983.8
XS Rating Curve= 0 ,0
Exp/Cntr=0.3,0.1

Type RM Length L Ch R = 1 ,466     ,181,181,181
BEGIN DESCRIPTION:
StreamM031 1.0
END DESCRIPTION:
XS GIS Cut Line= 3
      2486524.98       13839975.        2486775.       13839975.
      2486924.97     13839925.01
#Sta/Elev= 30
  4754.6  464.93  4774.6  464.24  4784.6  463.24  4804.6  460.82  4834.6  458.89
  4844.6  458.47  4914.6  454.01  4924.6  453.68  4934.6   453.1  4944.6  453.06
  4954.6  451.34  4964.6  447.43  4972.6  447.14  4972.9  446.64  4976.4  446.64
  4976.6  447.14  4984.6  447.24  4994.6   448.1  5002.1  449.69  5007.3  449.69
  5015.2  452.35  5036.2  454.18  5046.8  455.32  5057.3   454.6  5067.9  454.58
    5110  455.83  5120.6  456.65  5141.6   457.6  5160.1  459.54  5162.7  459.54
#Mann= 3 ,-1 , 0
  4754.6     .07       0  4972.6     .05       0  4976.6     .07       0
Bank Sta=4972.6,4976.6
XS Rating Curve= 0 ,0
Exp/Cntr=0.3,0.1

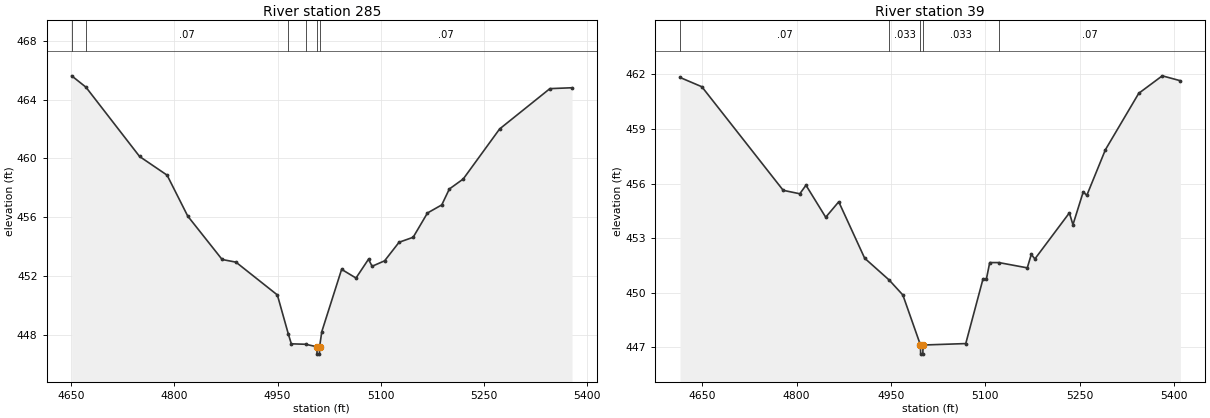
Type RM Length L Ch R = 1 ,285     ,246,246,246
BEGIN DESCRIPTION:
H21243
END DESCRIPTION:
XS GIS Cut Line= 3
      2486486.41     13840137.21      2486780.09     13840148.19
      2487197.24     13840030.18
#Sta/Elev= 30
  4650.8  465.61  4671.5  464.84  4749.5  460.13  4789.5  458.86  4819.5  456.08
  4869.5  453.13  4889.6  452.95  4949.8  450.72  4965.9  448.04  4970.1   447.4
    4991  447.37  5007.2   447.2  5007.5   446.7    5011   446.7  5011.2   447.2
  5014.4  448.23  5043.2  452.46  5064.1  451.87  5082.3  453.15  5087.5  452.67
  5105.7  453.04  5126.7   454.3  5147.2  454.64    5168  456.29  5188.8  456.84
  5199.8  457.92    5220   458.6  5272.9     462    5346  464.74  5378.2   464.8
#Mann= 6 ,-1 , 0
  4650.8     .12       0  4671.5     .07       0  4965.9    .033       0
    4991     .07       0  5007.2     .05       0  5011.2     .07       0
Bank Sta=5007.2,5011.2
XS Rating Curve= 0 ,0
Exp/Cntr=0.3,0.1

Type RM Length L Ch R = 1 ,39      ,0,0,0
BEGIN DESCRIPTION:
H21242
END DESCRIPTION:
XS GIS Cut Line= 4
      2486500.15     13840260.73      2486810.28     13840337.57
      2486974.96     13840334.83      2487250.52     13840190.23
#Sta/Elev= 30
  4614.6  461.83  4649.3  461.32  4778.6  455.63    4805  455.44  4814.8  455.91
  4846.2  454.15  4866.9     455  4908.1   451.9  4947.1   450.7  4968.8  449.88
  4996.8  447.13  4997.1  446.63  5000.6  446.63  5000.8  447.13  5068.8  447.21
  5096.3  450.77  5101.7  450.77  5106.9  451.66  5121.5  451.66  5166.6  451.37
    5173  452.11  5178.7  451.86  5233.5  454.39  5239.2  453.74  5255.6  455.55
  5261.2  455.35  5290.8  457.86  5343.8  460.96  5381.2  461.92    5410  461.65
#Mann= 5 ,-1 , 0
  4614.6     .07       0  4947.1    .033       0  4996.8    .033       0
  5000.8    .033       0  5121.5     .07       0
Bank Sta=4996.8,5000.8
XS Rating Curve= 0 ,0
Exp/Cntr=0.3,0.1

Chan Stop Cuts=-1
Use User Specified Reach Order=0
Composite Channel Slope=5