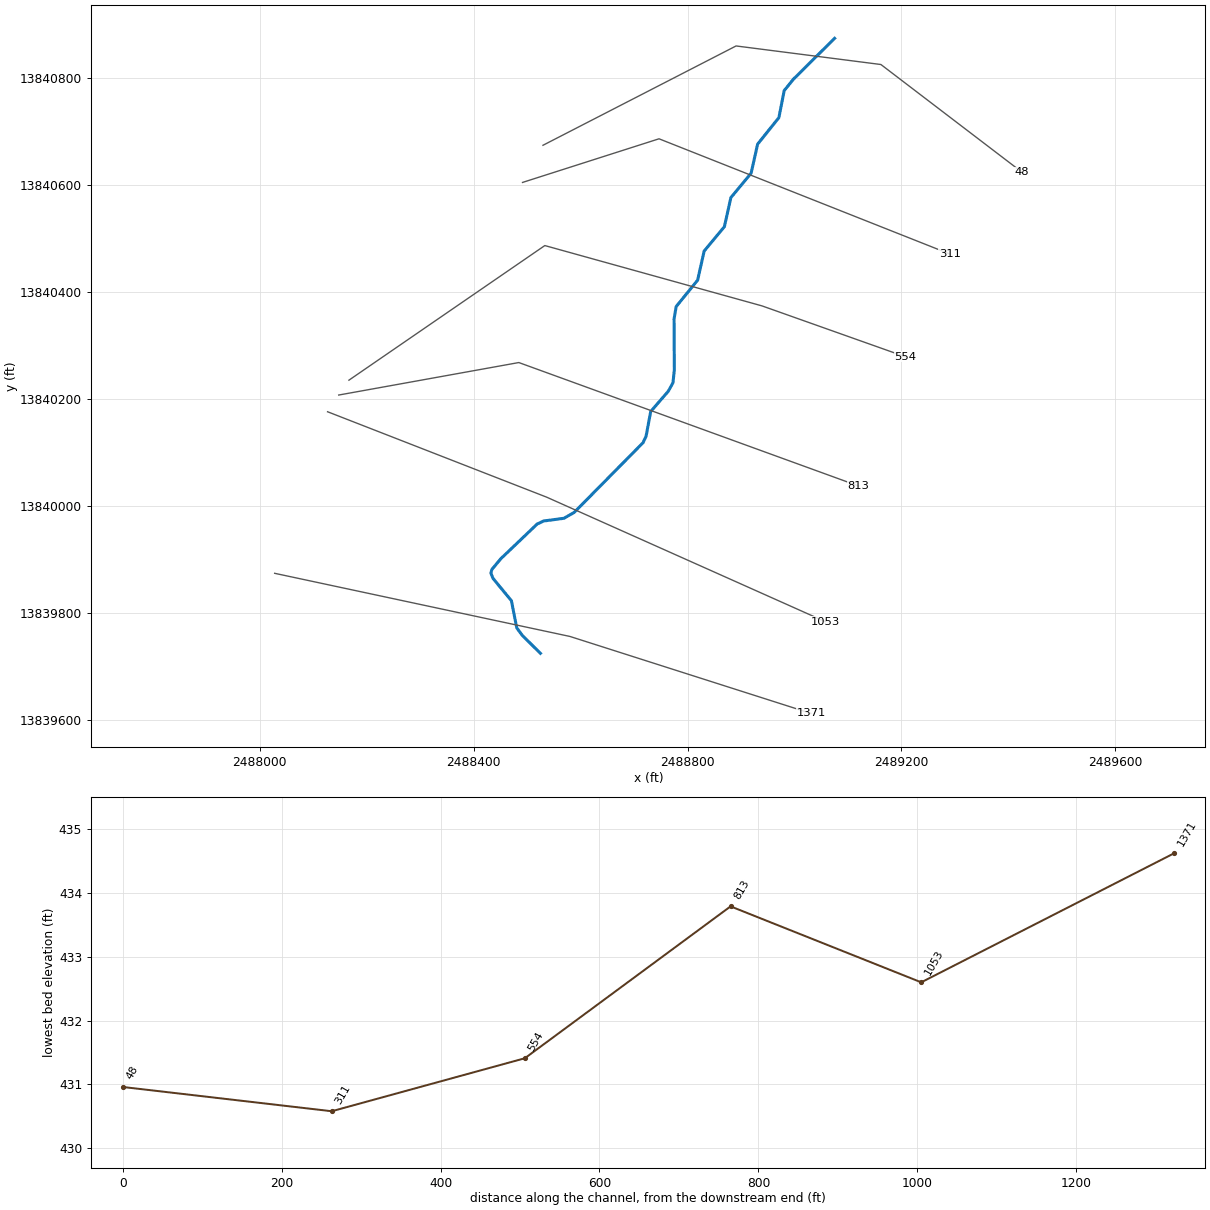
--- StreamM032.prj (project) ---

Proj Title=StreamM032 Base Level Engineering
Current Plan=p01
Default Exp/Contr=0.3,0.1
English Units
Geom File=g01
Flow File=f01
Plan File=p01
BEGIN DESCRIPTION:
StreamM032
END DESCRIPTION:

--- StreamM032.p01 (plan) ---

Plan Title=Multiple Run
Short Identifier=Multiple
Geom File=g01
Flow File=f01
Subcritical Flow
K Sum by GR= 0
Std Step Tol= 0.01
Critical Tol= 0.01
Num of Std Step Trials= 20
Max Error Tol= 0.3
Flow Tol Ratio= 0.001
Split Flow NTrial= 30
Split Flow Tol= 0.02
Split Flow Ratio= 0.02
Log Output Level= 0
Friction Slope Method= 1
Unsteady Friction Slope Method= 2
Unsteady Bridges Friction Slope Method= 1
Parabolic Critical Depth
Global Vel Dist=  1 , 1 , 1
Global Log Level= 0
CheckData=True
Encroach Param= -1, 0, 0, 0
BEGIN DESCRIPTION:
Multiple Run
END DESCRIPTION:

--- StreamM032.f01 (steady flow) ---

Flow Title=Multiple
Number of Profiles=7
Profile Names=10-year,25-year,50-year,1pct_min,100-year,1pct_plu,500-year
River Rch & RM= StreamM032,Reach-1,1371
     617     989    1324     860    1716    3424    2850
Boundary for River Rch & Prof#=StreamM032,Reach-1,1
Up Type=0
Dn Type=3
Dn Slope=0.005
Boundary for River Rch & Prof#=StreamM032,Reach-1,2
Up Type=0
Dn Type=3
Dn Slope=0.005
Boundary for River Rch & Prof#=StreamM032,Reach-1,3
Up Type=0
Dn Type=3
Dn Slope=0.005
Boundary for River Rch & Prof#=StreamM032,Reach-1,4
Up Type=0
Dn Type=3
Dn Slope=0.005
Boundary for River Rch & Prof#=StreamM032,Reach-1,5
Up Type=0
Dn Type=3
Dn Slope=0.005
Boundary for River Rch & Prof#=StreamM032,Reach-1,6
Up Type=0
Dn Type=3
Dn Slope=0.005
Boundary for River Rch & Prof#=StreamM032,Reach-1,7
Up Type=0
Dn Type=3
Dn Slope=0.005

--- StreamM032.g01 (geometry) ---

Geom Title=Existing Conditions

River Reach=StreamM032,Reach-1
Reach XY= 30
      2488525.00     13839725.00      2488491.39     13839758.08
      2488480.64     13839772.65      2488470.66     13839823.42
      2488436.24     13839865.14      2488432.26     13839875.10
      2488434.09     13839881.75      2488450.69     13839901.75
      2488518.91     13839966.84      2488531.03     13839972.47
      2488568.95     13839977.53      2488588.21     13839988.63
      2488716.86     13840118.94      2488722.51     13840131.03
      2488731.14     13840177.17      2488764.20     13840215.33
      2488772.75     13840230.93      2488775.33     13840254.86
      2488774.81     13840350.08      2488778.76     13840373.44
      2488818.88     13840422.82      2488831.08     13840477.20
      2488868.92     13840522.80      2488881.08     13840577.20
      2488918.92     13840622.80      2488931.08     13840677.20
      2488970.82     13840726.73      2488980.79     13840777.32
      2488997.92     13840798.51      2489075.00     13840875.00

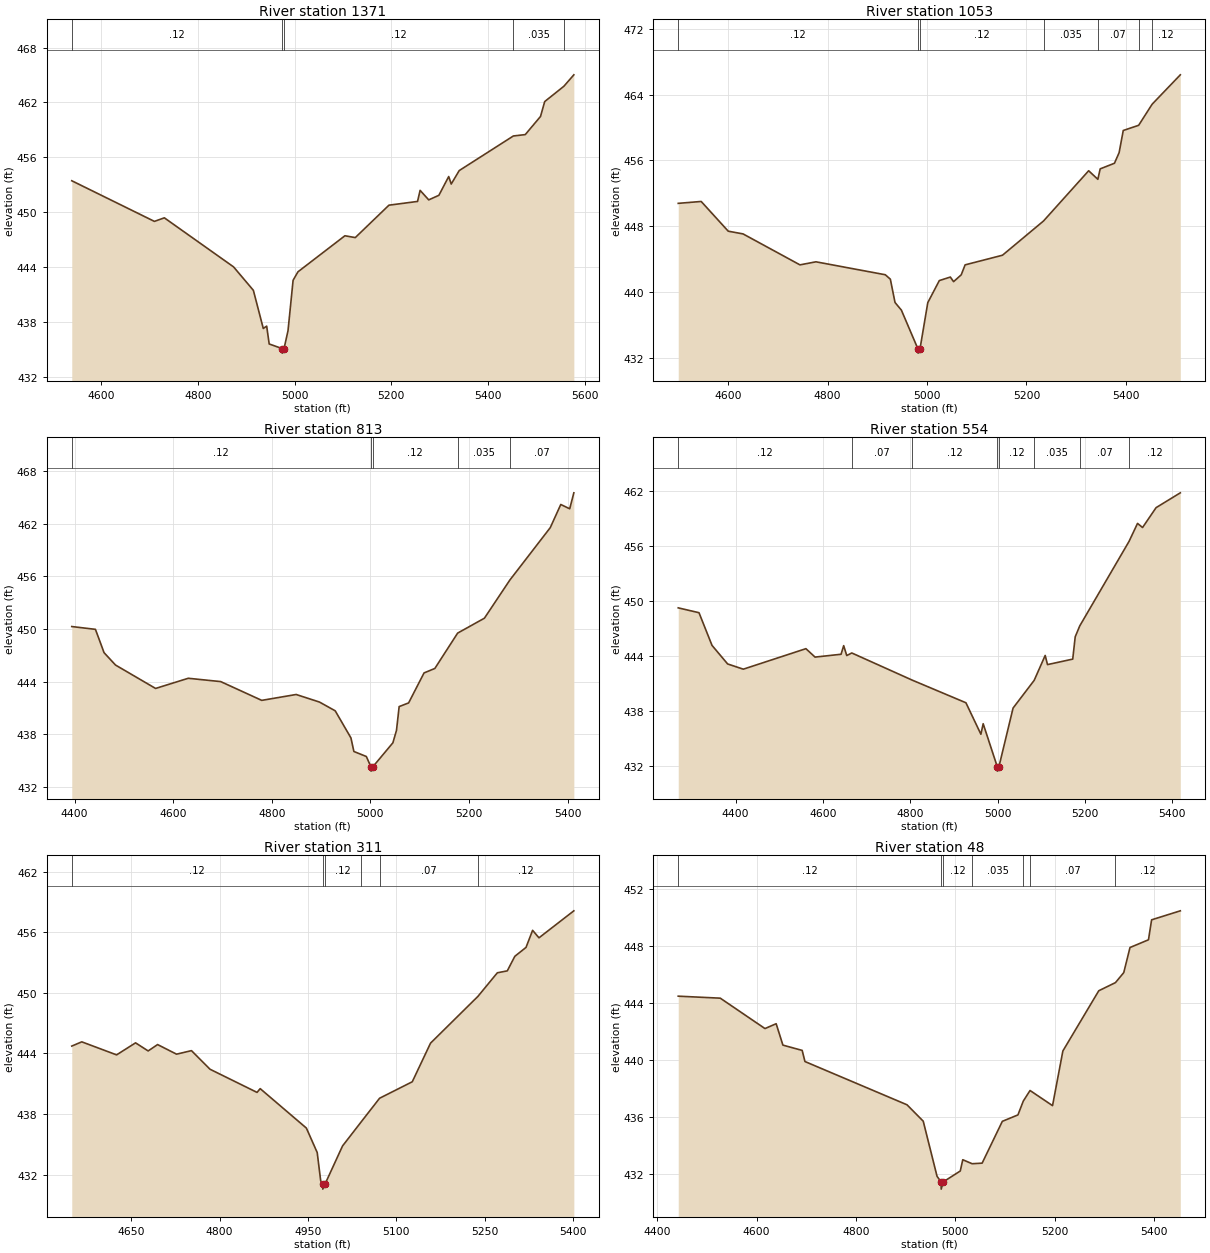
Type RM Length L Ch R = 1,1371,318,318,318
BEGIN DESCRIPTION:
H21255
END DESCRIPTION:
XS GIS Cut Line= 3
      2488027.97     13839874.65      2488580.02     13839756.60
      2489030.68     13839612.73
#Sta/Elev= 30
  4539.5  453.45  4710.3  449.01  4730.8  449.40  4873.9  444.04  4914.8  441.48
  4935.3  437.31  4942.3  437.57  4947.5  435.62  4974.2  435.12  4974.4  434.62
  4978.2  435.12  4986.4  437.07  4996.9  442.58  5006.9  443.50  5104.0  447.44
  5125.4  447.24  5195.0  450.78  5254.1  451.19  5259.4  452.40  5277.2  451.36
  5298.2  451.86  5318.5  453.91  5323.7  453.09  5340.2  454.56  5452.1  458.34
  5476.7  458.49  5508.2  460.47  5516.9  462.10  5556.5  463.77  5577.1  465.02
#Mann=5,-1,0
  4539.5    0.12       0  4974.2    0.05       0  4978.2    0.12       0
  5452.1   0.035       0  5556.5    0.12       0
Bank Sta=4974.2,4978.2
Exp/Cntr=0.3,0.1

Type RM Length L Ch R = 1,1053,240,240,240
BEGIN DESCRIPTION:
H21254
END DESCRIPTION:
XS GIS Cut Line= 3
      2488126.87     13840176.75      2488536.62     13840017.01
      2489057.44     13839784.38
#Sta/Elev= 30
  4499.3  450.79  4545.5  451.02  4599.9  447.41  4629.7  447.08  4744.2  443.32
  4776.4  443.69  4915.9  442.12  4926.1  441.58  4935.5  438.75  4948.3  437.82
  4981.7  433.10  4981.9  432.60  4985.7  433.10  5001.4  438.73  5024.6  441.41
  5046.8  441.84  5053.3  441.28  5068.7  442.11  5076.5  443.32  5151.7  444.49
  5234.3  448.65  5325.1  454.75  5343.6  453.71  5348.3  454.98  5377.0  455.66
  5386.4  456.95  5394.7  459.64  5425.7  460.27  5452.8  462.83  5509.5  466.40
#Mann=7,-1,0
  4499.3    0.12       0  4981.7    0.05       0  4985.7    0.12       0
  5234.3   0.035       0  5343.6    0.07       0  5425.7   0.035       0
  5452.8    0.12       0
Bank Sta=4981.7,4985.7
Exp/Cntr=0.3,0.1

Type RM Length L Ch R = 1,813,259,259,259
BEGIN DESCRIPTION:
H21253
END DESCRIPTION:
XS GIS Cut Line= 3
      2488147.73     13840207.99      2488484.53     13840268.75
      2489119.94     13840037.85
#Sta/Elev= 30
  4394.3  450.28  4442.3  449.96  4459.8  447.30  4483.0  445.89  4564.3  443.22
  4630.6  444.38  4696.4  444.00  4779.6  441.86  4849.4  442.53  4896.6  441.67
  4928.6  440.67  4960.5  437.58  4966.5  436.03  4991.7  435.46  5001.0  434.29
  5001.3  433.79  5005.0  434.29  5045.6  437.02  5052.9  438.44  5058.3  441.15
  5077.5  441.57  5108.8  444.99  5130.7  445.50  5176.9  449.53  5231.2  451.23
  5282.8  455.58  5364.8  461.56  5386.1  464.20  5404.2  463.71  5412.6  465.53
#Mann=5,-1,0
  4394.3    0.12       0  5001.0    0.05       0  5005.0    0.12       0
  5176.9   0.035       0  5282.8    0.07       0
Bank Sta=5001,5005
Exp/Cntr=0.3,0.1

Type RM Length L Ch R = 1,554,243,243,243
BEGIN DESCRIPTION:
H21252
END DESCRIPTION:
XS GIS Cut Line= 4
      2488166.83     13840235.77      2488533.14     13840487.50
      2488939.39     13840374.65      2489207.32     13840279.58
#Sta/Elev= 30
  4268.4  449.25  4316.0  448.72  4345.8  445.15  4381.6  443.12  4417.5  442.55
  4560.9  444.79  4581.9  443.87  4641.5  444.18  4647.5  445.12  4654.5  444.04
  4666.1  444.32  4804.7  441.35  4927.6  438.88  4961.9  435.44  4967.1  436.59
  4999.3  431.91  4999.6  431.41  5003.3  431.91  5035.6  438.30  5084.0  441.33
  5109.2  444.05  5114.5  443.05  5172.3  443.65  5178.0  446.09  5188.3  447.27
  5301.3  456.51  5320.8  458.48  5332.3  458.03  5363.3  460.20  5418.8  461.82
#Mann=8,-1,0
  4268.4    0.12       0  4666.1    0.07       0  4804.7    0.12       0
  4999.3    0.05       0  5003.3    0.12       0  5084.0   0.035       0
  5188.3    0.07       0  5301.3    0.12       0
Bank Sta=4999.3,5003.3
Exp/Cntr=0.3,0.1

Type RM Length L Ch R = 1,311,263,263,263
BEGIN DESCRIPTION:
H21251
END DESCRIPTION:
XS GIS Cut Line= 3
      2488491.47     13840605.55      2488746.69     13840687.15
      2489290.06     13840471.89
#Sta/Elev= 30
  4548.9  444.73  4565.9  445.15  4625.0  443.86  4657.2  445.05  4678.6  444.25
  4694.6  444.88  4726.8  443.93  4752.1  444.28  4783.6  442.44  4863.4  440.15
  4868.8  440.52  4947.2  436.62  4965.6  434.20  4971.5  431.41  4974.9  431.08
  4975.1  430.58  4978.9  431.08  5008.6  434.85  5040.1  437.22  5071.5  439.57
  5127.0  441.20  5158.0  445.02  5238.5  449.65  5271.4  451.98  5288.3  452.17
  5301.1  453.61  5320.1  454.49  5331.3  456.18  5342.1  455.44  5401.3  458.11
#Mann=6,-1,0
  4548.9    0.12       0  4974.9    0.05       0  4978.9    0.12       0
  5040.1   0.035       0  5071.5    0.07       0  5238.5    0.12       0
Bank Sta=4974.9,4978.9
Exp/Cntr=0.3,0.1

Type RM Length L Ch R = 1,48,0,0,0
BEGIN DESCRIPTION:
H21250
END DESCRIPTION:
XS GIS Cut Line= 4
      2488529.68     13840675.01      2488890.78     13840860.76
      2489161.62     13840826.04      2489425.52     13840624.64
#Sta/Elev= 30
  4442.2  444.48  4526.9  444.34  4616.9  442.21  4639.4  442.55  4653.0  441.05
  4691.8  440.68  4697.4  439.90  4902.9  436.87  4935.6  435.72  4963.4  431.86
  4971.5  431.46  4971.8  430.96  4975.5  431.46  5010.2  432.23  5015.2  433.02
  5034.0  432.74  5054.2  432.78  5094.9  435.71  5126.3  436.16  5137.1  437.13
  5150.7  437.87  5196.0  436.81  5216.8  440.64  5289.1  444.86  5322.7  445.43
  5339.4  446.13  5352.0  447.89  5389.2  448.43  5395.5  449.83  5453.3  450.46
#Mann=7,-1,0
  4442.2    0.12       0  4971.5    0.05       0  4975.5    0.12       0
  5034.0   0.035       0  5137.1     0.1       0  5150.7    0.07       0
  5322.7    0.12       0
Bank Sta=4971.5,4975.5
Exp/Cntr=0.3,0.1

Chan Stop Cuts=-1