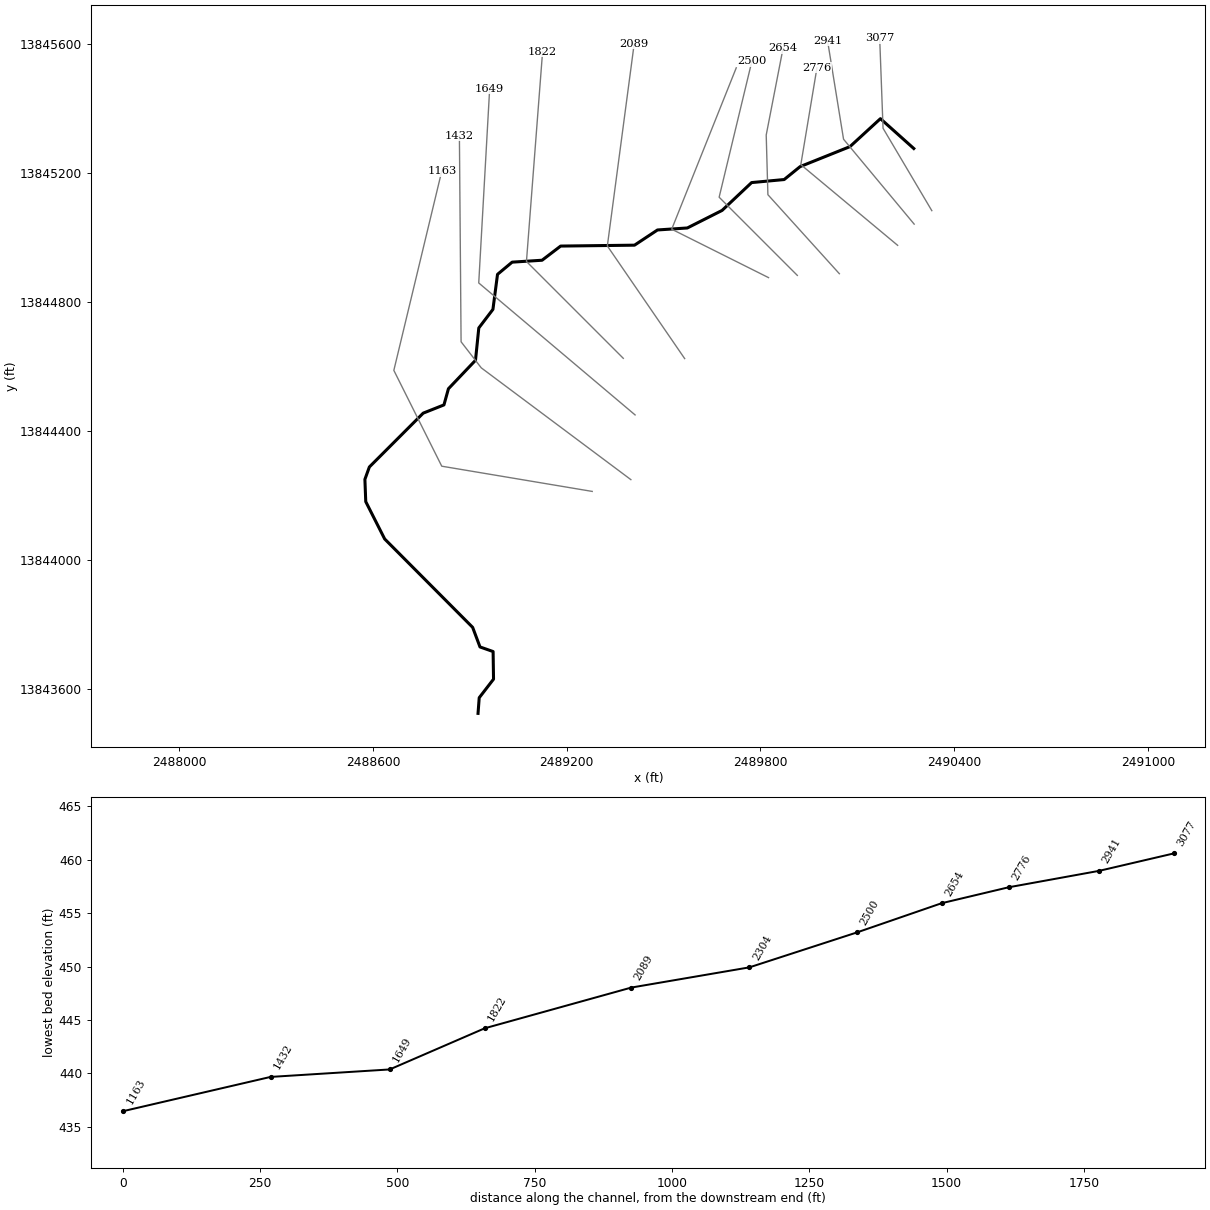
--- StreamM033.prj (project) ---

Proj Title=StreamM033 Base Level Engineering
Current Plan=p01
Default Exp/Contr=0.3,0.1
English Units
Geom File=g01
Flow File=f01
Plan File=p01
BEGIN DESCRIPTION:
StreamM033
END DESCRIPTION:

--- StreamM033.p01 (plan) ---

Plan Title=Multiple Run
Short Identifier=Multiple
Geom File=g01
Flow File=f01
Subcritical Flow
K Sum by GR= 0
Std Step Tol= 0.01
Critical Tol= 0.01
Num of Std Step Trials= 20
Max Error Tol= 0.3
Flow Tol Ratio= 0.001
Split Flow NTrial= 30
Split Flow Tol= 0.02
Split Flow Ratio= 0.02
Log Output Level= 0
Friction Slope Method= 1
Unsteady Friction Slope Method= 2
Unsteady Bridges Friction Slope Method= 1
Parabolic Critical Depth
Global Vel Dist=  1 , 1 , 1
Global Log Level= 0
CheckData=True
Encroach Param= -1, 0, 0, 0
BEGIN DESCRIPTION:
Multiple Run
END DESCRIPTION:

--- StreamM033.f01 (steady flow) ---

Flow Title=Multiple
Number of Profiles=7
Profile Names=10-year,25-year,50-year,1pct_min,100-year,1pct_plu,500-year
River Rch & RM= StreamM033,Reach-1,3077
     268     407     525     330     659    1315    1024
Boundary for River Rch & Prof#=StreamM033,Reach-1,1
Up Type=0
Dn Type=3
Dn Slope=0.005
Boundary for River Rch & Prof#=StreamM033,Reach-1,2
Up Type=0
Dn Type=3
Dn Slope=0.005
Boundary for River Rch & Prof#=StreamM033,Reach-1,3
Up Type=0
Dn Type=3
Dn Slope=0.005
Boundary for River Rch & Prof#=StreamM033,Reach-1,4
Up Type=0
Dn Type=3
Dn Slope=0.005
Boundary for River Rch & Prof#=StreamM033,Reach-1,5
Up Type=0
Dn Type=3
Dn Slope=0.005
Boundary for River Rch & Prof#=StreamM033,Reach-1,6
Up Type=0
Dn Type=3
Dn Slope=0.005
Boundary for River Rch & Prof#=StreamM033,Reach-1,7
Up Type=0
Dn Type=3
Dn Slope=0.005

--- StreamM033.g01 (geometry) ---

Geom Title=Existing Conditions

River Reach=StreamM033,Reach-1
Reach XY= 30
      2490275.00     13845275.00      2490171.67     13845367.48
      2490077.30     13845280.86      2489922.82     13845218.88
      2489873.41     13845178.83      2489772.58     13845169.46
      2489681.05     13845083.16      2489573.42     13845028.83
      2489480.98     13845022.64      2489409.78     13844975.52
      2489180.94     13844972.74      2489123.40     13844928.86
      2489030.69     13844922.93      2488985.36     13844885.16
      2488971.14     13844776.60      2488927.36     13844719.02
      2488917.12     13844618.83      2488833.30     13844530.74
      2488819.38     13844480.62      2488755.08     13844455.14
      2488588.34     13844288.30      2488574.50     13844250.04
      2488577.14     13844180.97      2488635.76     13844065.32
      2488908.30     13843791.49      2488931.07     13843730.80
      2488971.70     13843716.53      2488973.01     13843631.01
      2488928.65     13843573.50      2488925.00     13843525.00

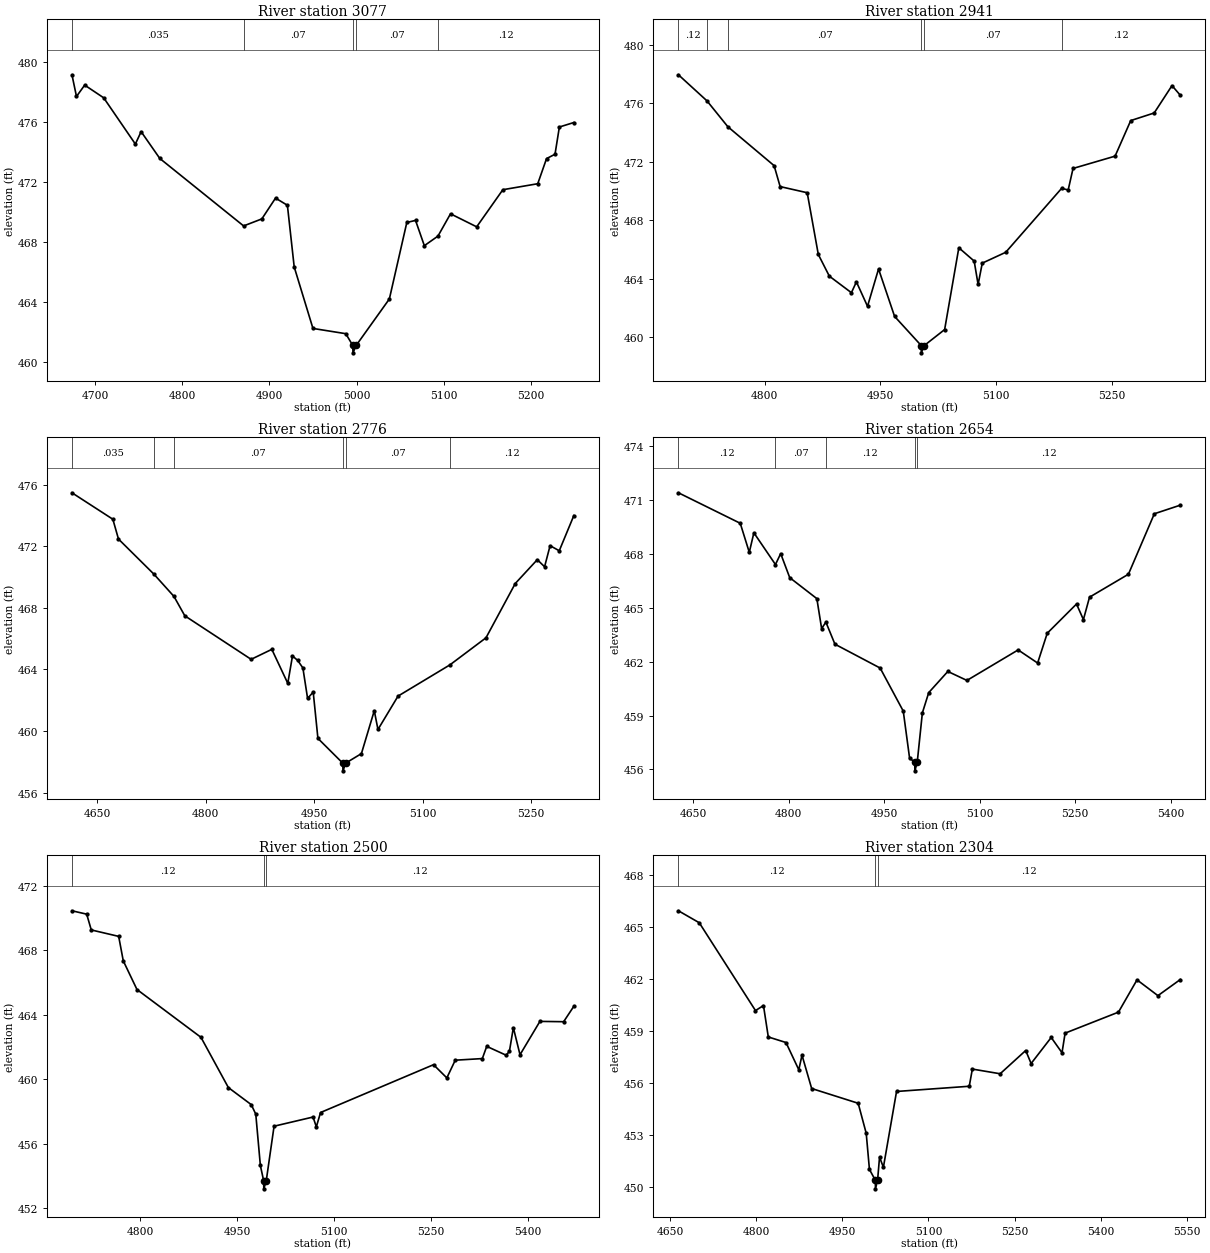
Type RM Length L Ch R = 1,3077,136,136,136
BEGIN DESCRIPTION:
H21263
END DESCRIPTION:
XS GIS Cut Line= 3
      2490330.82     13845082.46      2490179.78     13845337.66
      2490169.37     13845616.32
#Sta/Elev= 30
  4673.7  479.16  4678.9  477.71  4688.3  478.47  4710.1  477.62  4746.4  474.53
  4753.0  475.36  4774.4  473.57  4870.5  469.06  4891.4  469.53  4907.1  470.92
  4920.7  470.44  4928.5  466.32  4950.0  462.21  4987.6  461.86  4995.6  461.08
  4995.9  460.58  4999.6  461.08  5037.6  464.18  5057.6  469.29  5067.6  469.43
  5077.7  467.74  5093.3  468.38  5107.7  469.87  5137.7  469.00  5167.7  471.48
  5207.7  471.88  5217.8  473.56  5227.5  473.85  5232.5  475.67  5249.1  475.97
#Mann=5,-1,0
  4673.7   0.035       0  4870.5    0.07       0  4995.6    0.05       0
  4999.6    0.07       0  5093.3    0.12       0
Bank Sta=4995.6,4999.6
Exp/Cntr=0.3,0.1

Type RM Length L Ch R = 1,2941,165,165,165
BEGIN DESCRIPTION:
H21262
END DESCRIPTION:
XS GIS Cut Line= 3
      2490276.14     13845040.77      2490057.39     13845303.80
      2490007.91     13845608.50
#Sta/Elev= 30
  4688.1  477.95  4725.1  476.17  4752.2  474.40  4812.2  471.74  4820.0  470.31
  4855.1  469.89  4869.5  465.67  4883.8  464.19  4912.4  463.06  4918.9  463.80
  4933.3  462.13  4947.6  464.68  4968.4  461.44  5002.9  459.45  5003.1  458.95
  5006.9  459.45  5033.3  460.54  5051.7  466.13  5071.6  465.22  5076.7  463.62
  5082.1  465.08  5112.5  465.82  5185.0  470.19  5193.5  470.08  5199.8  471.55
  5254.3  472.39  5274.6  474.82  5305.0  475.34  5328.1  477.21  5338.9  476.55
#Mann=6,-1,0
  4688.1    0.12       0  4725.1   0.035       0  4752.2    0.07       0
  5002.9    0.05       0  5006.9    0.07       0  5185.0    0.12       0
Bank Sta=5002.9,5006.9
Exp/Cntr=0.3,0.1

Type RM Length L Ch R = 1,2776,122,122,122
BEGIN DESCRIPTION:
StreamM033 3.0
END DESCRIPTION:
XS GIS Cut Line= 3
      2490224.99     13844975.01      2489925.00     13845225.00
      2489974.99     13845524.96
#Sta/Elev= 30
  4614.8  475.49  4671.4  473.77  4679.2  472.48  4728.2  470.20  4756.0  468.75
  4771.0  467.49  4862.8  464.66  4891.4  465.31  4913.5  463.10  4920.0  464.88
  4927.2  464.59  4934.4  464.10  4940.9  462.12  4948.7  462.53  4955.2  459.52
  4989.6  457.91  4989.9  457.41  4993.6  457.91  5015.4  458.53  5033.2  461.32
  5038.3  460.10  5066.1  462.27  5137.9  464.30  5187.8  466.06  5228.3  469.59
  5258.8  471.14  5268.9  470.68  5276.5  472.05  5289.2  471.72  5309.4  474.01
#Mann=6,-1,0
  4614.8   0.035       0  4728.2    0.12       0  4756.0    0.07       0
  4989.6    0.05       0  4993.6    0.07       0  5137.9    0.12       0
Bank Sta=4989.6,4993.6
Exp/Cntr=0.3,0.1

Type RM Length L Ch R = 1,2654,154,154,154
BEGIN DESCRIPTION:
H21261
END DESCRIPTION:
XS GIS Cut Line= 4
      2490044.36     13844887.14      2489823.01     13845131.93
      2489817.80     13845316.82      2489869.88     13845585.02
#Sta/Elev= 30
  4626.8  471.42  4723.9  469.72  4738.1  468.10  4745.3  469.19  4779.2  467.42
  4787.4  468.03  4801.6  466.69  4844.2  465.52  4851.7  463.85  4858.4  464.21
  4872.6  462.98  4943.6  461.65  4979.9  459.25  4989.9  456.61  4997.9  456.42
  4998.2  455.92  5001.9  456.42  5009.9  459.15  5019.9  460.28  5049.9  461.46
  5079.9  460.96  5160.3  462.66  5190.9  461.93  5206.0  463.59  5252.0  465.22
  5262.8  464.35  5272.4  465.60  5333.5  466.88  5374.2  470.25  5415.0  470.73
#Mann=5,-1,0
  4626.8    0.12       0  4779.2    0.07       0  4858.4    0.12       0
  4997.9    0.05       0  5001.9    0.12       0
Bank Sta=4997.9,5001.9
Exp/Cntr=0.3,0.1

Type RM Length L Ch R = 1,2500,196,196,196
BEGIN DESCRIPTION:
H21260
END DESCRIPTION:
XS GIS Cut Line= 3
      2489914.18     13844881.91      2489671.97     13845124.11
      2489773.54     13845546.03
#Sta/Elev= 30
  4694.6  470.46  4717.4  470.25  4724.5  469.27  4766.9  468.87  4774.0  467.35
  4795.2  465.57  4894.2  462.60  4936.6  459.48  4972.0  458.42  4979.0  457.83
  4986.1  454.64  4991.2  453.69  4991.4  453.19  4995.2  453.69  5007.3  457.08
  5067.6  457.65  5072.7  457.04  5079.2  457.93  5254.0  460.90  5274.6  460.08
  5287.6  461.18  5329.5  461.28  5336.3  462.04  5366.3  461.49  5371.4  461.73
  5377.5  463.20  5387.8  461.52  5418.6  463.59  5455.3  463.57  5471.1  464.53
#Mann=3,-1,0
  4694.6    0.12       0  4991.2    0.05       0  4995.2    0.12       0
Bank Sta=4991.2,4995.2
Exp/Cntr=0.3,0.1

Type RM Length L Ch R = 1,2304,215,215,215
BEGIN DESCRIPTION:
StreamM033 2.0
END DESCRIPTION:
XS GIS Cut Line= 3
      2489825.00     13844875.00      2489525.00     13845025.00
      2489724.99     13845524.98
#Sta/Elev= 30
  4664.6  465.94  4700.9  465.25  4798.8  460.19  4812.7  460.48  4821.1  458.67
  4851.9  458.35  4874.2  456.78  4879.8  457.62  4896.6  455.70  4977.6  454.85
  4991.6  453.12  4997.2  451.04  5007.4  450.42  5007.7  449.92  5011.4  450.42
  5014.8  451.75  5021.5  451.16  5044.4  455.53  5171.0  455.83  5176.4  456.82
  5224.8  456.55  5269.3  457.89  5278.7  457.14  5313.7  458.64  5332.5  457.76
  5337.9  458.89  5430.8  460.10  5463.1  461.96  5499.5  461.05  5538.5  461.98
#Mann=3,-1,0
  4664.6    0.12       0  5007.4    0.05       0  5011.4    0.12       0
Bank Sta=5007.4,5011.4
Exp/Cntr=0.3,0.1

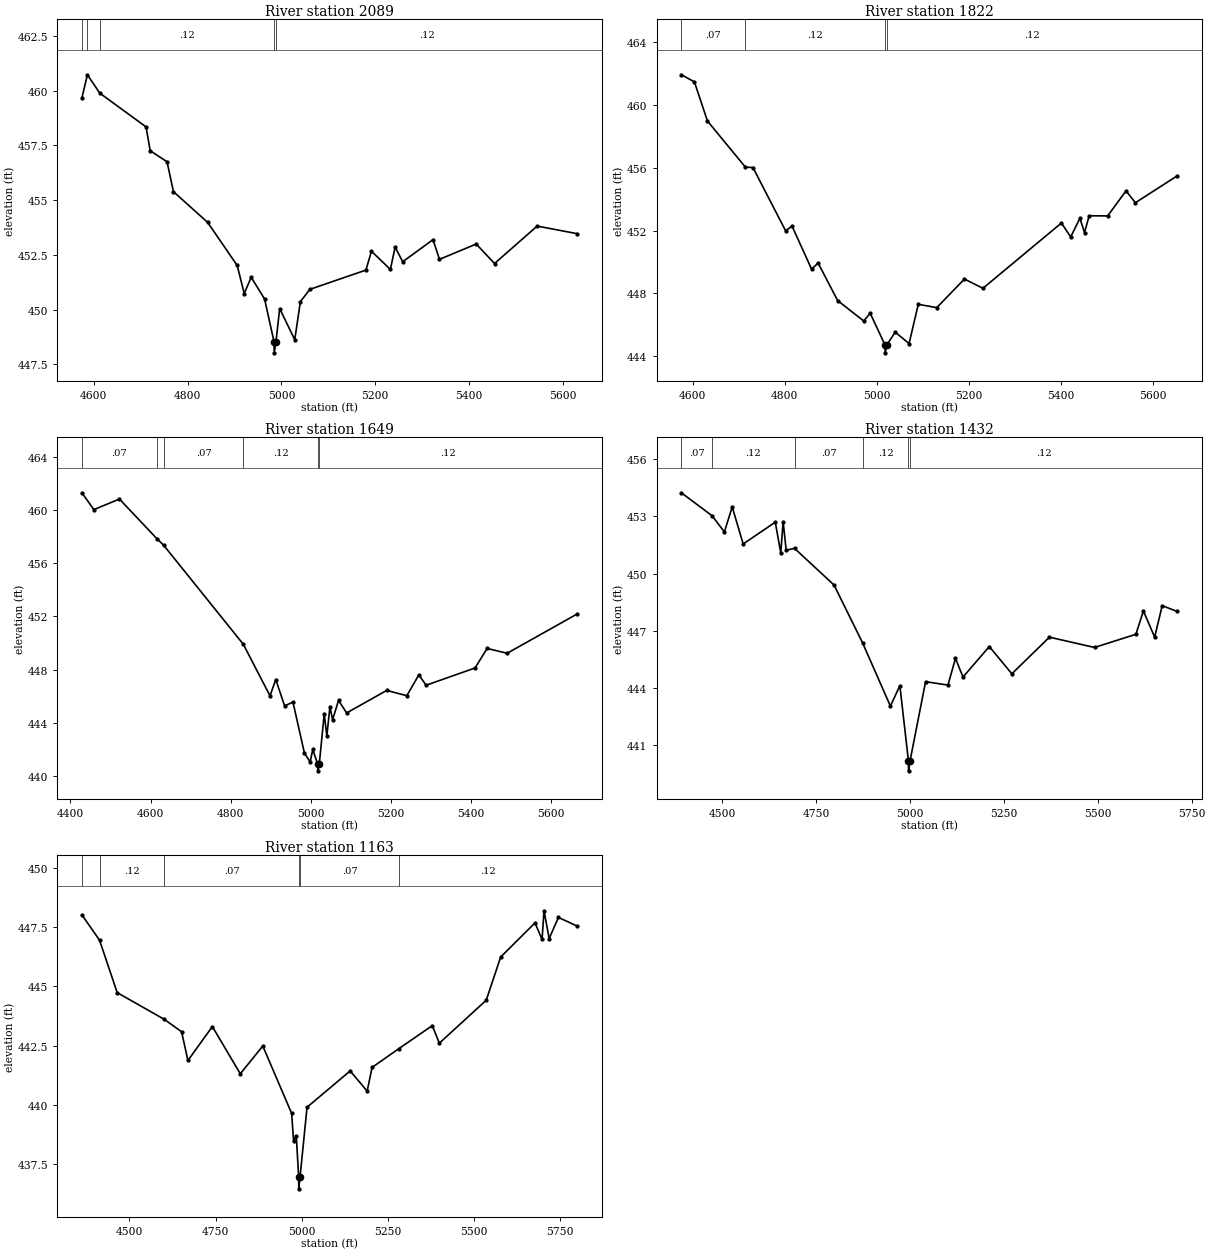
Type RM Length L Ch R = 1,2089,267,267,267
BEGIN DESCRIPTION:
H21259
END DESCRIPTION:
XS GIS Cut Line= 3
      2489565.17     13844624.15      2489325.62     13844973.07
      2489408.86     13845600.03
#Sta/Elev= 30
  4574.9  459.67  4586.7  460.73  4613.1  459.89  4711.6  458.35  4720.4  457.26
  4756.3  456.76  4770.0  455.39  4842.8  453.99  4905.8  452.02  4920.7  450.74
  4935.6  451.48  4964.1  450.49  4984.3  448.53  4984.6  448.03  4988.3  448.53
  4996.3  450.05  5028.4  448.63  5040.4  450.37  5060.6  450.93  5180.0  451.81
  5191.8  452.67  5232.1  451.84  5242.2  452.86  5258.3  452.19  5322.9  453.20
  5336.7  452.30  5415.0  453.00  5454.0  452.11  5544.8  453.82  5630.6  453.47
#Mann=5,-1,0
  4574.9    0.12       0  4586.7    0.07       0  4613.1    0.12       0
  4984.3    0.05       0  4988.3    0.12       0
Bank Sta=4984.3,4988.3
Exp/Cntr=0.3,0.1

Type RM Length L Ch R = 1,1822,173,173,173
BEGIN DESCRIPTION:
StreamM033 1.0
END DESCRIPTION:
XS GIS Cut Line= 3
      2489374.99     13844625.01      2489075.00     13844925.00
      2489125.00     13845575.03
#Sta/Elev= 30
  4575.7  461.93  4604.0  461.48  4632.3  458.99  4714.7  456.05  4731.2  456.02
  4802.0  452.00  4816.1  452.29  4858.5  449.55  4872.7  449.94  4915.1  447.55
  4971.7  446.25  4985.8  446.74  5018.0  444.72  5018.3  444.22  5022.0  444.72
  5040.1  445.54  5070.2  444.81  5090.2  447.31  5130.3  447.10  5190.5  448.92
  5230.6  448.33  5401.1  452.49  5421.2  451.60  5441.2  452.79  5451.3  451.88
  5461.3  452.95  5501.4  452.94  5541.5  454.54  5561.6  453.78  5651.9  455.48
#Mann=4,-1,0
  4575.7    0.07       0  4714.7    0.12       0  5018.0    0.05       0
  5022.0    0.12       0
Bank Sta=5018,5022
Exp/Cntr=0.3,0.1

Type RM Length L Ch R = 1,1649,217,217,217
BEGIN DESCRIPTION:
H21258
END DESCRIPTION:
XS GIS Cut Line= 3
      2489411.59     13844449.61      2488927.18     13844858.49
      2488961.03     13845460.03
#Sta/Elev= 30
  4428.7  461.32  4458.6  460.05  4522.4  460.85  4615.8  457.86  4632.4  457.38
  4831.6  449.90  4898.1  446.02  4912.4  447.25  4934.5  445.26  4955.3  445.55
  4983.9  441.71  4998.2  441.04  5004.8  441.98  5017.0  440.87  5017.3  440.37
  5021.0  440.87  5033.3  444.65  5039.9  443.00  5047.6  445.21  5054.2  444.22
  5069.1  445.68  5089.2  444.73  5189.3  446.43  5239.4  446.03  5269.4  447.60
  5287.6  446.82  5409.7  448.12  5439.7  449.59  5489.8  449.23  5665.1  452.20
#Mann=6,-1,0
  4428.7    0.07       0  4615.8    0.12       0  4632.4    0.07       0
  4831.6    0.12       0  5017.0    0.05       0  5021.0    0.12       0
Bank Sta=5017,5021
Exp/Cntr=0.3,0.1

Type RM Length L Ch R = 1,1432,269,269,269
BEGIN DESCRIPTION:
H21257
END DESCRIPTION:
XS GIS Cut Line= 4
      2489398.52     13844249.12      2488934.99     13844595.47
      2488872.49     13844676.20      2488867.28     13845314.25
#Sta/Elev= 30
  4392.0  454.23  4473.6  453.03  4506.5  452.18  4527.3  453.49  4556.5  451.55
  4641.9  452.69  4656.5  451.09  4662.8  452.72  4671.0  451.22  4693.1  451.32
  4798.3  449.40  4874.3  446.37  4948.3  443.06  4973.5  444.13  4996.4  440.17
  4996.6  439.67  5000.4  440.17  5041.9  444.34  5101.5  444.16  5121.5  445.56
  5141.5  444.58  5211.5  446.18  5271.5  444.75  5371.5  446.67  5491.5  446.13
  5601.6  446.82  5621.6  448.04  5651.6  446.67  5671.6  448.32  5710.8  448.02
#Mann=6,-1,0
  4392.0    0.07       0  4473.6    0.12       0  4693.1    0.07       0
  4874.3    0.12       0  4996.4    0.05       0  5000.4    0.12       0
Bank Sta=4996.4,5000.4
Exp/Cntr=0.3,0.1

Type RM Length L Ch R = 1,1163,0,0,0
BEGIN DESCRIPTION:
H21256
END DESCRIPTION:
XS GIS Cut Line= 4
      2489278.77     13844212.65      2488812.60     13844290.78
      2488664.16     13844587.66      2488812.60     13845204.86
#Sta/Elev= 30
  4361.7  448.01  4413.0  446.94  4464.3  444.73  4601.5  443.60  4651.3  443.08
  4669.7  441.87  4740.7  443.30  4821.8  441.31  4887.2  442.48  4971.0  439.64
  4976.6  438.47  4984.4  438.70  4991.4  436.96  4991.6  436.46  4995.4  436.96
  5015.7  439.90  5141.0  441.43  5190.3  440.58  5204.7  441.58  5282.5  442.37
  5379.5  443.34  5400.0  442.60  5536.2  444.41  5578.1  446.23  5677.8  447.67
  5698.4  446.97  5704.0  448.18  5719.0  447.01  5745.9  447.90  5801.1  447.53
#Mann=6,-1,0
  4361.7    0.07       0  4413.0    0.12       0  4601.5    0.07       0
  4991.4    0.05       0  4995.4    0.07       0  5282.5    0.12       0
Bank Sta=4991.4,4995.4
Exp/Cntr=0.3,0.1

Chan Stop Cuts=-1