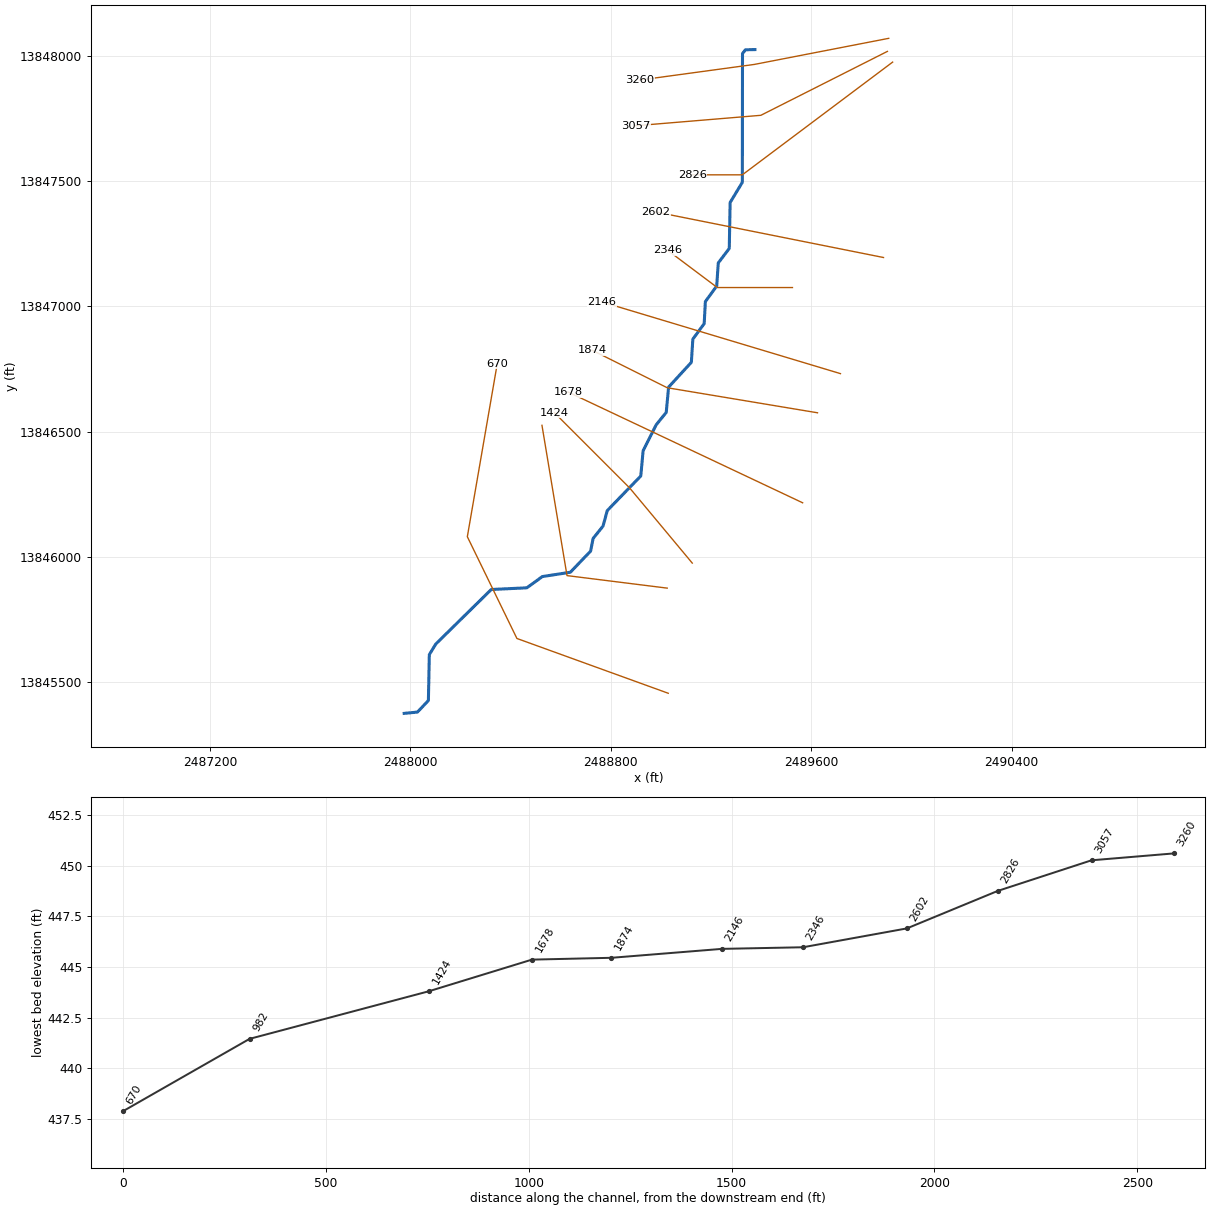
--- StreamM034.prj (project) ---

Proj Title=StreamM034 Base Level Engineering
Current Plan=p01
Default Exp/Contr=0.3,0.1
English Units
Geom File=g01
Flow File=f01
Plan File=p01
BEGIN DESCRIPTION:
StreamM034
END DESCRIPTION:

--- StreamM034.p01 (plan) ---

Plan Title=Multiple Run
Short Identifier=Multiple
Geom File=g01
Flow File=f01
Subcritical Flow
K Sum by GR= 0
Std Step Tol= 0.01
Critical Tol= 0.01
Num of Std Step Trials= 20
Max Error Tol= 0.3
Flow Tol Ratio= 0.001
Split Flow NTrial= 30
Split Flow Tol= 0.02
Split Flow Ratio= 0.02
Log Output Level= 0
Friction Slope Method= 1
Unsteady Friction Slope Method= 2
Unsteady Bridges Friction Slope Method= 1
Parabolic Critical Depth
Global Vel Dist=  1 , 1 , 1
Global Log Level= 0
CheckData=True
Encroach Param= -1, 0, 0, 0
BEGIN DESCRIPTION:
Multiple Run
END DESCRIPTION:

--- StreamM034.f01 (steady flow) ---

Flow Title=Multiple
Number of Profiles=7
Profile Names=10-year,25-year,50-year,1pct_min,100-year,1pct_plu,500-year
River Rch & RM= StreamM034,Reach-1,3260
     275     418     540     339     676    1349    1047
Boundary for River Rch & Prof#=StreamM034,Reach-1,1
Up Type=0
Dn Type=3
Dn Slope=0.005
Boundary for River Rch & Prof#=StreamM034,Reach-1,2
Up Type=0
Dn Type=3
Dn Slope=0.005
Boundary for River Rch & Prof#=StreamM034,Reach-1,3
Up Type=0
Dn Type=3
Dn Slope=0.005
Boundary for River Rch & Prof#=StreamM034,Reach-1,4
Up Type=0
Dn Type=3
Dn Slope=0.005
Boundary for River Rch & Prof#=StreamM034,Reach-1,5
Up Type=0
Dn Type=3
Dn Slope=0.005
Boundary for River Rch & Prof#=StreamM034,Reach-1,6
Up Type=0
Dn Type=3
Dn Slope=0.005
Boundary for River Rch & Prof#=StreamM034,Reach-1,7
Up Type=0
Dn Type=3
Dn Slope=0.005

--- StreamM034.g01 (geometry) ---

Geom Title=Existing Conditions

River Reach=StreamM034,Reach-1
Reach XY= 30
      2489375.00     13848025.00      2489337.43     13848024.17
      2489325.61     13848009.39      2489324.93     13847495.03
      2489276.22     13847414.49      2489272.74     13847230.94
      2489228.86     13847173.40      2489222.65     13847080.97
      2489177.35     13847019.03      2489172.65     13846930.97
      2489127.36     13846869.02      2489121.38     13846776.50
      2489030.54     13846677.42      2489021.17     13846576.59
      2488981.11     13846527.18      2488928.83     13846423.41
      2488919.48     13846322.57      2488785.77     13846184.68
      2488768.90     13846122.81      2488729.19     13846073.26
      2488719.17     13846022.69      2488638.33     13845938.39
      2488526.60     13845921.14      2488464.49     13845876.23
      2488322.55     13845869.53      2488101.17     13845651.87
      2488075.38     13845609.84      2488071.62     13845426.26
      2488027.95     13845380.13      2487975.00     13845375.00

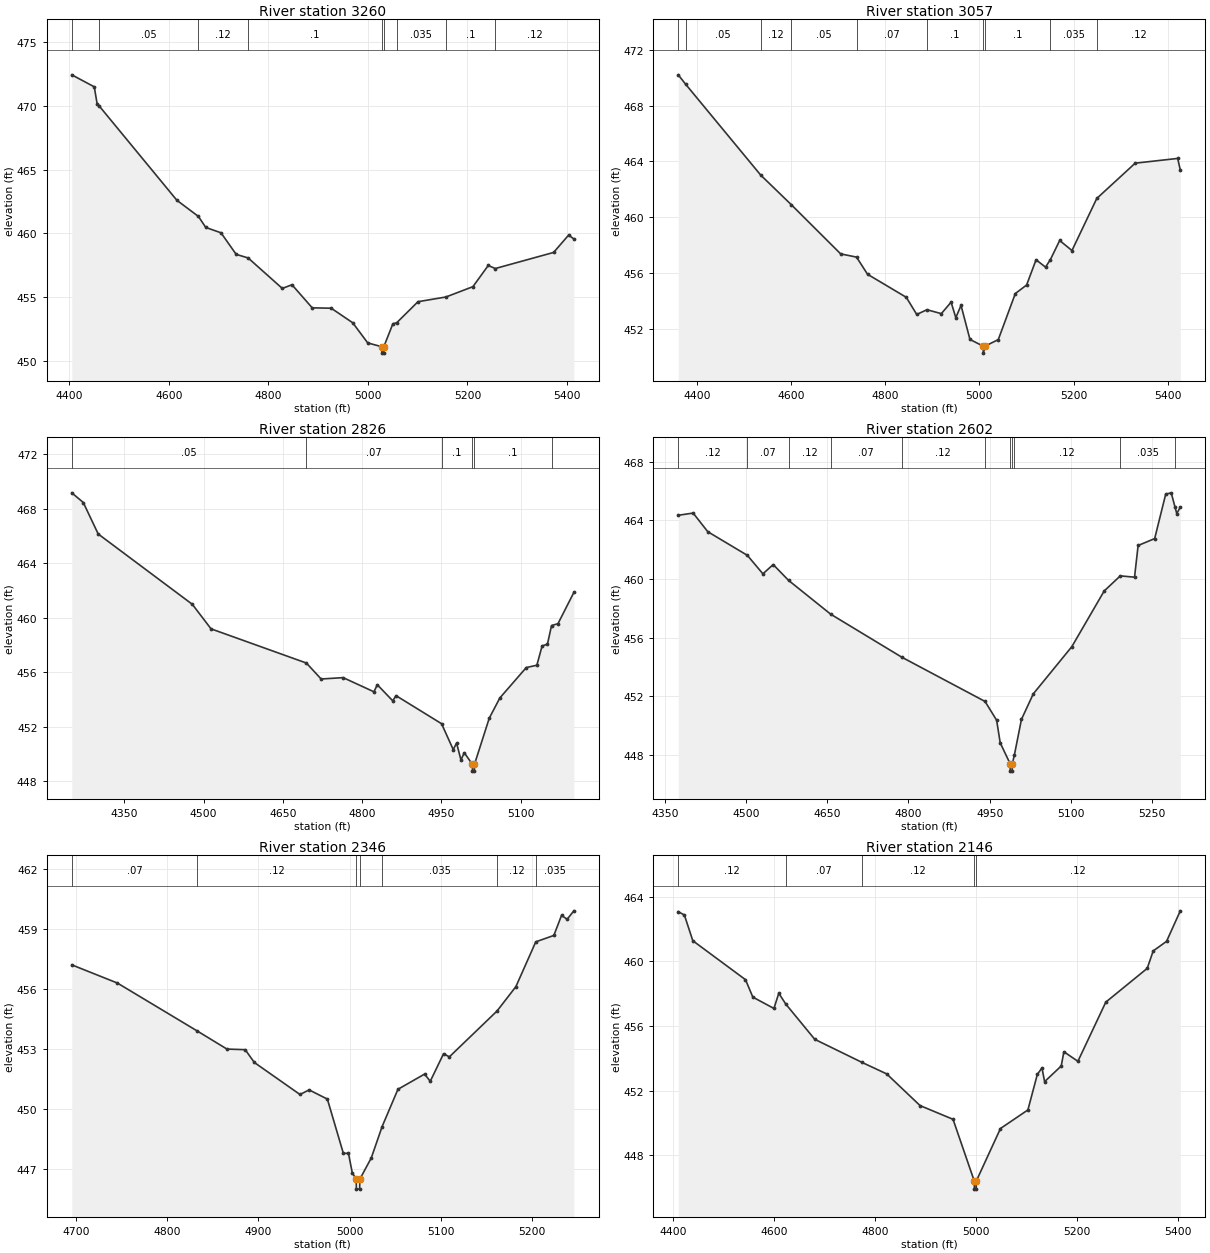
Type RM Length L Ch R = 1,3260,203,203,203
BEGIN DESCRIPTION:
H21269
END DESCRIPTION:
XS GIS Cut Line= 3
      2489909.36     13848069.87      2489372.92     13847965.71
      2488914.63     13847903.22
#Sta/Elev= 30
  4404.9  472.42  4450.1  471.48  4455.9  470.14  4459.8  469.99  4616.1  462.59
  4659.5  461.32  4674.2  460.46  4704.8  460.04  4735.3  458.35  4759.3  458.07
  4828.0  455.68  4847.4  455.97  4888.1  454.16  4926.3  454.13  4969.5  452.99
  4999.7  451.41  5028.0  451.11  5028.3  450.61  5031.8  450.61  5032.0  451.11
  5050.2  452.91  5057.9  452.99  5100.7  454.64  5156.9  455.01  5211.1  455.82
  5241.9  457.48  5256.0  457.24  5373.2  458.50  5403.4  459.86  5413.9  459.56
#Mann=9,-1,0
  4404.9    0.07       0  4459.8    0.05       0  4659.5    0.12       0
  4759.3     0.1       0  5028.0    0.05       0  5032.0     0.1       0
  5057.9   0.035       0  5156.9     0.1       0  5256.0    0.12       0
Bank Sta=5028,5032
Exp/Cntr=0.3,0.1

Type RM Length L Ch R = 1,3057,231,231,231
BEGIN DESCRIPTION:
H21268
END DESCRIPTION:
XS GIS Cut Line= 3
      2489904.14     13848017.78      2489398.96     13847762.58
      2488899.47     13847720.96
#Sta/Elev= 30
  4359.8  470.21  4375.7  469.53  4535.0  463.03  4600.3  460.90  4705.1  457.38
  4738.8  457.15  4762.2  455.92  4844.5  454.27  4866.8  453.04  4888.4  453.38
  4919.0  453.10  4939.8  453.92  4949.8  452.81  4960.9  453.69  4979.9  451.25
  5008.0  450.77  5008.3  450.27  5012.0  450.77  5040.1  451.24  5076.3  454.54
  5100.3  455.15  5120.4  456.96  5140.5  456.43  5150.8  456.97  5170.6  458.34
  5196.7  457.62  5249.4  461.35  5331.1  463.88  5421.4  464.22  5427.0  463.39
#Mann=10,-1,0
  4359.8    0.07       0  4375.7    0.05       0  4535.0    0.12       0
  4600.3    0.05       0  4738.8    0.07       0  4888.4     0.1       0
  5008.0    0.05       0  5012.0     0.1       0  5150.8   0.035       0
  5249.4    0.12       0
Bank Sta=5008,5012
Exp/Cntr=0.3,0.1

Type RM Length L Ch R = 1,2826,224,224,224
BEGIN DESCRIPTION:
StreamM034 5.0
END DESCRIPTION:
XS GIS Cut Line= 3
      2489924.98     13847974.98      2489325.00     13847525.00
      2489124.97     13847525.00
#Sta/Elev= 30
  4250.5  469.18  4272.3  468.47  4300.5  466.16  4478.6  461.00  4514.0  459.20
  4694.5  456.69  4722.3  455.52  4764.0  455.62  4822.3  454.58  4828.6  455.10
  4857.8  453.92  4864.0  454.30  4950.2  452.24  4972.3  450.34  4978.6  450.82
  4986.9  449.58  4993.2  450.11  5008.5  449.26  5008.7  448.76  5012.2  448.76
  5012.5  449.26  5040.5  452.65  5060.5  454.13  5110.5  456.36  5130.5  456.53
  5140.5  457.95  5150.5  458.07  5158.3  459.44  5170.5  459.58  5200.5  461.87
#Mann=6,-1,0
  4250.5    0.05       0  4694.5    0.07       0  4950.2     0.1       0
  5008.5    0.05       0  5012.5     0.1       0  5158.3    0.12       0
Bank Sta=5008.5,5012.5
Exp/Cntr=0.3,0.1

Type RM Length L Ch R = 1,2602,256,256,256
BEGIN DESCRIPTION:
H21267
END DESCRIPTION:
XS GIS Cut Line= 2
      2489888.51     13847194.88      2488978.53     13847376.88
#Sta/Elev= 30
  4374.4  464.35  4402.0  464.50  4429.0  463.23  4502.1  461.62  4530.9  460.36
  4549.9  460.99  4578.4  459.91  4656.1  457.61  4787.4  454.68  4941.5  451.66
  4962.9  450.38  4969.5  448.84  4987.9  447.41  4988.1  446.91  4991.6  446.91
  4991.9  447.41  4995.7  448.01  5008.8  450.44  5030.7  452.18  5102.0  455.40
  5161.7  459.19  5191.5  460.22  5217.8  460.13  5224.4  462.29  5255.0  462.76
  5275.4  465.79  5285.6  465.88  5292.6  464.91  5295.8  464.47  5302.4  464.90
#Mann=11,-1,0
  4374.4    0.12       0  4502.1    0.07       0  4578.4    0.12       0
  4656.1    0.07       0  4787.4    0.12       0  4941.5     0.1       0
  4987.9    0.05       0  4991.9     0.1       0  4995.7    0.12       0
  5191.5   0.035       0  5292.6    0.12       0
Bank Sta=4987.9,4991.9
Exp/Cntr=0.3,0.1

Type RM Length L Ch R = 1,2346,200,200,200
BEGIN DESCRIPTION:
StreamM034 4.0
END DESCRIPTION:
XS GIS Cut Line= 3
      2489525.02     13847075.00      2489225.00     13847075.00
      2489025.02     13847224.99
#Sta/Elev= 30
  4695.6  457.19  4745.6  456.28  4833.2  453.88  4865.6  452.98  4885.6  452.95
  4895.6  452.31  4945.6  450.71  4955.6  450.94  4975.6  450.48  4993.1  447.77
  4998.7  447.77  5002.9  446.79  5007.2  446.48  5007.4  445.98  5010.9  445.98
  5011.2  446.48  5023.7  447.54  5035.6  449.11  5052.9  450.97  5082.1  451.73
  5088.3  451.37  5102.9  452.75  5109.2  452.59  5161.4  454.88  5182.1  456.10
  5203.9  458.34  5223.7  458.66  5232.1  459.66  5238.3  459.47  5245.6  459.89
#Mann=7,-1,0
  4695.6    0.07       0  4833.2    0.12       0  5007.2    0.05       0
  5011.2    0.12       0  5035.6   0.035       0  5161.4    0.12       0
  5203.9   0.035       0
Bank Sta=5007.2,5011.2
Exp/Cntr=0.3,0.1

Type RM Length L Ch R = 1,2146,272,272,272
BEGIN DESCRIPTION:
H21266
END DESCRIPTION:
XS GIS Cut Line= 2
      2489716.64     13846731.34      2488763.55     13847017.79
#Sta/Elev= 30
  4409.6  463.07  4421.8  462.86  4438.5  461.27  4542.9  458.86  4557.5  457.78
  4599.3  457.08  4608.9  458.02  4622.8  457.35  4680.2  455.17  4773.3  453.75
  4822.8  453.03  4888.9  451.07  4954.3  450.22  4996.4  446.40  4996.7  445.90
  5000.2  445.90  5000.4  446.40  5048.3  449.65  5102.7  450.80  5121.4  453.00
  5130.6  453.40  5135.8  452.55  5168.8  453.52  5174.0  454.40  5201.8  453.81
  5257.1  457.47  5339.2  459.56  5351.1  460.64  5377.5  461.23  5404.8  463.12
#Mann=5,-1,0
  4409.6    0.12       0  4622.8    0.07       0  4773.3    0.12       0
  4996.4    0.05       0  5000.4    0.12       0
Bank Sta=4996.4,5000.4
Exp/Cntr=0.3,0.1

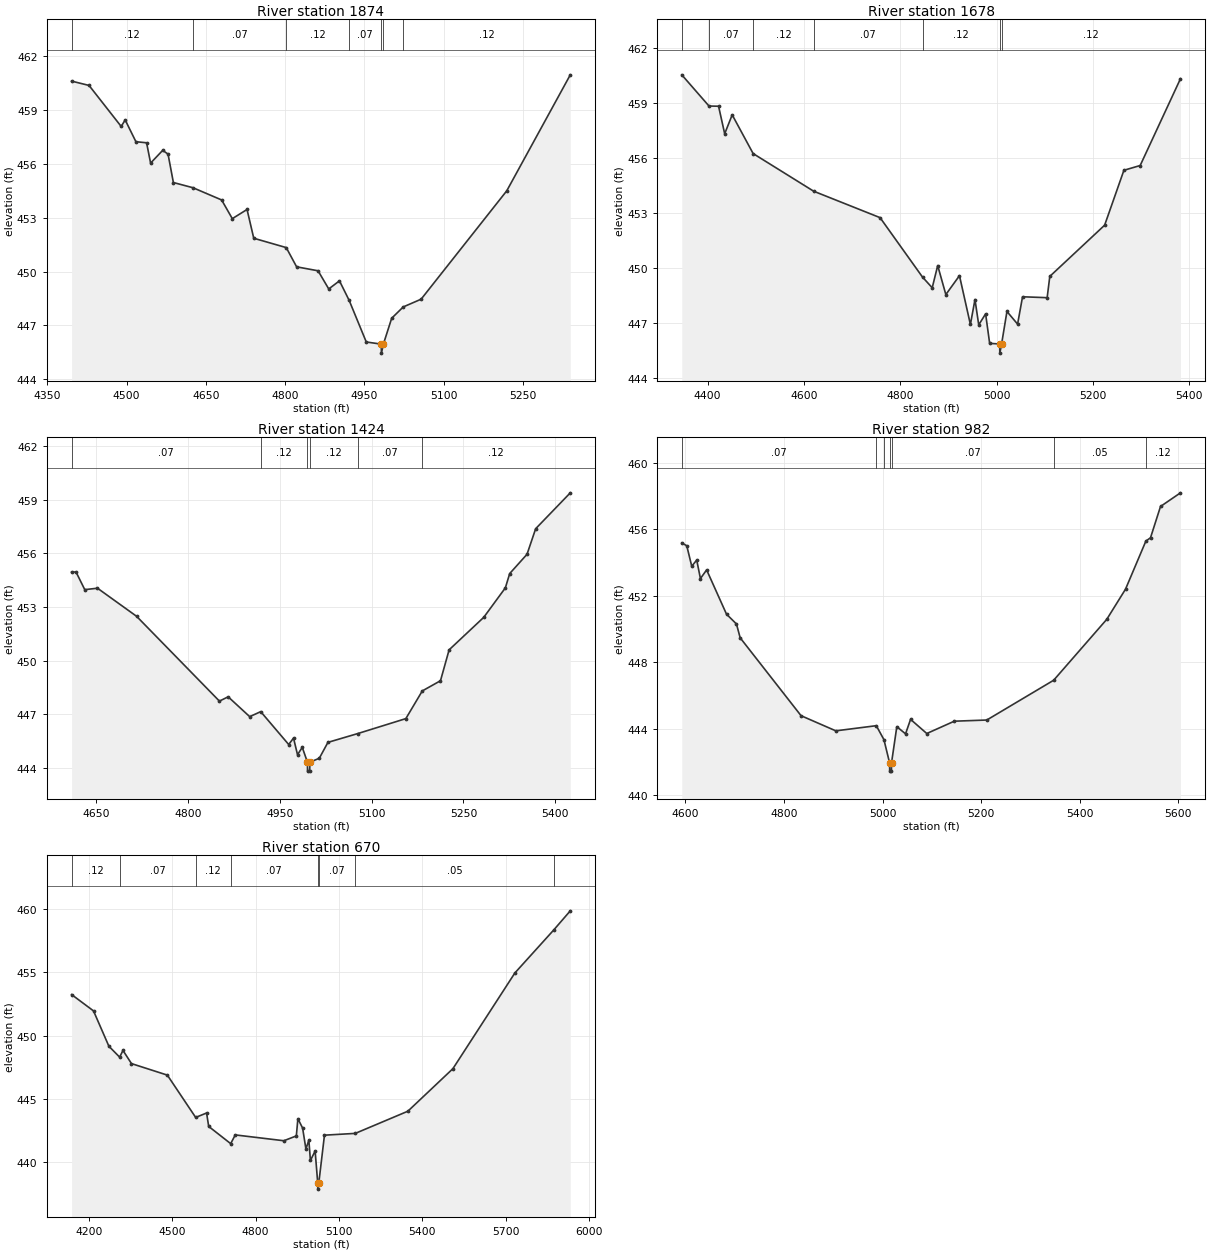
Type RM Length L Ch R = 1,1874,196,196,196
BEGIN DESCRIPTION:
StreamM034 3.0
END DESCRIPTION:
XS GIS Cut Line= 3
      2489625.01     13846575.00      2489025.00     13846675.00
      2488724.99     13846825.00
#Sta/Elev= 30
  4395.8  460.59  4428.8  460.35  4489.6  458.07  4497.2  458.43  4517.5  457.22
  4537.7  457.16  4545.3  456.03  4568.2  456.74  4578.3  456.53  4588.4  454.95
  4625.5  454.66  4679.7  453.98  4699.9  452.94  4727.8  453.45  4740.5  451.85
  4802.0  451.33  4821.6  450.26  4862.2  450.04  4882.4  449.03  4902.7  449.48
  4921.1  448.39  4953.4  446.08  4981.8  445.96  4982.1  445.46  4985.8  445.96
  5001.5  447.40  5023.4  448.03  5057.2  448.46  5219.3  454.49  5339.5  460.94
#Mann=7,-1,0
  4395.8    0.12       0  4625.5    0.07       0  4802.0    0.12       0
  4921.1    0.07       0  4981.8    0.05       0  4985.8    0.07       0
  5023.4    0.12       0
Bank Sta=4981.8,4985.8
Exp/Cntr=0.3,0.1

Type RM Length L Ch R = 1,1678,254,254,254
BEGIN DESCRIPTION:
H21265
END DESCRIPTION:
XS GIS Cut Line= 2
      2489565.60     13846215.72      2488629.07     13846657.97
#Sta/Elev= 30
  4346.3  460.53  4402.8  458.83  4422.7  458.82  4435.4  457.32  4451.0  458.35
  4494.5  456.24  4620.2  454.19  4758.1  452.75  4846.3  449.51  4866.4  448.93
  4877.8  450.14  4894.7  448.56  4923.0  449.59  4945.7  446.93  4955.2  448.29
  4963.0  446.91  4977.3  447.51  4985.7  445.90  5006.5  445.87  5006.8  445.37
  5010.5  445.87  5021.6  447.64  5043.7  446.95  5054.0  448.44  5105.1  448.39
  5110.6  449.55  5224.5  452.34  5264.5  455.33  5298.3  455.59  5382.0  460.32
#Mann=7,-1,0
  4346.3    0.12       0  4402.8    0.07       0  4494.5    0.12       0
  4620.2    0.07       0  4846.3    0.12       0  5006.5    0.05       0
  5010.5    0.12       0
Bank Sta=5006.5,5010.5
Exp/Cntr=0.3,0.1

Type RM Length L Ch R = 1,1424,442,442,442
BEGIN DESCRIPTION:
StreamM034 2.0
END DESCRIPTION:
XS GIS Cut Line= 3
      2489125.02     13845974.97      2488875.00     13846275.00
      2488575.01     13846574.99
#Sta/Elev= 30
  4609.7  454.95  4616.9  454.96  4631.2  453.97  4652.0  454.05  4715.8  452.48
  4851.2  447.73  4865.5  447.97  4900.7  446.86  4918.7  447.14  4964.4  445.30
  4972.3  445.66  4978.8  444.73  4986.6  445.14  4995.0  444.31  4995.2  443.81
  4998.7  443.81  4999.0  444.31  5014.4  444.53  5028.5  445.42  5077.0  445.91
  5155.8  446.75  5182.7  448.30  5212.4  448.87  5226.5  450.60  5283.1  452.42
  5318.4  454.07  5325.5  454.87  5353.8  455.95  5367.9  457.38  5424.5  459.39
#Mann=6,-1,0
  4609.7    0.07       0  4918.7    0.12       0  4995.0    0.05       0
  4999.0    0.12       0  5077.0    0.07       0  5182.7    0.12       0
Bank Sta=4995,4999
Exp/Cntr=0.3,0.1

Type RM Length L Ch R = 1,982,312,312,312
BEGIN DESCRIPTION:
StreamM034 1.0
END DESCRIPTION:
XS GIS Cut Line= 3
      2489025.03     13845875.00      2488625.00     13845925.00
      2488525.00     13846524.98
#Sta/Elev= 30
  4592.8  455.17  4602.9  455.00  4613.0  453.77  4623.1  454.14  4630.6  453.03
  4643.2  453.55  4683.5  450.89  4703.7  450.30  4711.2  449.47  4834.7  444.79
  4905.2  443.88  4987.3  444.19  5002.8  443.35  5014.2  441.96  5014.5  441.46
  5018.0  441.46  5018.2  441.96  5028.9  444.13  5046.6  443.70  5056.8  444.57
  5089.7  443.72  5145.5  444.46  5211.4  444.53  5347.0  446.92  5454.7  450.58
  5492.7  452.39  5534.0  455.28  5543.4  455.48  5563.7  457.36  5604.2  458.18
#Mann=7,-1,0
  4592.8    0.07       0  4987.3    0.12       0  5002.8    0.07       0
  5014.2    0.05       0  5018.2    0.07       0  5347.0    0.05       0
  5534.0    0.12       0
Bank Sta=5014.2,5018.2
Exp/Cntr=0.3,0.1

Type RM Length L Ch R = 1,670,0,0,0
BEGIN DESCRIPTION:
H21264
END DESCRIPTION:
XS GIS Cut Line= 4
      2489029.16     13845455.29      2488425.00     13845674.04
      2488227.08     13846080.29      2488346.61     13846771.49
#Sta/Elev= 30
  4137.1  453.25  4216.0  451.96  4271.4  449.17  4310.1  448.31  4322.1  448.84
  4352.7  447.80  4481.9  446.89  4583.9  443.55  4623.2  443.90  4630.8  442.84
  4710.0  441.48  4726.5  442.17  4901.4  441.71  4946.4  442.09  4952.0  443.45
  4969.0  442.71  4980.9  441.06  4991.5  441.76  4997.1  440.15  5014.1  440.90
  5023.4  438.39  5023.7  437.89  5027.4  438.39  5047.7  442.15  5158.7  442.29
  5348.0  444.04  5510.3  447.40  5733.6  454.96  5872.6  458.33  5933.0  459.86
#Mann=8,-1,0
  4137.1    0.12       0  4310.1    0.07       0  4583.9    0.12       0
  4710.0    0.07       0  5023.4    0.05       0  5027.4    0.07       0
  5158.7    0.05       0  5872.6    0.12       0
Bank Sta=5023.4,5027.4
Exp/Cntr=0.3,0.1

Chan Stop Cuts=-1