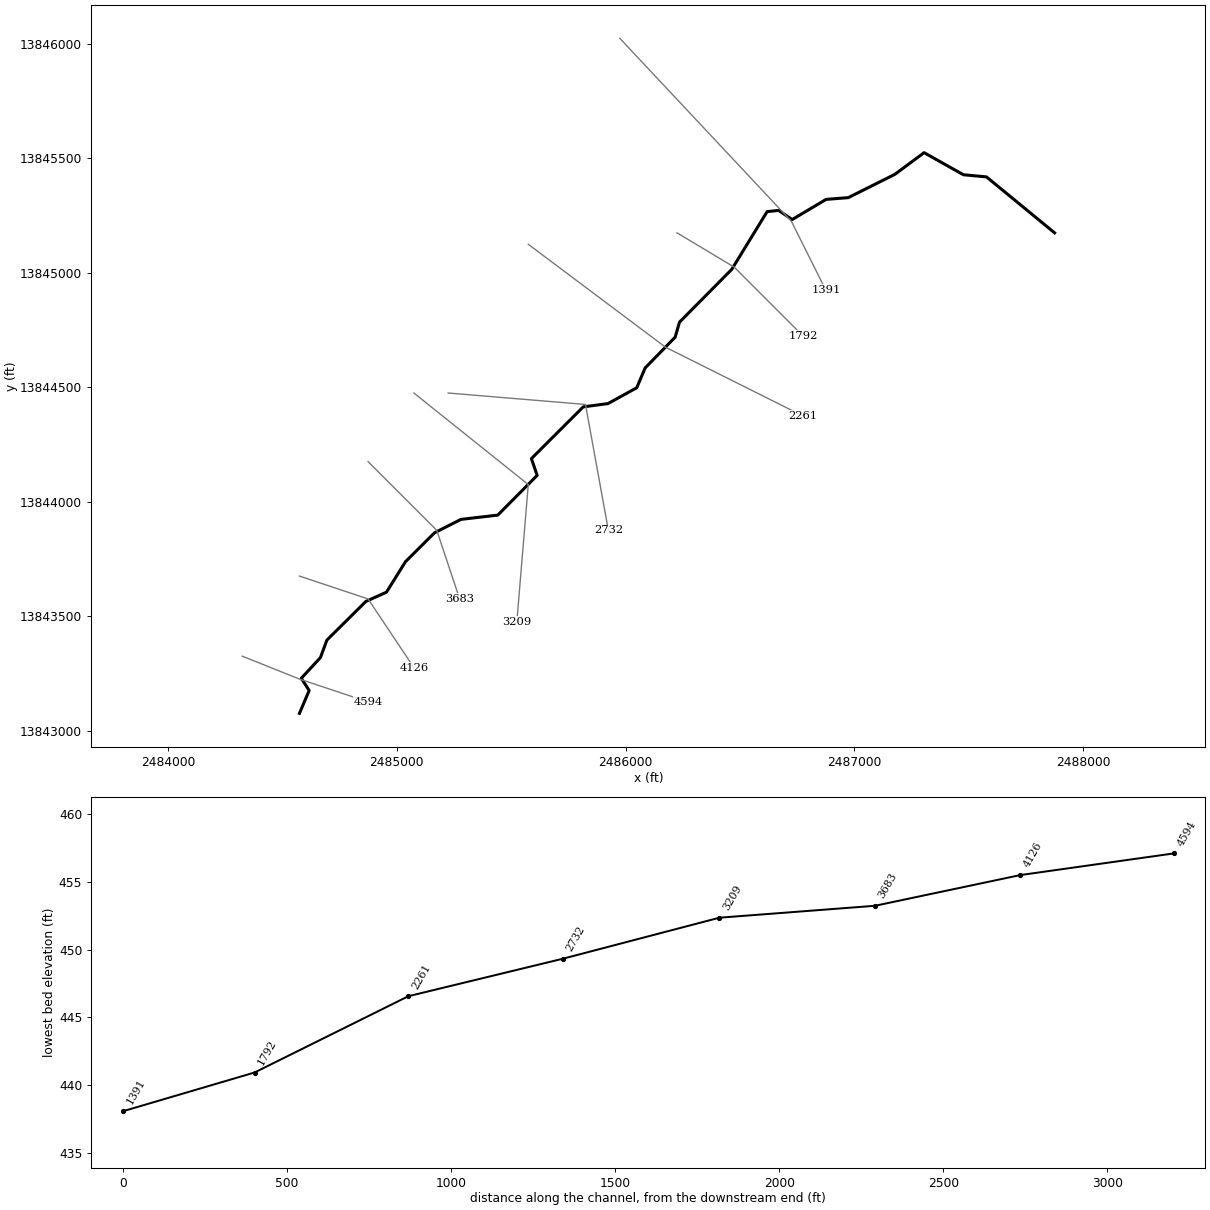
--- StreamM035.prj (project) ---

Proj Title=StreamM035 Base Level Engineering
Current Plan=p01
Default Exp/Contr=0.3,0.1
English Units
Geom File=g01
Flow File=f01
Plan File=p01
BEGIN DESCRIPTION:
StreamM035
END DESCRIPTION:

--- StreamM035.p01 (plan) ---

Plan Title=Multiple Run
Short Identifier=Multiple
Geom File=g01
Flow File=f01
Subcritical Flow
K Sum by GR= 0
Std Step Tol= 0.01
Critical Tol= 0.01
Num of Std Step Trials= 20
Max Error Tol= 0.3
Flow Tol Ratio= 0.001
Split Flow NTrial= 30
Split Flow Tol= 0.02
Split Flow Ratio= 0.02
Log Output Level= 0
Friction Slope Method= 1
Unsteady Friction Slope Method= 2
Unsteady Bridges Friction Slope Method= 1
Parabolic Critical Depth
Global Vel Dist=  1 , 1 , 1
Global Log Level= 0
CheckData=True
Encroach Param= -1, 0, 0, 0
BEGIN DESCRIPTION:
Multiple Run
END DESCRIPTION:

--- StreamM035.f01 (steady flow) ---

Flow Title=Multiple
Number of Profiles=7
Profile Names=10-year,25-year,50-year,1pct_min,100-year,1pct_plu,500-year
River Rch & RM= StreamM035,Reach-1,4594
     711    1145    1536     998    1991    3973    3312
Boundary for River Rch & Prof#=StreamM035,Reach-1,1
Up Type=0
Dn Type=3
Dn Slope=0.005
Boundary for River Rch & Prof#=StreamM035,Reach-1,2
Up Type=0
Dn Type=3
Dn Slope=0.005
Boundary for River Rch & Prof#=StreamM035,Reach-1,3
Up Type=0
Dn Type=3
Dn Slope=0.005
Boundary for River Rch & Prof#=StreamM035,Reach-1,4
Up Type=0
Dn Type=3
Dn Slope=0.005
Boundary for River Rch & Prof#=StreamM035,Reach-1,5
Up Type=0
Dn Type=3
Dn Slope=0.005
Boundary for River Rch & Prof#=StreamM035,Reach-1,6
Up Type=0
Dn Type=3
Dn Slope=0.005
Boundary for River Rch & Prof#=StreamM035,Reach-1,7
Up Type=0
Dn Type=3
Dn Slope=0.005

--- StreamM035.g01 (geometry) ---

Geom Title=Existing Conditions

River Reach=StreamM035,Reach-1
Reach XY= 30
      2484575.00     13843075.00      2484617.42     13843175.07
      2484582.99     13843228.33      2484666.80     13843318.95
      2484694.79     13843395.09      2484865.32     13843564.22
      2484955.23     13843604.58      2485038.63     13843738.21
      2485165.32     13843864.24      2485280.93     13843922.75
      2485441.76     13843941.43      2485613.76     13844115.00
      2485588.65     13844188.33      2485815.21     13844414.48
      2485923.42     13844428.83      2486048.84     13844497.85
      2486085.79     13844584.66      2486216.84     13844718.95
      2486235.78     13844784.68      2486464.22     13845015.32
      2486618.67     13845267.62      2486668.91     13845273.03
      2486728.31     13845233.07      2486876.58     13845321.17
      2486973.42     13845328.83      2487177.29     13845430.85
      2487304.80     13845525.37      2487476.59     13845428.83
      2487577.42     13845419.46      2487875.00     13845175.00

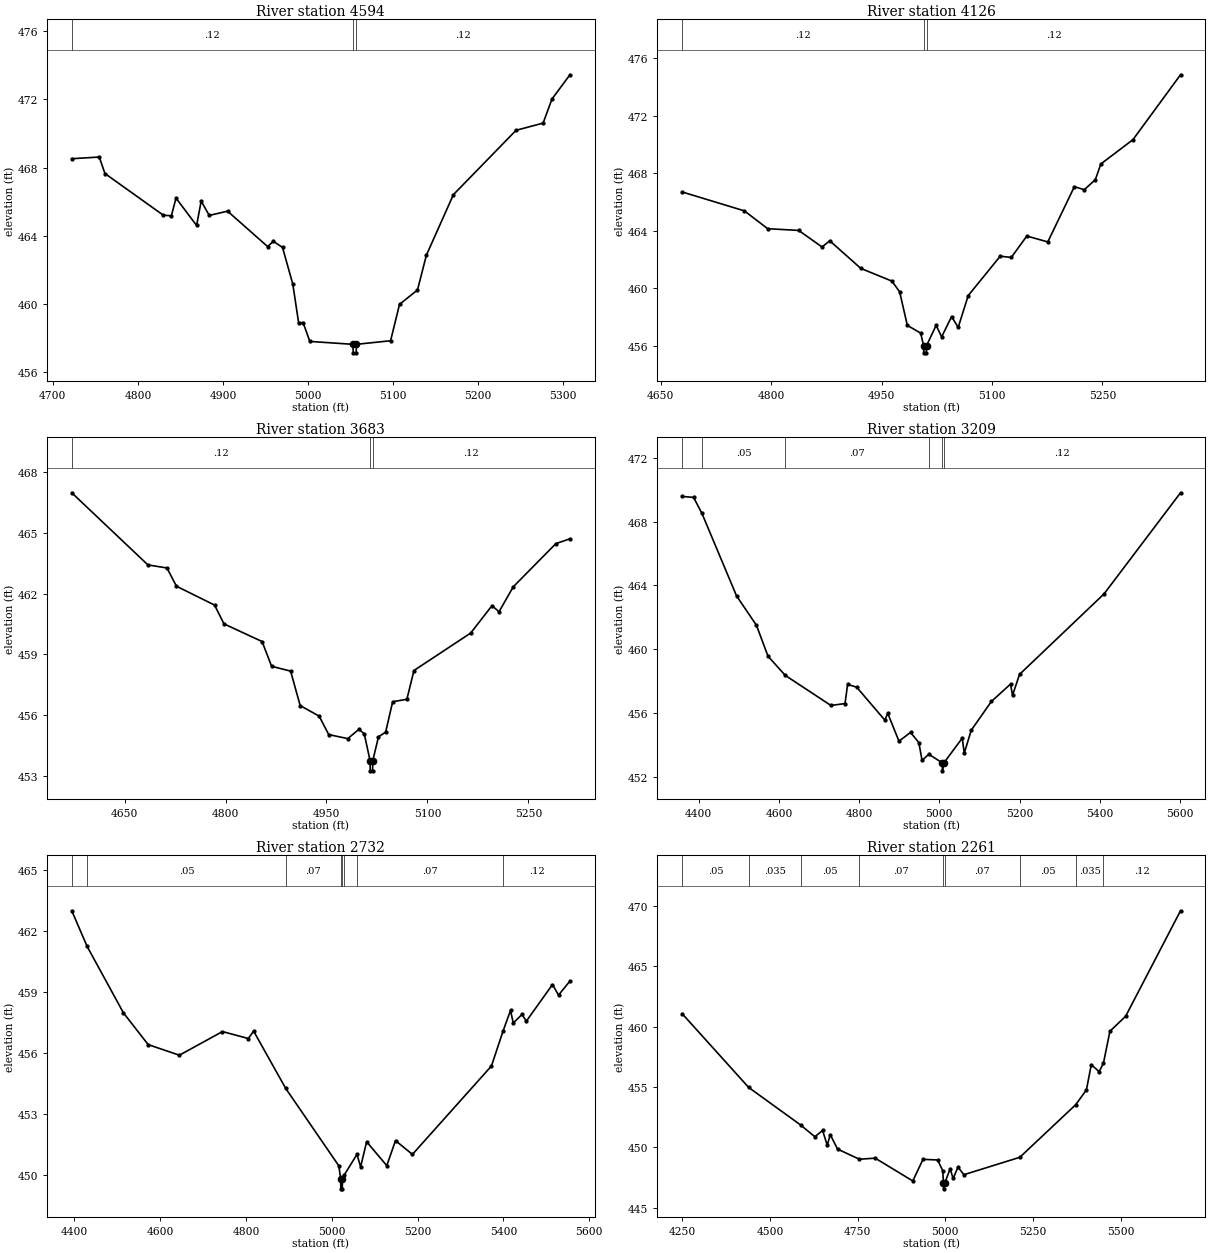
Type RM Length L Ch R = 1,4594,468,468,468
BEGIN DESCRIPTION:
StreamM035 8.0
END DESCRIPTION:
XS GIS Cut Line= 3
      2484325.00     13843325.00      2484575.00     13843225.00
      2484875.01     13843125.00
#Sta/Elev= 30
  4722.3  468.52  4754.6  468.62  4761.3  467.65  4830.0  465.20  4839.4  465.17
  4844.8  466.21  4869.0  464.60  4874.4  466.03  4883.9  465.19  4905.4  465.44
  4952.5  463.36  4959.2  463.67  4970.0  463.31  4982.1  461.15  4988.9  458.89
  4994.2  458.89  5002.1  457.79  5052.8  457.62  5053.1  457.12  5056.6  457.12
  5056.8  457.62  5097.0  457.83  5107.5  459.97  5128.6  460.81  5139.1  462.86
  5170.8  466.41  5244.5  470.19  5276.2  470.61  5286.7  472.03  5307.8  473.45
#Mann=3,-1,0
  4722.3    0.12       0  5052.8    0.05       0  5056.8    0.12       0
Bank Sta=5052.8,5056.8
Exp/Cntr=0.3,0.1

Type RM Length L Ch R = 1,4126,443,443,443
BEGIN DESCRIPTION:
StreamM035 7.0
END DESCRIPTION:
XS GIS Cut Line= 3
      2484574.98     13843675.01      2484875.00     13843575.00
      2485075.00     13843275.00
#Sta/Elev= 30
  4679.3  466.70  4763.6  465.39  4795.3  464.15  4837.4  464.03  4869.1  462.88
  4879.6  463.31  4921.8  461.39  4963.9  460.51  4974.5  459.77  4985.0  457.43
  5003.1  456.89  5007.1  456.02  5007.3  455.52  5010.8  455.52  5011.1  456.02
  5024.1  457.43  5031.6  456.63  5045.1  458.04  5054.1  457.29  5067.7  459.50
  5111.2  462.24  5126.2  462.15  5147.3  463.64  5175.8  463.23  5211.9  467.07
  5225.4  466.86  5240.4  467.56  5247.9  468.65  5291.5  470.34  5356.1  474.85
#Mann=3,-1,0
  4679.3    0.12       0  5007.1    0.05       0  5011.1    0.12       0
Bank Sta=5007.1,5011.1
Exp/Cntr=0.3,0.1

Type RM Length L Ch R = 1,3683,474,474,474
BEGIN DESCRIPTION:
StreamM035 6.0
END DESCRIPTION:
XS GIS Cut Line= 3
      2484874.97     13844175.03      2485175.00     13843875.00
      2485274.99     13843575.03
#Sta/Elev= 30
  4571.4  466.97  4684.6  463.41  4712.9  463.26  4727.0  462.36  4783.6  461.43
  4797.7  460.50  4854.3  459.63  4868.4  458.41  4896.7  458.17  4910.9  456.47
  4939.1  455.95  4953.3  455.04  4981.6  454.84  4998.3  455.30  5006.2  455.07
  5014.8  453.75  5015.0  453.25  5018.5  453.25  5018.8  453.75  5027.3  454.93
  5037.9  455.16  5048.4  456.66  5069.5  456.78  5080.0  458.20  5164.4  460.05
  5196.0  461.40  5206.5  461.10  5227.6  462.33  5290.9  464.46  5311.9  464.70
#Mann=3,-1,0
  4571.4    0.12       0  5014.8    0.05       0  5018.8    0.12       0
Bank Sta=5014.8,5018.8
Exp/Cntr=0.3,0.1

Type RM Length L Ch R = 1,3209,477,477,477
BEGIN DESCRIPTION:
StreamM035 5.0
END DESCRIPTION:
XS GIS Cut Line= 3
      2485074.97     13844475.03      2485575.00     13844075.00
      2485525.00     13843475.03
#Sta/Elev= 30
  4359.1  469.58  4387.2  469.52  4408.0  468.52  4494.4  463.34  4544.0  461.50
  4572.8  459.56  4615.7  458.36  4729.7  456.47  4764.9  456.59  4771.3  457.79
  4793.8  457.62  4864.2  455.55  4871.4  455.98  4899.4  454.23  4928.2  454.78
  4949.0  454.14  4957.0  453.02  4973.8  453.41  5007.5  452.87  5007.7  452.37
  5011.5  452.87  5057.2  454.42  5062.2  453.48  5079.7  454.92  5129.9  456.72
  5177.6  457.81  5182.6  457.11  5200.1  458.42  5410.9  463.47  5601.5  469.81
#Mann=6,-1,0
  4359.1   0.035       0  4408.0    0.05       0  4615.7    0.07       0
  4973.8    0.12       0  5007.5    0.05       0  5011.5    0.12       0
Bank Sta=5007.5,5011.5
Exp/Cntr=0.3,0.1

Type RM Length L Ch R = 1,2732,471,471,471
BEGIN DESCRIPTION:
StreamM035 4.0
END DESCRIPTION:
XS GIS Cut Line= 3
      2485225.03     13844475.00      2485825.00     13844425.00
      2485925.01     13843874.96
#Sta/Elev= 30
  4393.9  462.99  4429.7  461.24  4514.3  457.98  4572.0  456.42  4644.7  455.90
  4745.1  457.06  4805.3  456.72  4817.8  457.08  4892.5  454.27  5016.3  450.47
  5020.6  449.84  5020.9  449.34  5024.4  449.34  5024.6  449.84  5029.5  450.04
  5058.6  451.03  5067.1  450.42  5081.1  451.65  5128.1  450.48  5148.4  451.71
  5187.8  451.03  5372.0  455.37  5399.5  457.11  5416.5  458.10  5422.8  457.48
  5443.2  457.90  5453.3  457.57  5514.3  459.37  5528.3  458.85  5555.0  459.54
#Mann=8,-1,0
  4393.9   0.035       0  4429.7    0.05       0  4892.5    0.07       0
  5020.6    0.05       0  5024.6    0.07       0  5029.5    0.05       0
  5058.6    0.07       0  5399.5    0.12       0
Bank Sta=5020.6,5024.6
Exp/Cntr=0.3,0.1

Type RM Length L Ch R = 1,2261,469,469,469
BEGIN DESCRIPTION:
StreamM035 3.0
END DESCRIPTION:
XS GIS Cut Line= 3
      2485575.03     13845124.98      2486175.00     13844675.00
      2486775.02     13844374.99
#Sta/Elev= 30
  4249.8  461.05  4439.1  454.96  4586.9  451.86  4627.9  450.88  4649.8  451.40
  4663.3  450.17  4671.6  451.06  4692.5  449.86  4754.8  449.02  4799.8  449.11
  4907.1  447.22  4936.2  449.01  4977.9  448.96  4992.5  448.07  4994.6  447.07
  4994.9  446.57  4998.6  447.07  5013.7  448.23  5022.1  447.43  5036.1  448.36
  5052.9  447.74  5212.3  449.18  5372.0  453.54  5402.3  454.76  5416.2  456.85
  5438.6  456.26  5450.9  456.98  5469.3  459.61  5514.1  460.85  5670.6  469.58
#Mann=9,-1,0
  4249.8    0.05       0  4439.1   0.035       0  4586.9    0.05       0
  4754.8    0.07       0  4994.6    0.05       0  4998.6    0.07       0
  5212.3    0.05       0  5372.0   0.035       0  5450.9    0.12       0
Bank Sta=4994.6,4998.6
Exp/Cntr=0.3,0.1

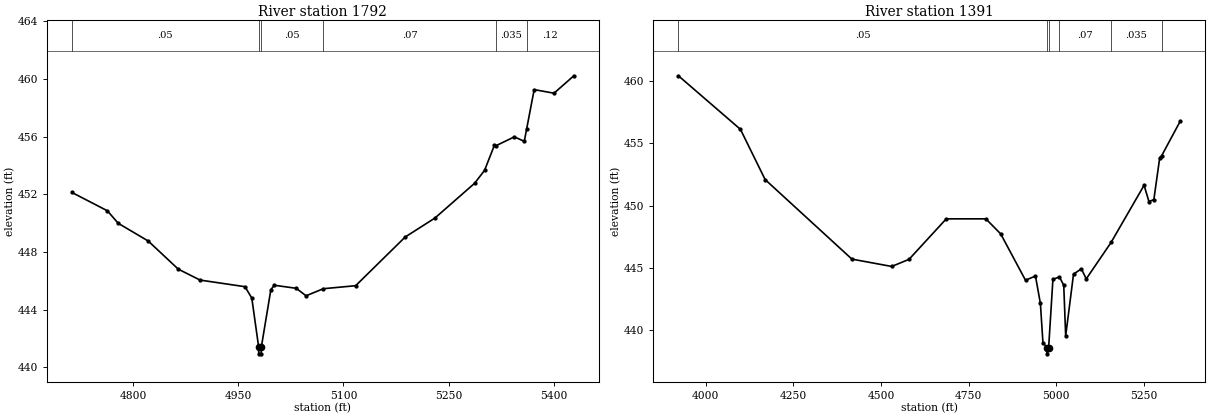
Type RM Length L Ch R = 1,1792,401,401,401
BEGIN DESCRIPTION:
StreamM035 2.0
END DESCRIPTION:
XS GIS Cut Line= 3
      2486225.04     13845174.98      2486475.00     13845025.00
      2486775.03     13844724.97
#Sta/Elev= 30
  4712.9  452.13  4763.4  450.86  4778.9  449.99  4821.7  448.76  4864.5  446.81
  4895.6  446.05  4959.7  445.59  4969.4  444.80  4979.1  441.43  4979.3  440.93
  4982.8  440.93  4983.1  441.43  4996.6  445.39  5001.5  445.69  5032.7  445.48
  5046.8  444.96  5071.4  445.45  5117.5  445.66  5188.2  449.04  5230.7  450.36
  5287.2  452.77  5301.4  453.67  5315.5  455.42  5317.8  455.38  5343.8  455.99
  5358.0  455.68  5361.3  456.52  5372.1  459.27  5400.4  459.02  5428.7  460.23
#Mann=6,-1,0
  4712.9    0.05       0  4979.1    0.05       0  4983.1    0.05       0
  5071.4    0.07       0  5317.8   0.035       0  5361.3    0.12       0
Bank Sta=4979.1,4983.1
Exp/Cntr=0.3,0.1

Type RM Length L Ch R = 1,1391,0,0,0
BEGIN DESCRIPTION:
StreamM035 1.0
END DESCRIPTION:
XS GIS Cut Line= 3
      2485975.02     13846024.98      2486725.00     13845225.00
      2486875.01     13844924.98
#Sta/Elev= 30
  3922.3  460.44  4099.3  456.13  4169.7  452.09  4417.3  445.69  4530.7  445.10
  4580.2  445.67  4686.5  448.93  4799.5  448.93  4841.8  447.72  4912.6  443.99
  4941.0  444.33  4955.1  442.12  4962.4  438.94  4974.6  438.57  4974.8  438.07
  4978.6  438.57  4990.8  444.06  5009.3  444.26  5021.7  443.59  5027.2  439.51
  5049.6  444.48  5072.0  444.91  5085.9  444.10  5156.7  447.03  5250.9  451.63
  5264.8  450.32  5278.8  450.48  5295.6  453.86  5300.7  453.99  5354.3  456.80
#Mann=6,-1,0
  3922.3    0.05       0  4974.6    0.05       0  4978.6    0.05       0
  5009.3    0.07       0  5156.7   0.035       0  5300.7    0.12       0
Bank Sta=4974.6,4978.6
Exp/Cntr=0.3,0.1

Chan Stop Cuts=-1