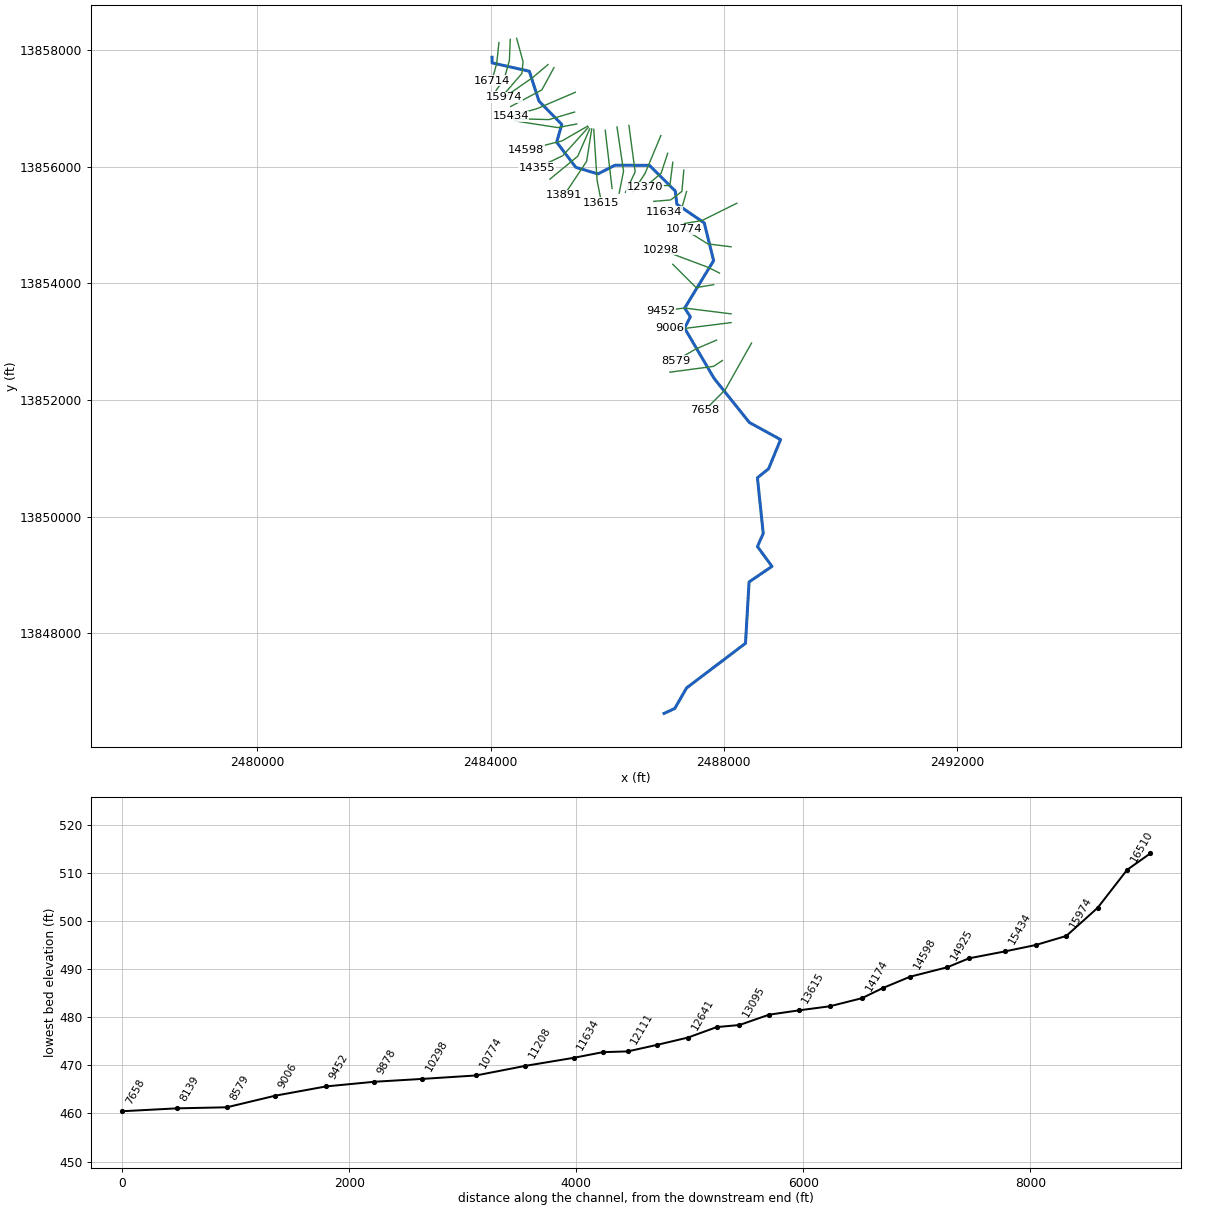
--- StreamM036.prj (project) ---

Proj Title=StreamM036 Base Level Engineering
Current Plan=p01
Default Exp/Contr=0.3,0.1
English Units
Geom File=g01
Flow File=f01
Plan File=p01
Y Axis Title=Elevation
X Axis Title(PF)=Main Channel Distance
X Axis Title(XS)=Station
BEGIN DESCRIPTION:
StreamM036
END DESCRIPTION:
DSS Export Rating Curves= 0
DSS Export Rating Curve Sorted= 0
DSS Export Volume Flow Curves= 0
DXF OffsetX= 0
DXF OffsetY= 0
DXF ScaleX= 1
DXF ScaleY= 10

--- StreamM036.p01 (plan) ---

Plan Title=Multiple Run
Short Identifier=Multiple
Geom File=g01
Flow File=f01
Subcritical Flow
K Sum by GR= 0
Std Step Tol= 0.01
Critical Tol= 0.01
Num of Std Step Trials= 20
Max Error Tol= 0.3
Flow Tol Ratio= 0.001
Split Flow NTrial= 30
Split Flow Tol= 0.02
Split Flow Ratio= 0.02
Log Output Level= 0
Friction Slope Method= 1
Unsteady Friction Slope Method= 2
Unsteady Bridges Friction Slope Method= 1
Parabolic Critical Depth
Global Vel Dist=  1 , 1 , 1
Global Log Level= 0
CheckData=True
Encroach Param= -1, 0, 0, 0
BEGIN DESCRIPTION:
Multiple Run
END DESCRIPTION:

--- StreamM036.f01 (steady flow) ---

Flow Title=Multiple
Number of Profiles=7
Profile Names=10-year,25-year,50-year,1pct_min,100-year,1pct_plu,500-year
River Rch & RM= StreamM036,Reach-1,16714
     587     946    1271     829    1653    3298    2767
River Rch & RM= StreamM036,Reach-1,14355
     830    1355    1835    1205    2403    4795    4079
River Rch & RM= StreamM036,Reach-1,11208
    1049    1725    2348    1545    3083    6152    5266
River Rch & RM= StreamM036,Reach-1,6454
    1401    2334    3206    2127    4244    8468    7367
River Rch & RM= StreamM036,Reach-1,4585
    1711    2880    3980    2655    5298   10571    9304
River Rch & RM= StreamM036,Reach-1,3654
    1797    3021    4172    2781    5548   11070    9721
Boundary for River Rch & Prof#=StreamM036,Reach-1,1
Up Type=0
Dn Type=3
Dn Slope=0.005
Boundary for River Rch & Prof#=StreamM036,Reach-1,2
Up Type=0
Dn Type=3
Dn Slope=0.005
Boundary for River Rch & Prof#=StreamM036,Reach-1,3
Up Type=0
Dn Type=3
Dn Slope=0.005
Boundary for River Rch & Prof#=StreamM036,Reach-1,4
Up Type=0
Dn Type=3
Dn Slope=0.005
Boundary for River Rch & Prof#=StreamM036,Reach-1,5
Up Type=0
Dn Type=3
Dn Slope=0.005
Boundary for River Rch & Prof#=StreamM036,Reach-1,6
Up Type=0
Dn Type=3
Dn Slope=0.005
Boundary for River Rch & Prof#=StreamM036,Reach-1,7
Up Type=0
Dn Type=3
Dn Slope=0.005

--- StreamM036.g01 (geometry) ---

Geom Title=Existing Conditions
Program Version=4.10

River Reach=StreamM036      ,Reach-1
Reach XY= 30
        2484025.       13857875.      2484026.03     13857778.48
      2484664.62     13857635.11      2484830.52     13857122.57
      2485221.69     13856723.27       2485134.3     13856418.33
      2485461.27      13855988.4      2485840.08     13855874.22
      2486135.55      13856023.9      2486723.72     13856021.63
      2487167.19     13855581.19      2487194.59     13855354.79
      2487664.53     13855034.82       2487824.4     13854386.85
      2487328.09     13853573.33      2487426.03     13853425.36
      2487326.76     13853231.12      2487832.81     13852368.81
      2488438.61     13851611.76      2488972.95     13851319.54
      2488766.98     13850818.66      2488576.04     13850664.57
      2488675.49      13849709.8      2488575.94     13849485.49
      2488825.48     13849145.16      2488432.82     13848878.41
      2488371.39     13847826.48      2487361.43     13847061.53
      2487158.37     13846708.29        2486975.       13846625.

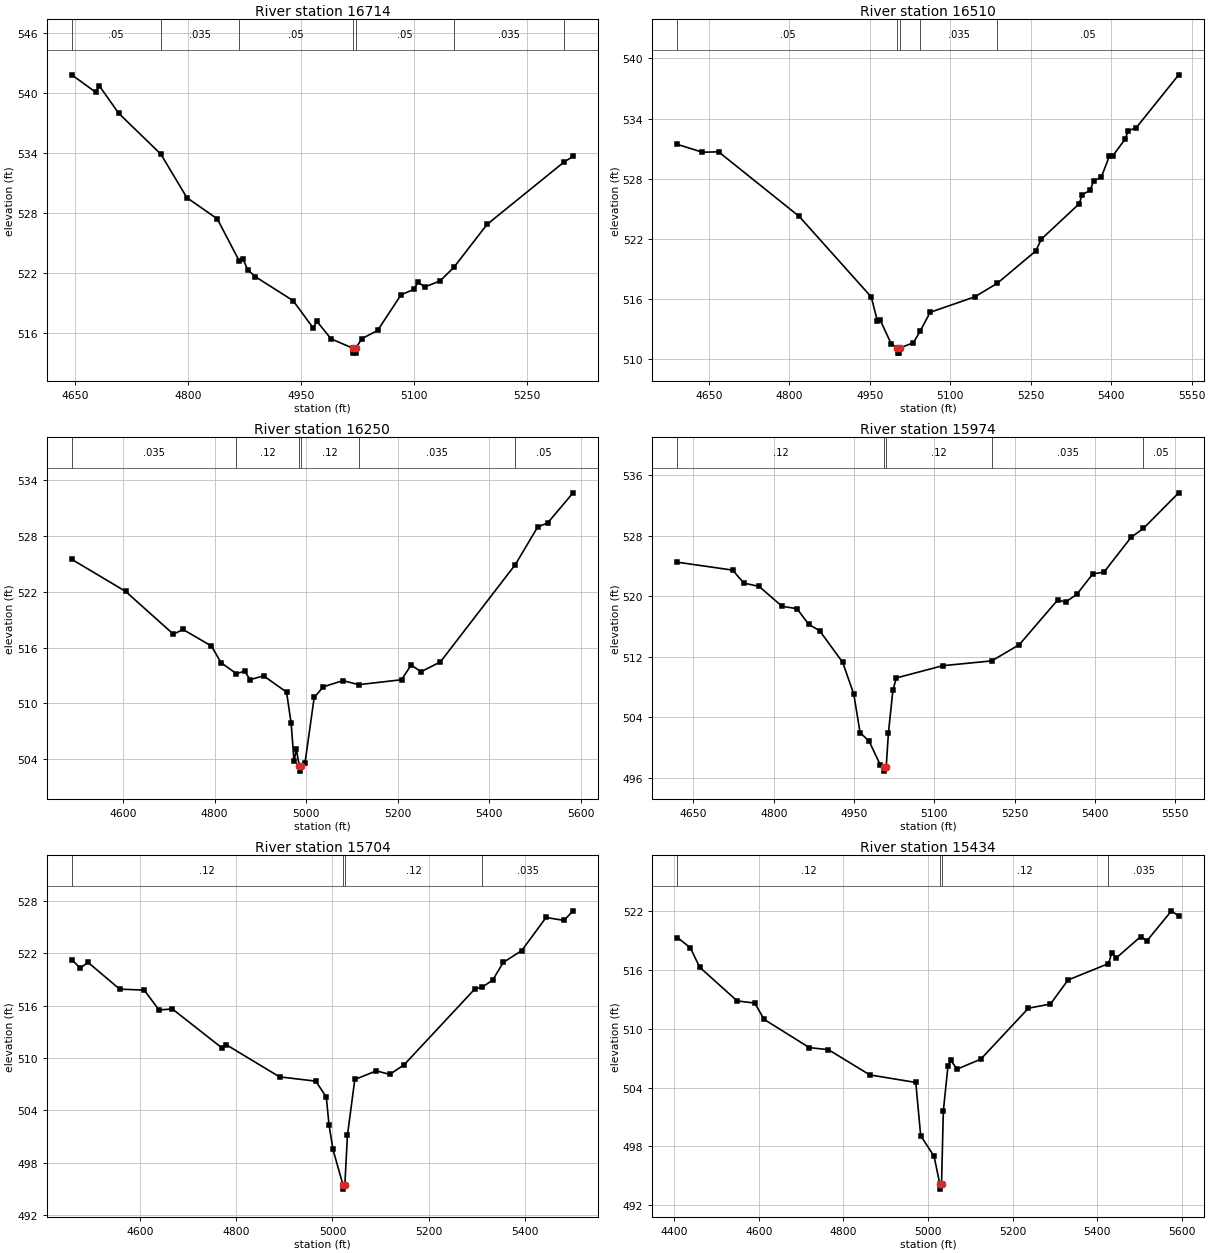
Type RM Length L Ch R = 1 ,16714   ,204,204,204
BEGIN DESCRIPTION:
StreamM036 34.0
END DESCRIPTION:
XS GIS Cut Line= 3
      2484143.78     13858126.97      2484106.43      13857773.4
      2484024.99     13857474.95
#Sta/Elev= 30
  4645.9  541.85  4677.5  540.12  4682.5  540.75  4708.2     538    4764  533.92
  4798.7  529.55  4838.9  527.44  4868.1  523.22  4873.2  523.39  4879.2  522.35
  4889.2  521.66  4939.5  519.25  4966.1  516.52  4971.1  517.18  4989.8  515.43
  5018.5   514.5  5018.8     514  5022.3     514  5022.5   514.5    5031  515.46
  5051.6  516.27  5082.7  519.84    5100  520.39  5105.2  521.13  5113.8  520.61
  5134.5  521.23  5152.9   522.6  5196.7  526.88  5299.1  533.14  5310.8  533.68
#Mann= 7 ,-1 , 0
  4645.9     .05       0    4764    .035       0  4868.1     .05       0
  5018.5     .05       0  5022.5     .05       0  5152.9    .035       0
  5299.1     .05       0
Bank Sta=5018.5,5022.5
XS Rating Curve= 0 ,0
Exp/Cntr=0.3,0.1

Type RM Length L Ch R = 1 ,16510   ,260,260,260
BEGIN DESCRIPTION:
H21290
END DESCRIPTION:
XS GIS Cut Line= 4
      2484338.01     13858181.78      2484323.07     13857820.71
      2484233.43       13857497.      2484093.96     13857305.22
#Sta/Elev= 30
  4591.5  531.42  4638.3  530.64  4668.3  530.68  4818.5  524.24  4952.9   516.2
  4964.2  513.83  4969.4  513.91  4989.9  511.55  5001.7   511.1  5001.9   510.6
  5005.4   510.6  5005.7   511.1  5031.4  511.64  5044.6  512.85  5062.6  514.67
  5145.6  516.21  5187.9  517.57  5259.3  520.78  5270.1  521.98  5340.1  525.48
  5346.2  526.41  5360.9  526.84  5367.1  527.76  5381.8  528.17  5396.5  530.23
  5402.7  530.25  5425.8  531.93    5432  532.78  5446.7  533.08  5525.9  538.36
#Mann= 5 ,-1 , 0
  4591.5     .05       0  5001.7     .05       0  5005.7     .05       0
  5044.6    .035       0  5187.9     .05       0
Bank Sta=5001.7,5005.7
XS Rating Curve= 0 ,0
Exp/Cntr=0.3,0.1

Type RM Length L Ch R = 1 ,16250   ,276,276,276
BEGIN DESCRIPTION:
H21289
END DESCRIPTION:
XS GIS Cut Line= 4
      2484447.57     13858199.24      2484557.14     13857800.79
      2484537.22      13857596.6      2484225.96     13857235.54
#Sta/Elev= 30
    4488  525.51  4605.8  522.05  4710.2  517.44  4730.9  517.96  4793.2  516.17
  4813.9  514.39  4847.5   513.2  4865.8  513.46  4877.8  512.55  4907.1  512.96
  4957.3  511.21  4967.3  507.84  4973.6  503.76  4978.6  505.03  4985.4   503.2
  4985.7   502.7  4989.4   503.2  4997.5  503.56  5017.6  510.64  5037.7  511.78
  5080.3  512.45  5114.7  512.01  5208.4  512.54  5229.3  514.12  5251.2  513.41
  5293.3  514.46  5457.1  524.95  5505.8  528.99  5527.7  529.43  5583.1  532.67
#Mann= 6 ,-1 , 0
    4488    .035       0  4847.5     .12       0  4985.4     .05       0
  4989.4     .12       0  5114.7    .035       0  5457.1     .05       0
Bank Sta=4985.4,4989.4
XS Rating Curve= 0 ,0
Exp/Cntr=0.3,0.1

Type RM Length L Ch R = 1 ,15974   ,270,270,270
BEGIN DESCRIPTION:
H21288
END DESCRIPTION:
XS GIS Cut Line= 3
      2484985.45      13857749.5      2484723.98     13857527.88
       2484236.5     13857189.62
#Sta/Elev= 30
  4620.1  524.51  4723.3  523.46  4744.1  521.75  4772.7   521.3  4815.6  518.67
  4843.5  518.36    4865  516.31  4885.8  515.43  4928.7  511.27  4949.5  507.05
  4961.2  501.97  4978.3  500.79  4999.2  497.65    5006  497.36  5006.2  496.86
    5010  497.36  5014.1  501.85  5022.5  507.54  5028.9  509.19  5115.4  510.81
  5207.2  511.45  5258.6   513.6  5330.2  519.51    5345  519.23    5366  520.26
  5395.7  522.96  5416.6  523.19  5467.3   527.8  5490.4  528.99  5556.2  533.69
#Mann= 5 ,-1 , 0
  4620.1     .12       0    5006     .05       0    5010     .12       0
  5207.2    .035       0  5490.4     .05       0
Bank Sta=5006,5010
XS Rating Curve= 0 ,0
Exp/Cntr=0.3,0.1

Type RM Length L Ch R = 1 ,15704   ,270,270,270
BEGIN DESCRIPTION:
H21287
END DESCRIPTION:
XS GIS Cut Line= 3
      2485087.55     13857697.23      2484880.86     13857316.22
      2484345.59     13857029.91
#Sta/Elev= 30
  4458.8  521.25  4476.5   520.3  4492.7  520.94  4558.3  517.88  4609.2  517.77
    4640  515.49  4667.6  515.61  4771.2  511.12  4779.9   511.5  4890.1  507.83
  4965.2  507.34  4987.1  505.53  4992.8  502.34    5001  499.51  5021.7  495.47
  5021.9  494.97  5025.7  495.47    5031  501.12  5046.3  507.53  5091.1  508.52
  5118.8  508.11  5148.4   509.2  5295.8  517.92  5310.8  518.11  5332.5  518.91
  5354.4  520.94  5392.7  522.29  5443.3  526.09  5480.4  525.75  5499.3  526.85
#Mann= 4 ,-1 , 0
  4458.8     .12       0  5021.7     .05       0  5025.7     .12       0
  5310.8    .035       0
Bank Sta=5021.7,5025.7
XS Rating Curve= 0 ,0
Exp/Cntr=0.3,0.1

Type RM Length L Ch R = 1 ,15434   ,317,317,317
BEGIN DESCRIPTION:
H21286
END DESCRIPTION:
XS GIS Cut Line= 3
      2485453.58     13857273.88       2484793.7      13856992.5
      2484343.02     13856865.51
#Sta/Elev= 30
  4407.4  519.29  4437.9  518.25  4460.2  516.26  4548.7  512.83  4590.5  512.61
  4612.4  510.95  4719.5  508.07  4764.6  507.86  4862.5  505.29  4971.2  504.52
  4982.8   499.1  5014.6  496.98  5028.1  494.15  5028.3  493.65  5032.1  494.15
  5036.4  501.63  5047.3  506.17  5053.7  506.79    5069  505.88  5124.8  506.89
  5237.7  512.09  5289.7  512.51  5331.2  514.96  5426.8  516.63  5435.1  517.76
  5445.5  517.21  5502.7  519.37  5518.2  518.97  5575.9  522.01    5593  521.47
#Mann= 4 ,-1 , 0
  4407.4     .12       0  5028.1     .05       0  5032.1     .12       0
  5426.8    .035       0
Bank Sta=5028.1,5032.1
XS Rating Curve= 0 ,0
Exp/Cntr=0.3,0.1

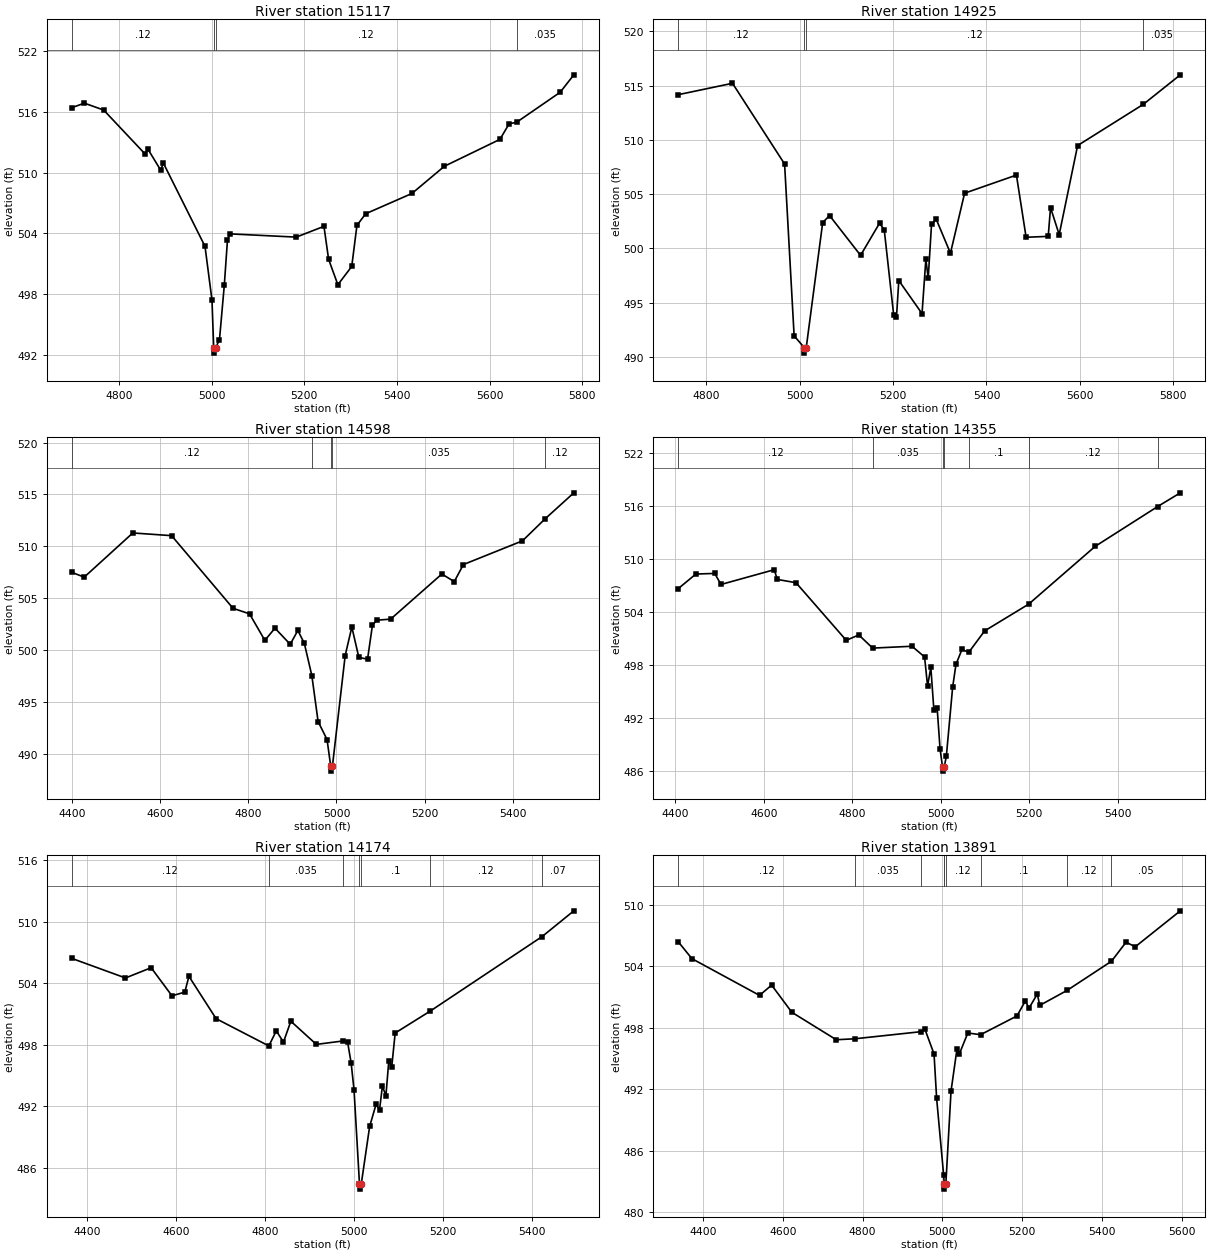
Type RM Length L Ch R = 1 ,15117   ,192,192,192
BEGIN DESCRIPTION:
H21285
END DESCRIPTION:
XS GIS Cut Line= 3
      2485441.11     13856935.22      2485000.38     13856805.74
      2484375.38     13856823.17
#Sta/Elev= 30
  4697.6  516.39  4724.8  516.84  4766.5  516.16  4856.6   511.8  4861.8  512.33
  4889.9  510.22  4895.2  510.96  4985.4  502.73  5000.5  497.43  5004.2  492.71
  5004.5  492.21  5008.2  492.71  5016.7  493.55  5027.1   498.9  5033.9  503.32
  5039.1  503.96  5182.4  503.64  5242.4   504.7  5252.4  501.46  5272.4  498.95
  5302.4  500.75  5313.6  504.79  5332.4  505.94  5432.4  507.94  5502.5  510.62
  5622.5  513.27  5642.5  514.81  5658.4  514.95  5752.6  517.91  5782.2  519.63
#Mann= 4 ,-1 , 0
  4697.6     .12       0  5004.2     .05       0  5008.2     .12       0
  5658.4    .035       0
Bank Sta=5004.2,5008.2
XS Rating Curve= 0 ,0
Exp/Cntr=0.3,0.1

Type RM Length L Ch R = 1 ,14925   ,327,327,327
BEGIN DESCRIPTION:
H21284
END DESCRIPTION:
XS GIS Cut Line= 3
      2485478.52     13856731.05      2485154.77     13856668.79
      2484418.89     13856783.15
#Sta/Elev= 30
  4740.4  514.17  4856.5  515.22    4968  507.78  4988.4  491.94  5010.3  490.85
  5010.5  490.35  5014.3  490.85  5049.5  502.38  5064.2  503.03  5130.6  499.36
  5171.1  502.32  5181.2  501.73  5201.4  493.87  5207.4  493.64  5212.4  497.04
  5262.1  493.99  5270.3  499.01  5275.3  497.23  5282.4  502.22  5292.5  502.69
  5322.9  499.56  5353.2  505.09  5464.1  506.76  5484.8  501.03  5532.1  501.11
  5537.1  503.76  5555.6  501.27    5595  509.48  5735.6  513.28  5814.8     516
#Mann= 4 ,-1 , 0
  4740.4     .12       0  5010.3     .05       0  5014.3     .12       0
  5735.6    .035       0
Bank Sta=5010.3,5014.3
XS Rating Curve= 0 ,0
Exp/Cntr=0.3,0.1

Type RM Length L Ch R = 1 ,14598   ,243,243,243
BEGIN DESCRIPTION:
H21283
END DESCRIPTION:
XS GIS Cut Line= 3
      2485665.22     13856693.67      2485226.99     13856442.18
      2484611.94     13856285.31
#Sta/Elev= 30
    4399  507.51  4427.3  507.05  4537.6   511.3  4625.7  511.04  4765.2  504.05
  4802.6  503.52  4837.4  500.97  4860.4  502.14    4895  500.59  4912.3  501.92
    4927  500.69  4944.1  497.58  4958.3  493.16  4978.6  491.43  4986.9  488.89
  4987.1  488.39  4990.9  488.89  5019.8  499.51  5034.9  502.25  5050.8  499.33
  5070.6  499.16  5081.8  502.46  5092.1  502.91    5123  503.01  5239.3  507.35
  5267.5  506.62  5288.2  508.26  5422.3  510.54  5474.3  512.68    5539  515.16
#Mann= 5 ,-1 , 0
    4399     .12       0  4944.1    .035       0  4986.9    .035       0
  4990.9    .035       0  5474.3     .12       0
Bank Sta=4986.9,4990.9
XS Rating Curve= 0 ,0
Exp/Cntr=0.3,0.1

Type RM Length L Ch R = 1 ,14355   ,181,181,181
BEGIN DESCRIPTION:
H21282
END DESCRIPTION:
XS GIS Cut Line= 3
      2485675.21     13856671.28      2485236.95      13856185.7
      2484802.18      13855979.5
#Sta/Elev= 30
  4406.6  506.66  4446.5  508.31  4489.1  508.38  4503.3  507.13  4623.6   508.8
  4630.6   507.7  4672.9  507.33  4786.5  500.81  4814.9  501.42  4846.2  499.93
  4935.2  500.14  4963.6  498.93  4970.4  495.65  4977.8  497.74  4984.6  492.96
    4992  493.19  4998.7  488.48  5004.2  486.51  5004.5  486.01  5008.2  486.51
  5012.9  487.72  5027.1  495.51  5034.6  498.09  5048.2  499.78  5063.5  499.45
  5099.5  501.88  5198.9   504.9  5349.6  511.45  5490.4  515.94  5541.9   517.5
#Mann= 7 ,-1 , 0
  4406.6     .12       0  4846.2    .035       0  5004.2    .035       0
  5008.2    .035       0  5063.5      .1       0  5198.9     .12       0
  5490.4     .07       0
Bank Sta=5004.2,5008.2
XS Rating Curve= 0 ,0
Exp/Cntr=0.3,0.1

Type RM Length L Ch R = 1 ,14174   ,283,283,283
BEGIN DESCRIPTION:
H21281
END DESCRIPTION:
XS GIS Cut Line= 3
      2485700.09     13856646.34      2485495.92     13856178.23
      2485018.88     13855785.67
#Sta/Elev= 30
  4365.9  506.44  4486.6  504.53  4544.3  505.53  4591.1  502.79    4620  503.15
  4629.2  504.69  4690.3  500.56  4808.8   497.9  4825.6  499.37  4841.7  498.27
  4858.3  500.31  4915.6  498.05  4974.8  498.38  4985.9  498.27  4993.8  496.25
  5000.3  493.63  5012.6  484.43  5012.9  483.93  5016.6  484.43  5035.4  490.04
  5049.8   492.2  5057.6  491.66  5064.1  493.98    5072  493.04  5078.5  496.46
    5085  495.83  5092.8  499.16    5172  501.31  5423.1  508.57  5494.4  511.08
#Mann= 7 ,-1 , 0
  4365.9     .12       0  4808.8    .035       0  4974.8      .1       0
  5012.6     .05       0  5016.6      .1       0    5172     .12       0
  5423.1     .07       0
Bank Sta=5012.6,5016.6
XS Rating Curve= 0 ,0
Exp/Cntr=0.3,0.1

Type RM Length L Ch R = 1 ,13891   ,276,276,276
BEGIN DESCRIPTION:
H21280
END DESCRIPTION:
XS GIS Cut Line= 3
      2485734.97     13856646.36      2485647.81     13856091.08
      2485261.87     13855510.91
#Sta/Elev= 30
  4337.7  506.39  4372.1  504.74  4541.5  501.16  4571.9  502.16  4622.5  499.51
  4733.9  496.83  4779.9  496.92  4947.5  497.62  4955.6  497.92  4979.1  495.44
  4985.6   491.1  5003.2  483.62  5004.7  482.75  5004.9  482.25  5008.7  482.75
  5021.7  491.82  5036.7  495.95  5042.7  495.46  5063.8  497.49  5095.7  497.32
    5187  499.15  5208.1  500.62  5217.1  499.91  5238.1  501.29  5244.1  500.18
  5312.5  501.64    5424  504.49  5460.6  506.35  5483.6   505.9  5596.6  509.41
#Mann= 9 ,-1 , 0
  4337.7     .12       0  4779.9    .035       0  4947.5      .1       0
  5003.2     .12       0  5004.7     .05       0  5008.7     .12       0
  5095.7      .1       0  5312.5     .12       0    5424     .05       0
Bank Sta=5004.7,5008.7
XS Rating Curve= 0 ,0
Exp/Cntr=0.3,0.1

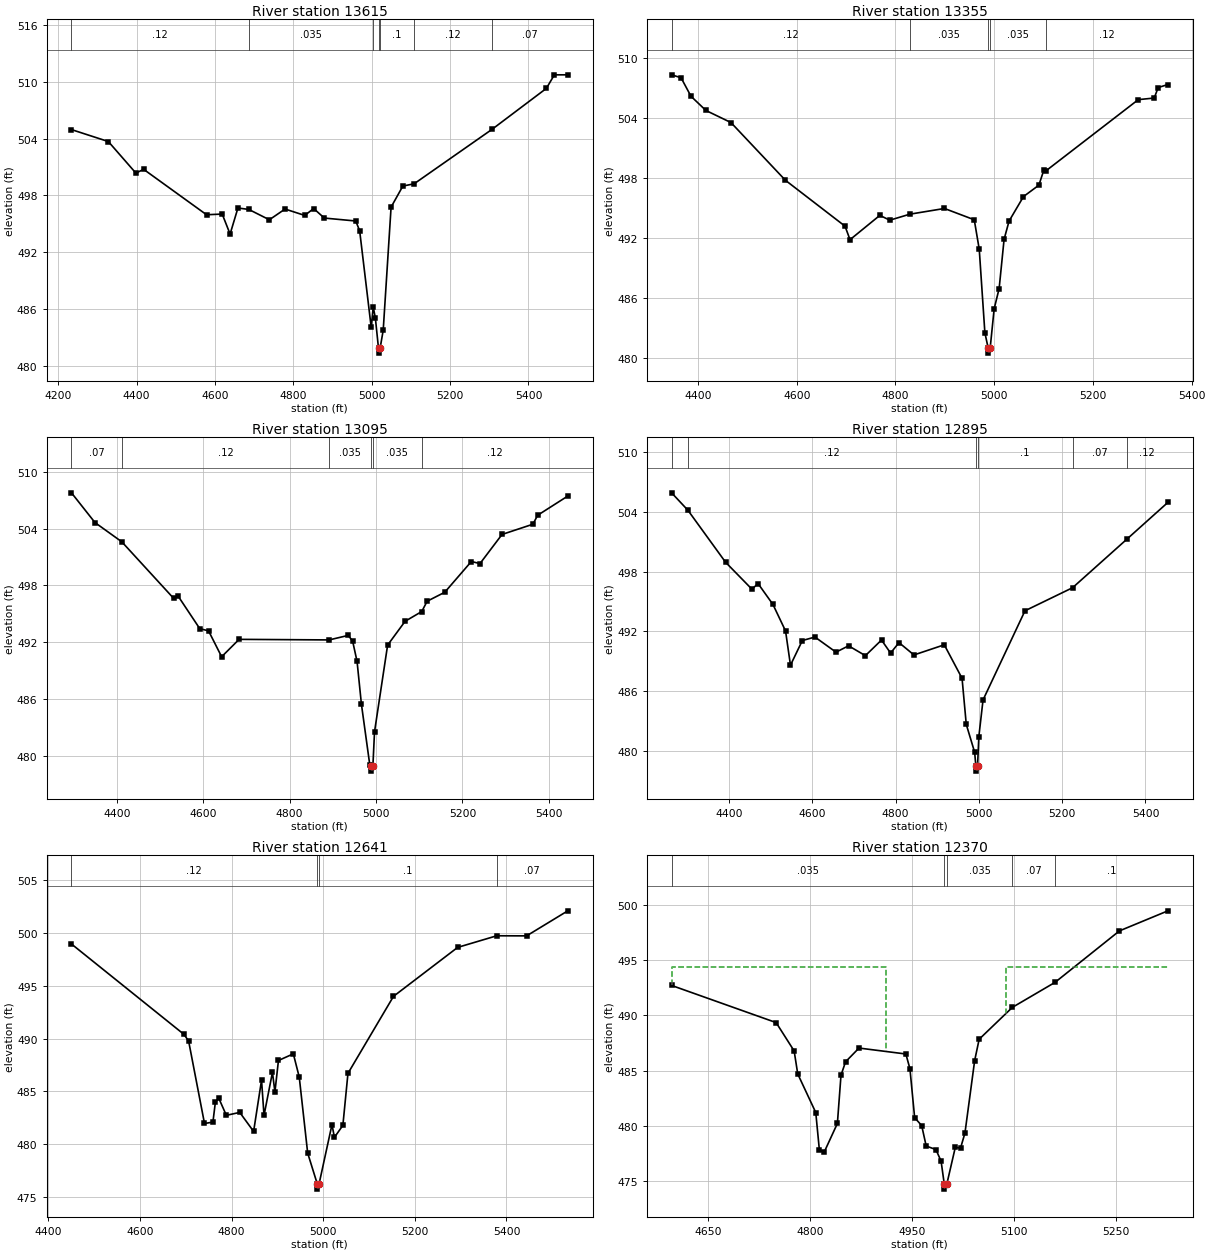
Type RM Length L Ch R = 1 ,13615   ,260,260,260
BEGIN DESCRIPTION:
H21279
END DESCRIPTION:
XS GIS Cut Line= 3
      2485769.83     13856638.92       2485827.1     13855762.38
      2485901.82     13855381.35
#Sta/Elev= 30
  4233.6  504.94  4327.7  503.68  4397.9  500.36  4417.9  500.75  4578.3  495.97
  4618.3  496.04  4638.4  493.93  4658.4  496.68  4686.1  496.53  4738.6  495.44
  4778.7  496.57  4828.8   495.9  4851.8  496.62  4878.9  495.62  4959.1  495.31
  4969.1  494.28  4998.6  484.09  5003.7  486.25  5009.2  485.08  5017.2  481.89
  5017.4  481.39  5021.2  481.89  5029.2   483.8  5049.3  496.77  5079.3  498.99
  5108.1  499.23  5307.4  504.98  5445.6  509.28    5466  510.71  5500.3  510.71
#Mann= 7 ,-1 , 0
  4233.6     .12       0  4686.1    .035       0  5003.7      .1       0
  5017.2    .035       0  5021.2      .1       0  5108.1     .12       0
  5307.4     .07       0
Bank Sta=5017.2,5021.2
XS Rating Curve= 0 ,0
Exp/Cntr=0.3,0.1

Type RM Length L Ch R = 1 ,13355   ,260,260,260
BEGIN DESCRIPTION:
H21278
END DESCRIPTION:
XS GIS Cut Line= 2
      2485966.55     13856623.96      2486083.59      13855625.4
#Sta/Elev= 30
  4346.5  508.32  4365.6  508.03  4385.7  506.18  4415.9  504.76  4466.7  503.55
    4577  497.78  4697.8  493.19  4707.9  491.84  4768.3  494.27  4788.5  493.79
  4829.2  494.39  4899.2  494.96  4959.6  493.83  4969.7  490.88  4981.1  482.54
  4987.8     481  4988.1   480.5  4991.8     481  4999.9  484.93    5010  486.96
    5020  491.87  5030.1   493.7  5059.3  496.15  5090.5  497.29  5100.6  498.81
  5104.5  498.71  5291.9  505.84  5324.1     506  5332.2  507.05  5351.9  507.35
#Mann= 5 ,-1 , 0
  4346.5     .12       0  4829.2    .035       0  4987.8    .035       0
  4991.8    .035       0  5104.5     .12       0
Bank Sta=4987.8,4991.8
XS Rating Curve= 0 ,0
Exp/Cntr=0.3,0.1

Type RM Length L Ch R = 1 ,13095   ,200,200,200
BEGIN DESCRIPTION:
H21277
END DESCRIPTION:
XS GIS Cut Line= 3
      2486168.25     13856678.73       2486280.3     13855921.75
       2486205.6     13855545.73
#Sta/Elev= 30
  4295.2  507.78  4349.5  504.64  4411.7   502.6  4531.5  496.63  4541.6  496.89
  4592.1  493.42  4612.4  493.19  4642.7  490.45  4683.1  492.29  4891.5  492.23
  4935.8  492.71  4945.9  492.09  4956.1  489.96  4966.2  485.43  4985.7  478.97
  4988.7  478.86    4989  478.36  4992.7  478.86  4996.5  482.51  5026.8  491.68
  5067.3   494.2  5105.8  495.23  5118.3  496.32  5159.1  497.27  5220.6  500.52
  5240.6   500.3  5291.6  503.38    5363  504.46  5374.1  505.41  5443.8  507.44
#Mann= 6 ,-1 , 0
  4295.2     .07       0  4411.7     .12       0  4891.5    .035       0
  4988.7    .035       0  4992.7    .035       0  5105.8     .12       0
Bank Sta=4988.7,4992.7
XS Rating Curve= 0 ,0
Exp/Cntr=0.3,0.1

Type RM Length L Ch R = 1 ,12895   ,254,254,254
BEGIN DESCRIPTION:
H21276
END DESCRIPTION:
XS GIS Cut Line= 3
      2486372.44     13856706.15      2486479.51      13855909.3
      2486313.12     13855559.13
#Sta/Elev= 30
  4262.2  505.91  4301.3  504.16  4391.8  498.93  4455.1  496.22  4469.7  496.79
  4505.5  494.69  4535.8  492.02  4547.6  488.58  4576.1  491.06  4606.4  491.41
  4656.9  489.89  4687.1  490.53  4727.5  489.54  4766.2  491.11    4788   489.8
  4808.2  490.85  4844.1  489.61  4916.9  490.63  4959.6  487.26  4969.7  482.63
  4989.8  479.83  4992.8  478.43  4993.1  477.93  4996.8  478.43  4999.9   481.4
    5010  485.09  5110.7  494.05    5225  496.37  5354.8  501.23  5453.9  504.95
#Mann= 6 ,-1 , 0
  4262.2     .07       0  4301.3     .12       0  4992.8    .035       0
  4996.8      .1       0    5225     .07       0  5354.8     .12       0
Bank Sta=4992.8,4996.8
XS Rating Curve= 0 ,0
Exp/Cntr=0.3,0.1

Type RM Length L Ch R = 1 ,12641   ,271,271,271
BEGIN DESCRIPTION:
H21275
END DESCRIPTION:
XS GIS Cut Line= 3
      2486920.25     13856531.81      2486648.84     13855881.91
      2486439.81     13855565.88
#Sta/Elev= 30
  4450.7  498.94  4696.5  490.38  4706.4  489.75    4741  481.96  4759.4  482.09
  4764.8     484  4772.3  484.34  4788.7  482.73  4817.9  483.01  4848.2  481.21
  4865.5  486.06  4870.9  482.72  4889.3   486.8  4894.7  484.94  4902.4  487.92
  4934.9  488.55  4947.8  486.35  4966.2  479.16  4987.1  476.25  4987.3  475.75
  4991.1  476.25  5019.2  481.85  5024.6  480.65    5043  481.78  5054.1   486.7
  5153.5  493.99  5293.5  498.62  5378.9  499.72    5444  499.71  5533.9  502.08
#Mann= 4 ,-1 , 0
  4450.7     .12       0  4987.1    .035       0  4991.1      .1       0
  5378.9     .07       0
Bank Sta=4987.1,4991.1
XS Rating Curve= 0 ,0
Exp/Cntr=0.3,0.1

Type RM Length L Ch R = 1 ,12370   ,259,259,259
BEGIN DESCRIPTION:
H21274
END DESCRIPTION:
XS GIS Cut Line= 3
      2487037.29     13856228.01      2486925.24     13855886.89
      2486643.85     13855645.34
#Sta/Elev= 30
  4596.9  492.72  4750.6  489.35  4777.1  486.78  4782.4  484.69  4808.9  481.19
  4814.2   477.8  4821.1  477.57  4840.7   480.2    4846  484.57  4852.7  485.79
  4872.5  487.04  4941.4   486.5  4947.4  485.16  4954.3  480.73  4964.7     480
  4971.3  478.15  4985.6  477.83  4993.2  476.78  4997.8  474.74  4998.1  474.24
  5001.8  474.74  5014.1  478.03  5021.8  477.96  5028.3  479.33  5042.6  485.91
  5049.2  487.84    5098  490.73  5160.8     493  5255.5  497.67  5326.8  499.49
#Mann= 5 ,-1 , 0
  4596.9    .035       0  4997.8    .035       0  5001.8    .035       0
    5098     .07       0  5160.8      .1       0
#XS Ineff= 2 , 0
       0    4912  494.42    5088       0  494.42
Permanent Ineff=
       F       F
Bank Sta=4997.8,5001.8
XS Rating Curve= 0 ,0
Exp/Cntr=0.3,0.1

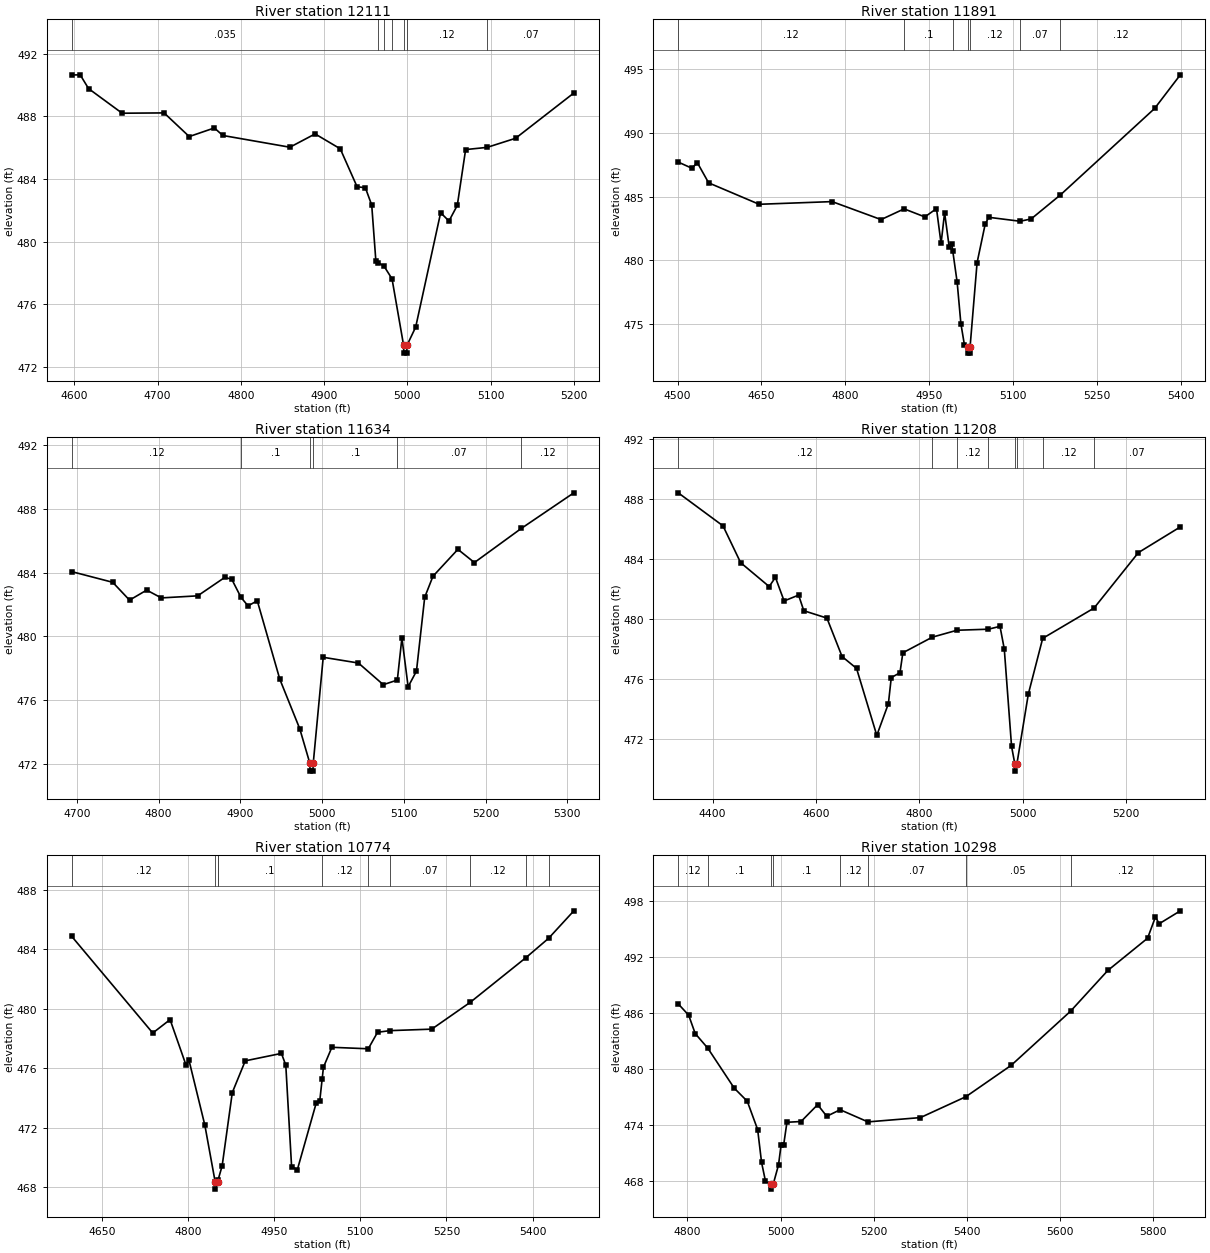
Type RM Length L Ch R = 1 ,12111   ,220,220,220
BEGIN DESCRIPTION:
StreamM036 24.0
END DESCRIPTION:
XS GIS Cut Line= 3
        2487125.     13856075.02        2487075.       13855675.
      2486875.03       13855675.
#Sta/Elev= 30
  4596.9  490.63    4607  490.64  4617.1  489.76  4657.4  488.19  4707.8  488.21
    4738   486.7  4768.2  487.25  4778.3  486.77  4858.9  486.02  4889.2  486.87
  4919.4  485.92  4939.6   483.5  4949.6  483.43  4957.2  482.33  4962.2  478.75
  4965.1  478.66  4972.1  478.42  4981.6  477.62  4995.5  473.38  4995.7  472.88
  4999.3  472.88  4999.6  473.38    5010  474.54    5040  481.84    5050  481.31
    5060  482.31    5070  485.87  5095.8  486.01    5130  486.59    5200  489.48
#Mann= 7 ,-1 , 0
  4596.9    .035       0  4965.1     .12       0  4972.1      .1       0
  4981.6     .12       0  4995.5     .05       0  4999.6     .12       0
  5095.8     .07       0
Bank Sta=4995.5,4999.6
XS Rating Curve= 0 ,0
Exp/Cntr=0.3,0.1

Type RM Length L Ch R = 1 ,11891   ,257,257,257
BEGIN DESCRIPTION:
H21273
END DESCRIPTION:
XS GIS Cut Line= 4
       2487313.7     13855939.15      2487281.33     13855575.62
      2487089.59     13855428.71      2486799.16     13855403.88
#Sta/Elev= 30
  4501.3   487.7  4525.5  487.22  4535.6  487.64  4555.7  486.07    4646  484.39
  4776.5   484.6  4864.1  483.19  4905.3  484.03  4942.4   483.4  4963.2  484.05
  4971.4  481.32  4977.7  483.73    4986  481.03  4990.6  481.26  4992.2  480.76
  5000.2  478.27  5006.8  475.04  5013.1  473.38  5019.2  473.22  5019.5  472.72
  5023.1  472.72  5023.3  473.22  5035.8  479.81  5050.3  482.83  5056.6  483.37
  5112.6  483.06  5132.5  483.24    5185  485.13  5353.3   491.9  5399.3  494.54
#Mann= 7 ,-1 , 0
  4501.3     .12       0  4905.3      .1       0  4992.2     .12       0
  5019.2     .05       0  5023.3     .12       0  5112.6     .07       0
    5185     .12       0
Bank Sta=5019.2,5023.3
XS Rating Curve= 0 ,0
Exp/Cntr=0.3,0.1

Type RM Length L Ch R = 1 ,11634   ,426,426,426
BEGIN DESCRIPTION:
StreamM036 23.0
END DESCRIPTION:
XS GIS Cut Line= 3
        2487361.      13855573.1        2487275.       13855275.
      2486974.99       13855225.
#Sta/Elev= 30
  4693.7  484.07  4743.8   483.4  4764.4  482.28  4785.4  482.91  4803.3  482.42
  4847.8  482.55    4881  483.71  4889.5  483.59  4900.8  482.45  4909.4  481.92
  4920.7  482.24  4948.3  477.31  4972.7   474.2    4985  472.04  4985.3  471.54
  4988.9  471.54  4989.2  472.04  5001.4  478.69  5044.5  478.33  5074.9  476.97
  5092.1  477.26  5097.7  479.91  5105.3  476.84  5115.5  477.82  5125.6  482.46
  5135.7  483.78  5166.2  485.47  5186.4  484.64  5243.7  486.78  5308.1  489.02
#Mann= 6 ,-1 , 0
  4693.7     .12       0  4900.8      .1       0    4985     .05       0
  4989.2      .1       0  5092.1     .07       0  5243.7     .12       0
Bank Sta=4985,4989.2
XS Rating Curve= 0 ,0
Exp/Cntr=0.3,0.1

Type RM Length L Ch R = 1 ,11208   ,434,434,434
BEGIN DESCRIPTION:
StreamM036 22.0
END DESCRIPTION:
XS GIS Cut Line= 3
       2488222.6     13855371.44        2487625.       13855075.
      2487325.02       13855025.
#Sta/Elev= 30
  4333.4   488.4    4420   486.2  4454.1  483.75  4509.3  482.16  4521.4  482.77
  4538.2   481.2  4566.2  481.59  4576.3  480.55    4621  480.06  4650.3   477.5
  4678.3  476.71  4717.5  472.25  4739.9  474.36  4745.5   476.1  4762.3  476.42
  4767.9  477.75  4824.9  478.79  4872.6  479.25  4933.4  479.32  4955.8  479.51
  4964.1     478  4978.2  471.51  4984.4  470.37  4984.7  469.87  4988.6  470.37
  5010.6     475  5038.4  478.71  5137.8  480.73  5223.5  484.42  5304.6  486.13
#Mann= 8 ,-1 , 0
  4333.4     .12       0  4824.9      .1       0  4872.6     .12       0
  4933.4      .1       0  4984.4     .05       0  4988.6      .1       0
  5038.4     .12       0  5137.8     .07       0
Bank Sta=4984.4,4988.6
XS Rating Curve= 0 ,0
Exp/Cntr=0.3,0.1

Type RM Length L Ch R = 1 ,10774   ,476,476,476
BEGIN DESCRIPTION:
StreamM036 21.0
END DESCRIPTION:
XS GIS Cut Line= 3
        2488125.       13854625.        2487725.       13854675.
      2487325.01       13854925.
#Sta/Elev= 30
  4597.2  484.86  4738.3  478.37  4768.5  479.27  4796.2  476.22  4801.3  476.56
    4829  472.19    4847  468.38  4847.3  467.88  4851.2  468.38  4851.9  468.47
  4859.2  469.44  4876.9  474.37  4899.5   476.5  4962.5     477  4970.1  476.21
  4980.2   469.4  4990.2  469.18  5023.3  473.69  5029.2  473.78  5033.5  475.29
  5035.7  476.07  5050.4  477.41  5113.8  477.31    5130  478.42  5151.8  478.53
  5224.4  478.63  5291.4  480.43  5388.4  483.43  5427.9  484.73    5472  486.58
#Mann= 10 ,-1 , 0
  4597.2     .12       0    4847     .05       0  4851.2     .12       0
  4851.9      .1       0  5033.5     .12       0  5113.8      .1       0
  5151.8     .07       0  5291.4     .12       0  5388.4     .07       0
  5427.9     .12       0
Bank Sta=4847,4851.2
XS Rating Curve= 0 ,0
Exp/Cntr=0.3,0.1

Type RM Length L Ch R = 1 ,10298   ,420,420,420
BEGIN DESCRIPTION:
StreamM036 20.0
END DESCRIPTION:
XS GIS Cut Line= 3
      2487925.03     13854174.98        2487725.       13854275.
      2486925.04     13854574.99
#Sta/Elev= 30
  4780.3  486.97  4802.7  485.76  4816.7   483.8  4843.8  482.23  4900.5  477.96
  4928.5  476.56  4950.8  473.53  4959.2  470.02  4967.6  468.01  4979.1  467.66
  4979.5  467.16  4984.1  467.66  4995.6  469.75  5001.1  471.87  5006.6  471.87
  5013.7  474.31    5044  474.39  5079.6  476.19  5099.2  474.95  5127.9  475.65
  5187.6  474.35  5300.3  474.81  5397.8  477.04  5495.2   480.4  5622.7  486.19
  5702.6  490.54    5788  493.99  5804.9  496.26    5813  495.54  5858.3  496.92
#Mann= 8 ,-1 , 0
  4780.3     .12       0  4843.8      .1       0  4979.1     .05       0
  4984.1      .1       0  5127.9     .12       0  5187.6     .07       0
  5397.8     .05       0  5622.7     .12       0
Bank Sta=4979.1,4984.1
XS Rating Curve= 0 ,0
Exp/Cntr=0.3,0.1

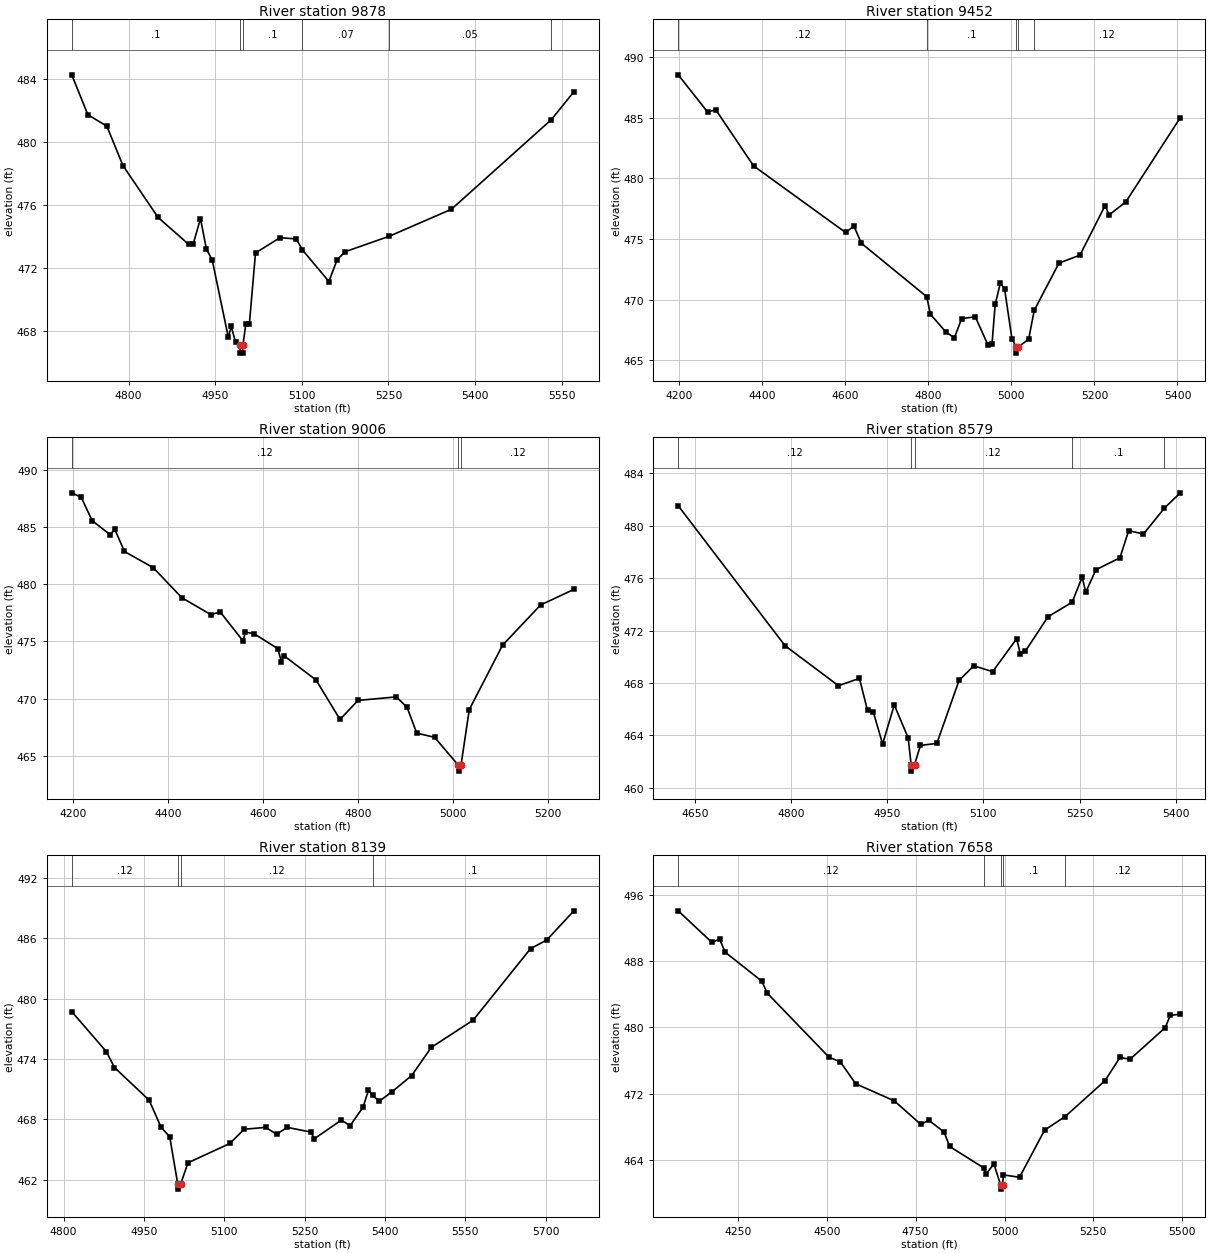
Type RM Length L Ch R = 1 ,9878    ,426,426,426
BEGIN DESCRIPTION:
StreamM036 19.0
END DESCRIPTION:
XS GIS Cut Line= 3
      2487824.98       13853975.        2487525.       13853925.
        2487125.       13854325.
#Sta/Elev= 30
  4701.4  484.29  4729.3  481.75  4762.2  481.02  4790.1  478.51  4850.9  475.21
  4904.1  473.49  4911.7  473.51  4924.4  475.14  4934.6   473.2  4944.7   472.5
  4972.6  467.58  4977.6  468.27  4985.2  467.26  4992.9  467.07  4993.3  466.57
  4997.5  466.57  4997.9  467.07    5003  468.44  5009.1  468.44  5019.7  472.95
  5062.1  473.92  5090.4  473.84  5100.8  473.15  5146.9  471.13  5161.1  472.52
  5175.2  473.03  5251.2  474.01  5359.1  475.73  5532.3  481.44  5571.2  483.21
#Mann= 6 ,-1 , 0
  4701.4      .1       0  4992.9     .05       0  4997.9      .1       0
  5100.8     .07       0  5251.2     .05       0  5532.3     .12       0
Bank Sta=4992.9,4997.9
XS Rating Curve= 0 ,0
Exp/Cntr=0.3,0.1

Type RM Length L Ch R = 1 ,9452    ,446,446,446
BEGIN DESCRIPTION:
StreamM036 18.0
END DESCRIPTION:
XS GIS Cut Line= 3
        2488125.       13853475.        2487325.       13853575.
      2486925.03       13853525.
#Sta/Elev= 30
  4197.5  488.53    4268  485.48  4288.2  485.64  4378.9  481.03  4600.6  475.54
  4620.8  476.07  4638.4  474.66  4796.3  470.24  4804.7  468.81  4842.5  467.33
  4862.6  466.87  4880.3  468.45    4913  468.59  4943.3  466.29  4953.3  466.37
  4960.9  469.62  4973.5  471.39  4983.6  470.87  5001.2   466.8  5011.2   466.1
  5011.6   465.6  5016.4   466.1  5041.5  466.75    5055  469.13  5114.6  473.02
    5165  473.67  5225.4  477.74  5235.5  476.99  5275.8  478.07  5406.8     485
#Mann= 5 ,-1 , 0
  4197.5     .12       0  4796.3      .1       0  5011.2     .05       0
  5016.4      .1       0    5055     .12       0
Bank Sta=5011.2,5016.4
XS Rating Curve= 0 ,0
Exp/Cntr=0.3,0.1

Type RM Length L Ch R = 1 ,9006    ,427,427,427
BEGIN DESCRIPTION:
StreamM036 17.0
END DESCRIPTION:
XS GIS Cut Line= 3
      2488124.95     13853324.99        2487325.       13853225.
      2487074.98       13853225.
#Sta/Elev= 30
  4197.8  487.97  4217.9  487.57  4240.6  485.54  4278.4  484.33  4288.5  484.77
  4308.6  482.85  4369.1  481.44  4429.5  478.81    4490  477.35  4510.2  477.56
    4558  475.05  4563.1   475.8  4580.7  475.69  4631.1  474.37  4638.7  473.24
  4643.7  473.77  4711.7  471.63  4762.1  468.19  4799.9  469.85  4880.5  470.16
  4903.2  469.25  4923.4     467  4961.1  466.63  5011.3  464.18  5011.7  463.68
  5016.6  464.18    5034  469.05    5104  474.67    5184  478.18    5254  479.54
#Mann= 3 ,-1 , 0
  4197.8     .12       0  5011.3     .05       0  5016.6     .12       0
Bank Sta=5011.3,5016.6
XS Rating Curve= 0 ,0
Exp/Cntr=0.3,0.1

Type RM Length L Ch R = 1 ,8579    ,440,440,440
BEGIN DESCRIPTION:
StreamM036 16.0
END DESCRIPTION:
XS GIS Cut Line= 3
      2487874.98     13853024.99        2487525.       13852875.
      2487174.99     13852674.99
#Sta/Elev= 30
  4623.5  481.52  4790.3  470.84  4873.7  467.79  4906.4  468.35    4919   465.9
  4928.1  465.78  4942.6  463.34  4960.8  466.32  4982.5  463.81  4987.1  461.77
  4987.5  461.27  4992.5  461.77  5001.6  463.23  5027.3  463.39  5061.9  468.19
  5084.9  469.31  5114.4  468.86  5151.8  471.37  5157.6  470.24  5165.5  470.43
  5200.8  473.05  5238.5  474.16  5254.1  476.07  5259.8  474.93  5275.7  476.64
  5313.1  477.55  5326.8  479.63  5349.8  479.36  5382.7  481.35  5407.4  482.51
#Mann= 5 ,-1 , 0
  4623.5     .12       0  4987.1     .05       0  4992.5     .12       0
  5238.5      .1       0  5382.7     .12       0
Bank Sta=4987.1,4992.5
XS Rating Curve= 0 ,0
Exp/Cntr=0.3,0.1

Type RM Length L Ch R = 1 ,8139    ,481,481,481
BEGIN DESCRIPTION:
StreamM036 15.0
END DESCRIPTION:
XS GIS Cut Line= 3
      2487975.03     13852675.02        2487825.       13852575.
      2487074.96     13852474.99
#Sta/Elev= 30
  4815.4   478.7    4880  474.72  4895.1  473.14  4959.7   469.9  4982.2  467.19
  4998.2  466.26  5013.2  461.55  5013.6  461.05  5018.6  461.55  5032.3  463.67
  5110.5  465.59    5137     467  5177.3  467.19  5197.5  466.51  5217.7  467.19
  5261.8  466.72  5268.1  466.06  5318.5  467.91  5334.9  467.36  5358.9  469.19
    5369  470.86  5376.9  470.36  5389.2  469.79  5413.1  470.73  5449.7  472.34
  5486.3  475.14  5564.5  477.85  5671.6  484.96  5701.9  485.82  5752.4  488.72
#Mann= 4 ,-1 , 0
  4815.4     .12       0  5013.2     .05       0  5018.6     .12       0
  5376.9      .1       0
Bank Sta=5013.2,5018.6
XS Rating Curve= 0 ,0
Exp/Cntr=0.3,0.1

Type RM Length L Ch R = 1 ,7658    ,421,421,421
BEGIN DESCRIPTION:
StreamM036 14.0
END DESCRIPTION:
XS GIS Cut Line= 3
      2488474.99     13852974.98        2488025.       13852175.
      2487675.02     13851825.02
#Sta/Elev= 30
  4081.9  494.07  4176.5  490.26  4198.2  490.65  4214.1  489.07  4316.8  485.58
  4332.7  484.11  4506.4  476.38    4538  475.82  4581.3  473.18    4690  471.11
  4764.9  468.26  4786.5  468.78  4829.9  467.35  4845.8   465.6  4941.3  463.02
  4948.4  462.28  4970.1   463.5  4989.1  460.95  4989.5  460.45  4994.5  460.95
  4996.9  462.17  5042.2  461.88  5112.9  467.58  5170.1   469.2  5282.6  473.54
    5325  476.36  5353.3  476.14  5452.3  479.96  5466.4  481.44  5494.7  481.58
#Mann= 5 ,-1 , 0
  4081.9     .12       0  4941.3      .1       0  4989.1     .05       0
  4994.5      .1       0  5170.1     .12       0
Bank Sta=4989.1,4994.5
XS Rating Curve= 0 ,0
Exp/Cntr=0.3,0.1