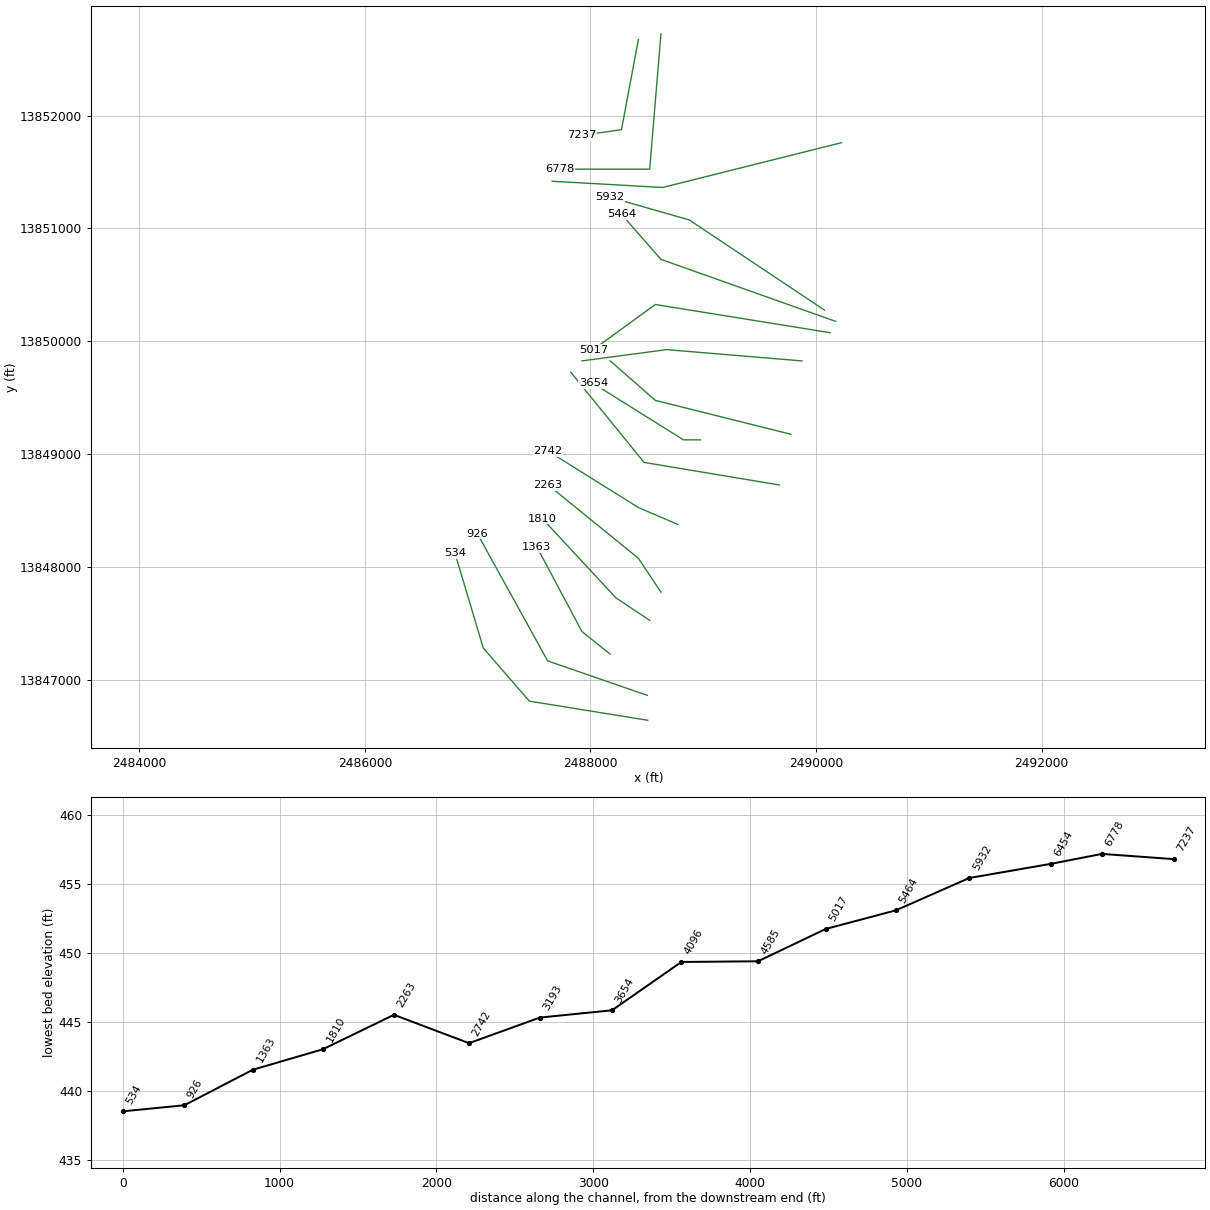
HEC-RAS study StreamM036.prj: StreamM036 Base Level Engineering

--- StreamM036.g01 (geometry) --- (continued)

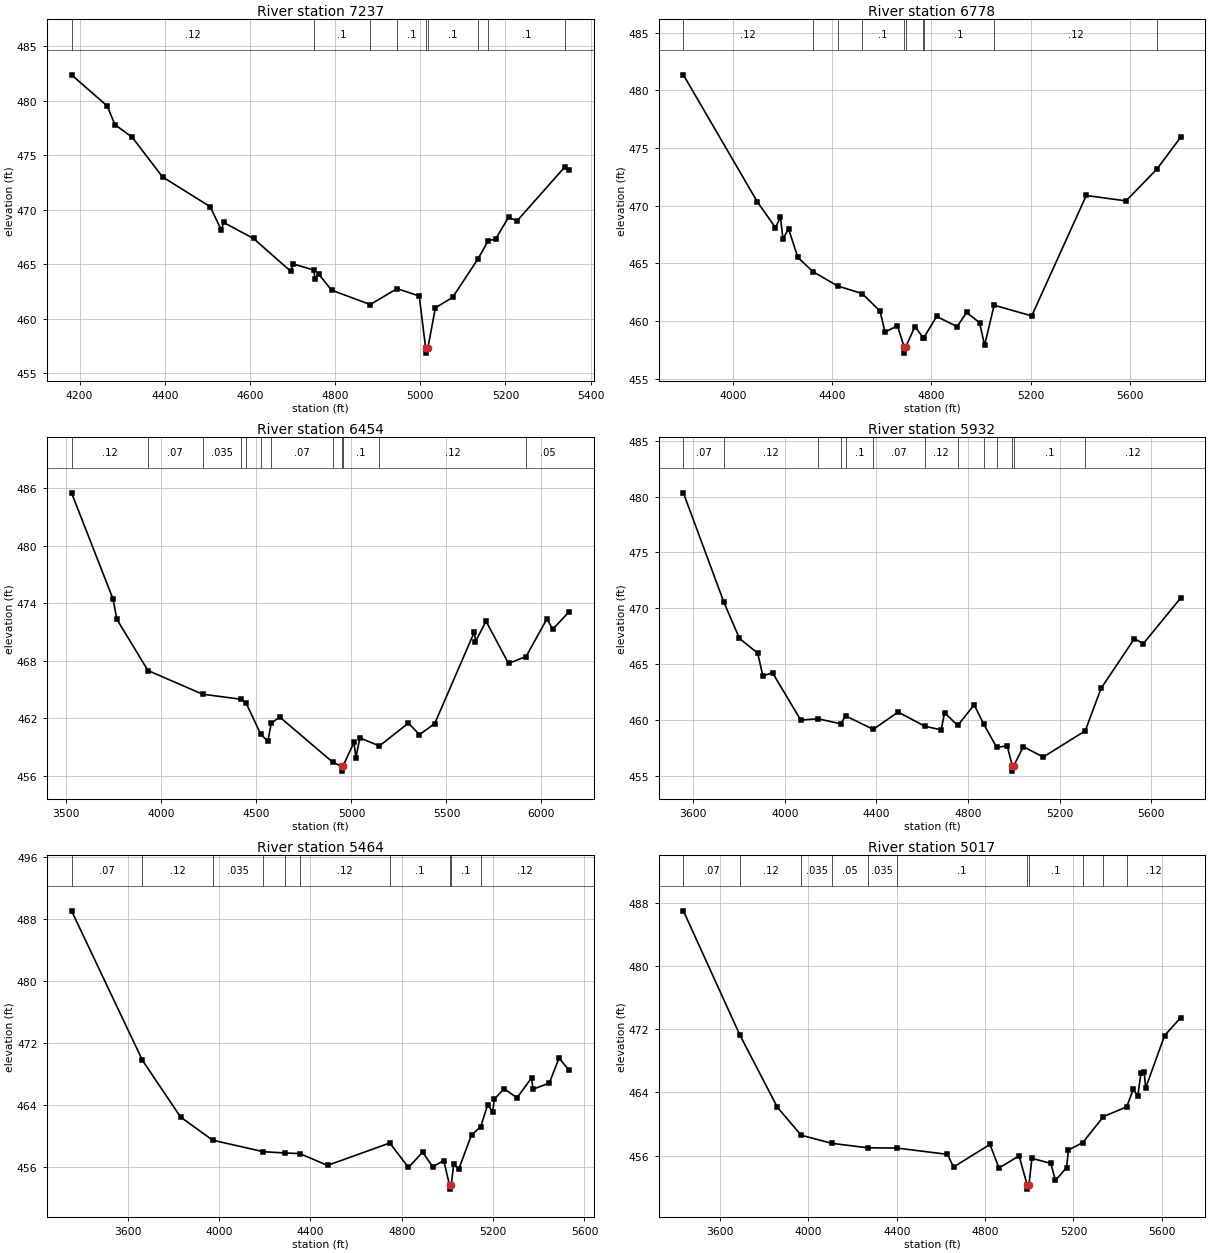
Type RM Length L Ch R = 1 ,7237    ,459,459,459
BEGIN DESCRIPTION:
StreamM036 13.0
END DESCRIPTION:
XS GIS Cut Line= 3
      2488425.01     13852675.05        2488275.       13851875.
      2487925.04     13851825.01
#Sta/Elev= 30
  4181.2  482.37  4265.2   479.5    4283   477.8  4323.7  476.64  4394.9     473
  4506.8  470.27  4533.1  468.11  4538.2  468.82  4608.6  467.35  4695.9  464.34
    4701  465.02  4749.5  464.46  4753.6  463.65  4761.2   464.1  4791.7  462.61
  4882.7  461.29  4945.7  462.75  4997.7  462.07  5012.6  457.33  5013.1  456.83
  5018.1  457.33  5035.6  460.99    5076  461.94    5136   465.5  5159.6  467.14
    5177   467.3  5207.3  469.29  5227.5  468.97  5340.1  473.94  5348.7  473.59
#Mann= 9 ,-1 , 0
  4181.2     .12       0  4749.5      .1       0  4882.7     .12       0
  4945.7      .1       0  5012.6     .05       0  5018.1      .1       0
    5136     .12       0  5159.6      .1       0  5340.1     .12       0
Bank Sta=5012.6,5018.1
XS Rating Curve= 0 ,0
Exp/Cntr=0.3,0.1

Type RM Length L Ch R = 1 ,6778    ,324,324,324
BEGIN DESCRIPTION:
StreamM036 12.0
END DESCRIPTION:
XS GIS Cut Line= 3
        2488625.     13852724.99        2488525.       13851525.
      2487725.05       13851525.
#Sta/Elev= 30
  3799.9  481.36  4098.4  470.33  4171.2   468.1  4191.2  469.01  4201.3  467.13
  4223.9  467.99  4261.5  465.51  4322.5  464.28  4421.5  463.04  4520.5  462.38
  4592.6  460.86  4612.7  459.04  4662.9  459.58  4690.2  457.71  4690.7  457.21
  4695.7  457.71  4733.1  459.52  4766.2  458.56  4769.4  458.56  4820.9  460.39
  4903.7  459.51  4941.3  460.74    4994  459.85    5014  457.89  5052.7  461.37
    5204  460.44    5424  470.89    5584  470.42  5708.7  473.18    5804  475.93
#Mann= 10 ,-1 , 0
  3799.9     .12       0  4322.5      .1       0  4421.5     .12       0
  4520.5      .1       0  4690.2     .05       0  4695.7      .1       0
  4766.2     .07       0  4769.4      .1       0  5052.7     .12       0
  5708.7     .05       0
Bank Sta=4690.2,4695.7
XS Rating Curve= 0 ,0
Exp/Cntr=0.3,0.1

Type RM Length L Ch R = 1 ,6454    ,522,522,522
BEGIN DESCRIPTION:
H21272
END DESCRIPTION:
XS GIS Cut Line= 3
      2490226.81     13851760.06       2488640.1     13851362.46
      2487660.82     13851417.69
#Sta/Elev= 30
  3526.9  485.53  3745.3  474.45  3765.9  472.32    3929  466.99  4216.2  464.52
  4417.9  463.99  4445.3  463.61  4522.2  460.36  4560.3  459.59  4577.5  461.46
  4621.5  462.15  4901.7  457.42  4947.8  456.99  4948.3  456.49  4955.1  456.99
  5013.3  459.49  5023.6  457.89  5044.2  459.96  5147.2  459.12  5299.8   461.5
  5358.1   460.3  5438.2  461.45  5647.6  471.04  5652.6  470.01  5708.6  472.13
  5826.6  467.73  5919.2  468.45  6029.1  472.39  6059.2  471.28  6143.5  473.08
#Mann= 12 ,-1 , 0
  3526.9     .12       0    3929     .07       0  4216.2    .035       0
  4417.9     .12       0  4445.3     .07       0  4522.2     .12       0
  4577.5     .07       0  4901.7      .1       0  4947.8     .05       0
  4955.1      .1       0  5147.2     .12       0  5919.2     .05       0
Bank Sta=4947.8,4955.1
XS Rating Curve= 0 ,0
Exp/Cntr=0.3,0.1

Type RM Length L Ch R = 1 ,5932    ,468,468,468
BEGIN DESCRIPTION:
StreamM036 11.0
END DESCRIPTION:
XS GIS Cut Line= 3
      2490074.98     13850275.02        2488875.       13851075.
        2488175.       13851275.
#Sta/Elev= 30
  3557.5  480.33  3734.1  470.57  3802.3  467.32    3882     466  3904.5  463.97
  3946.6  464.25  4069.8  460.02  4144.8  460.14  4244.5  459.69  4265.5   460.4
  4386.2  459.19  4494.9  460.74  4611.8  459.47  4682.7  459.15  4697.7  460.68
  4754.9  459.54  4826.9  461.38  4868.9  459.65  4925.1  457.58  4971.1  457.72
  4992.9  455.96  4993.4  455.46  5000.5  455.96  5041.3  457.65  5128.4  456.72
  5311.6  459.06  5380.6  462.85  5526.2   467.3  5565.2  466.85  5727.7  470.92
#Mann= 13 ,-1 , 0
  3557.5     .07       0  3734.1     .12       0  4144.8    .035       0
  4244.5     .12       0  4265.5      .1       0  4386.2     .07       0
  4611.8     .12       0  4754.9      .1       0  4868.9     .07       0
  4925.1      .1       0  4992.9     .05       0  5000.5      .1       0
  5311.6     .12       0
Bank Sta=4992.9,5000.5
XS Rating Curve= 0 ,0
Exp/Cntr=0.3,0.1

Type RM Length L Ch R = 1 ,5464    ,447,447,447
BEGIN DESCRIPTION:
StreamM036 10.0
END DESCRIPTION:
XS GIS Cut Line= 3
      2490175.01       13850175.        2488625.       13850725.
      2488275.01     13851124.99
#Sta/Elev= 30
  3354.8  489.06  3665.2  469.75  3832.3  462.41  3972.9  459.43  4194.9  457.94
  4289.7  457.78  4354.5   457.7  4475.2  456.17  4747.8  459.07  4829.7  455.91
  4891.5  457.89  4935.8     456  4984.1   456.8  5009.4  453.61  5009.9  453.11
  5017.1  453.61  5027.5  456.38  5049.3  455.66  5105.8  460.14  5145.1  461.12
  5176.5  464.02  5198.3  463.04    5205  464.71  5247.7  466.08  5304.6  464.91
  5368.2  467.47  5374.9  466.02  5446.1  466.81  5488.8  470.06    5531  468.49
#Mann= 10 ,-1 , 0
  3354.8     .07       0  3665.2     .12       0  3972.9    .035       0
  4194.9     .07       0  4289.7      .1       0  4354.5     .12       0
  4747.8      .1       0  5009.4     .05       0  5017.1      .1       0
  5145.1     .12       0
Bank Sta=5009.4,5017.1
XS Rating Curve= 0 ,0
Exp/Cntr=0.3,0.1

Type RM Length L Ch R = 1 ,5017    ,432,432,432
BEGIN DESCRIPTION:
StreamM036 9.0
END DESCRIPTION:
XS GIS Cut Line= 3
      2490125.03       13850075.        2488575.       13850325.
      2488025.03     13849925.02
#Sta/Elev= 30
  3434.4  486.96  3690.5  471.23  3859.9  462.11  3967.4  458.58  4106.4  457.55
  4268.2  456.99  4402.1  456.95  4629.7  456.16    4657  454.56  4822.1  457.41
  4862.6  454.43  4953.8  455.97  4990.5  452.26    4991  451.76  4998.2  452.26
  5011.8  455.65  5097.2  455.02  5118.4  452.87  5168.7  454.48  5177.2  456.71
  5242.1  457.65  5335.5  460.93  5440.8  462.17  5470.1  464.37  5490.9  463.54
  5505.6  466.46  5520.3  466.54  5526.5  464.55  5612.3  471.19  5684.5  473.43
#Mann= 11 ,-1 , 0
  3434.4     .07       0  3690.5     .12       0  3967.4    .035       0
  4106.4     .05       0  4268.2    .035       0  4402.1      .1       0
  4990.5     .05       0  4998.2      .1       0  5242.1     .12       0
  5335.5      .1       0  5440.8     .12       0
Bank Sta=4990.5,4998.2
XS Rating Curve= 0 ,0
Exp/Cntr=0.3,0.1

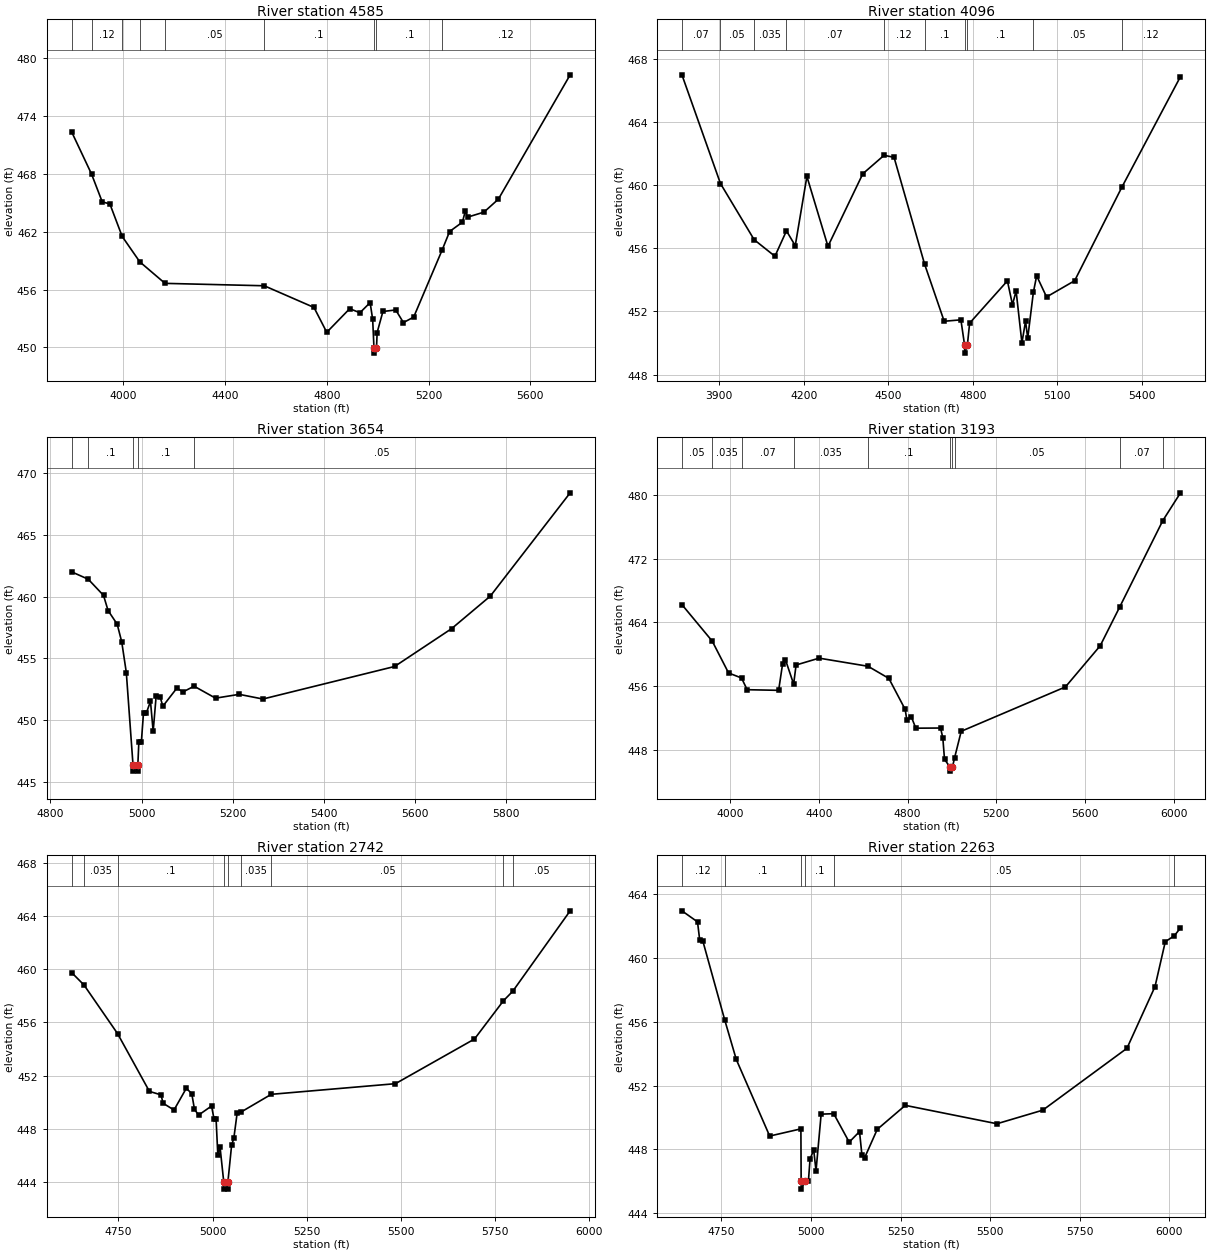
Type RM Length L Ch R = 1 ,4585    ,489,489,489
BEGIN DESCRIPTION:
StreamM036 8.0
END DESCRIPTION:
XS GIS Cut Line= 3
      2489875.03       13849825.        2488675.       13849925.
      2487925.03       13849825.
#Sta/Elev= 30
  3796.2  472.38  3874.7  467.99  3916.6  465.11  3946.8  464.89  3995.1  461.52
  4064.5  458.88  4163.6  456.65  4553.9   456.4  4749.5  454.15  4799.7  451.57
    4890  454.02  4930.1   453.6  4970.3  454.65  4980.3  452.91  4985.5  449.91
    4986  449.41  4995.3  449.91  4997.9  451.55  5020.6  453.73    5071  453.89
  5101.3  452.58  5141.6  453.15  5253.5  460.11  5282.9  462.03  5333.3     463
  5344.7  464.16  5353.5  463.52  5417.8  464.04  5474.5  465.38    5757  478.29
#Mann= 9 ,-1 , 0
  3796.2     .05       0  3874.7     .12       0  3995.1     .05       0
  4064.5    .035       0  4163.6     .05       0  4553.9      .1       0
  4985.5     .05       0  4995.3      .1       0  5253.5     .12       0
Bank Sta=4985.5,4995.3
XS Rating Curve= 0 ,0
Exp/Cntr=0.3,0.1

Type RM Length L Ch R = 1 ,4096    ,442,442,442
BEGIN DESCRIPTION:
StreamM036 7.0
END DESCRIPTION:
XS GIS Cut Line= 3
      2489775.02     13849174.99        2488575.       13849475.
      2488174.97     13849825.03
#Sta/Elev= 30
    3768     467  3904.7  460.11  4024.2  456.55  4097.9   455.5  4138.8  457.11
    4170  456.17  4211.3  460.56    4286  456.13  4409.7  460.73  4485.1   461.9
  4520.5  461.77  4628.8     455  4698.3  451.38  4757.6  451.47  4770.7  449.86
  4771.2  449.36  4780.5  449.86  4788.5  451.26  4922.5  453.94  4940.5  452.43
  4953.4   453.3    4974  450.01  4986.9  451.38  4994.6  450.31  5014.6  453.21
  5026.3  454.26  5061.4  452.92  5161.1  453.95    5328  459.86  5536.5  466.89
#Mann= 10 ,-1 , 0
    3768     .07       0  3904.7     .05       0  4024.2    .035       0
  4138.8     .07       0  4485.1     .12       0  4628.8      .1       0
  4770.7     .05       0  4780.5      .1       0  5014.6     .05       0
    5328     .12       0
Bank Sta=4770.7,4780.5
XS Rating Curve= 0 ,0
Exp/Cntr=0.3,0.1

Type RM Length L Ch R = 1 ,3654    ,461,461,461
BEGIN DESCRIPTION:
StreamM036 6.0
END DESCRIPTION:
XS GIS Cut Line= 3
      2488975.05       13849125.        2488825.       13849125.
      2488025.04     13849624.98
#Sta/Elev= 30
  4846.4  462.02  4882.9  461.42  4916.4  460.11  4926.4  458.88  4946.4  457.77
  4956.4  456.33  4966.4  453.85  4981.1  446.35  4981.6  445.85  4991.2  445.85
  4991.7  446.35  4993.9  448.22  4999.4  448.22  5004.1  450.57    5010  450.53
  5019.4  451.51  5025.3  449.08  5031.8  451.92  5040.7  451.84  5046.6  451.12
  5077.2  452.58  5090.8  452.28  5115.1  452.74  5162.1  451.77    5214  452.08
  5265.9   451.7  5554.8  454.34  5679.8  457.41  5764.7  460.05  5939.8  468.43
#Mann= 5 ,-1 , 0
  4846.4     .07       0  4882.9      .1       0  4981.1     .05       0
  4991.7      .1       0  5115.1     .05       0
Bank Sta=4981.1,4991.7
XS Rating Curve= 0 ,0
Exp/Cntr=0.3,0.1

Type RM Length L Ch R = 1 ,3193    ,451,451,451
BEGIN DESCRIPTION:
StreamM036 5.0
END DESCRIPTION:
XS GIS Cut Line= 3
      2489674.97       13848725.        2488475.       13848925.
        2487825.       13849725.
#Sta/Elev= 30
  3783.1  466.22  3919.6  461.64  3993.4  457.64  4051.7  457.01  4077.1  455.54
    4219  455.46  4236.7  458.75  4249.4  459.33  4286.7  456.24  4297.6  458.64
  4401.5   459.5  4622.1  458.48  4715.8  456.96  4789.3  453.07  4796.9  451.76
  4817.1  452.13  4837.4  450.71  4948.9  450.73  4959.1   449.5  4966.7   446.8
  4991.8  445.82  4992.3  445.32  5002.4  445.82    5012  446.98    5042  450.32
  5511.8  455.89  5668.4  461.05  5757.1  465.96  5950.6  476.76  6030.4  480.25
#Mann= 10 ,-1 , 0
  3783.1     .05       0  3919.6    .035       0  4051.7     .07       0
  4286.7    .035       0  4622.1      .1       0  4991.8     .05       0
  5002.4      .1       0    5012     .05       0  5757.1     .07       0
  5950.6     .12       0
Bank Sta=4991.8,5002.4
XS Rating Curve= 0 ,0
Exp/Cntr=0.3,0.1

Type RM Length L Ch R = 1 ,2742    ,479,479,479
BEGIN DESCRIPTION:
StreamM036 4.0
END DESCRIPTION:
XS GIS Cut Line= 3
      2488774.99       13848375.        2488425.       13848525.
      2487624.98     13849025.01
#Sta/Elev= 30
  4625.6  459.75  4658.6  458.81  4747.6  455.16  4832.3  450.81  4863.1  450.55
  4868.6  449.92  4897.6  449.41  4930.2  451.04  4944.7  450.65    4952  449.46
  4962.9  449.03  4997.3  449.71  5003.7  448.77  5009.3  448.77    5014  446.02
  5019.9  446.62  5029.9  443.96  5030.4  443.46  5040.1  443.46  5040.6  443.96
  5050.6  446.76  5056.5  447.29  5065.3  449.18  5075.8  449.26  5155.9  450.59
  5485.7  451.39  5695.7  454.75  5772.7  457.63  5797.3  458.34  5949.8  464.39
#Mann= 9 ,-1 , 0
  4625.6     .05       0  4658.6    .035       0  4747.6      .1       0
  5029.9     .05       0  5040.6      .1       0  5075.8    .035       0
  5155.9     .05       0  5772.7    .035       0  5797.3     .05       0
Bank Sta=5029.9,5040.6
XS Rating Curve= 0 ,0
Exp/Cntr=0.3,0.1

Type RM Length L Ch R = 1 ,2263    ,453,453,453
BEGIN DESCRIPTION:
StreamM036 3.0
END DESCRIPTION:
XS GIS Cut Line= 3
      2488624.99     13847775.01        2488425.       13848075.
      2487625.01     13848724.99
#Sta/Elev= 30
  4639.6  462.93  4683.1  462.24  4689.2   461.1  4698.2  461.02  4759.2  456.09
  4791.3  453.63  4884.5  448.84  4971.6  449.29  4972.3  446.02  4972.8  445.52
    4983  446.02  4992.6  446.03  4997.1  447.38  5007.3  447.99  5013.8  446.66
  5028.1  450.21  5063.2  450.24  5106.4  448.46  5135.2  449.12  5141.9  447.66
  5149.6  447.49  5184.7  449.26    5263  450.76  5518.7  449.61  5646.6  450.46
  5881.5  454.33  5959.8  458.19  5988.5     461  6013.7  461.37  6030.9  461.86
#Mann= 6 ,-1 , 0
  4639.6     .12       0  4759.2      .1       0  4972.3     .05       0
    4983      .1       0  5063.2     .05       0  6013.7     .12       0
Bank Sta=4972.3,4983
XS Rating Curve= 0 ,0
Exp/Cntr=0.3,0.1

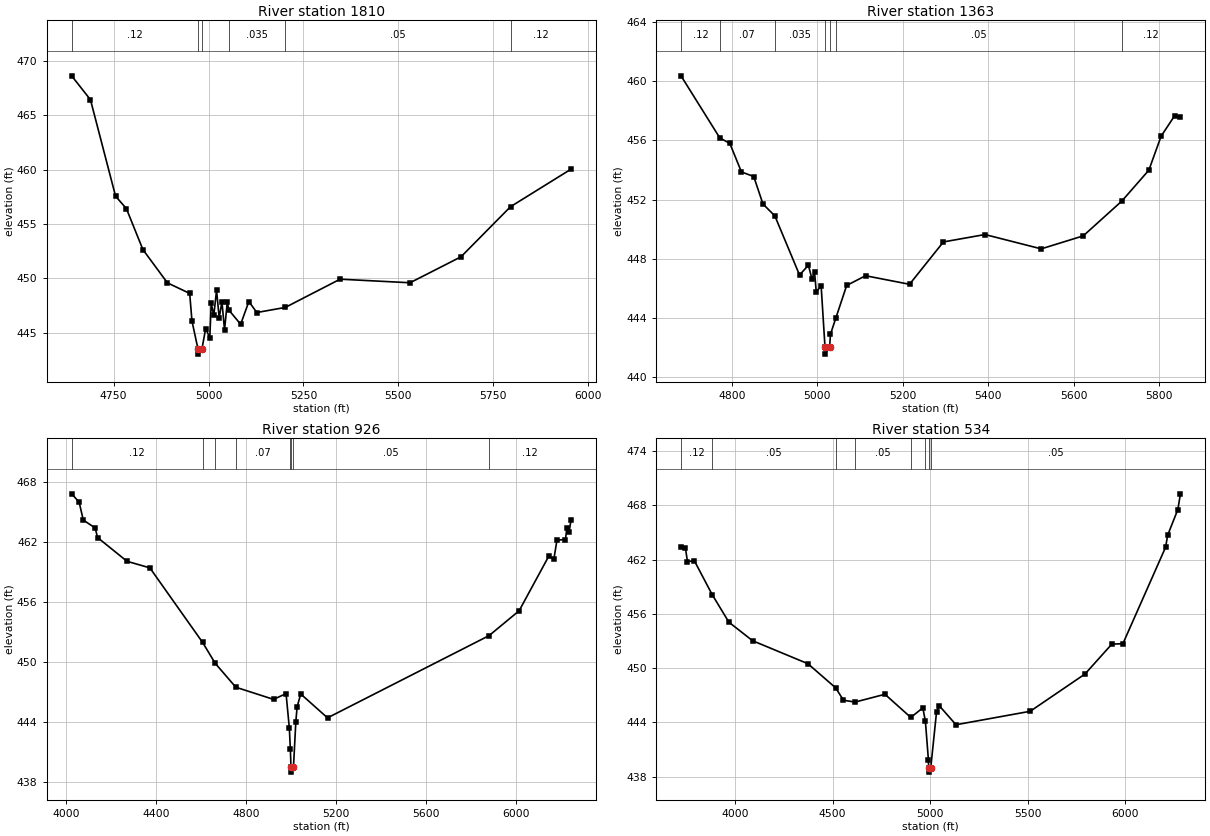
Type RM Length L Ch R = 1 ,1810    ,447,447,447
BEGIN DESCRIPTION:
StreamM036 2.0
END DESCRIPTION:
XS GIS Cut Line= 3
      2488525.02     13847524.99        2488225.       13847725.
      2487575.02     13848424.98
#Sta/Elev= 30
  4639.4  468.64    4689  466.44  4755.1  457.56  4783.6  456.42  4827.2  452.64
  4891.8  449.58  4950.4  448.61  4956.4  446.07  4972.1  443.52  4972.6  443.02
  4982.8  443.52  4992.5  445.37  5003.4  444.53  5007.1  447.69  5013.9   446.6
  5021.2   448.9  5028.1  446.36  5035.4  447.84  5042.2  445.25  5049.6  447.85
    5053   447.1  5084.7  445.77  5106.3  447.86  5127.3  446.85  5202.3  447.32
  5346.7  449.92  5530.9  449.59  5665.2  451.98  5795.6  456.59  5955.2  460.05
#Mann= 6 ,-1 , 0
  4639.4     .12       0  4972.1     .05       0  4982.8     .12       0
    5053    .035       0  5202.3     .05       0  5795.6     .12       0
Bank Sta=4972.1,4982.8
XS Rating Curve= 0 ,0
Exp/Cntr=0.3,0.1

Type RM Length L Ch R = 1 ,1363    ,437,437,437
BEGIN DESCRIPTION:
StreamM036 1.0
END DESCRIPTION:
XS GIS Cut Line= 3
      2488174.96     13847225.03        2487925.       13847425.
        2487525.     13848174.99
#Sta/Elev= 30
  4680.4  460.38  4771.2  456.18  4794.8   455.8    4822  453.87  4850.8  453.56
  4872.4   451.7  4900.3  450.89  4958.1  446.89  4978.9  447.55  4986.9  446.65
  4993.3  447.08  4997.3  445.74  5008.7  446.16  5017.7  442.03  5018.2  441.53
  5028.6  442.03  5030.6  442.88    5043  443.96  5068.5  446.18  5112.8  446.84
  5215.8  446.26  5295.2  449.13  5392.6  449.63  5524.3  448.66  5622.8  449.54
  5713.3   451.9  5776.5  453.99  5805.2  456.29  5836.7  457.67  5850.5   457.6
#Mann= 7 ,-1 , 0
  4680.4     .12       0  4771.2     .07       0  4900.3    .035       0
  5017.7    .035       0  5028.6    .035       0    5043     .05       0
  5713.3     .12       0
Bank Sta=5017.7,5028.6
XS Rating Curve= 0 ,0
Exp/Cntr=0.3,0.1

Type RM Length L Ch R = 1 ,926     ,392,392,392
BEGIN DESCRIPTION:
H21271
END DESCRIPTION:
XS GIS Cut Line= 3
      2488503.92     13846859.94      2487620.32     13847165.52
      2486998.14     13848292.07
#Sta/Elev= 30
  4025.1  466.84  4058.4  466.01  4076.9  464.21  4129.8  463.42  4140.4  462.46
  4271.3  460.08  4373.1  459.42  4607.4  451.96    4664  449.85  4755.4  447.46
  4923.4  446.24    4979  446.82  4993.7  443.34  4998.1  441.25    5001  439.45
  5001.5  438.95    5012  439.45  5022.5  444.01  5028.2  445.49  5044.3  446.78
  5163.5  444.39  5882.1  452.63  6015.9  455.12  6147.5  460.58  6170.4  460.29
  6184.3  462.21  6222.1  462.25  6227.8  463.38  6238.2  463.04    6247  464.24
#Mann= 8 ,-1 , 0
  4025.1     .12       0  4607.4     .07       0    4664    .035       0
  4755.4     .07       0  4998.1     .05       0    5001     .05       0
    5012     .05       0  5882.1     .12       0
Bank Sta=5001,5012
XS Rating Curve= 0 ,0
Exp/Cntr=0.3,0.1

Type RM Length L Ch R = 1 ,534     ,0,0,0
BEGIN DESCRIPTION:
H21270
END DESCRIPTION:
XS GIS Cut Line= 4
      2488507.59     13846639.06      2487458.33     13846808.41
      2487049.68     13847279.65      2486799.68     13848117.88
#Sta/Elev= 30
  3722.6  463.39  3745.5  463.28  3755.6   461.8  3791.2  461.88  3882.3  458.15
  3968.3  455.09  4089.9  453.04  4373.5   450.5  4515.7  447.83  4555.8  446.46
  4615.9  446.26  4768.5  447.12  4901.1  444.56  4962.8  445.62    4976  444.12
  4991.3   439.9  4992.4  439.01  4992.9  438.51  5003.5  439.01  5033.1  445.17
  5047.3  445.85  5132.8  443.75  5513.5  445.24  5794.3  449.36  5932.1  452.67
  5988.7  452.71  6207.7  463.38  6218.3  464.71  6270.5  467.55  6283.9  469.29
#Mann= 8 ,-1 , 0
  3722.6     .12       0  3882.3     .05       0  4515.7    .035       0
  4615.9     .05       0  4901.1     .12       0    4976     .05       0
  4992.4     .05       0  5003.5     .05       0
Bank Sta=4992.4,5003.5
XS Rating Curve= 0 ,0
Exp/Cntr=0.3,0.1

Chan Stop Cuts=-1
Use User Specified Reach Order=0
Composite Channel Slope=5