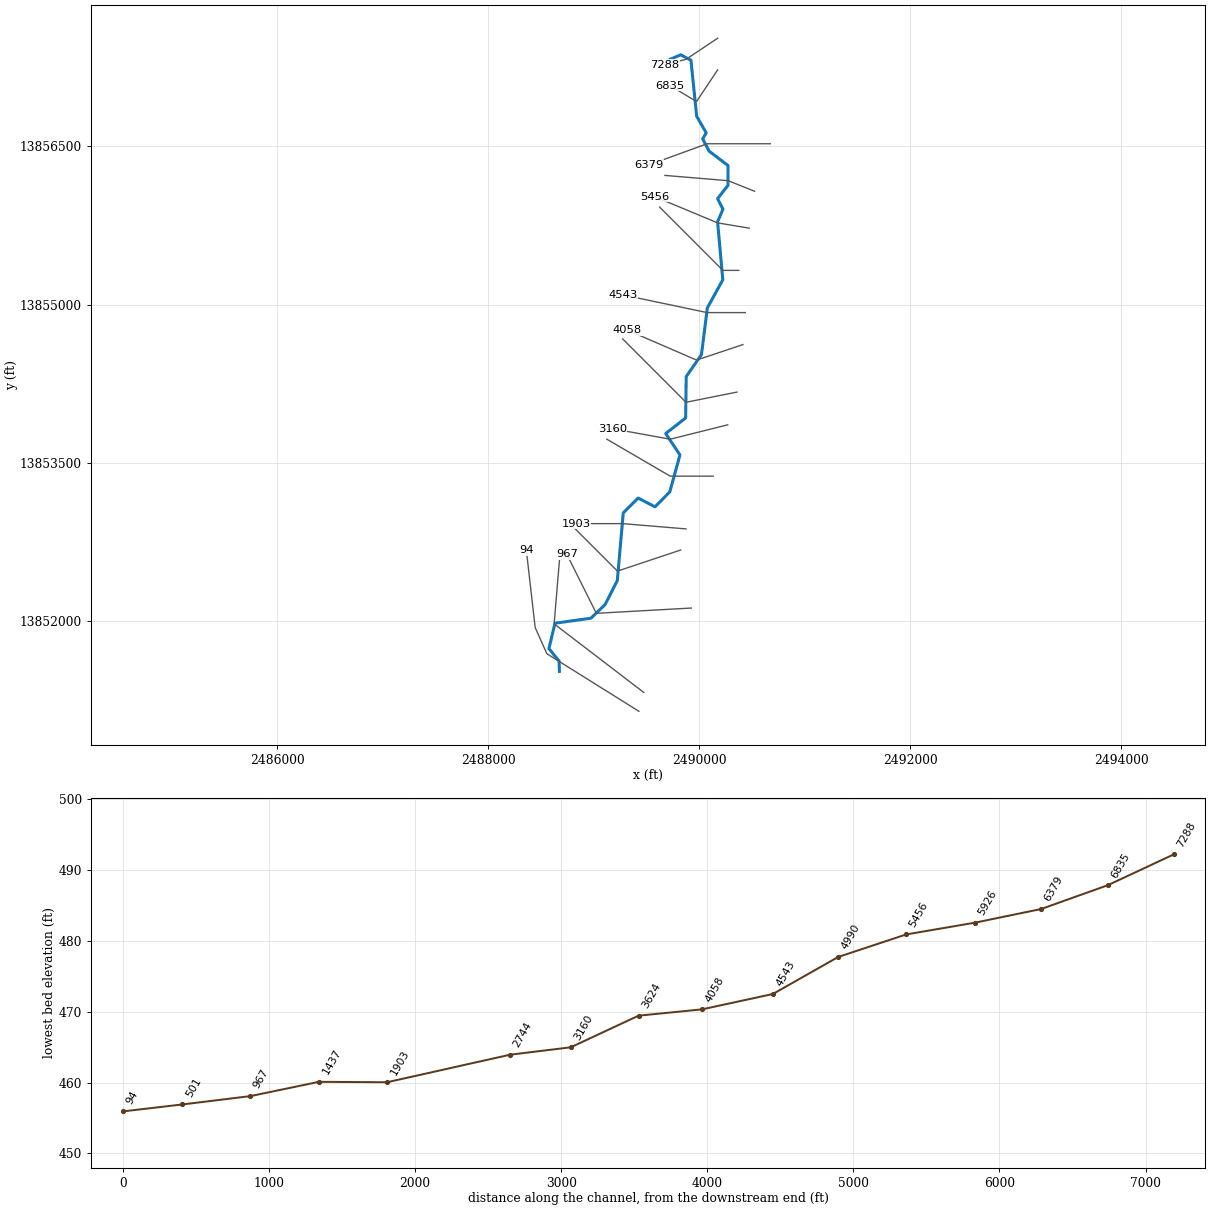
--- StreamM037.prj (project) ---

Proj Title=StreamM037 Base Level Engineering
Current Plan=p01
Default Exp/Contr=0.3,0.1
English Units
Geom File=g01
Flow File=f01
Plan File=p01
BEGIN DESCRIPTION:
StreamM037
END DESCRIPTION:

--- StreamM037.p01 (plan) ---

Plan Title=Multiple Run
Short Identifier=Multiple
Geom File=g01
Flow File=f01
Subcritical Flow
K Sum by GR= 0
Std Step Tol= 0.01
Critical Tol= 0.01
Num of Std Step Trials= 20
Max Error Tol= 0.3
Flow Tol Ratio= 0.001
Split Flow NTrial= 30
Split Flow Tol= 0.02
Split Flow Ratio= 0.02
Log Output Level= 0
Friction Slope Method= 1
Unsteady Friction Slope Method= 2
Unsteady Bridges Friction Slope Method= 1
Parabolic Critical Depth
Global Vel Dist=  1 , 1 , 1
Global Log Level= 0
CheckData=True
Encroach Param= -1, 0, 0, 0
BEGIN DESCRIPTION:
Multiple Run
END DESCRIPTION:

--- StreamM037.f01 (steady flow) ---

Flow Title=Multiple
Number of Profiles=7
Profile Names=10-year,25-year,50-year,1pct_min,100-year,1pct_plu,500-year
River Rch & RM= StreamM037,Reach-1,7288
     411     639     839     534    1066    2127    1702
River Rch & RM= StreamM037,Reach-1,3624
     515     810    1069     684    1365    2724    2202
Boundary for River Rch & Prof#=StreamM037,Reach-1,1
Up Type=0
Dn Type=3
Dn Slope=0.005
Boundary for River Rch & Prof#=StreamM037,Reach-1,2
Up Type=0
Dn Type=3
Dn Slope=0.005
Boundary for River Rch & Prof#=StreamM037,Reach-1,3
Up Type=0
Dn Type=3
Dn Slope=0.005
Boundary for River Rch & Prof#=StreamM037,Reach-1,4
Up Type=0
Dn Type=3
Dn Slope=0.005
Boundary for River Rch & Prof#=StreamM037,Reach-1,5
Up Type=0
Dn Type=3
Dn Slope=0.005
Boundary for River Rch & Prof#=StreamM037,Reach-1,6
Up Type=0
Dn Type=3
Dn Slope=0.005
Boundary for River Rch & Prof#=StreamM037,Reach-1,7
Up Type=0
Dn Type=3
Dn Slope=0.005

--- StreamM037.g01 (geometry) ---

Geom Title=Existing Conditions

River Reach=StreamM037,Reach-1
Reach XY= 30
      2489725.00     13857325.00      2489825.01     13857367.73
      2489921.92     13857316.75      2489976.20     13856785.50
      2490066.76     13856628.23      2490033.24     13856571.76
      2490094.62     13856454.53      2490272.95     13856319.16
      2490272.93     13856130.86      2490174.61     13856004.87
      2490225.27     13855904.83      2490174.55     13855785.19
      2490223.81     13855235.50      2490077.24     13854969.07
      2490021.45     13854526.47      2489877.24     13854319.07
      2489871.47     13853926.45      2489682.67     13853778.66
      2489817.68     13853575.10      2489721.46     13853226.47
      2489581.73     13853084.11      2489421.59     13853167.23
      2489280.46     13853027.45      2489223.80     13852385.50
      2489108.36     13852158.32      2488973.50     13852028.61
      2488633.00     13851981.39      2488575.37     13851740.17
      2488671.61     13851623.59      2488675.00     13851525.00

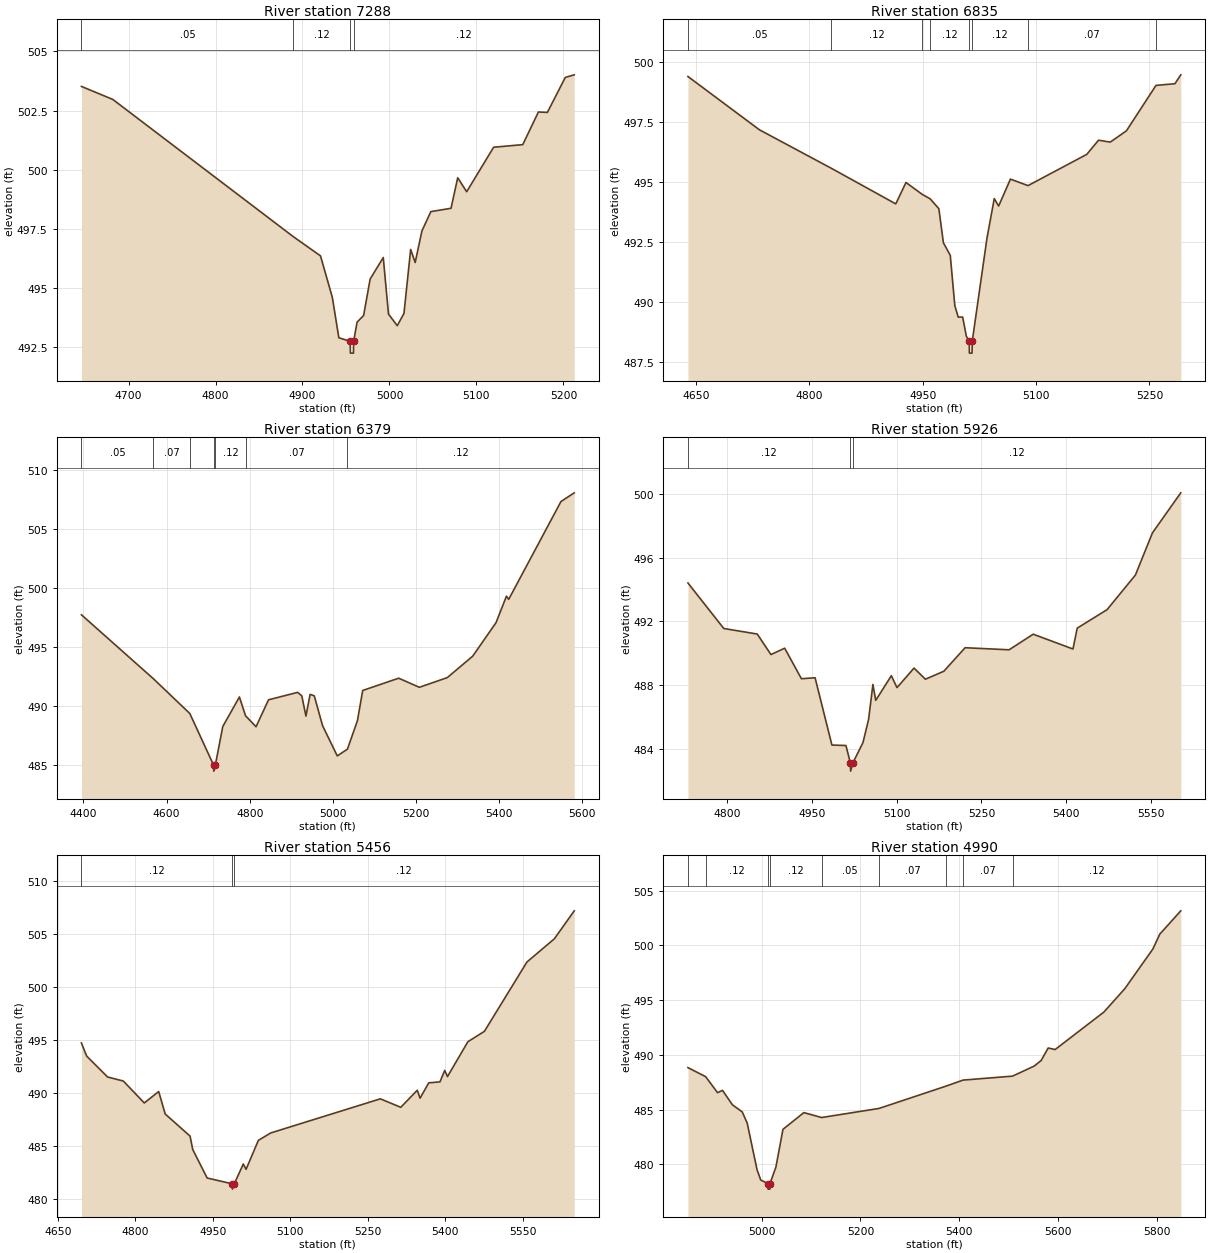
Type RM Length L Ch R = 1,7288,453,453,453
BEGIN DESCRIPTION:
StreamM037 15.0
END DESCRIPTION:
XS GIS Cut Line= 3
      2490175.02     13857525.01      2489875.00     13857325.00
      2489675.04     13857275.01
#Sta/Elev= 30
  4645.8  503.52  4681.9  502.97  4889.5  497.17  4920.7  496.36  4934.3  494.61
  4941.8  492.90  4954.8  492.75  4955.1  492.25  4958.6  492.25  4958.8  492.75
  4962.8  493.56  4970.3  493.84  4977.8  495.38  4992.9  496.29  4998.9  493.90
  5009.0  493.41  5016.7  493.93  5024.4  496.63  5029.6  496.08  5037.3  497.41
  5047.6  498.23  5070.8  498.37  5078.5  499.66  5088.8  499.07  5119.8  500.95
  5153.3  501.06  5171.3  502.44  5181.6  502.42  5202.2  503.90  5212.5  504.01
#Mann=4,-1,0
  4645.8    0.05       0  4889.5    0.12       0  4954.8    0.05       0
  4958.8    0.12       0
Bank Sta=4954.8,4958.8
Exp/Cntr=0.3,0.1

Type RM Length L Ch R = 1,6835,456,456,456
BEGIN DESCRIPTION:
StreamM037 14.0
END DESCRIPTION:
XS GIS Cut Line= 3
      2490175.02     13857225.02      2489975.00     13856925.00
      2489725.03     13857074.98
#Sta/Elev= 30
  4639.4  499.39  4734.1  497.17  4829.2  495.57  4914.4  494.09  4927.9  494.98
  4949.7  494.48  4959.9  494.30  4971.4  493.89  4977.4  492.47  4986.5  491.95
  4992.5  489.86  4997.0  489.38  5002.9  489.38  5007.8  488.58  5011.6  488.38
  5011.8  487.88  5015.3  487.88  5015.6  488.38  5035.0  492.65  5044.7  494.31
  5050.5  494.00  5066.1  495.12  5089.4  494.85  5167.1  496.15  5182.7  496.74
  5198.2  496.66  5219.6  497.13  5258.7  499.02  5283.8  499.09  5291.5  499.46
#Mann=8,-1,0
  4639.4    0.05       0  4829.2    0.12       0  4949.7    0.05       0
  4959.9    0.12       0  5011.6    0.05       0  5015.6    0.12       0
  5089.4    0.07       0  5258.7    0.12       0
Bank Sta=5011.6,5015.6
Exp/Cntr=0.3,0.1

Type RM Length L Ch R = 1,6379,453,453,453
BEGIN DESCRIPTION:
StreamM037 13.0
END DESCRIPTION:
XS GIS Cut Line= 3
      2490675.04     13856525.00      2490075.00     13856525.00
      2489524.97     13856324.99
#Sta/Elev= 30
  4395.2  497.76  4568.1  492.35  4655.9  489.40  4713.2  485.02  4713.5  484.52
  4717.2  485.02  4735.2  488.30  4775.2  490.80  4789.9  489.21  4815.2  488.28
  4845.2  490.56  4915.2  491.19  4925.2  490.90  4935.2  489.18  4945.2  491.02
  4955.2  490.90  4975.2  488.37  5010.5  485.81  5035.0  486.38  5059.1  488.80
  5071.7  491.35  5158.2  492.39  5208.0  491.62  5275.2  492.44  5336.4  494.26
  5392.3  497.09  5417.5  499.34  5422.9  499.07  5548.5  507.35  5580.5  508.09
#Mann=7,-1,0
  4395.2    0.05       0  4568.1    0.07       0  4655.9    0.12       0
  4713.2    0.05       0  4717.2    0.12       0  4789.9    0.07       0
  5035.0    0.12       0
Bank Sta=4713.2,4717.2
Exp/Cntr=0.3,0.1

Type RM Length L Ch R = 1,5926,470,470,470
BEGIN DESCRIPTION:
StreamM037 12.0
END DESCRIPTION:
XS GIS Cut Line= 3
      2490525.00     13856075.00      2490275.00     13856175.00
      2489675.04     13856225.00
#Sta/Elev= 30
  4731.2  494.42  4794.5  491.56  4853.7  491.21  4877.9  489.92  4902.2  490.32
  4931.8  488.40  4956.0  488.46  4985.7  484.23  5010.5  484.20  5018.5  483.09
  5018.8  482.59  5022.5  483.09  5040.6  484.38  5050.6  485.85  5058.2  488.04
  5063.2  487.04  5090.8  488.59  5100.8  487.84  5130.9  489.07  5151.0  488.37
  5183.6  488.87  5221.2  490.35  5299.0  490.22  5341.6  491.20  5411.9  490.27
  5419.4  491.58  5472.1  492.74  5522.3  494.92  5552.4  497.57  5602.5  500.09
#Mann=3,-1,0
  4731.2    0.12       0  5018.5    0.05       0  5022.5    0.12       0
Bank Sta=5018.5,5022.5
Exp/Cntr=0.3,0.1

Type RM Length L Ch R = 1,5456,466,466,466
BEGIN DESCRIPTION:
StreamM037 11.0
END DESCRIPTION:
XS GIS Cut Line= 3
      2490475.04     13855724.99      2490175.00     13855775.00
      2489574.98     13856025.01
#Sta/Elev= 30
  4695.4  494.72  4705.6  493.48  4746.1  491.51  4776.5  491.13  4817.1  489.06
  4845.0  490.14  4857.6  488.02  4905.8  485.93  4910.9  484.67  4938.8  481.98
  4987.4  481.43  4987.7  480.93  4991.4  481.43  5008.8  483.30  5014.2  482.80
  5038.0  485.53  5061.9  486.23  5274.2  489.45  5313.7  488.65  5345.7  490.26
  5351.1  489.51  5367.9  490.96  5389.6  491.05  5398.8  492.13  5404.2  491.55
  5443.7  494.84  5475.7  495.82  5558.0  502.36  5611.1  504.55  5649.6  507.19
#Mann=3,-1,0
  4695.4    0.12       0  4987.4    0.05       0  4991.4    0.12       0
Bank Sta=4987.4,4991.4
Exp/Cntr=0.3,0.1

Type RM Length L Ch R = 1,4990,447,447,447
BEGIN DESCRIPTION:
StreamM037 10.0
END DESCRIPTION:
XS GIS Cut Line= 3
      2490375.04     13855325.00      2490225.00     13855325.00
      2489624.98     13855925.02
#Sta/Elev= 30
  4850.4  488.84  4886.3  488.01  4910.4  486.55  4920.4  486.76  4940.4  485.45
  4960.4  484.79  4970.4  483.78  4990.4  479.51  4997.9  478.57  5012.6  478.24
  5012.8  477.74  5016.3  477.74  5016.6  478.24  5028.7  479.77  5042.9  483.20
  5085.3  484.73  5121.2  484.28  5237.5  485.11  5372.8  487.14  5408.0  487.70
  5508.1  488.06  5552.0  488.98  5566.1  489.49  5580.3  490.63  5594.4  490.49
  5693.4  493.92  5735.8  496.06  5792.4  499.67  5806.5  501.03  5849.0  503.16
#Mann=9,-1,0
  4850.4    0.05       0  4886.3    0.12       0  5012.6    0.05       0
  5016.6    0.12       0  5121.2    0.05       0  5237.5    0.07       0
  5372.8    0.12       0  5408.0    0.07       0  5508.1    0.12       0
Bank Sta=5012.6,5016.6
Exp/Cntr=0.3,0.1

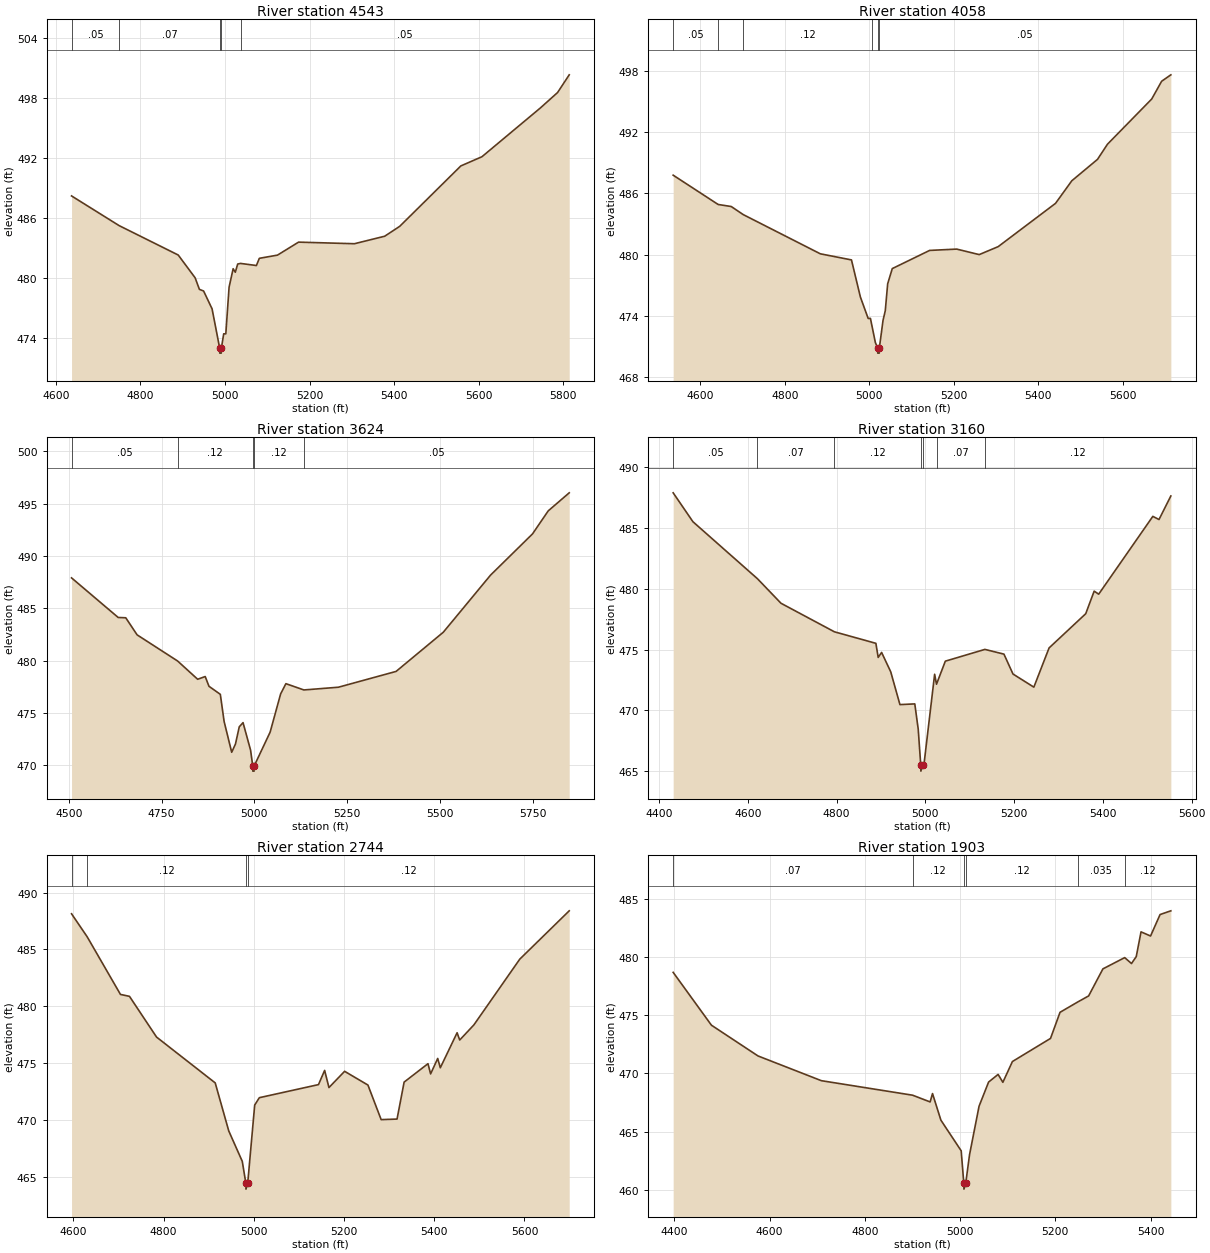
Type RM Length L Ch R = 1,4543,485,485,485
BEGIN DESCRIPTION:
StreamM037 9.0
END DESCRIPTION:
XS GIS Cut Line= 4
      2490437.19     13854925.00      2490225.00     13854925.00
      2490075.00     13854925.00      2489278.08     13855092.43
#Sta/Elev= 30
  4637.4  488.23  4749.9  485.26  4889.6  482.32  4929.6  480.04  4939.6  478.89
  4949.6  478.72  4969.6  476.94  4987.6  473.01  4987.8  472.51  4991.3  472.51
  4991.6  473.01  4997.1  474.44  5002.1  474.44  5009.8  479.10  5019.4  480.95
  5024.5  480.60  5030.2  481.42  5037.0  481.48  5074.4  481.27  5081.3  481.99
  5124.2  482.31  5174.1  483.61  5306.1  483.45  5377.7  484.20  5413.2  485.19
  5557.7  491.23  5607.6  492.15  5745.5  497.02  5786.4  498.57  5813.9  500.34
#Mann=5,-1,0
  4637.4    0.05       0  4749.9    0.07       0  4987.6    0.05       0
  4991.6    0.07       0  5037.0    0.05       0
Bank Sta=4987.6,4991.6
Exp/Cntr=0.3,0.1

Type RM Length L Ch R = 1,4058,434,434,434
BEGIN DESCRIPTION:
StreamM037 8.0
END DESCRIPTION:
XS GIS Cut Line= 4
      2490415.44     13854621.81      2490125.00     13854525.00
      2489975.00     13854475.00      2489319.78     13854758.54
#Sta/Elev= 30
  4535.8  487.77  4642.3  484.90  4673.3  484.70  4701.6  483.91  4884.1  480.07
  4957.9  479.47  4979.0  475.84  4997.4  473.74  5002.8  473.74  5006.6  472.97
  5014.5  471.37  5019.9  470.84  5020.1  470.34  5023.6  470.34  5023.9  470.84
  5032.6  473.54  5038.0  474.51  5043.6  477.13  5054.5  478.62  5142.9  480.40
  5207.1  480.53  5260.3  479.99  5305.2  480.77  5441.0  485.01  5479.5  487.22
  5540.4  489.32  5563.9  490.80  5668.7  495.23  5692.2  496.97  5714.0  497.60
#Mann=6,-1,0
  4535.8    0.05       0  4642.3    0.07       0  4701.6    0.12       0
  5006.6    0.05       0  5019.9    0.05       0  5023.9    0.05       0
Bank Sta=5019.9,5023.9
Exp/Cntr=0.3,0.1

Type RM Length L Ch R = 1,3624,464,464,464
BEGIN DESCRIPTION:
StreamM037 7.0
END DESCRIPTION:
XS GIS Cut Line= 4
      2490358.25     13854171.65      2490125.00     13854125.00
      2489875.00     13854075.00      2489275.04     13854674.96
#Sta/Elev= 30
  4507.2  487.90  4632.9  484.12  4653.3  484.09  4683.9  482.46  4793.2  479.96
  4847.1  478.22  4867.4  478.48  4877.6  477.55  4908.2  476.78  4918.4  474.19
  4938.8  471.25  4949.0  472.04  4959.2  473.68  4969.4  474.08  4989.8  471.44
  4995.5  469.95  4995.7  469.45  4999.2  469.45  4999.5  469.95  5042.4  473.17
  5070.7  476.82  5084.9  477.80  5133.4  477.20  5226.3  477.46  5381.9  478.97
  5509.1  482.71  5636.4  488.16  5749.6  492.10  5792.0  494.30  5848.5  496.02
#Mann=5,-1,0
  4507.2    0.05       0  4793.2    0.12       0  4995.5    0.05       0
  4999.5    0.12       0  5133.4    0.05       0
Bank Sta=4995.5,4999.5
Exp/Cntr=0.3,0.1

Type RM Length L Ch R = 1,3160,416,416,416
BEGIN DESCRIPTION:
StreamM037 6.0
END DESCRIPTION:
XS GIS Cut Line= 4
      2490270.70     13853861.42      2489925.00     13853775.00
      2489725.00     13853725.00      2489175.01     13853825.00
#Sta/Elev= 30
  4431.6  487.91  4476.1  485.53  4621.6  480.83  4674.6  478.81  4794.9  476.46
  4888.4  475.51  4893.6  474.35  4901.3  474.76  4921.9  473.16  4942.6  470.46
  4976.1  470.52  4983.8  468.44  4989.5  465.48  4989.8  464.98  4993.5  465.48
  4996.6  465.48  5020.8  472.96  5025.0  472.14  5044.9  474.04  5134.1  475.01
  5177.0  474.62  5197.4  472.98  5244.4  471.90  5278.7  475.13  5361.3  477.95
  5380.3  479.81  5390.5  479.56  5512.5  485.97  5526.4  485.71  5553.1  487.65
#Mann=7,-1,0
  4431.6    0.05       0  4621.6    0.07       0  4794.9    0.12       0
  4989.5    0.05       0  4993.5    0.12       0  5025.0    0.07       0
  5134.1    0.12       0
Bank Sta=4989.5,4993.5
Exp/Cntr=0.3,0.1

Type RM Length L Ch R = 1,2744,841,841,841
BEGIN DESCRIPTION:
StreamM037 5.0
END DESCRIPTION:
XS GIS Cut Line= 4
      2490133.38     13853375.00      2489925.00     13853375.00
      2489725.00     13853375.00      2489125.00     13853725.00
#Sta/Elev= 30
  4596.2  488.14  4630.8  486.12  4704.6  481.05  4724.6  480.88  4784.6  477.30
  4914.6  473.27  4944.6  469.05  4974.6  466.37  4982.6  464.43  4982.8  463.93
  4986.6  464.43  5002.1  471.32  5012.4  471.97  5143.5  473.12  5157.1  474.37
  5166.7  472.86  5201.4  474.29  5253.1  473.08  5282.4  470.04  5317.6  470.09
  5333.3  473.34  5386.2  474.96  5392.0  474.06  5407.7  475.42  5413.5  474.60
  5450.7  477.68  5456.5  477.04  5487.9  478.37  5589.6  484.15  5699.2  488.40
#Mann=4,-1,0
  4596.2    0.07       0  4630.8    0.12       0  4982.6    0.05       0
  4986.6    0.12       0
Bank Sta=4982.6,4986.6
Exp/Cntr=0.3,0.1

Type RM Length L Ch R = 1,1903,466,466,466
BEGIN DESCRIPTION:
StreamM037 4.0
END DESCRIPTION:
XS GIS Cut Line= 4
      2489875.03     13852875.00      2489275.00     13852925.00
      2489125.00     13852925.00      2488832.41     13852925.00
#Sta/Elev= 30
  4397.8  478.71  4478.1  474.16  4575.9  471.51  4708.9  469.38  4900.4  468.13
  4937.2  467.55  4942.2  468.27  4959.8  465.98  5002.4  463.34  5007.9  460.54
  5008.2  460.04  5011.9  460.54  5019.9  463.00  5039.9  467.18  5059.9  469.26
  5079.9  469.92  5089.9  469.24  5109.9  471.03  5189.9  473.02  5209.9  475.27
  5247.1  476.16  5269.9  476.68  5299.9  479.01  5345.6  479.98  5359.9  479.47
  5369.9  480.07  5379.9  482.20  5399.9  481.84  5419.9  483.69  5442.5  484.01
#Mann=6,-1,0
  4397.8    0.07       0  4900.4    0.12       0  5007.9    0.05       0
  5011.9    0.12       0  5247.1   0.035       0  5345.6    0.12       0
Bank Sta=5007.9,5011.9
Exp/Cntr=0.3,0.1

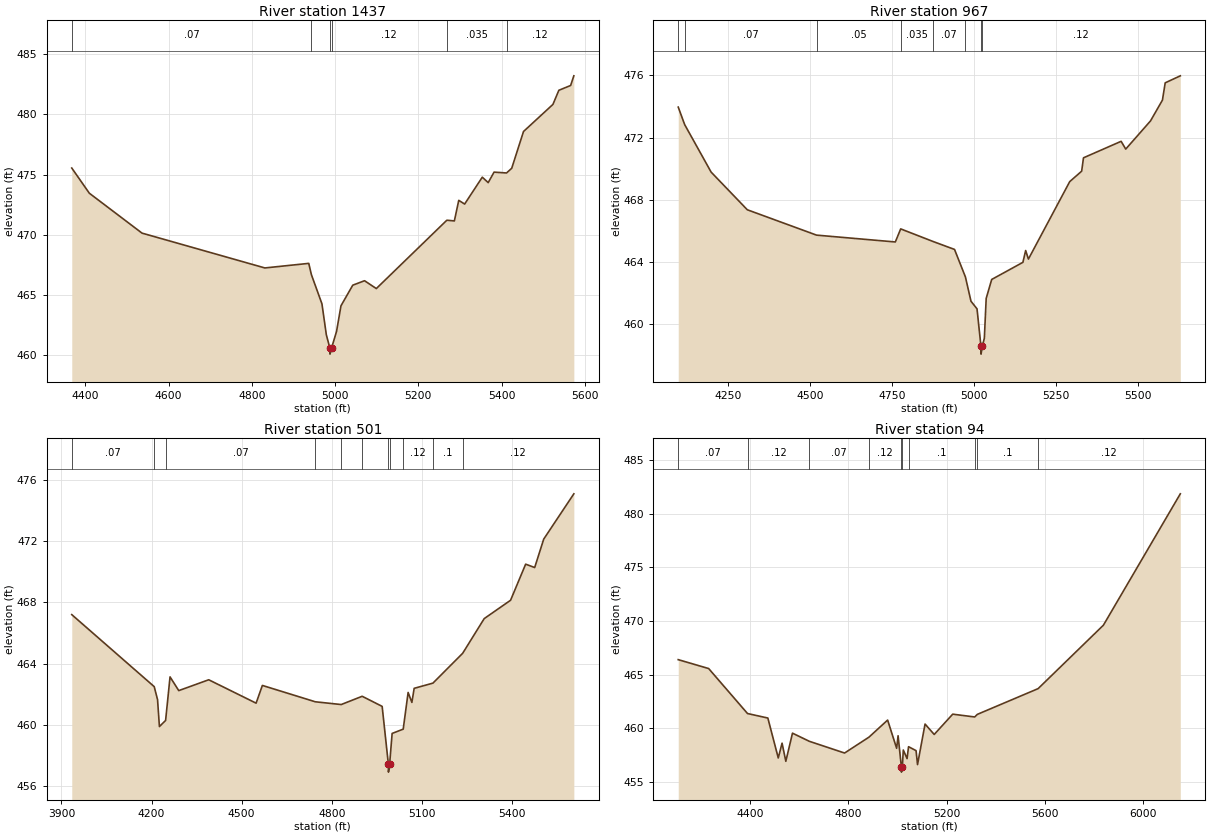
Type RM Length L Ch R = 1,1437,470,470,470
BEGIN DESCRIPTION:
StreamM037 3.0
END DESCRIPTION:
XS GIS Cut Line= 4
      2489825.03     13852675.01      2489225.00     13852475.00
      2489025.00     13852675.00      2488819.53     13852880.47
#Sta/Elev= 30
  4367.6  475.54  4409.8  473.45  4536.3  470.14  4831.4  467.25  4936.8  467.63
  4943.1  466.70  4968.5  464.27  4979.0  461.71  4987.5  460.60  4987.8  460.10
  4991.5  460.60  5003.6  461.99  5014.2  464.11  5042.5  465.82  5070.8  466.19
  5099.1  465.54  5268.5  471.21  5286.5  471.15  5297.1  472.86  5311.2  472.55
  5353.6  474.78  5367.8  474.33  5381.9  475.20  5411.9  475.13  5424.3  475.52
  5452.6  478.57  5523.3  480.82  5537.5  481.99  5565.8  482.39  5573.5  483.19
#Mann=6,-1,0
  4367.6    0.07       0  4943.1    0.12       0  4987.5    0.05       0
  4991.5    0.12       0  5268.5   0.035       0  5411.9    0.12       0
Bank Sta=4987.5,4991.5
Exp/Cntr=0.3,0.1

Type RM Length L Ch R = 1,967,466,466,466
BEGIN DESCRIPTION:
StreamM037 2.0
END DESCRIPTION:
XS GIS Cut Line= 4
      2489925.00     13852125.00      2489025.00     13852075.00
      2488875.00     13852375.00      2488744.41     13852636.17
#Sta/Elev= 30
  4099.0  473.96  4118.7  472.83  4199.2  469.78  4309.3  467.36  4520.1  465.73
  4760.0  465.29  4776.4  466.13  4875.0  465.32  4940.3  464.81  4973.5  463.04
  4990.4  461.48  5008.8  460.99  5020.8  458.58  5021.0  458.08  5024.8  458.58
  5031.1  459.10  5036.7  461.66  5053.5  462.88  5148.5  463.98  5156.9  464.74
  5165.3  464.19  5291.1  469.17  5327.4  469.84  5333.0  470.70  5447.6  471.76
  5461.6  471.26  5537.0  473.07  5573.4  474.41  5581.8  475.52  5627.8  475.97
#Mann=8,-1,0
  4099.0    0.12       0  4118.7    0.07       0  4520.1    0.05       0
  4776.4   0.035       0  4875.0    0.07       0  4973.5    0.12       0
  5020.8    0.05       0  5024.8    0.12       0
Bank Sta=5020.8,5024.8
Exp/Cntr=0.3,0.1

Type RM Length L Ch R = 1,501,407,407,407
BEGIN DESCRIPTION:
StreamM037 1.0
END DESCRIPTION:
XS GIS Cut Line= 3
      2489474.99     13851325.01      2488625.00     13851975.00
      2488675.00     13852574.99
#Sta/Elev= 30
  3934.3  467.20  4208.9  462.49  4220.0  461.64  4226.2  459.88  4246.8  460.28
  4261.6  463.13  4290.6  462.23  4390.4  462.94  4548.2  461.41  4569.1  462.57
  4745.3  461.50  4831.7  461.32  4901.5  461.86  4968.0  461.20  4988.8  457.40
  4989.0  456.90  4992.8  457.40  5001.2  459.43  5038.1  459.71  5054.5  462.11
  5067.0  461.46  5074.6  462.38  5137.1  462.72  5236.1  464.67  5307.9  466.94
  5395.7  468.14  5445.9  470.50  5476.0  470.28  5506.1  472.14  5606.4  475.10
#Mann=11,-1,0
  3934.3    0.07       0  4208.9    0.12       0  4246.8    0.07       0
  4745.3     0.1       0  4831.7    0.07       0  4901.5     0.1       0
  4988.8    0.05       0  4992.8     0.1       0  5038.1    0.12       0
  5137.1     0.1       0  5236.1    0.12       0
Bank Sta=4988.8,4992.8
Exp/Cntr=0.3,0.1

Type RM Length L Ch R = 1,94,0,0,0
BEGIN DESCRIPTION:
H21291
END DESCRIPTION:
XS GIS Cut Line= 4
      2489428.31     13851146.61      2488555.78     13851692.29
      2488445.02     13851940.81      2488361.28     13852675.55
#Sta/Elev= 30
  4109.4  466.40  4233.1  465.57  4391.0  461.38  4473.6  460.96  4516.0  457.24
  4531.4  458.62  4546.7  456.93  4573.8  459.55  4642.4  458.79  4785.6  457.70
  4884.7  459.18  4960.5  460.77  4997.1  458.14  5003.0  459.31  5016.3  456.42
  5016.6  455.92  5020.3  456.42  5024.2  457.98  5039.5  457.18  5045.5  458.29
  5076.1  457.92  5082.0  456.62  5112.6  460.40  5149.8  459.43  5225.0  461.32
  5314.4  461.06  5325.0  461.30  5572.2  463.70  5837.5  469.61  6150.1  481.85
#Mann=10,-1,0
  4109.4    0.07       0  4391.0    0.12       0  4642.4    0.07       0
  4884.7    0.12       0  5016.3    0.05       0  5020.3    0.12       0
  5045.5     0.1       0  5314.4    0.12       0  5325.0     0.1       0
  5572.2    0.12       0
Bank Sta=5016.3,5020.3
Exp/Cntr=0.3,0.1

Chan Stop Cuts=-1