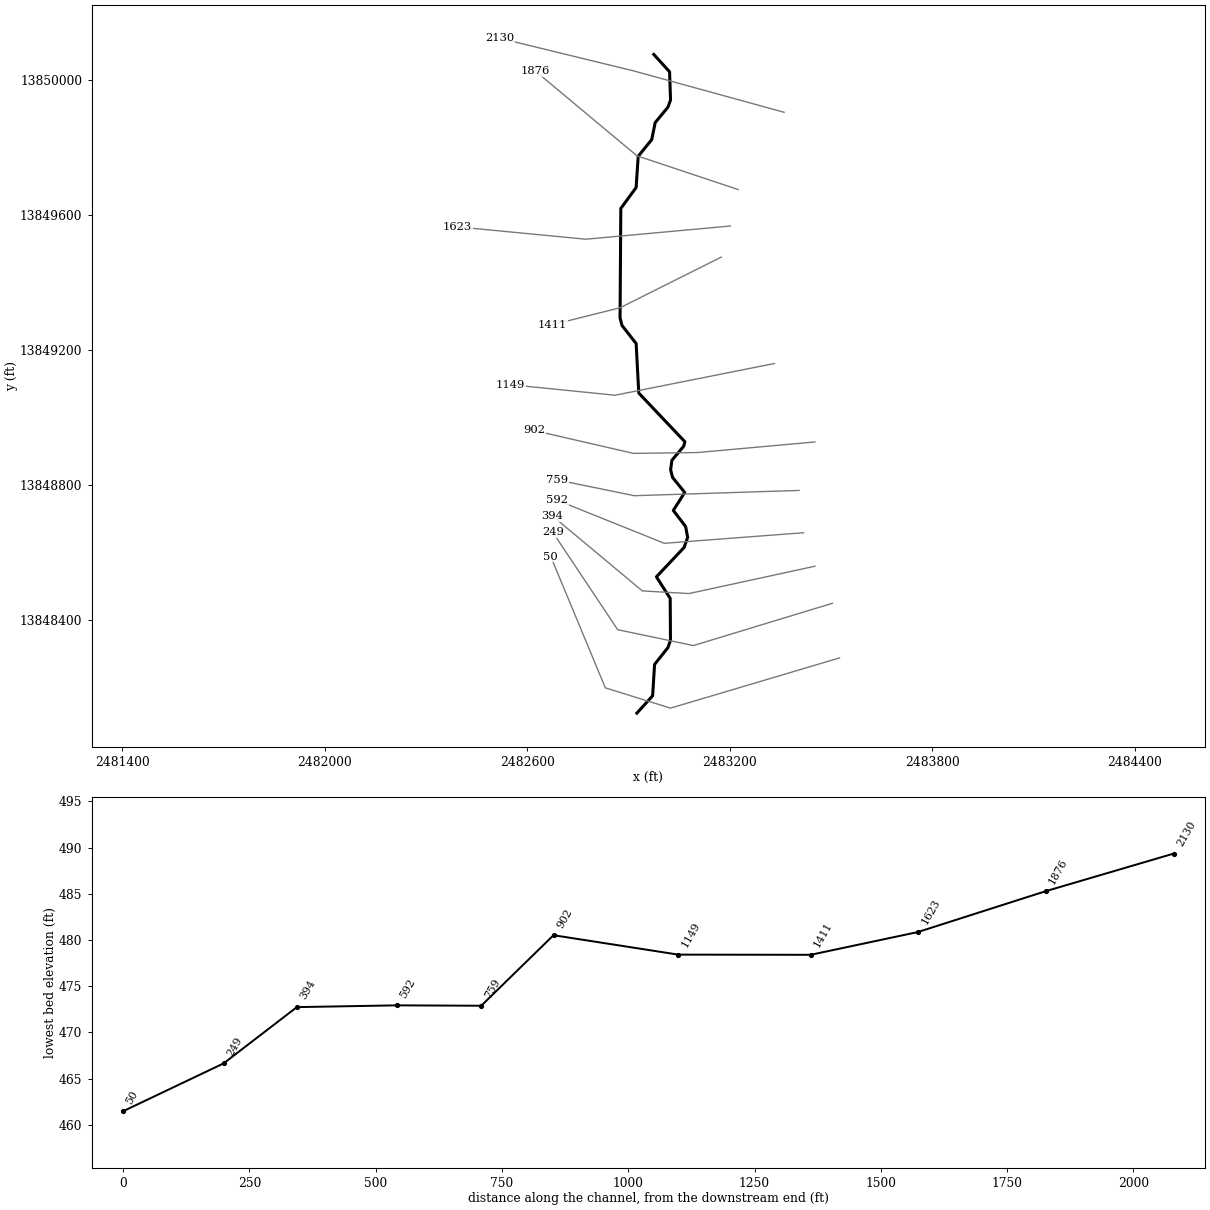
--- StreamM039.prj (project) ---

Proj Title=StreamM039 Base Level Engineering
Current Plan=p01
Default Exp/Contr=0.3,0.1
English Units
Geom File=g01
Flow File=f01
Plan File=p01
BEGIN DESCRIPTION:
StreamM039
END DESCRIPTION:

--- StreamM039.p01 (plan) ---

Plan Title=Multiple Run
Short Identifier=Multiple
Geom File=g01
Flow File=f01
Subcritical Flow
K Sum by GR= 0
Std Step Tol= 0.01
Critical Tol= 0.01
Num of Std Step Trials= 20
Max Error Tol= 0.3
Flow Tol Ratio= 0.001
Split Flow NTrial= 30
Split Flow Tol= 0.02
Split Flow Ratio= 0.02
Log Output Level= 0
Friction Slope Method= 1
Unsteady Friction Slope Method= 2
Unsteady Bridges Friction Slope Method= 1
Parabolic Critical Depth
Global Vel Dist=  1 , 1 , 1
Global Log Level= 0
CheckData=True
Encroach Param= -1, 0, 0, 0
BEGIN DESCRIPTION:
Multiple Run
END DESCRIPTION:

--- StreamM039.f01 (steady flow) ---

Flow Title=Multiple
Number of Profiles=7
Profile Names=10-year,25-year,50-year,1pct_min,100-year,1pct_plu,500-year
River Rch & RM= StreamM039,Reach-1,2130
     320     494     646     411     820    1636    1304
Boundary for River Rch & Prof#=StreamM039,Reach-1,1
Up Type=0
Dn Type=3
Dn Slope=0.005
Boundary for River Rch & Prof#=StreamM039,Reach-1,2
Up Type=0
Dn Type=3
Dn Slope=0.005
Boundary for River Rch & Prof#=StreamM039,Reach-1,3
Up Type=0
Dn Type=3
Dn Slope=0.005
Boundary for River Rch & Prof#=StreamM039,Reach-1,4
Up Type=0
Dn Type=3
Dn Slope=0.005
Boundary for River Rch & Prof#=StreamM039,Reach-1,5
Up Type=0
Dn Type=3
Dn Slope=0.005
Boundary for River Rch & Prof#=StreamM039,Reach-1,6
Up Type=0
Dn Type=3
Dn Slope=0.005
Boundary for River Rch & Prof#=StreamM039,Reach-1,7
Up Type=0
Dn Type=3
Dn Slope=0.005

--- StreamM039.g01 (geometry) ---

Geom Title=Existing Conditions

River Reach=StreamM039,Reach-1
Reach XY= 30
      2482975.00     13850075.00      2483021.81     13850023.60
      2483024.65     13849940.25      2483016.96     13849918.94
      2482979.19     13849873.27      2482968.89     13849822.82
      2482928.83     13849773.42      2482922.64     13849680.98
      2482877.26     13849619.06      2482875.07     13849295.03
      2482880.75     13849272.67      2482922.73     13849219.06
      2482930.47     13849072.55      2483067.18     13848928.41
      2483063.62     13848915.13      2483028.65     13848873.35
      2483024.90     13848845.16      2483030.66     13848822.71
      2483066.68     13848778.23      2483032.83     13848725.08
      2483069.39     13848677.29      2483075.32     13848645.16
      2483064.75     13848615.32      2482982.81     13848528.41
      2483023.62     13848464.56      2483024.50     13848340.22
      2483016.87     13848318.94      2482977.32     13848269.04
      2482971.61     13848176.40      2482925.00     13848125.00

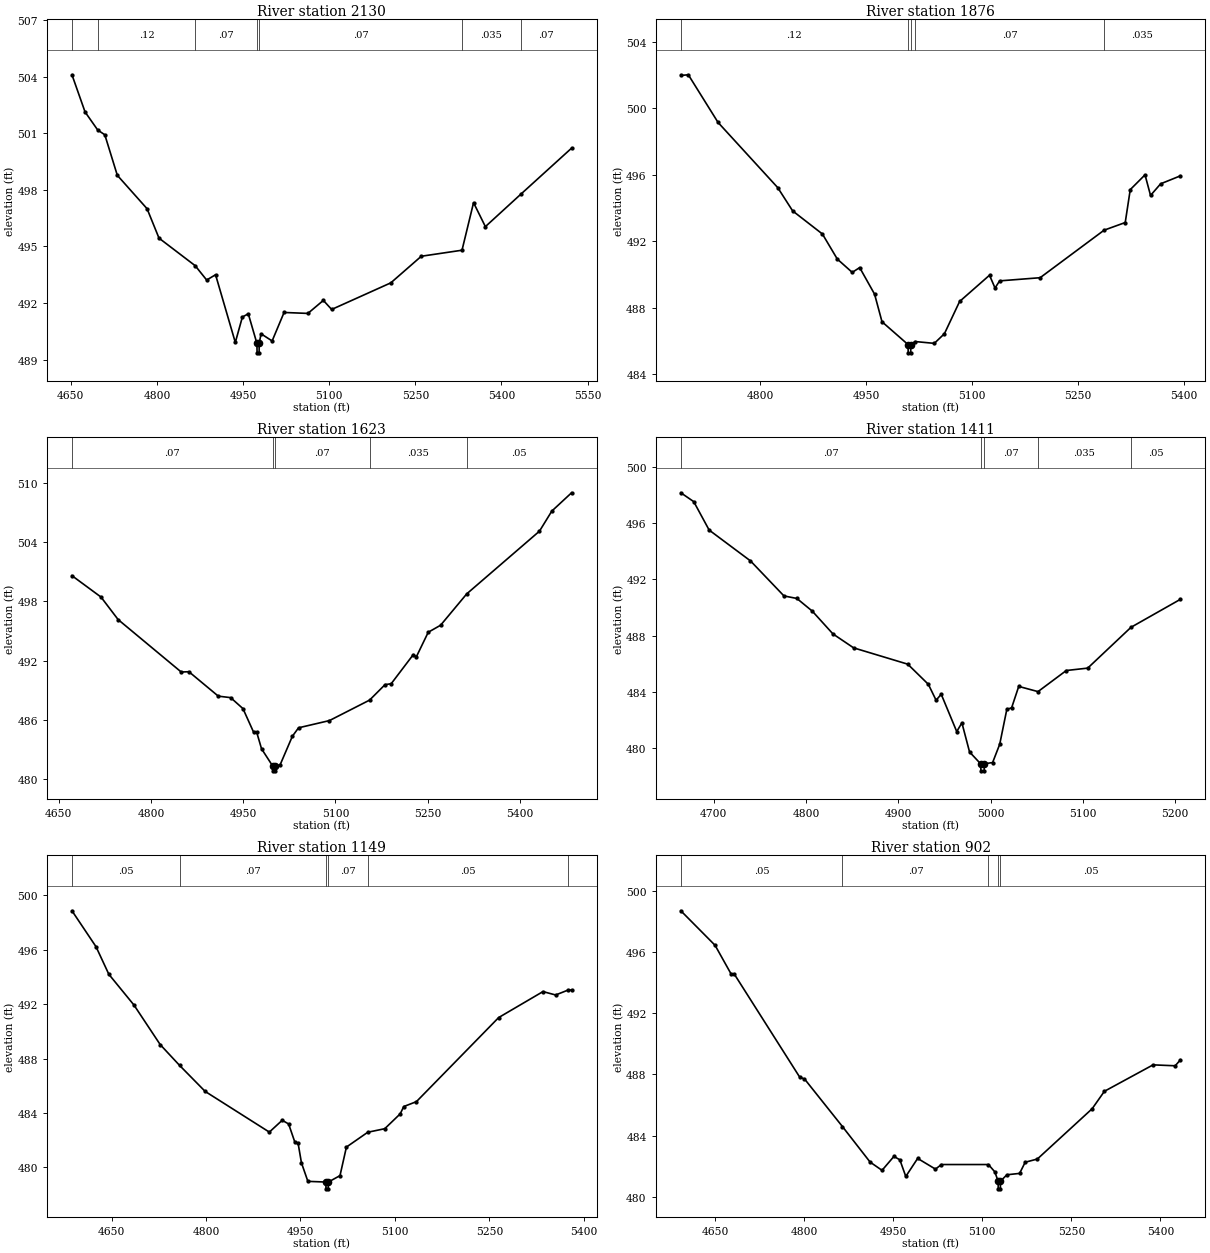
Type RM Length L Ch R = 1,2130,254,254,254
BEGIN DESCRIPTION:
H21300
END DESCRIPTION:
XS GIS Cut Line= 3
      2483361.17     13849903.73      2482914.96     13850026.37
      2482519.17     13850122.71
#Sta/Elev= 30
  4652.0  504.10  4674.8  502.13  4696.9  501.17  4709.2  500.92  4731.0  498.77
  4782.8  497.00  4803.6  495.44  4866.6  493.98  4886.6  493.22  4902.1  493.50
  4936.5  489.91  4948.8  491.26  4959.1  491.43  4974.1  489.86  4974.4  489.36
  4977.9  489.36  4978.1  489.86  4981.3  490.37  5000.6  489.99  5021.4  491.50
  5062.9  491.45  5089.8  492.14  5104.3  491.66  5207.3  493.07  5260.4  494.48
  5331.3  494.80  5351.4  497.32  5372.0  496.05  5433.4  497.76  5522.1  500.21
#Mann=7,-1,0
  4652.0    0.07       0  4696.9    0.12       0  4866.6    0.07       0
  4974.1    0.05       0  4978.1    0.07       0  5331.3   0.035       0
  5433.4    0.07       0
Bank Sta=4974.1,4978.1
Exp/Cntr=0.3,0.1

Type RM Length L Ch R = 1,1876,253,253,253
BEGIN DESCRIPTION:
StreamM039 3.0
END DESCRIPTION:
XS GIS Cut Line= 3
      2483225.04     13849674.99      2482925.00     13849775.00
      2482624.99     13850025.01
#Sta/Elev= 30
  4687.9  501.97  4698.5  502.01  4740.6  499.14  4825.0  495.22  4846.1  493.82
  4888.2  492.43  4909.3  490.92  4930.4  490.12  4940.9  490.41  4962.0  488.81
  4972.5  487.15  5009.3  485.78  5009.6  485.28  5013.1  485.28  5013.3  485.78
  5019.3  485.96  5046.5  485.85  5060.8  486.43  5082.3  488.37  5124.6  489.95
  5132.4  489.18  5138.9  489.61  5196.2  489.80  5286.7  492.66  5316.6  493.12
  5323.7  495.10  5344.6  495.99  5352.4  494.75  5366.7  495.45  5394.7  495.93
#Mann=5,-1,0
  4687.9    0.12       0  5009.3    0.05       0  5013.3    0.12       0
  5019.3    0.07       0  5286.7   0.035       0
Bank Sta=5009.3,5013.3
Exp/Cntr=0.3,0.1

Type RM Length L Ch R = 1,1623,212,212,212
BEGIN DESCRIPTION:
H21299
END DESCRIPTION:
XS GIS Cut Line= 3
      2483201.98     13849567.10      2482774.05     13849527.96
      2482393.01     13849564.49
#Sta/Elev= 30
  4671.5  500.59  4718.7  498.43  4746.6  496.15  4849.2  490.85  4861.7  490.88
  4909.5  488.41  4929.6  488.26  4949.6  487.15  4966.8  484.78  4971.9  484.77
  4979.8  483.09  4997.8  481.36  4998.1  480.86  5001.6  480.86  5001.8  481.36
  5009.9  481.45  5030.0  484.36  5040.0  485.21  5090.2  485.94  5155.5  488.01
  5180.6  489.57  5190.7  489.67  5226.6  492.61  5231.6  492.39  5250.9  494.87
  5271.0  495.58  5313.5  498.75  5431.8  505.09  5451.9  507.12  5484.0  508.97
#Mann=5,-1,0
  4671.5    0.07       0  4997.8    0.05       0  5001.8    0.07       0
  5155.5   0.035       0  5313.5    0.05       0
Bank Sta=4997.8,5001.8
Exp/Cntr=0.3,0.1

Type RM Length L Ch R = 1,1411,262,262,262
BEGIN DESCRIPTION:
StreamM039 2.0
END DESCRIPTION:
XS GIS Cut Line= 3
      2483174.99     13849475.00      2482875.00     13849325.00
      2482674.96     13849274.99
#Sta/Elev= 30
  4664.2  498.16  4678.2  497.53  4694.9  495.51  4739.7  493.32  4776.0  490.83
  4790.0  490.65  4806.7  489.75  4829.1  488.13  4851.5  487.14  4910.2  485.98
  4932.5  484.55  4940.9  483.42  4946.5  483.84  4963.3  481.19  4968.9  481.81
  4977.2  479.74  4989.2  478.90  4989.5  478.40  4993.0  478.40  4993.2  478.90
  5002.2  478.99  5009.9  480.29  5017.6  482.77  5022.8  482.88  5030.5  484.40
  5051.4  484.03  5082.1  485.53  5105.3  485.70  5152.2  488.60  5205.8  490.59
#Mann=5,-1,0
  4664.2    0.07       0  4989.2    0.05       0  4993.2    0.07       0
  5051.4   0.035       0  5152.2    0.05       0
Bank Sta=4989.2,4993.2
Exp/Cntr=0.3,0.1

Type RM Length L Ch R = 1,1149,247,247,247
BEGIN DESCRIPTION:
H21298
END DESCRIPTION:
XS GIS Cut Line= 3
      2483332.50     13849160.02      2482860.16     13849066.08
      2482549.82     13849097.37
#Sta/Elev= 30
  4587.1  498.86  4625.3  496.22  4645.7  494.19  4685.6  491.93  4727.3  489.02
  4758.1  487.49  4798.7  485.58  4900.6  482.59  4921.0  483.46  4931.2  483.19
  4941.2  481.84  4946.3  481.76  4951.6  480.33  4961.8  478.97  4990.3  478.92
  4990.6  478.42  4994.1  478.42  4994.3  478.92  5012.8  479.39  5023.0  481.49
  5056.9  482.58  5083.9  482.84  5108.4  483.93  5114.1  484.47  5134.2  484.83
  5264.8  491.01  5335.2  492.92  5355.3  492.67  5375.5  493.04  5380.6  493.03
#Mann=6,-1,0
  4587.1    0.05       0  4758.1    0.07       0  4990.3    0.05       0
  4994.3    0.07       0  5056.9    0.05       0  5375.5    0.07       0
Bank Sta=4990.3,4994.3
Exp/Cntr=0.3,0.1

Type RM Length L Ch R = 1,902,143,143,143
BEGIN DESCRIPTION:
H21297
END DESCRIPTION:
XS GIS Cut Line= 4
      2483452.48     13848927.77      2483105.45     13848896.46
      2482914.96     13848893.85      2482620.11     13848961.69
#Sta/Elev= 30
  4592.1  498.71  4649.8  496.45  4676.7  494.58  4681.8  494.59  4792.6  487.81
  4800.4  487.71  4864.4  484.59  4910.9  482.27  4931.0  481.73  4951.0  482.64
  4961.0  482.42  4971.0  481.33  4991.0  482.51  5021.0  481.81  5031.0  482.11
  5110.2  482.11  5121.0  481.63  5126.5  481.02  5126.8  480.52  5130.3  480.52
  5130.5  481.02  5141.3  481.44  5162.7  481.53  5172.1  482.26  5192.6  482.47
  5284.9  485.76  5305.5  486.90  5387.5  488.63  5424.8  488.57  5433.6  488.96
#Mann=5,-1,0
  4592.1    0.05       0  4864.4    0.07       0  5110.2    0.05       0
  5126.5    0.05       0  5130.5    0.05       0
Bank Sta=5126.5,5130.5
Exp/Cntr=0.3,0.1

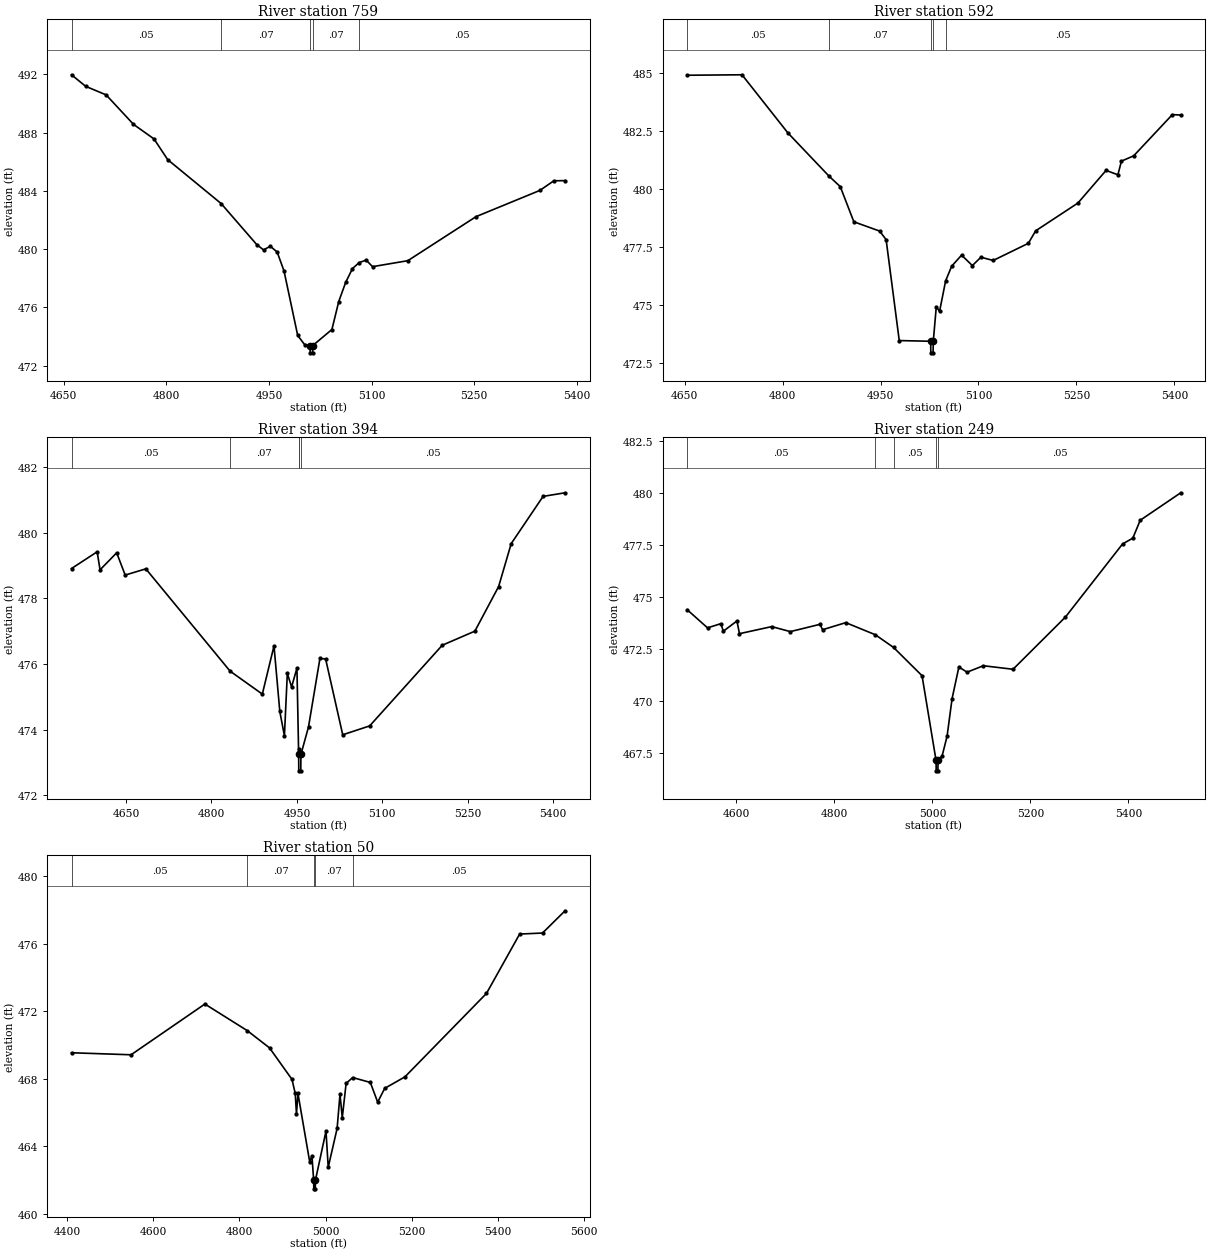
Type RM Length L Ch R = 1,759,167,167,167
BEGIN DESCRIPTION:
H21296
END DESCRIPTION:
XS GIS Cut Line= 3
      2483405.55     13848784.25      2482917.57     13848768.59
      2482688.93     13848815.36
#Sta/Elev= 30
  4661.2  491.96  4681.8  491.17  4711.8  490.58  4751.8  488.56  4781.8  487.56
  4801.8  486.14  4879.9  483.13  4931.9  480.32  4941.9  479.95  4951.9  480.20
  4961.9  479.80  4971.9  478.50  4991.9  474.08  5001.9  473.46  5009.9  473.39
  5010.2  472.89  5013.7  472.89  5013.9  473.39  5041.9  474.49  5051.9  476.41
  5062.0  477.72  5072.0  478.67  5081.8  479.08  5092.0  479.25  5101.3  478.80
  5152.9  479.21  5252.6  482.23  5346.0  484.03  5366.4  484.69  5382.8  484.70
#Mann=5,-1,0
  4661.2    0.05       0  4879.9    0.07       0  5009.9    0.05       0
  5013.9    0.07       0  5081.8    0.05       0
Bank Sta=5009.9,5013.9
Exp/Cntr=0.3,0.1

Type RM Length L Ch R = 1,592,198,198,198
BEGIN DESCRIPTION:
H21295
END DESCRIPTION:
XS GIS Cut Line= 3
      2483418.62     13848659.00      2483006.29     13848627.68
      2482688.95     13848755.14
#Sta/Elev= 30
  4654.1  484.92  4738.0  484.94  4808.2  482.43  4871.6  480.55  4888.4  480.11
  4909.2  478.59  4948.6  478.19  4958.6  477.82  4978.7  473.46  5026.8  473.43
  5027.0  472.93  5030.5  472.93  5030.8  473.43  5035.4  474.92  5040.4  474.72
  5049.7  476.04  5058.9  476.67  5074.1  477.15  5090.6  476.70  5103.7  477.06
  5122.5  476.92  5176.3  477.66  5187.5  478.20  5252.2  479.40  5295.3  480.81
  5313.4  480.62  5318.8  481.21  5337.6  481.44  5396.8  483.22  5409.6  483.20
#Mann=5,-1,0
  4654.1    0.05       0  4871.6    0.07       0  5026.8    0.05       0
  5030.8    0.07       0  5049.7    0.05       0
Bank Sta=5026.8,5030.8
Exp/Cntr=0.3,0.1

Type RM Length L Ch R = 1,394,145,145,145
BEGIN DESCRIPTION:
H21294
END DESCRIPTION:
XS GIS Cut Line= 4
      2483452.52     13848559.84      2483079.36     13848478.94
      2482941.05     13848486.77      2482674.91     13848708.56
#Sta/Elev= 30
  4554.2  478.91  4599.2  479.42  4604.3  478.87  4633.5  479.39  4648.4  478.71
  4684.7  478.90  4832.7  475.78  4889.3  475.08  4909.8  476.55  4920.0  474.55
  4928.1  473.81  4933.2  475.71  4940.7  475.30  4950.1  475.87  4952.9  473.42
  4953.1  473.24  4953.3  472.74  4956.8  472.74  4957.1  473.24  4970.4  474.08
  4990.5  476.17  5000.5  476.15  5030.5  473.84  5077.8  474.11  5205.3  476.57
  5262.6  477.00  5304.3  478.36  5326.4  479.67  5382.4  481.11  5421.0  481.22
#Mann=5,-1,0
  4554.2    0.05       0  4832.7    0.07       0  4952.9    0.05       0
  4953.1    0.05       0  4957.1    0.05       0
Bank Sta=4953.1,4957.1
Exp/Cntr=0.3,0.1

Type RM Length L Ch R = 1,249,199,199,199
BEGIN DESCRIPTION:
H21293
END DESCRIPTION:
XS GIS Cut Line= 4
      2483504.67     13848450.23      2483092.40     13848324.98
      2482867.99     13848371.95      2482675.42     13848660.80
#Sta/Elev= 30
  4499.6  474.39  4541.1  473.52  4568.2  473.72  4573.4  473.36  4601.1  473.85
  4606.3  473.24  4672.0  473.58  4710.1  473.34  4770.7  473.69  4775.9  473.43
  4823.2  473.77  4883.5  473.19  4920.7  472.58  4978.9  471.22  5007.5  467.15
  5007.8  466.65  5011.3  466.65  5011.5  467.15  5019.8  467.36  5030.0  468.31
  5040.2  470.12  5054.1  471.64  5070.8  471.39  5104.0  471.70  5164.6  471.53
  5271.6  474.04  5388.1  477.55  5409.1  477.83  5424.2  478.69  5506.9  480.01
#Mann=5,-1,0
  4499.6    0.05       0  4883.5    0.07       0  4920.7    0.05       0
  5007.5    0.05       0  5011.5    0.05       0
Bank Sta=5007.5,5011.5
Exp/Cntr=0.3,0.1

Type RM Length L Ch R = 1,50,0,0,0
BEGIN DESCRIPTION:
H21292
END DESCRIPTION:
XS GIS Cut Line= 4
      2483525.54     13848288.44      2483024.56     13848139.71
      2482831.45     13848199.73      2482669.84     13848588.13
#Sta/Elev= 30
  4410.2  469.54  4548.4  469.42  4719.7  472.43  4818.2  470.85  4869.7  469.83
  4921.9  467.96  4929.4  467.13  4932.3  465.91  4935.7  467.13  4963.0  463.07
  4968.2  463.43  4972.2  461.97  4972.5  461.47  4976.0  461.47  4976.2  461.97
  5000.8  464.89  5006.0  462.75  5026.6  465.05  5033.3  467.07  5038.6  465.69
  5047.5  467.72  5062.7  468.07  5103.7  467.78  5120.8  466.61  5137.1  467.43
  5184.0  468.11  5373.3  473.06  5450.3  476.58  5503.4  476.64  5555.7  477.96
#Mann=5,-1,0
  4410.2    0.05       0  4818.2    0.07       0  4972.2    0.05       0
  4976.2    0.07       0  5062.7    0.05       0
Bank Sta=4972.2,4976.2
Exp/Cntr=0.3,0.1

Chan Stop Cuts=-1