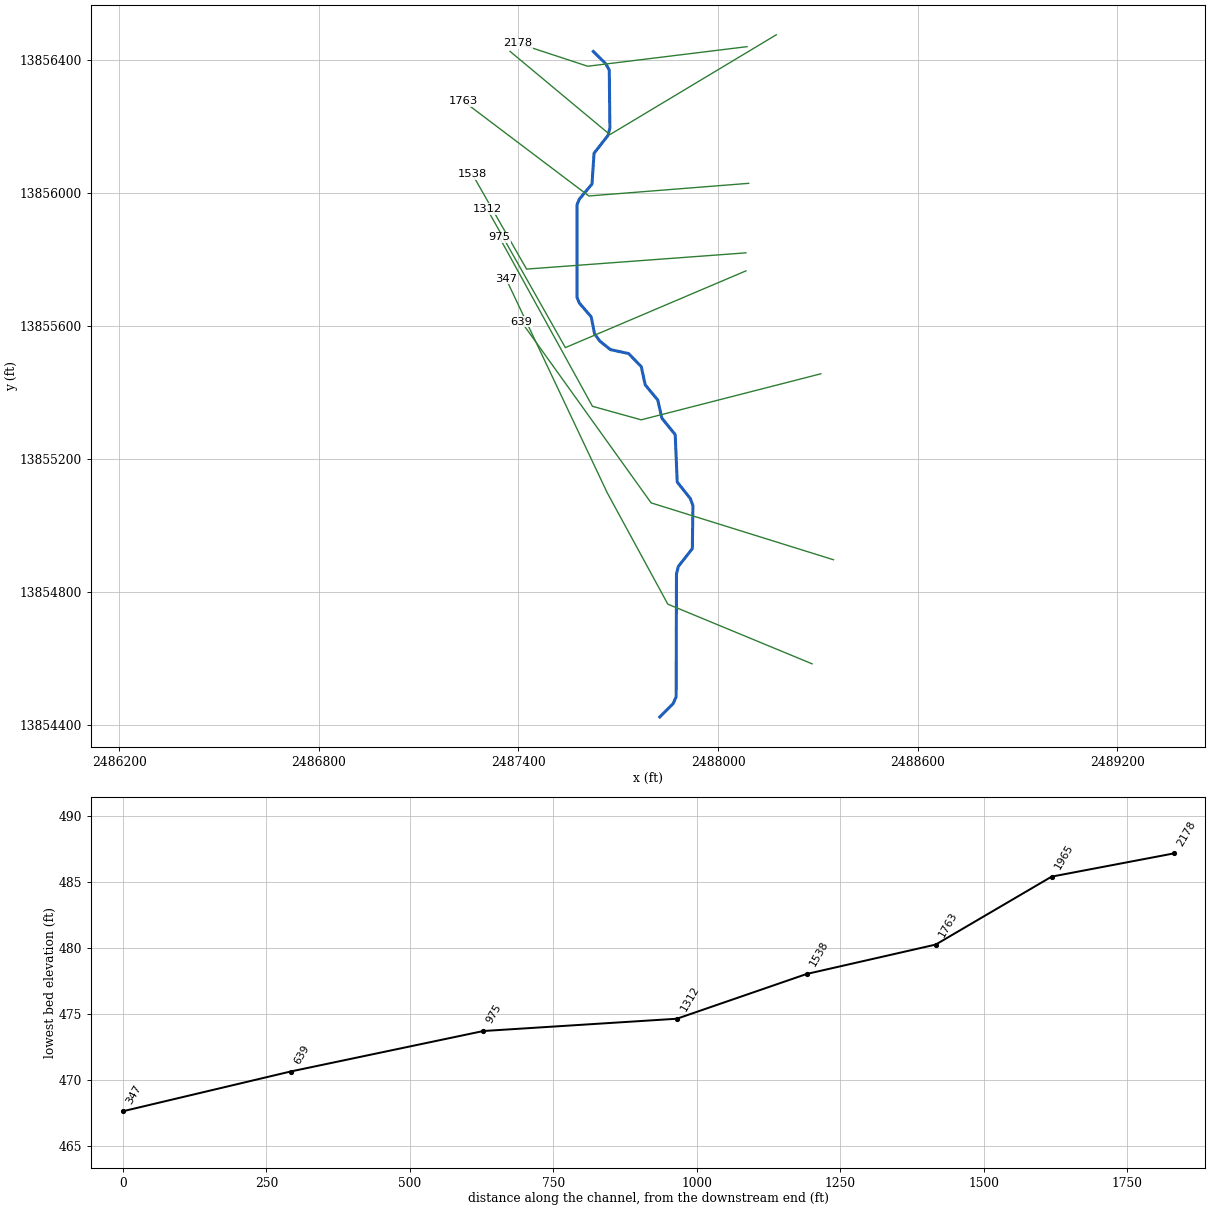
--- StreamM039a.prj (project) ---

Proj Title=StreamM039a Base Level Engineering
Current Plan=p01
Default Exp/Contr=0.3,0.1
English Units
Geom File=g01
Flow File=f01
Plan File=p01
BEGIN DESCRIPTION:
StreamM039a
END DESCRIPTION:

--- StreamM039a.p01 (plan) ---

Plan Title=Multiple Run
Short Identifier=Multiple
Geom File=g01
Flow File=f01
Subcritical Flow
K Sum by GR= 0
Std Step Tol= 0.01
Critical Tol= 0.01
Num of Std Step Trials= 20
Max Error Tol= 0.3
Flow Tol Ratio= 0.001
Split Flow NTrial= 30
Split Flow Tol= 0.02
Split Flow Ratio= 0.02
Log Output Level= 0
Friction Slope Method= 1
Unsteady Friction Slope Method= 2
Unsteady Bridges Friction Slope Method= 1
Parabolic Critical Depth
Global Vel Dist=  1 , 1 , 1
Global Log Level= 0
CheckData=True
Encroach Param= -1, 0, 0, 0
BEGIN DESCRIPTION:
Multiple Run
END DESCRIPTION:

--- StreamM039a.f01 (steady flow) ---

Flow Title=Multiple
Number of Profiles=7
Profile Names=10-year,25-year,50-year,1pct_min,100-year,1pct_plu,500-year
River Rch & RM= StreamM039a,Reach-1,2178
     351     541     705     447     891    1779    1406
Boundary for River Rch & Prof#=StreamM039a,Reach-1,1
Up Type=0
Dn Type=3
Dn Slope=0.005
Boundary for River Rch & Prof#=StreamM039a,Reach-1,2
Up Type=0
Dn Type=3
Dn Slope=0.005
Boundary for River Rch & Prof#=StreamM039a,Reach-1,3
Up Type=0
Dn Type=3
Dn Slope=0.005
Boundary for River Rch & Prof#=StreamM039a,Reach-1,4
Up Type=0
Dn Type=3
Dn Slope=0.005
Boundary for River Rch & Prof#=StreamM039a,Reach-1,5
Up Type=0
Dn Type=3
Dn Slope=0.005
Boundary for River Rch & Prof#=StreamM039a,Reach-1,6
Up Type=0
Dn Type=3
Dn Slope=0.005
Boundary for River Rch & Prof#=StreamM039a,Reach-1,7
Up Type=0
Dn Type=3
Dn Slope=0.005

--- StreamM039a.g01 (geometry) ---

Geom Title=Existing Conditions

River Reach=StreamM039a,Reach-1
Reach XY= 30
      2487625.00     13856425.00      2487662.08     13856388.50
      2487673.11     13856369.22      2487674.93     13856195.03
      2487669.26     13856172.66      2487627.36     13856119.02
      2487621.14     13856026.60      2487583.14     13855981.06
      2487576.22     13855964.50      2487576.20     13855685.50
      2487583.09     13855668.92      2487618.85     13855627.15
      2487628.86     13855576.42      2487644.63     13855554.53
      2487676.46     13855528.90      2487731.31     13855516.95
      2487769.27     13855477.55      2487781.11     13855422.84
      2487818.92     13855377.20      2487831.12     13855322.82
      2487871.24     13855273.44      2487877.27     13855130.94
      2487916.86     13855081.05      2487924.49     13855059.78
      2487922.75     13854930.94      2487880.75     13854877.33
      2487875.07     13854854.97      2487874.04     13854485.40
      2487864.95     13854465.02      2487825.00     13854425.00

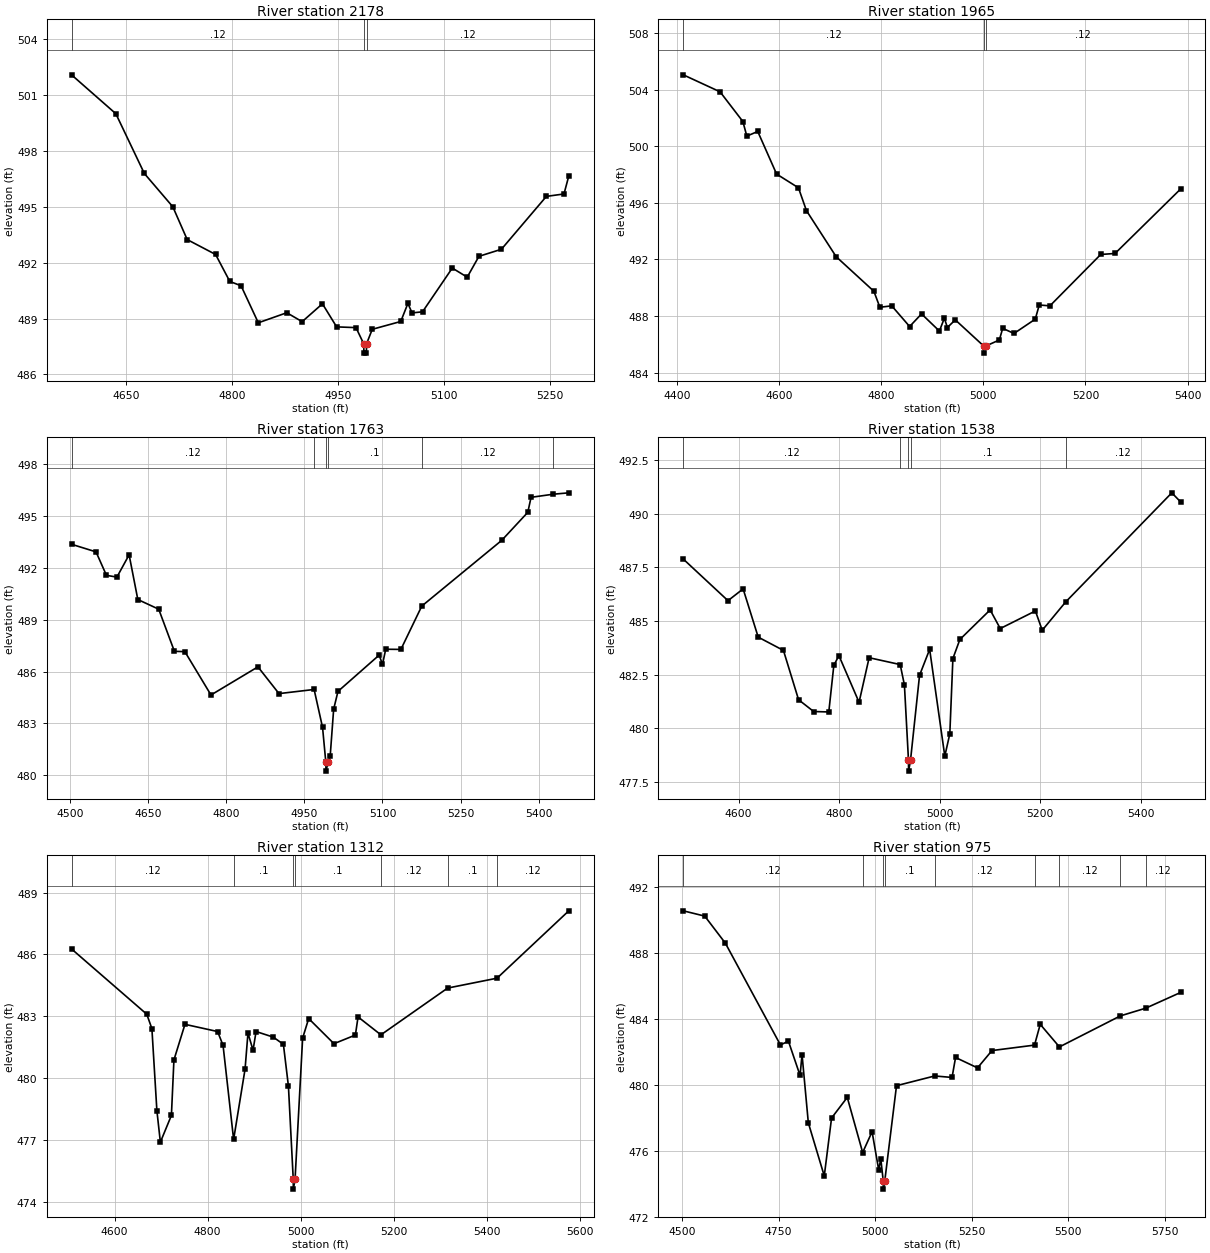
Type RM Length L Ch R = 1,2178,213,213,213
BEGIN DESCRIPTION:
H21302
END DESCRIPTION:
XS GIS Cut Line= 3
      2488087.23     13856439.35      2487608.16     13856380.47
      2487398.50     13856449.48
#Sta/Elev= 30
  4572.7  502.09  4635.4  500.00  4675.7  496.79  4716.0  495.00  4736.3  493.24
  4776.5  492.44  4796.6  490.99  4812.5  490.76  4836.9  488.77  4877.2  489.31
  4898.9  488.83  4927.6  489.79  4947.7  488.55  4975.1  488.51  4986.0  487.64
  4986.3  487.14  4989.8  487.14  4990.0  487.64  4998.1  488.42  5038.4  488.84
  5048.5  489.81  5054.4  489.30  5069.2  489.36  5111.3  491.71  5132.4  491.22
  5149.0  492.34  5180.8  492.72  5244.4  495.56  5269.3  495.69  5276.1  496.66
#Mann=3,-1,0
  4572.7    0.12       0  4986.0    0.05       0  4990.0    0.12       0
Bank Sta=4986,4990
Exp/Cntr=0.3,0.1

Type RM Length L Ch R = 1,1965,202,202,202
BEGIN DESCRIPTION:
StreamM039a 1.0
END DESCRIPTION:
XS GIS Cut Line= 3
      2488175.04     13856475.02      2487675.00     13856175.00
      2487374.96     13856425.03
#Sta/Elev= 30
  4412.5  505.04  4484.5  503.84  4529.2  501.74  4536.9  500.71  4558.3  501.04
  4595.2  498.03  4638.0  497.06  4653.6  495.45  4711.9  492.19  4785.7  489.75
  4797.4  488.62  4820.7  488.72  4855.7  487.26  4879.0  488.15  4914.0  486.94
  4923.7  487.85  4929.6  487.19  4945.1  487.73  5000.8  485.88  5001.0  485.38
  5004.8  485.88  5031.4  486.31  5037.9  487.13  5060.1  486.77  5101.7  487.78
  5109.5  488.78  5130.4  488.72  5229.9  492.35  5257.9  492.42  5386.2  496.97
#Mann=3,-1,0
  4412.5    0.12       0  5000.8    0.05       0  5004.8    0.12       0
Bank Sta=5000.8,5004.8
Exp/Cntr=0.3,0.1

Type RM Length L Ch R = 1,1763,225,225,225
BEGIN DESCRIPTION:
MXS18483
END DESCRIPTION:
XS GIS Cut Line= 3
      2488091.81     13856028.58      2487611.66     13855990.60
      2487234.60     13856275.43
#Sta/Elev= 30
  4503.3  493.37  4550.3  492.93  4570.3  491.57  4590.4  491.47  4613.8  492.76
  4630.5  490.17  4670.6  489.61  4700.7  487.17  4720.8  487.15  4770.9  484.64
  4861.0  486.27  4901.4  484.72  4968.8  484.96  4985.0  482.76  4991.3  480.73
  4991.6  480.23  4995.3  480.73  4999.6  481.09  5006.3  483.82  5014.6  484.85
  5093.6  486.95  5100.0  486.41  5106.2  487.29  5135.3  487.28  5175.4  489.79
  5328.9  493.60  5378.8  495.22  5385.1  496.09  5427.8  496.27  5457.5  496.35
#Mann=6,-1,0
  4503.3    0.12       0  4968.8     0.1       0  4991.3    0.05       0
  4995.3     0.1       0  5175.4    0.12       0  5427.8   0.035       0
Bank Sta=4991.3,4995.3
Exp/Cntr=0.3,0.1

Type RM Length L Ch R = 1,1538,226,226,226
BEGIN DESCRIPTION:
MXS18482
END DESCRIPTION:
XS GIS Cut Line= 3
      2488083.63     13855819.69      2487424.49     13855770.87
      2487261.73     13856055.70
#Sta/Elev= 30
  4489.9  487.89  4578.8  485.95  4608.9  486.50  4638.9  484.25  4689.1  483.63
  4719.2  481.33  4749.2  480.78  4779.3  480.76  4789.3  482.93  4799.4  483.39
  4839.5  481.21  4859.5  483.29  4921.3  482.97  4929.7  482.02  4937.8  478.50
  4938.0  478.00  4941.8  478.50  4959.8  482.47  4979.9  483.68  5010.0  478.70
  5020.0  479.74  5026.1  483.25  5040.0  484.14  5100.2  485.52  5120.3  484.65
  5190.2  485.47  5203.8  484.57  5250.4  485.89  5461.5  490.98  5478.9  490.56
#Mann=5,-1,0
  4489.9    0.12       0  4921.3     0.1       0  4937.8    0.05       0
  4941.8     0.1       0  5250.4    0.12       0
Bank Sta=4937.8,4941.8
Exp/Cntr=0.3,0.1

Type RM Length L Ch R = 1,1312,337,337,337
BEGIN DESCRIPTION:
MXS18481
END DESCRIPTION:
XS GIS Cut Line= 3
      2488083.71     13855765.46      2487541.13     13855534.86
      2487305.84     13855951.35
#Sta/Elev= 30
  4507.6  486.27  4669.2  483.10  4680.2  482.40  4690.9  478.42  4698.4  476.89
  4722.1  478.19  4727.5  480.88  4751.2  482.61  4821.3  482.26  4833.0  481.59
  4855.7  477.02  4880.3  480.44  4886.5  482.19  4897.4  481.35  4903.9  482.26
  4940.8  481.99  4962.6  481.64  4973.4  479.61  4983.7  475.11  4984.0  474.61
  4987.7  475.11  5003.9  481.94  5016.9  482.89  5071.2  481.67  5117.2  482.09
  5122.9  482.97  5172.0  482.10  5315.3  484.37  5421.4  484.85  5575.5  488.12
#Mann=7,-1,0
  4507.6    0.12       0  4855.7     0.1       0  4983.7    0.05       0
  4987.7     0.1       0  5172.0    0.12       0  5315.3     0.1       0
  5421.4    0.12       0
Bank Sta=4983.7,4987.7
Exp/Cntr=0.3,0.1

Type RM Length L Ch R = 1,975,336,336,336
BEGIN DESCRIPTION:
MXS18480
END DESCRIPTION:
XS GIS Cut Line= 4
      2488308.86     13855456.21      2487769.00     13855317.85
      2487622.51     13855358.54      2487343.09     13855865.83
#Sta/Elev= 30
  4502.9  490.55  4558.5  490.23  4611.9  488.59  4754.6  482.42  4775.3  482.65
  4805.5  480.57  4810.6  481.84  4826.9  477.70  4868.2  474.48  4887.1  477.99
  4927.8  479.24  4967.7  475.90  4992.1  477.16  5009.4  474.83  5014.6  475.53
  5021.0  474.18  5021.3  473.68  5025.0  474.18  5055.4  479.95  5154.3  480.54
  5199.3  480.45  5208.4  481.66  5265.3  481.03  5302.8  482.08  5413.0  482.41
  5427.8  483.67  5477.5  482.30  5635.3  484.18  5701.3  484.65  5791.4  485.60
#Mann=9,-1,0
  4502.9    0.12       0  4967.7     0.1       0  5021.0    0.05       0
  5025.0     0.1       0  5154.3    0.12       0  5413.0     0.1       0
  5477.5    0.12       0  5635.3     0.1       0  5701.3    0.12       0
Bank Sta=5021,5025
Exp/Cntr=0.3,0.1

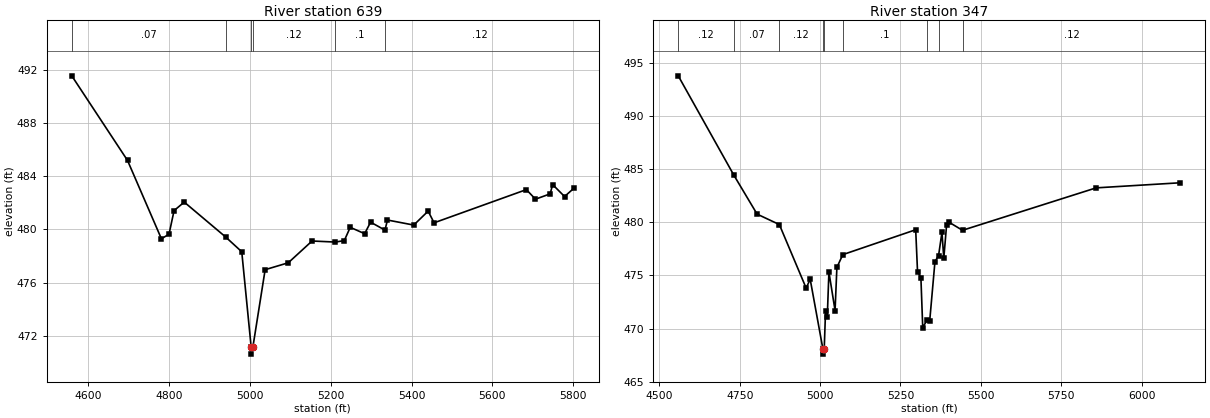
Type RM Length L Ch R = 1,639,292,292,292
BEGIN DESCRIPTION:
MXS18479
END DESCRIPTION:
XS GIS Cut Line= 3
      2488346.83     13854897.37      2487798.84     13855068.28
      2487409.12     13855612.26
#Sta/Elev= 30
  4558.6  491.57  4696.6  485.20  4780.5  479.30  4799.4  479.64  4811.9  481.42
  4837.1  482.06  4939.3  479.44  4979.5  478.32  5002.9  471.11  5003.1  470.61
  5006.9  471.11  5037.4  476.97  5094.7  477.49  5153.6  479.13  5211.3  479.05
  5233.4  479.16  5248.1  480.16  5283.8  479.68  5298.5  480.55  5334.1  479.95
  5340.3  480.71  5405.4  480.33  5441.0  481.38  5455.7  480.50  5684.2  483.00
  5706.8  482.28  5743.1  482.68  5749.3  483.38  5778.8  482.48  5801.8  483.10
#Mann=6,-1,0
  4558.6    0.07       0  4939.3    0.12       0  5002.9    0.05       0
  5006.9    0.12       0  5211.3     0.1       0  5334.1    0.12       0
Bank Sta=5002.9,5006.9
Exp/Cntr=0.3,0.1

Type RM Length L Ch R = 1,347,0,0,0
BEGIN DESCRIPTION:
H21301
END DESCRIPTION:
XS GIS Cut Line= 4
      2488282.66     13854584.59      2487849.04     13854763.93
      2487667.04     13855098.48      2487362.75     13855741.75
#Sta/Elev= 30
  4558.8  493.78  4731.9  484.43  4804.1  480.77  4873.3  479.79  4956.7  473.81
  4969.2  474.65  5008.7  468.10  5009.0  467.60  5012.9  468.10  5017.0  471.64
  5022.4  471.11  5027.5  475.33  5046.6  471.70  5052.3  475.76  5070.7  476.96
  5297.4  479.30  5303.1  475.37  5313.6  474.80  5319.3  470.10  5333.7  470.85
  5341.1  470.76  5357.3  476.30  5368.5  476.86  5379.1  479.06  5384.8  476.61
  5393.5  479.75  5401.0  480.01  5443.0  479.25  5858.6  483.24  6120.5  483.72
#Mann=9,-1,0
  4558.8    0.12       0  4731.9    0.07       0  4873.3    0.12       0
  5008.7    0.05       0  5012.9    0.12       0  5070.7     0.1       0
  5333.7    0.12       0  5368.5     0.1       0  5443.0    0.12       0
Bank Sta=5008.7,5012.9
Exp/Cntr=0.3,0.1

Chan Stop Cuts=-1