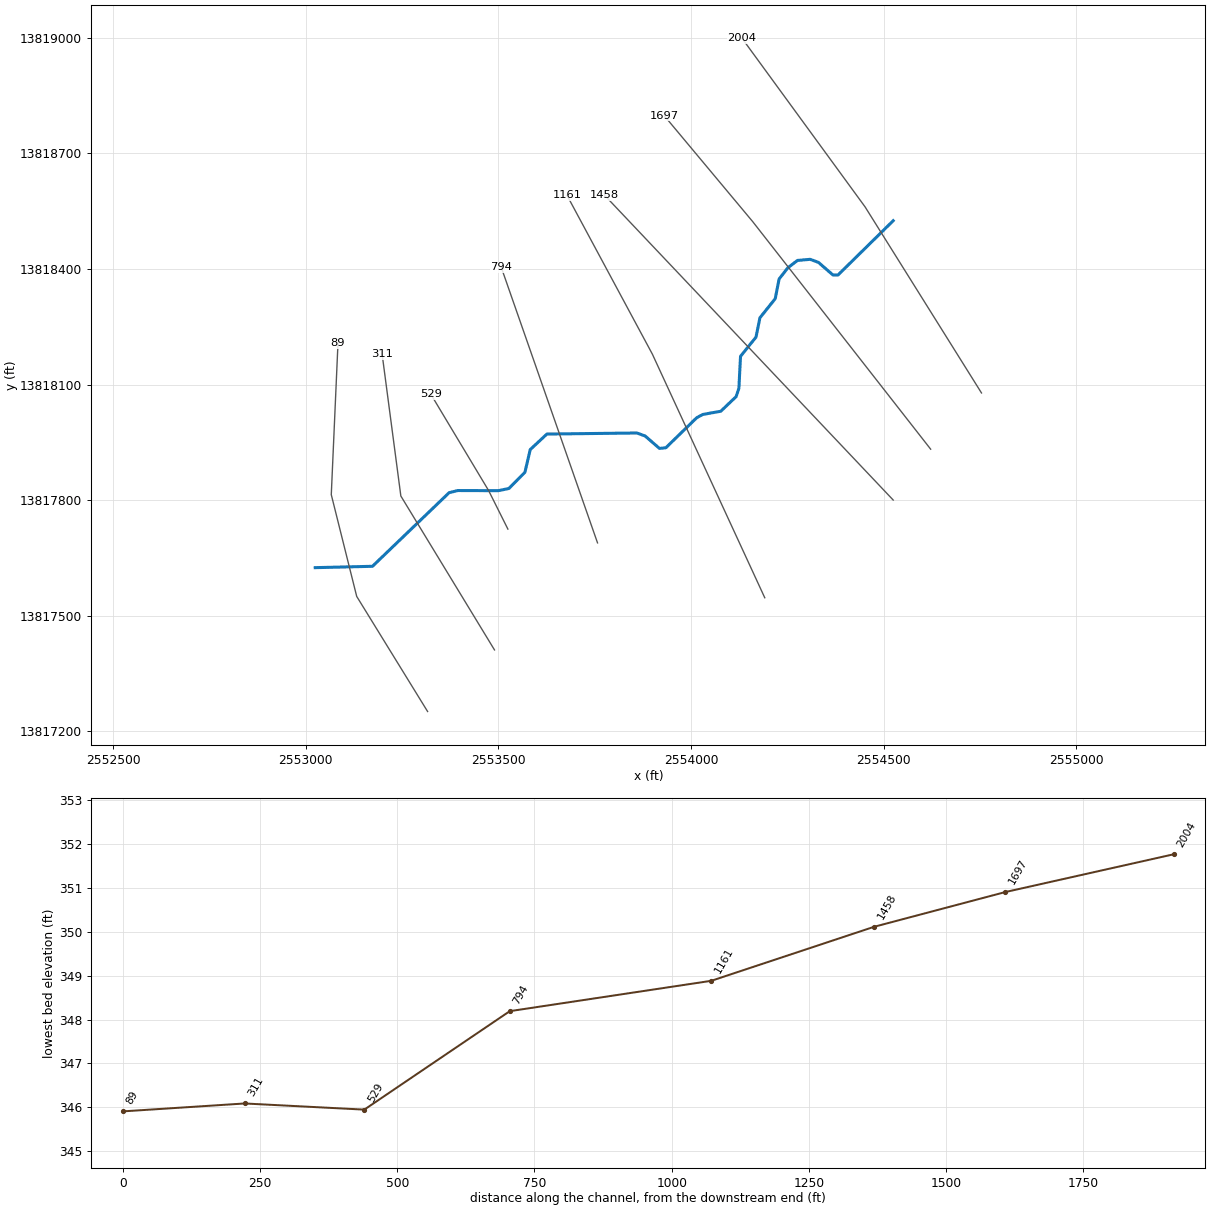
--- StreamM04.prj (project) ---

Proj Title=StreamM04 Base Level Engineering
Current Plan=p01
Default Exp/Contr=0.3,0.1
English Units
Geom File=g01
Flow File=f01
Plan File=p01
BEGIN DESCRIPTION:
StreamM04
END DESCRIPTION:

--- StreamM04.p01 (plan) ---

Plan Title=Multiple Run
Short Identifier=Multiple
Geom File=g01
Flow File=f01
Subcritical Flow
K Sum by GR= 0
Std Step Tol= 0.01
Critical Tol= 0.01
Num of Std Step Trials= 20
Max Error Tol= 0.3
Flow Tol Ratio= 0.001
Split Flow NTrial= 30
Split Flow Tol= 0.02
Split Flow Ratio= 0.02
Log Output Level= 0
Friction Slope Method= 1
Unsteady Friction Slope Method= 2
Unsteady Bridges Friction Slope Method= 1
Parabolic Critical Depth
Global Vel Dist=  1 , 1 , 1
Global Log Level= 0
CheckData=True
Encroach Param= -1, 0, 0, 0
BEGIN DESCRIPTION:
Multiple Run
END DESCRIPTION:

--- StreamM04.f01 (steady flow) ---

Flow Title=Multiple
Number of Profiles=7
Profile Names=10-year,25-year,50-year,1pct_min,100-year,1pct_plu,500-year
River Rch & RM= StreamM04,Reach-1,2004
     591     934    1238     795    1586    3164    2573
Boundary for River Rch & Prof#=StreamM04,Reach-1,1
Up Type=0
Dn Type=3
Dn Slope=0.005
Boundary for River Rch & Prof#=StreamM04,Reach-1,2
Up Type=0
Dn Type=3
Dn Slope=0.005
Boundary for River Rch & Prof#=StreamM04,Reach-1,3
Up Type=0
Dn Type=3
Dn Slope=0.005
Boundary for River Rch & Prof#=StreamM04,Reach-1,4
Up Type=0
Dn Type=3
Dn Slope=0.005
Boundary for River Rch & Prof#=StreamM04,Reach-1,5
Up Type=0
Dn Type=3
Dn Slope=0.005
Boundary for River Rch & Prof#=StreamM04,Reach-1,6
Up Type=0
Dn Type=3
Dn Slope=0.005
Boundary for River Rch & Prof#=StreamM04,Reach-1,7
Up Type=0
Dn Type=3
Dn Slope=0.005

--- StreamM04.g01 (geometry) ---

Geom Title=Existing Conditions

River Reach=StreamM04,Reach-1
Reach XY= 30
      2554525.00     13818525.00      2554381.73     13818384.14
      2554368.45     13818384.33      2554331.03     13818416.88
      2554309.58     13818424.85      2554276.43     13818421.93
      2554251.16     13818402.44      2554228.86     13818373.64
      2554218.89     13818322.84      2554179.16     13818273.28
      2554168.88     13818222.82      2554128.83     13818173.41
      2554124.53     13818090.09      2554117.26     13818068.55
      2554077.57     13818030.74      2554031.09     13818022.43
      2554015.34     13818014.17      2553935.05     13817936.12
      2553918.47     13817934.29      2553881.19     13817966.53
      2553859.84     13817974.34      2553626.25     13817971.55
      2553583.03     13817931.36      2553569.25     13817872.45
      2553527.70     13817830.37      2553500.20     13817824.70
      2553394.99     13817825.02      2553372.55     13817819.53
      2553173.55     13817628.50      2553025.00     13817625.00

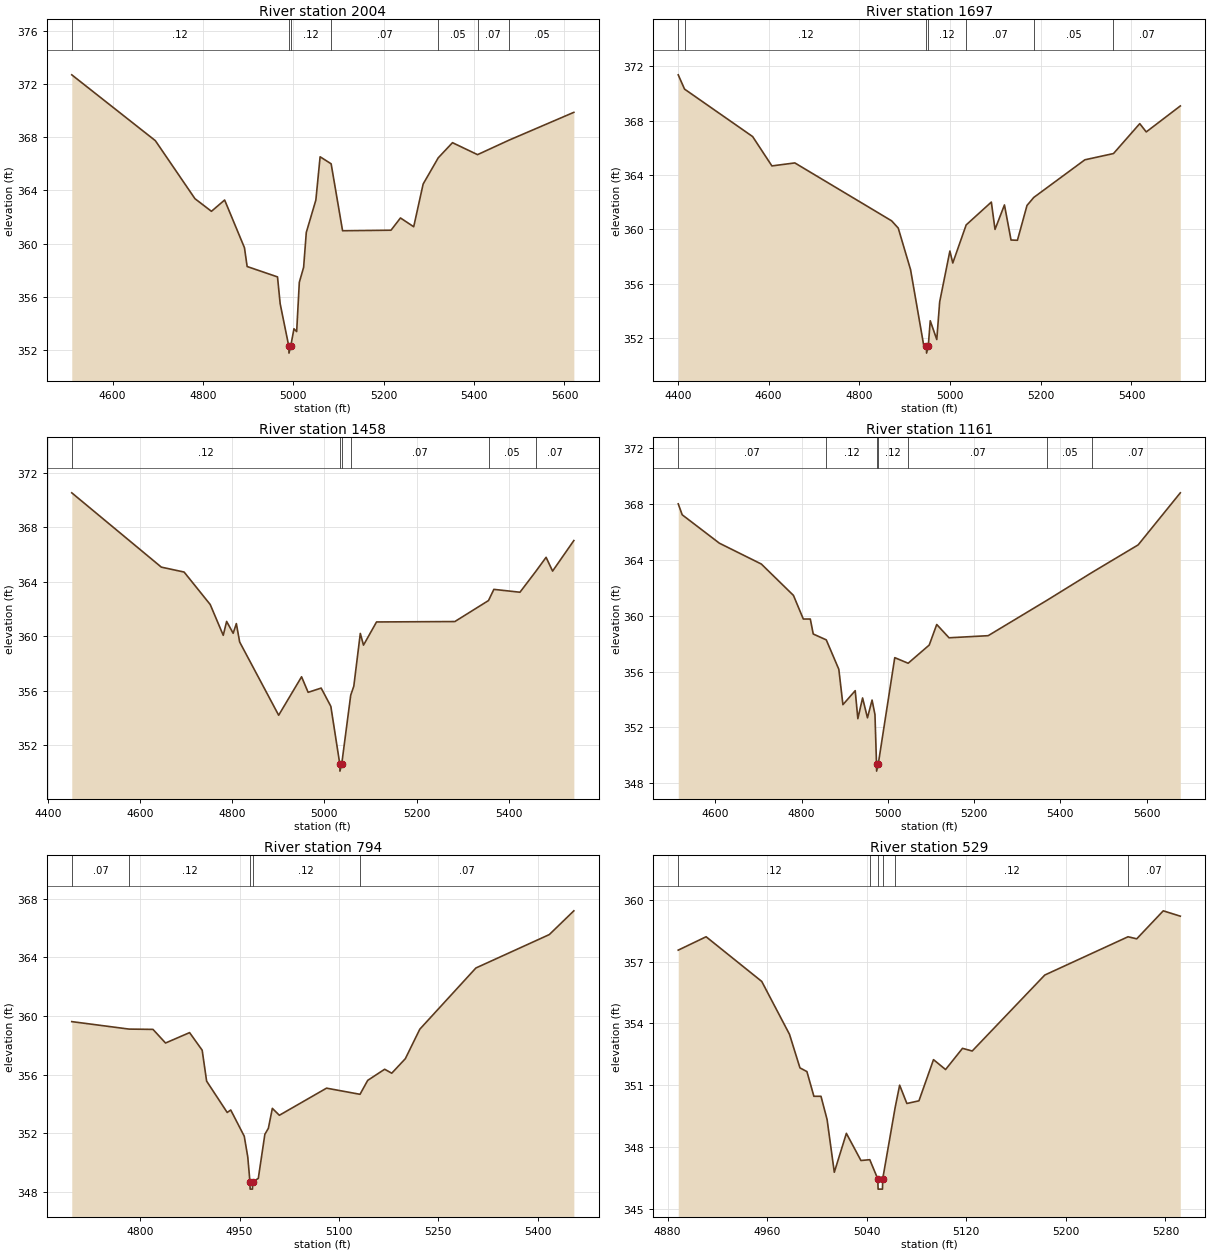
Type RM Length L Ch R = 1,2004,307,307,307
BEGIN DESCRIPTION:
H21309
END DESCRIPTION:
XS GIS Cut Line= 3
      2554754.14     13818078.21      2554452.08     13818560.82
      2554132.61     13818998.36
#Sta/Elev= 30
  4509.6  372.68  4694.6  367.73  4782.2  363.37  4818.7  362.42  4847.9  363.27
  4891.8  359.68  4897.7  358.27  4964.9  357.49  4970.8  355.47  4990.0  352.26
  4990.3  351.76  4994.0  352.26  5001.3  353.59  5007.3  353.38  5013.2  357.09
  5022.7  358.21  5028.6  360.83  5049.8  363.27  5059.2  366.52  5083.6  365.99
  5108.9  360.96  5216.1  361.00  5237.0  361.92  5266.3  361.26  5287.2  364.47
  5320.6  366.44  5352.1  367.58  5407.6  366.68  5477.3  367.77  5620.7  369.86
#Mann=7,-1,0
  4509.6    0.12       0  4990.0    0.05       0  4994.0    0.12       0
  5083.6    0.07       0  5320.6    0.05       0  5407.6    0.07       0
  5477.3    0.05       0
Bank Sta=4990,4994
Exp/Cntr=0.3,0.1

Type RM Length L Ch R = 1,1697,239,239,239
BEGIN DESCRIPTION:
H21308
END DESCRIPTION:
XS GIS Cut Line= 3
      2554622.24     13817932.33      2554160.42     13818522.62
      2553931.26     13818796.91
#Sta/Elev= 30
  4400.8  371.37  4414.7  370.32  4564.8  366.83  4607.3  364.67  4657.9  364.89
  4871.3  360.63  4885.8  360.10  4913.0  357.04  4941.9  351.49  4948.0  351.40
  4948.3  350.90  4952.0  351.40  4956.4  353.28  4970.8  351.90  4977.2  354.67
  4999.7  358.41  5006.1  357.53  5035.6  360.33  5091.1  362.01  5099.2  360.00
  5120.0  361.80  5134.5  359.22  5148.6  359.20  5169.7  361.76  5184.6  362.35
  5297.3  365.12  5360.4  365.58  5418.3  367.78  5432.6  367.17  5507.7  369.08
#Mann=7,-1,0
  4400.8    0.07       0  4414.7    0.12       0  4948.0    0.05       0
  4952.0    0.12       0  5035.6    0.07       0  5184.6    0.05       0
  5360.4    0.07       0
Bank Sta=4948,4952
Exp/Cntr=0.3,0.1

Type RM Length L Ch R = 1,1458,297,297,297
BEGIN DESCRIPTION:
H21307
END DESCRIPTION:
XS GIS Cut Line= 2
      2554525.02     13817800.38      2553776.00     13818591.01
#Sta/Elev= 30
  4452.0  370.52  4646.3  365.07  4695.7  364.71  4752.3  362.33  4780.6  360.07
  4787.9  361.09  4802.1  360.22  4809.0  360.93  4816.2  359.58  4900.8  354.21
  4950.5  357.03  4964.7  355.89  4993.0  356.20  5014.0  354.86  5033.5  350.61
  5033.7  350.11  5037.5  350.61  5057.1  355.68  5063.8  356.34  5077.9  360.21
  5084.8  359.35  5113.1  361.05  5283.0  361.08  5356.0  362.62  5367.6  363.44
  5424.2  363.23  5458.2  364.74  5480.9  365.79  5495.0  364.78  5541.1  367.02
#Mann=6,-1,0
  4452.0    0.12       0  5033.5    0.05       0  5037.5    0.12       0
  5057.1    0.07       0  5356.0    0.05       0  5458.2    0.07       0
Bank Sta=5033.5,5037.5
Exp/Cntr=0.3,0.1

Type RM Length L Ch R = 1,1161,367,367,367
BEGIN DESCRIPTION:
H21306
END DESCRIPTION:
XS GIS Cut Line= 3
      2554191.66     13817546.94      2553900.00     13818178.87
      2553678.32     13818591.05
#Sta/Elev= 30
  4514.0  367.98  4523.2  367.20  4609.4  365.17  4706.7  363.68  4781.1  361.44
  4804.0  359.75  4820.2  359.75  4827.0  358.68  4857.2  358.26  4886.3  356.16
  4895.8  353.63  4924.3  354.63  4930.4  352.63  4941.4  354.11  4952.7  352.69
  4963.4  353.96  4970.1  352.92  4973.7  349.38  4973.9  348.88  4977.7  349.38
  5016.0  356.99  5047.0  356.59  5095.9  357.89  5113.3  359.36  5141.8  358.41
  5232.5  358.56  5370.0  361.11  5472.8  363.07  5580.3  365.05  5678.0  368.77
#Mann=7,-1,0
  4514.0    0.07       0  4857.2    0.12       0  4973.7    0.05       0
  4977.7    0.12       0  5047.0    0.07       0  5370.0    0.05       0
  5472.8    0.07       0
Bank Sta=4973.7,4977.7
Exp/Cntr=0.3,0.1

Type RM Length L Ch R = 1,794,265,265,265
BEGIN DESCRIPTION:
H21305
END DESCRIPTION:
XS GIS Cut Line= 2
      2553757.65     13817689.26      2553507.65     13818404.53
#Sta/Elev= 30
  4696.8  359.62  4783.2  359.11  4819.4  359.09  4838.3  358.16  4874.6  358.87
  4893.6  357.67  4900.3  355.56  4931.4  353.42  4936.7  353.59  4957.1  351.80
  4962.4  350.39  4965.7  348.69  4966.0  348.19  4969.5  348.19  4969.7  348.69
  4978.3  348.92  4988.2  351.93  4993.5  352.34  4999.5  353.70  5010.1  353.23
  5081.3  355.08  5131.8  354.66  5143.4  355.61  5169.0  356.37  5179.7  356.10
  5200.2  357.09  5222.0  359.10  5306.7  363.28  5417.5  365.56  5454.5  367.18
#Mann=5,-1,0
  4696.8    0.07       0  4783.2    0.12       0  4965.7    0.05       0
  4969.7    0.12       0  5131.8    0.07       0
Bank Sta=4965.7,4969.7
Exp/Cntr=0.3,0.1

Type RM Length L Ch R = 1,529,218,218,218
BEGIN DESCRIPTION:
StreamM04 1.0
END DESCRIPTION:
XS GIS Cut Line= 3
      2553525.00     13817725.00      2553475.00     13817825.00
      2553324.98     13818075.04
#Sta/Elev= 30
  4888.6  357.56  4911.0  358.21  4955.7  356.04  4978.0  353.47  4986.4  351.84
  4992.0  351.66  4997.6  350.46  5003.3  350.46  5008.2  349.33  5014.0  346.77
  5023.7  348.66  5035.4  347.34  5042.5  347.38  5048.9  346.45  5049.2  345.95
  5052.7  345.95  5052.9  346.45  5062.9  349.92  5066.5  351.00  5072.3  350.11
  5082.0  350.24  5093.7  352.24  5103.4  351.76  5117.0  352.79  5124.8  352.66
  5183.1  356.35  5250.0  358.21  5257.0  358.11  5278.3  359.47  5292.0  359.21
#Mann=6,-1,0
  4888.6    0.12       0  5042.5    0.07       0  5048.9    0.05       0
  5052.9    0.07       0  5062.9    0.12       0  5250.0    0.07       0
Bank Sta=5048.9,5052.9
Exp/Cntr=0.3,0.1

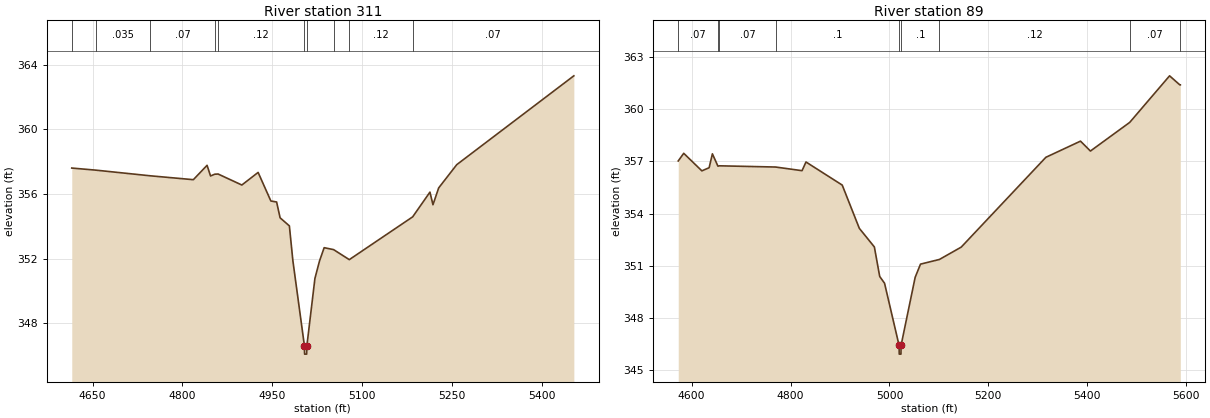
Type RM Length L Ch R = 1,311,222,222,222
BEGIN DESCRIPTION:
H21304
END DESCRIPTION:
XS GIS Cut Line= 3
      2553490.26     13817411.54      2553247.22     13817810.82
      2553198.61     13818178.89
#Sta/Elev= 30
  4615.2  357.61  4655.5  357.48  4746.4  357.13  4818.3  356.89  4841.2  357.78
  4847.0  357.12  4854.1  357.23  4859.7  357.24  4899.3  356.56  4926.5  357.34
  4947.8  355.57  4957.4  355.51  4963.2  354.53  4978.7  354.03  4984.6  351.86
  5003.9  346.59  5004.1  346.09  5007.6  346.09  5007.9  346.59  5021.4  350.78
  5029.0  351.85  5036.8  352.68  5052.6  352.56  5078.8  351.94  5184.7  354.59
  5213.5  356.12  5218.6  355.34  5228.1  356.38  5258.3  357.82  5453.9  363.32
#Mann=10,-1,0
  4615.2    0.07       0  4655.5   0.035       0  4746.4    0.07       0
  4854.1     0.1       0  4859.7    0.12       0  5003.9    0.05       0
  5007.9    0.12       0  5052.6     0.1       0  5078.8    0.12       0
  5184.7    0.07       0
Bank Sta=5003.9,5007.9
Exp/Cntr=0.3,0.1

Type RM Length L Ch R = 1,89,0,0,0
BEGIN DESCRIPTION:
H21303
END DESCRIPTION:
XS GIS Cut Line= 4
      2553316.65     13817251.81      2553132.64     13817550.40
      2553066.67     13817814.29      2553084.03     13818206.66
#Sta/Elev= 30
  4572.8  357.03  4583.9  357.47  4620.6  356.46  4635.3  356.64  4641.9  357.44
  4653.1  356.73  4656.0  356.75  4769.7  356.68  4823.2  356.47  4831.2  356.97
  4904.5  355.64  4939.1  353.15  4969.5  352.08  4980.3  350.38  4990.1  349.99
  5019.5  346.41  5019.8  345.91  5023.3  345.91  5023.5  346.41  5052.0  350.33
  5062.8  351.09  5101.1  351.36  5145.2  352.07  5316.4  357.24  5386.4  358.17
  5406.5  357.60  5486.0  359.25  5566.6  361.93  5587.3  361.41  5588.3  361.41
#Mann=9,-1,0
  4572.8    0.07       0  4653.1   0.035       0  4656.0    0.07       0
  4769.7     0.1       0  5019.5    0.05       0  5023.5     0.1       0
  5101.1    0.12       0  5486.0    0.07       0  5587.3   0.035       0
Bank Sta=5019.5,5023.5
Exp/Cntr=0.3,0.1

Chan Stop Cuts=-1