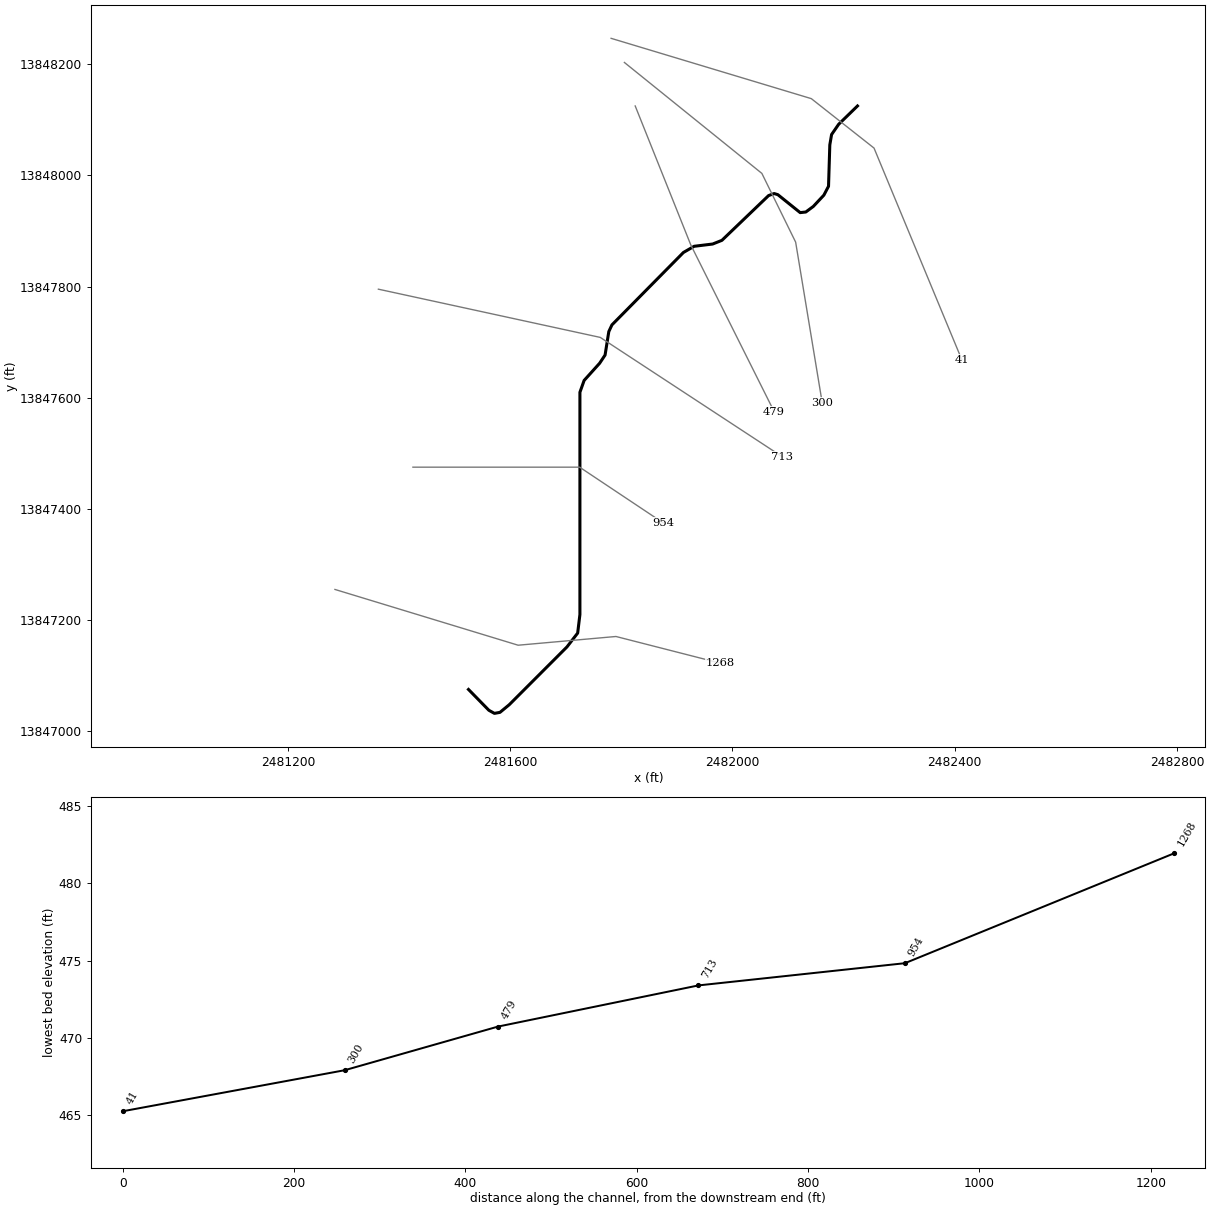
--- StreamM040.prj (project) ---

Proj Title=StreamM040 Base Level Engineering
Current Plan=p01
Default Exp/Contr=0.3,0.1
English Units
Geom File=g01
Flow File=f01
Plan File=p01
BEGIN DESCRIPTION:
StreamM040
END DESCRIPTION:

--- StreamM040.p01 (plan) ---

Plan Title=Multiple Run
Short Identifier=Multiple
Geom File=g01
Flow File=f01
Subcritical Flow
K Sum by GR= 0
Std Step Tol= 0.01
Critical Tol= 0.01
Num of Std Step Trials= 20
Max Error Tol= 0.3
Flow Tol Ratio= 0.001
Split Flow NTrial= 30
Split Flow Tol= 0.02
Split Flow Ratio= 0.02
Log Output Level= 0
Friction Slope Method= 1
Unsteady Friction Slope Method= 2
Unsteady Bridges Friction Slope Method= 1
Parabolic Critical Depth
Global Vel Dist=  1 , 1 , 1
Global Log Level= 0
CheckData=True
Encroach Param= -1, 0, 0, 0
BEGIN DESCRIPTION:
Multiple Run
END DESCRIPTION:

--- StreamM040.f01 (steady flow) ---

Flow Title=Multiple
Number of Profiles=7
Profile Names=10-year,25-year,50-year,1pct_min,100-year,1pct_plu,500-year
River Rch & RM= StreamM040,Reach-1,1268
     275     419     541     340     679    1355    1055
Boundary for River Rch & Prof#=StreamM040,Reach-1,1
Up Type=0
Dn Type=3
Dn Slope=0.005
Boundary for River Rch & Prof#=StreamM040,Reach-1,2
Up Type=0
Dn Type=3
Dn Slope=0.005
Boundary for River Rch & Prof#=StreamM040,Reach-1,3
Up Type=0
Dn Type=3
Dn Slope=0.005
Boundary for River Rch & Prof#=StreamM040,Reach-1,4
Up Type=0
Dn Type=3
Dn Slope=0.005
Boundary for River Rch & Prof#=StreamM040,Reach-1,5
Up Type=0
Dn Type=3
Dn Slope=0.005
Boundary for River Rch & Prof#=StreamM040,Reach-1,6
Up Type=0
Dn Type=3
Dn Slope=0.005
Boundary for River Rch & Prof#=StreamM040,Reach-1,7
Up Type=0
Dn Type=3
Dn Slope=0.005

--- StreamM040.g01 (geometry) ---

Geom Title=Existing Conditions

River Reach=StreamM040,Reach-1
Reach XY= 30
      2481525.00     13847075.00      2481561.67     13847037.50
      2481571.67     13847031.94      2481581.67     13847033.77
      2481598.34     13847047.54      2481702.14     13847151.47
      2481721.46     13847176.46      2481725.49     13847209.80
      2481725.51     13847609.79      2481733.09     13847631.08
      2481760.95     13847661.97      2481770.78     13847676.75
      2481777.49     13847718.97      2481783.14     13847731.06
      2481911.79     13847861.37      2481931.05     13847872.47
      2481964.36     13847876.56      2481981.05     13847883.20
      2482065.02     13847963.73      2482075.02     13847967.42
      2482081.69     13847965.37      2482121.87     13847933.07
      2482131.99     13847934.17      2482145.48     13847944.17
      2482164.49     13847964.49      2482172.89     13847980.48
      2482175.20     13848054.90      2482178.39     13848073.59
      2482191.13     13848092.04      2482225.00     13848125.00

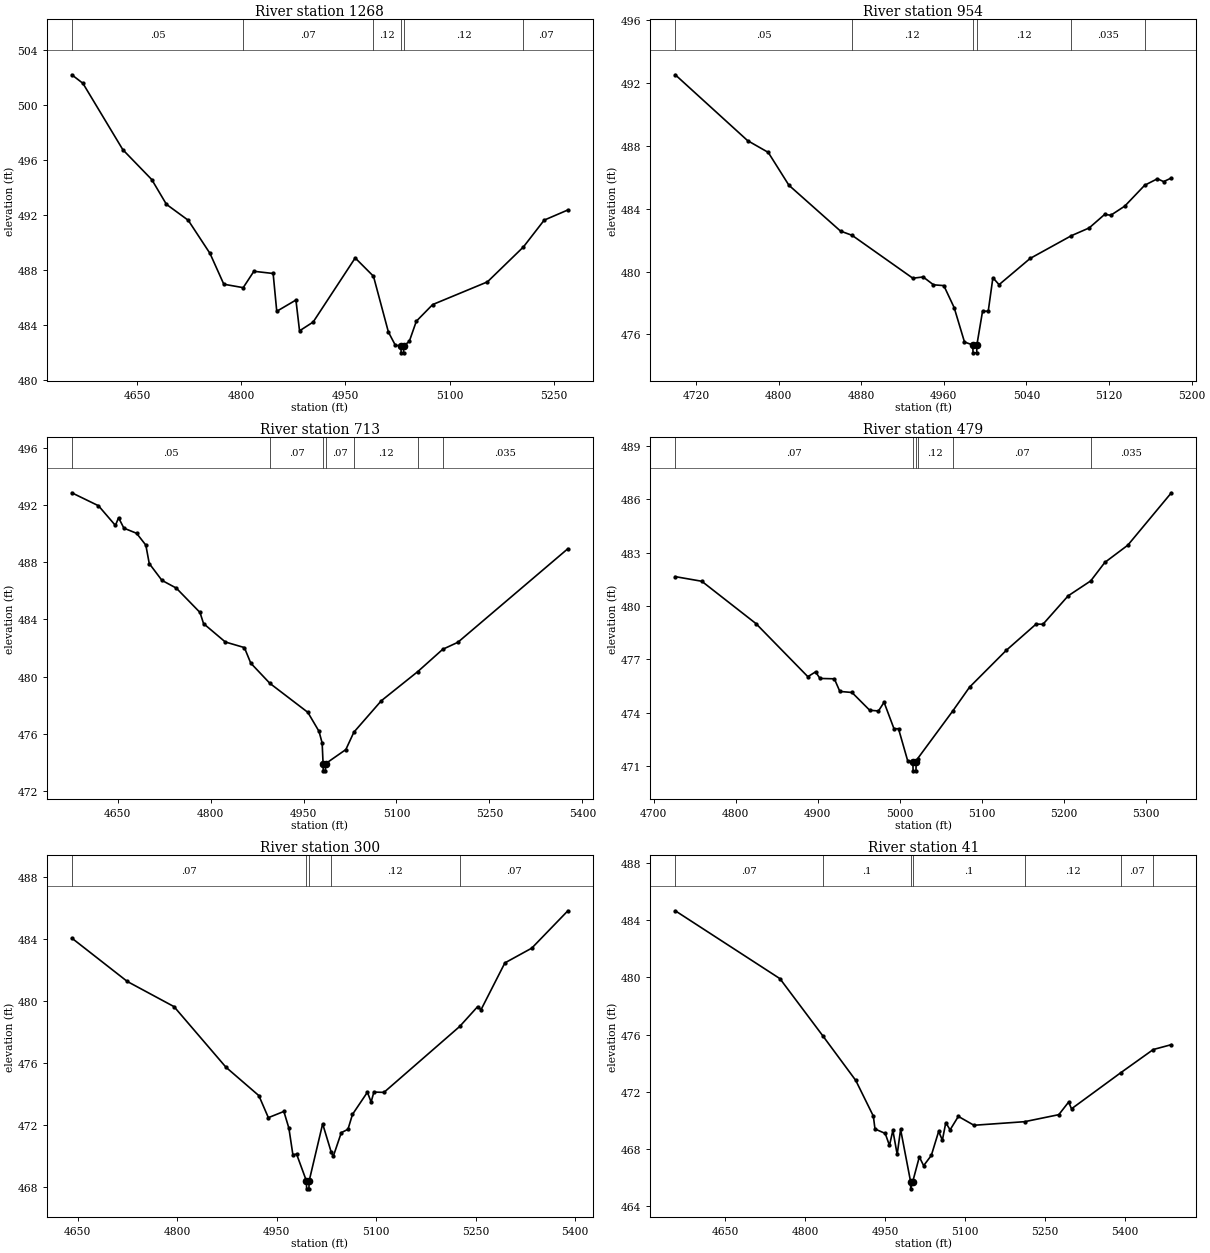
Type RM Length L Ch R = 1,1268,314,314,314
BEGIN DESCRIPTION:
H21313
END DESCRIPTION:
XS GIS Cut Line= 4
      2481284.68     13847254.95      2481614.33     13847154.60
      2481790.36     13847170.30      2481977.03     13847122.55
#Sta/Elev= 30
  4556.3  502.17  4572.3  501.55  4629.8  496.72  4671.4  494.55  4692.5  492.75
  4723.9  491.59  4755.2  489.18  4775.1  486.94  4803.0  486.69  4818.4  487.88
  4846.1  487.72  4851.3  484.97  4878.9  485.79  4884.1  483.55  4903.7  484.19
  4964.2  488.85  4990.5  487.52  5012.0  483.46  5022.0  482.50  5030.1  482.45
  5030.3  481.95  5033.8  481.95  5034.1  482.45  5042.1  482.79  5052.2  484.25
  5075.7  485.46  5154.5  487.11  5206.3  489.65  5236.2  491.60  5270.3  492.34
#Mann=6,-1,0
  4556.3    0.05       0  4803.0    0.07       0  4990.5    0.12       0
  5030.1    0.05       0  5034.1    0.12       0  5206.3    0.07       0
Bank Sta=5030.1,5034.1
Exp/Cntr=0.3,0.1

Type RM Length L Ch R = 1,954,241,241,241
BEGIN DESCRIPTION:
StreamM040 2.0
END DESCRIPTION:
XS GIS Cut Line= 3
      2481424.98     13847475.00      2481725.00     13847475.00
      2481875.00     13847375.00
#Sta/Elev= 30
  4700.0  492.53  4770.0  488.34  4790.0  487.59  4810.0  485.50  4860.0  482.58
  4871.2  482.31  4930.0  479.58  4940.0  479.66  4950.0  479.16  4960.0  479.11
  4970.0  477.71  4980.0  475.52  4988.0  475.33  4988.3  474.83  4991.8  474.83
  4992.0  475.33  4997.5  477.48  5003.0  477.48  5007.5  479.61  5013.5  479.17
  5043.6  480.84  5083.6  482.29  5100.7  482.78  5115.7  483.64  5121.7  483.59
  5135.2  484.17  5154.5  485.50  5166.8  485.91  5172.8  485.73  5180.3  485.96
#Mann=6,-1,0
  4700.0    0.05       0  4871.2    0.12       0  4988.0    0.05       0
  4992.0    0.12       0  5083.6   0.035       0  5154.5    0.07       0
Bank Sta=4988,4992
Exp/Cntr=0.3,0.1

Type RM Length L Ch R = 1,713,234,234,234
BEGIN DESCRIPTION:
H21312
END DESCRIPTION:
XS GIS Cut Line= 3
      2481362.84     13847795.30      2481762.15     13847708.50
      2482089.86     13847493.64
#Sta/Elev= 30
  4576.1  492.88  4619.2  491.97  4646.5  490.59  4651.6  491.13  4660.2  490.40
  4680.7  490.04  4695.6  489.21  4701.1  487.92  4721.6  486.74  4744.7  486.20
  4783.0  484.49  4788.7  483.71  4823.9  482.42  4854.6  482.03  4864.9  480.94
  4895.8  479.52  4957.0  477.49  4975.0  476.16  4980.1  475.34  4981.6  473.89
  4981.9  473.39  4985.4  473.39  4985.6  473.89  5018.3  474.88  5031.3  476.10
  5075.5  478.30  5134.5  480.35  5174.7  481.91  5199.1  482.40  5376.6  488.96
#Mann=7,-1,0
  4576.1    0.05       0  4895.8    0.07       0  4981.6    0.05       0
  4985.6    0.07       0  5031.3    0.12       0  5134.5    0.07       0
  5174.7   0.035       0
Bank Sta=4981.6,4985.6
Exp/Cntr=0.3,0.1

Type RM Length L Ch R = 1,479,179,179,179
BEGIN DESCRIPTION:
StreamM040 1.0
END DESCRIPTION:
XS GIS Cut Line= 3
      2481825.00     13848125.01      2481925.00     13847875.00
      2482075.01     13847574.98
#Sta/Elev= 30
  4726.4  481.65  4758.7  481.39  4824.7  479.01  4888.0  476.02  4897.4  476.29
  4902.8  475.92  4920.3  475.90  4927.0  475.19  4941.8  475.13  4963.4  474.13
  4974.1  474.09  4980.9  474.58  4993.0  473.09  4998.5  473.09  5009.6  471.30
  5016.0  471.22  5016.3  470.72  5019.8  470.72  5020.0  471.22  5021.7  471.40
  5064.5  474.08  5085.1  475.43  5129.8  477.50  5166.2  478.98  5174.6  478.97
  5205.3  480.57  5232.8  481.41  5250.0  482.45  5278.0  483.42  5331.1  486.37
#Mann=6,-1,0
  4726.4    0.07       0  5016.0    0.05       0  5020.0    0.07       0
  5021.7    0.12       0  5064.5    0.07       0  5232.8   0.035       0
Bank Sta=5016,5020
Exp/Cntr=0.3,0.1

Type RM Length L Ch R = 1,300,259,259,259
BEGIN DESCRIPTION:
H21311
END DESCRIPTION:
XS GIS Cut Line= 4
      2481805.56     13848203.28      2482052.95     13848003.63
      2482113.72     13847879.94      2482161.46     13847591.27
#Sta/Elev= 30
  4641.0  484.06  4724.8  481.26  4795.2  479.64  4873.6  475.73  4923.2  473.90
  4937.5  472.48  4960.9  472.88  4968.5  471.80  4974.5  470.09  4980.1  470.13
  4995.0  468.39  4995.2  467.89  4998.7  467.89  4999.0  468.39  5019.4  472.08
  5032.1  470.29  5035.4  469.98  5047.5  471.51  5057.6  471.73  5064.4  472.69
  5086.9  474.12  5092.5  473.49  5096.7  474.13  5111.9  474.11  5226.1  478.36
  5253.2  479.64  5258.3  479.44  5294.3  482.46  5334.8  483.41  5389.3  485.82
#Mann=5,-1,0
  4641.0    0.07       0  4995.0    0.05       0  4999.0    0.07       0
  5032.1    0.12       0  5226.1    0.07       0
Bank Sta=4995,4999
Exp/Cntr=0.3,0.1

Type RM Length L Ch R = 1,41,0,0,0
BEGIN DESCRIPTION:
H21310
END DESCRIPTION:
XS GIS Cut Line= 4
      2481781.66     13848246.70      2482141.93     13848138.18
      2482254.77     13848049.21      2482412.64     13847668.60
#Sta/Elev= 30
  4556.0  484.65  4752.6  479.91  4833.7  475.89  4895.1  472.80  4928.1  470.31
  4931.2  469.41  4950.4  469.10  4958.4  468.26  4964.8  469.31  4972.9  467.63
  4979.3  469.38  4998.1  465.73  4998.3  465.23  5002.1  465.73  5014.5  467.46
  5022.6  466.85  5037.0  467.56  5050.8  469.24  5057.8  468.63  5064.2  469.85
  5072.3  469.35  5087.8  470.29  5117.1  469.67  5212.3  469.92  5276.5  470.41
  5295.0  471.29  5300.4  470.82  5393.3  473.35  5454.0  474.96  5488.0  475.30
#Mann=7,-1,0
  4556.0    0.07       0  4833.7     0.1       0  4998.1    0.05       0
  5002.1     0.1       0  5212.3    0.12       0  5393.3    0.07       0
  5454.0    0.12       0
Bank Sta=4998.1,5002.1
Exp/Cntr=0.3,0.1

Chan Stop Cuts=-1