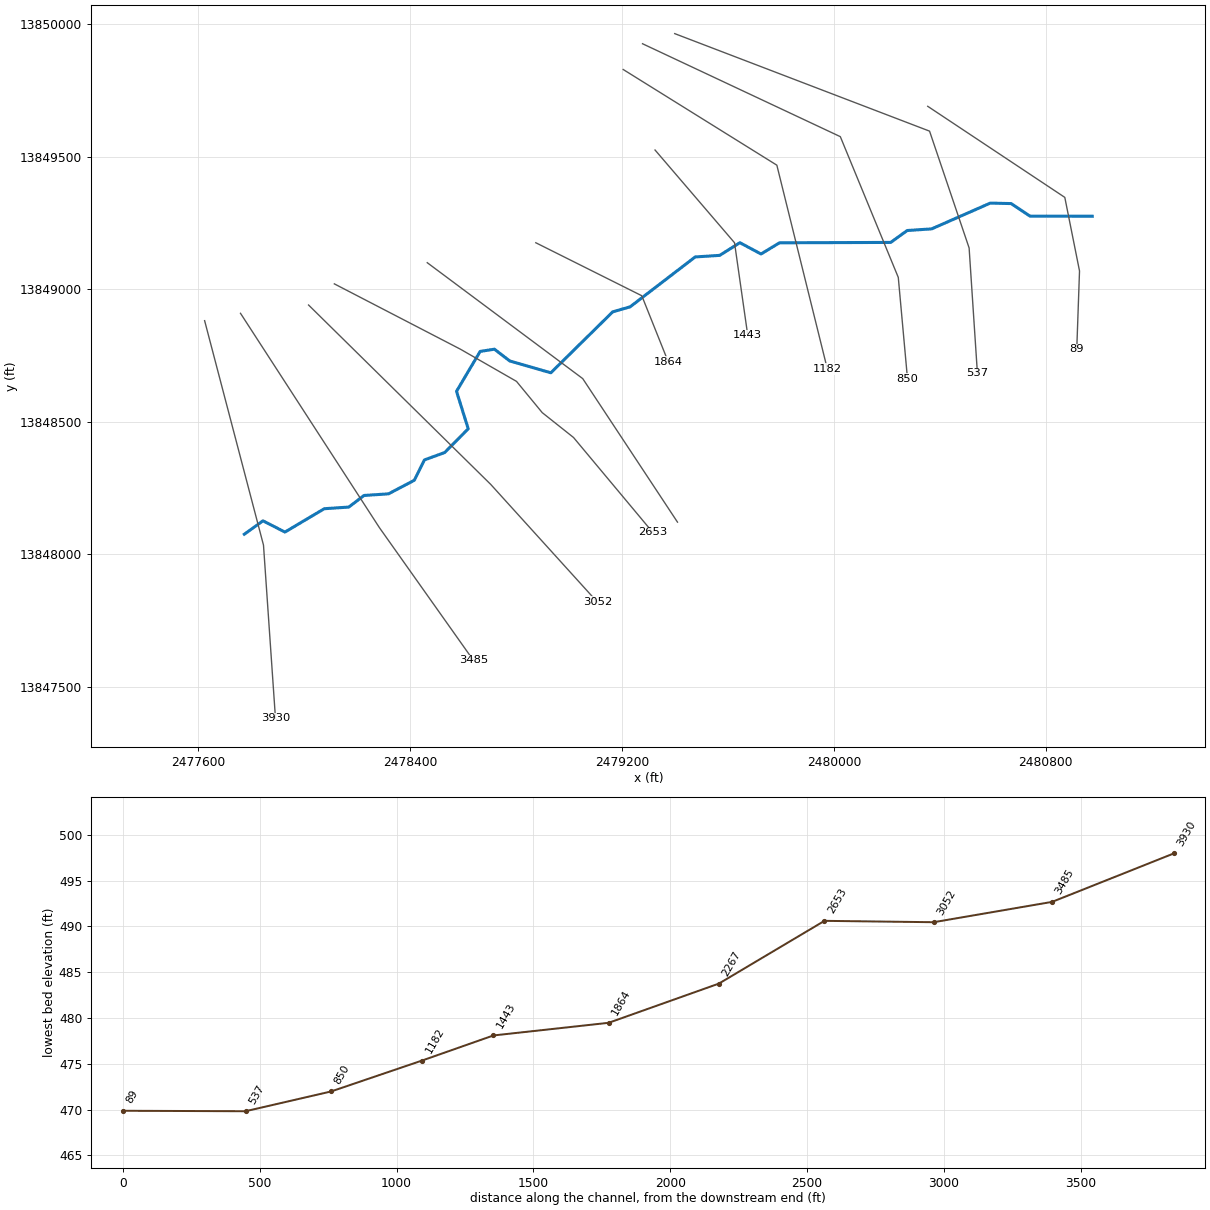
--- StreamM041.prj (project) ---

Proj Title=StreamM041 Base Level Engineering
Current Plan=p01
Default Exp/Contr=0.3,0.1
English Units
Geom File=g01
Flow File=f01
Plan File=p01
BEGIN DESCRIPTION:
StreamM041
END DESCRIPTION:

--- StreamM041.p01 (plan) ---

Plan Title=Multiple Run
Short Identifier=Multiple
Geom File=g01
Flow File=f01
Subcritical Flow
K Sum by GR= 0
Std Step Tol= 0.01
Critical Tol= 0.01
Num of Std Step Trials= 20
Max Error Tol= 0.3
Flow Tol Ratio= 0.001
Split Flow NTrial= 30
Split Flow Tol= 0.02
Split Flow Ratio= 0.02
Log Output Level= 0
Friction Slope Method= 1
Unsteady Friction Slope Method= 2
Unsteady Bridges Friction Slope Method= 1
Parabolic Critical Depth
Global Vel Dist=  1 , 1 , 1
Global Log Level= 0
CheckData=True
Encroach Param= -1, 0, 0, 0
BEGIN DESCRIPTION:
Multiple Run
END DESCRIPTION:

--- StreamM041.f01 (steady flow) ---

Flow Title=Multiple
Number of Profiles=7
Profile Names=10-year,25-year,50-year,1pct_min,100-year,1pct_plu,500-year
River Rch & RM= StreamM041,Reach-1,3930
     491     780    1039     672    1341    2675    2206
Boundary for River Rch & Prof#=StreamM041,Reach-1,1
Up Type=0
Dn Type=3
Dn Slope=0.005
Boundary for River Rch & Prof#=StreamM041,Reach-1,2
Up Type=0
Dn Type=3
Dn Slope=0.005
Boundary for River Rch & Prof#=StreamM041,Reach-1,3
Up Type=0
Dn Type=3
Dn Slope=0.005
Boundary for River Rch & Prof#=StreamM041,Reach-1,4
Up Type=0
Dn Type=3
Dn Slope=0.005
Boundary for River Rch & Prof#=StreamM041,Reach-1,5
Up Type=0
Dn Type=3
Dn Slope=0.005
Boundary for River Rch & Prof#=StreamM041,Reach-1,6
Up Type=0
Dn Type=3
Dn Slope=0.005
Boundary for River Rch & Prof#=StreamM041,Reach-1,7
Up Type=0
Dn Type=3
Dn Slope=0.005

--- StreamM041.g01 (geometry) ---

Geom Title=Existing Conditions

River Reach=StreamM041,Reach-1
Reach XY= 30
      2477775.00     13848075.00      2477845.25     13848125.46
      2477928.30     13848083.05      2478076.58     13848171.17
      2478169.03     13848177.35      2478226.60     13848221.15
      2478319.06     13848227.32      2478416.51     13848278.53
      2478454.57     13848355.27      2478531.05     13848383.16
      2478619.91     13848472.69      2478575.75     13848614.32
      2478665.00     13848764.94      2478718.83     13848773.23
      2478776.58     13848728.89      2478931.74     13848684.13
      2479165.32     13848914.22      2479231.04     13848933.18
      2479476.50     13849121.38      2479569.03     13849127.38
      2479645.21     13849175.21      2479724.99     13849132.59
      2479794.98     13849174.82      2480214.50     13849176.22
      2480276.60     13849221.14      2480369.03     13849227.35
      2480590.27     13849324.62      2480669.02     13849322.83
      2480740.22     13849275.52      2480975.00     13849275.00

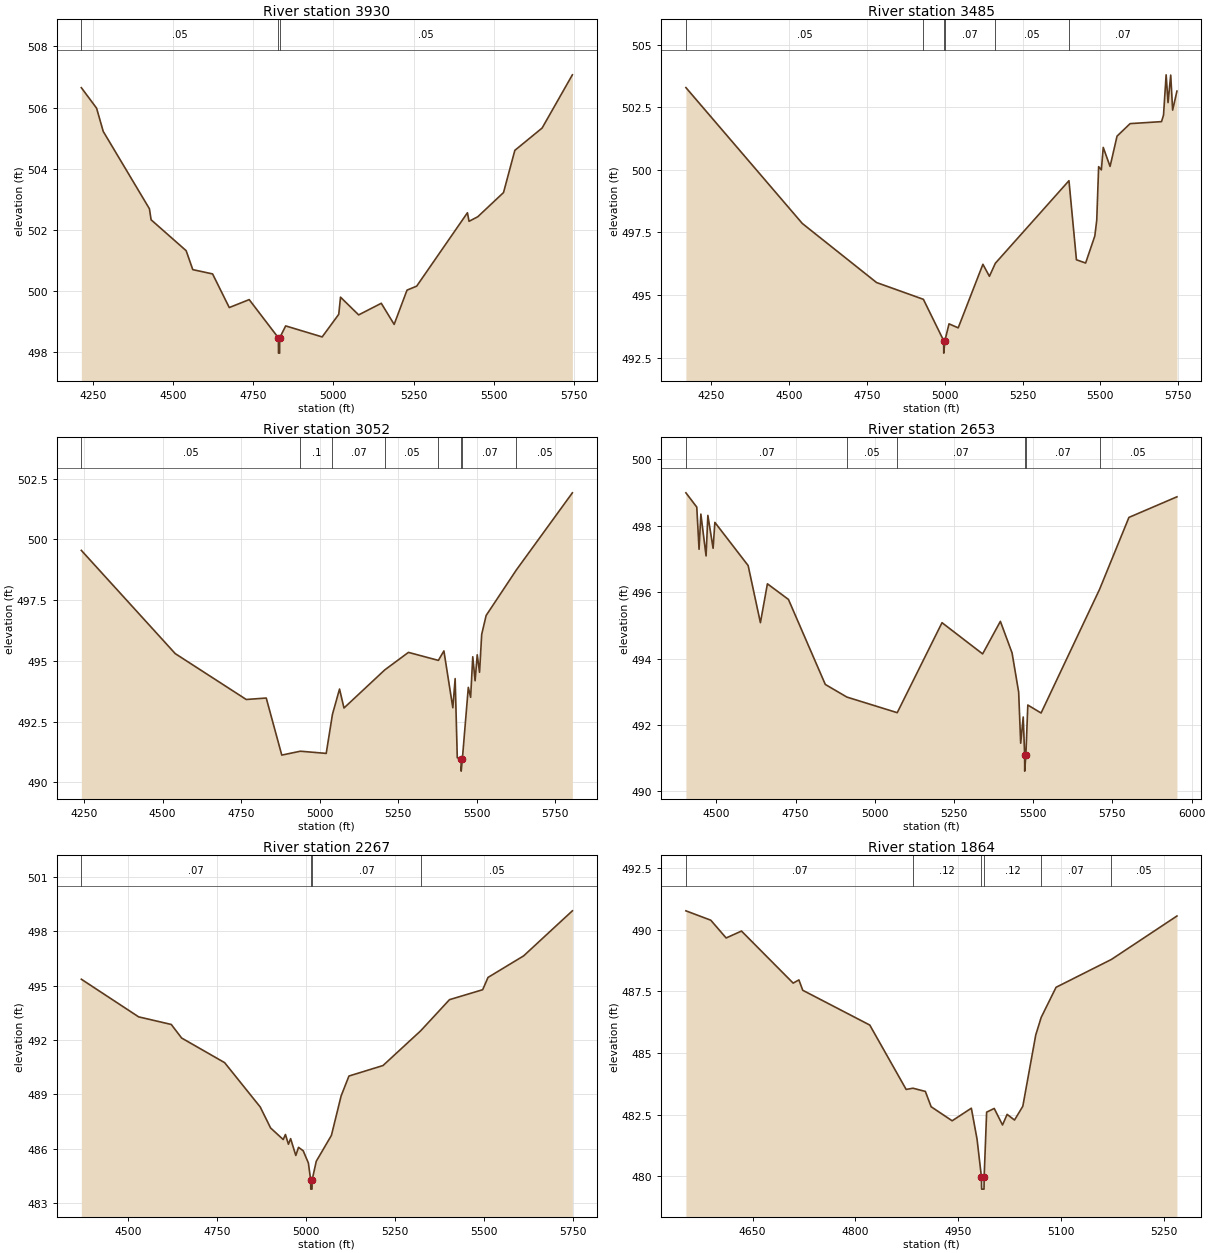
Type RM Length L Ch R = 1,3930,445,445,445
BEGIN DESCRIPTION:
H21322
END DESCRIPTION:
XS GIS Cut Line= 3
      2477625.01     13848880.94      2477847.22     13848033.74
      2477892.36     13847380.96
#Sta/Elev= 30
  4214.5  506.65  4262.0  505.98  4282.7  505.22  4426.7  502.69  4431.9  502.33
  4541.1  501.32  4561.8  500.70  4623.5  500.56  4675.5  499.46  4737.6  499.72
  4828.6  498.47  4828.9  497.97  4832.4  497.97  4832.6  498.47  4851.3  498.86
  4965.0  498.50  5016.7  499.24  5022.2  499.80  5078.7  499.22  5149.2  499.60
  5189.3  498.91  5229.4  500.03  5259.5  500.16  5417.7  502.56  5422.7  502.28
  5450.0  502.43  5530.1  503.22  5565.4  504.60  5650.4  505.33  5744.7  507.07
#Mann=3,-1,0
  4214.5    0.05       0  4828.6    0.05       0  4832.6    0.05       0
Bank Sta=4828.6,4832.6
Exp/Cntr=0.3,0.1

Type RM Length L Ch R = 1,3485,433,433,433
BEGIN DESCRIPTION:
H21321
END DESCRIPTION:
XS GIS Cut Line= 3
      2477760.44     13848908.71      2478284.72     13848099.71
      2478638.80     13847599.84
#Sta/Elev= 30
  4169.2  503.29  4543.0  497.86  4781.4  495.50  4931.7  494.83  4996.8  493.18
  4997.1  492.68  5000.8  493.18  5014.0  493.85  5043.5  493.69  5122.8  496.23
  5143.7  495.75  5162.7  496.27  5399.1  499.57  5423.1  496.41  5452.6  496.28
  5482.1  497.36  5488.3  497.99  5494.4  500.13  5503.1  500.00  5509.2  500.90
  5531.1  500.14  5553.5  501.35  5595.4  501.85  5696.3  501.93  5702.7  502.19
  5711.1  503.80  5717.2  502.69  5725.8  503.79  5732.0  502.39  5745.8  503.15
#Mann=6,-1,0
  4169.2    0.05       0  4931.7    0.07       0  4996.8    0.05       0
  5000.8    0.07       0  5162.7    0.05       0  5399.1    0.07       0
Bank Sta=4996.8,5000.8
Exp/Cntr=0.3,0.1

Type RM Length L Ch R = 1,3052,399,399,399
BEGIN DESCRIPTION:
H21320
END DESCRIPTION:
XS GIS Cut Line= 3
      2478017.33     13848940.02      2478704.86     13848262.91
      2479106.91     13847819.26
#Sta/Elev= 30
  4241.0  499.55  4539.9  495.30  4766.2  493.41  4829.8  493.47  4879.3  491.12
  4938.5  491.28  5020.8  491.19  5040.7  492.80  5063.2  493.84  5077.4  493.06
  5207.4  494.63  5282.7  495.35  5378.0  495.02  5395.6  495.41  5424.0  493.07
  5431.4  494.27  5438.2  491.01  5450.4  490.96  5450.6  490.46  5454.4  490.96
  5473.3  493.91  5480.7  493.50  5487.5  495.17  5494.9  494.18  5501.7  495.25
  5509.1  494.53  5515.9  496.09  5530.1  496.87  5626.1  498.74  5804.7  501.92
#Mann=8,-1,0
  4241.0    0.05       0  4938.5     0.1       0  5040.7    0.07       0
  5207.4    0.05       0  5378.0    0.07       0  5450.4    0.05       0
  5454.4    0.07       0  5626.1    0.05       0
Bank Sta=5450.4,5454.4
Exp/Cntr=0.3,0.1

Type RM Length L Ch R = 1,2653,386,386,386
BEGIN DESCRIPTION:
H21319
END DESCRIPTION:
XS GIS Cut Line= 6
      2478114.58     13849019.85      2478590.28     13848773.33
      2478802.08     13848651.80      2478899.31     13848533.74
      2479017.36     13848439.99      2479315.99     13848082.33
#Sta/Elev= 30
  4404.0  498.99  4438.3  498.56  4445.5  497.29  4451.2  498.35  4467.6  497.09
  4473.3  498.31  4489.8  497.32  4495.4  498.10  4600.4  496.80  4639.1  495.08
  4661.2  496.25  4727.6  495.78  4843.9  493.22  4911.9  492.84  5070.9  492.37
  5212.2  495.08  5340.4  494.14  5396.4  495.12  5433.3  494.17  5454.1  492.99
  5460.5  491.45  5468.5  492.24  5472.9  491.11  5473.2  490.61  5476.9  491.11
  5483.0  492.60  5524.9  492.36  5709.7  496.09  5802.1  498.25  5953.6  498.87
#Mann=6,-1,0
  4404.0    0.07       0  4911.9    0.05       0  5070.9    0.07       0
  5472.9    0.05       0  5476.9    0.07       0  5709.7    0.05       0
Bank Sta=5472.9,5476.9
Exp/Cntr=0.3,0.1

Type RM Length L Ch R = 1,2267,403,403,403
BEGIN DESCRIPTION:
H21318
END DESCRIPTION:
XS GIS Cut Line= 3
      2478465.28     13849099.71      2479052.08     13848662.21
      2479409.71     13848120.57
#Sta/Elev= 30
  4367.6  495.36  4528.8  493.28  4620.5  492.86  4649.7  492.11  4770.6  490.75
  4870.7  488.30  4899.9  487.14  4935.4  486.50  4941.6  486.78  4950.0  486.24
  4956.2  486.55  4970.8  485.62  4978.4  486.07  4991.6  485.88  5006.2  485.20
  5012.6  484.26  5012.9  483.76  5016.4  483.76  5016.6  484.26  5028.3  485.30
  5070.9  486.73  5098.2  488.91  5120.2  490.01  5216.0  490.59  5322.0  492.51
  5403.0  494.23  5496.3  494.78  5511.4  495.46  5611.5  496.65  5748.6  499.14
#Mann=4,-1,0
  4367.6    0.07       0  5012.6    0.05       0  5016.6    0.07       0
  5322.0    0.05       0
Bank Sta=5012.6,5016.6
Exp/Cntr=0.3,0.1

Type RM Length L Ch R = 1,1864,421,421,421
BEGIN DESCRIPTION:
StreamM041 4.0
END DESCRIPTION:
XS GIS Cut Line= 3
      2478875.00     13849175.00      2479275.00     13848975.00
      2479375.01     13848724.97
#Sta/Elev= 30
  4552.8  490.76  4589.1  490.38  4611.5  489.66  4633.9  489.94  4709.3  487.83
  4717.7  487.96  4723.3  487.54  4821.1  486.13  4874.2  483.52  4884.1  483.57
  4902.2  483.44  4910.6  482.82  4941.3  482.25  4969.3  482.76  4977.6  481.51
  4984.0  479.98  4984.3  479.48  4987.8  479.48  4988.0  479.98  4991.6  482.60
  5002.7  482.75  5014.8  482.08  5021.5  482.51  5032.3  482.28  5044.4  482.84
  5063.3  485.73  5071.2  486.44  5092.9  487.66  5173.7  488.79  5269.3  490.55
#Mann=6,-1,0
  4552.8    0.07       0  4884.1    0.12       0  4984.0    0.05       0
  4988.0    0.12       0  5071.2    0.07       0  5173.7    0.05       0
Bank Sta=4984,4988
Exp/Cntr=0.3,0.1

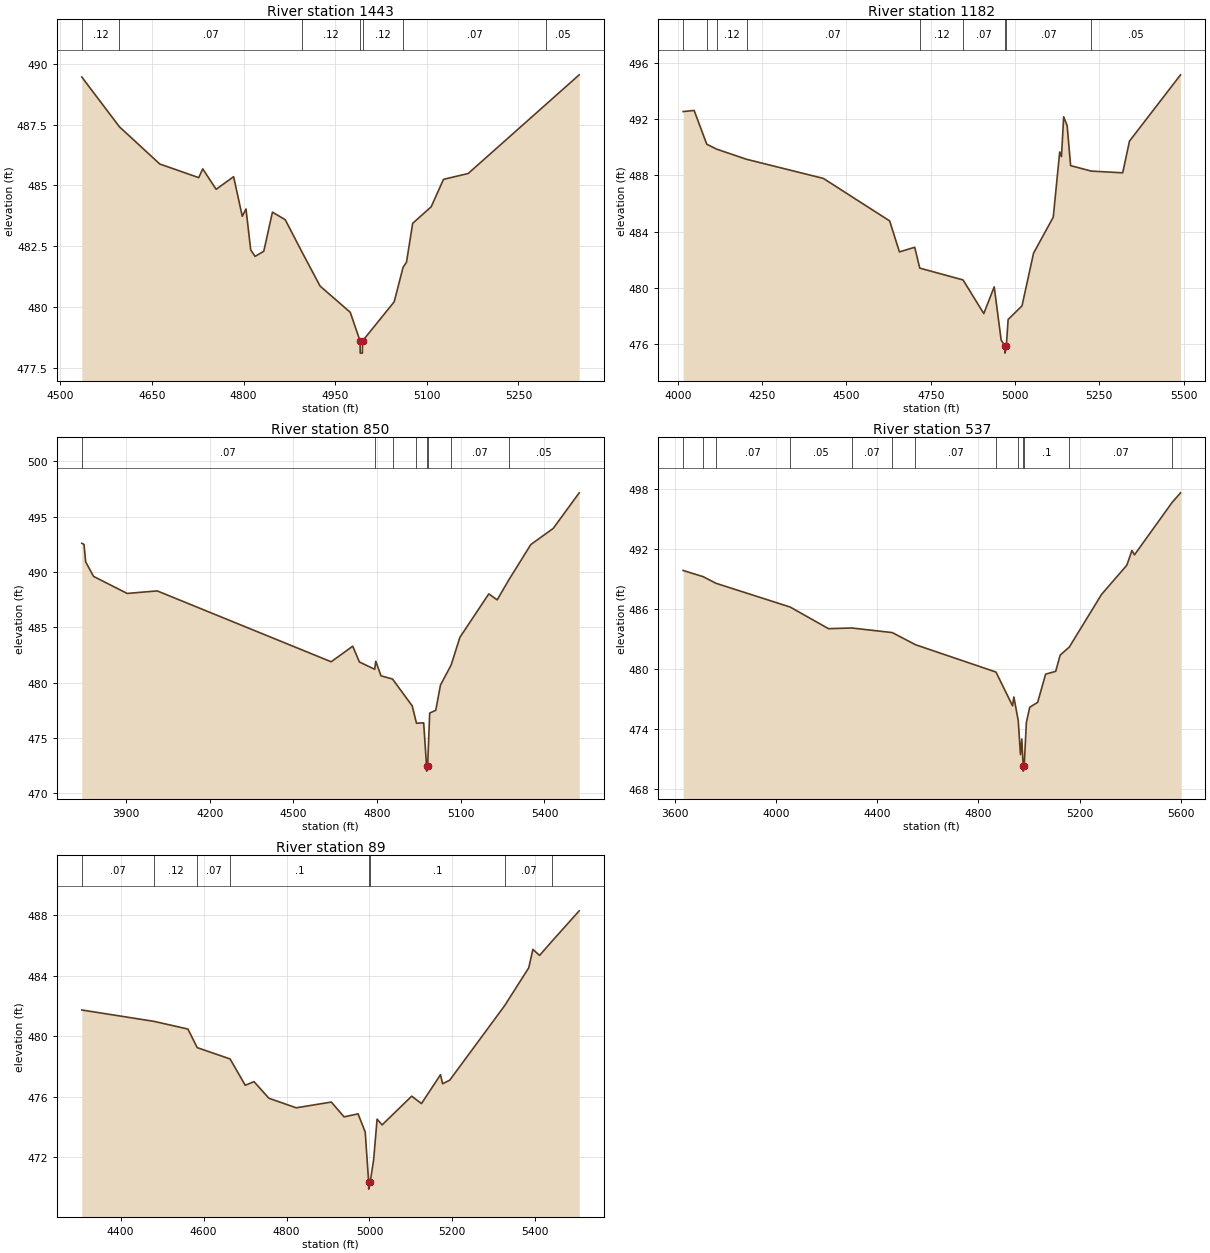
Type RM Length L Ch R = 1,1443,261,261,261
BEGIN DESCRIPTION:
StreamM041 3.0
END DESCRIPTION:
XS GIS Cut Line= 3
      2479325.01     13849524.99      2479625.00     13849175.00
      2479675.00     13848825.01
#Sta/Elev= 30
  4535.0  489.46  4596.7  487.41  4662.8  485.88  4726.5  485.32  4733.1  485.68
  4755.0  484.84  4783.6  485.36  4797.8  483.73  4803.9  484.03  4811.6  482.35
  4818.7  482.08  4833.0  482.29  4847.2  483.90  4868.1  483.59  4896.0  482.24
  4925.2  480.86  4974.6  479.78  4990.7  478.60  4990.9  478.10  4994.4  478.10
  4994.7  478.60  5046.5  480.21  5061.1  481.63  5066.7  481.84  5076.8  483.44
  5107.1  484.12  5127.3  485.25  5167.7  485.49  5295.8  488.35  5349.5  489.55
#Mann=7,-1,0
  4535.0    0.12       0  4596.7    0.07       0  4896.0    0.12       0
  4990.7    0.05       0  4994.7    0.12       0  5061.1    0.07       0
  5295.8    0.05       0
Bank Sta=4990.7,4994.7
Exp/Cntr=0.3,0.1

Type RM Length L Ch R = 1,1182,332,332,332
BEGIN DESCRIPTION:
H21317
END DESCRIPTION:
XS GIS Cut Line= 3
      2479204.84     13849828.89      2479784.72     13849467.77
      2479975.32     13848698.46
#Sta/Elev= 30
  4015.4  492.52  4048.1  492.60  4085.5  490.20  4115.0  489.85  4203.6  489.13
  4431.6  487.77  4628.2  484.75  4657.1  482.55  4702.5  482.88  4717.4  481.40
  4845.8  480.56  4907.4  478.17  4938.3  480.07  4958.9  476.29  4970.2  475.86
  4970.4  475.36  4974.2  475.86  4979.6  477.75  5020.8  478.72  5055.0  482.46
  5113.5  485.02  5132.6  489.65  5137.8  489.32  5144.4  492.15  5154.7  491.52
  5165.0  488.68  5226.4  488.29  5319.5  488.17  5339.6  490.42  5491.1  495.13
#Mann=9,-1,0
  4015.4    0.07       0  4085.5   0.035       0  4115.0    0.12       0
  4203.6    0.07       0  4717.4    0.12       0  4845.8    0.07       0
  4970.2    0.05       0  4974.2    0.07       0  5226.4    0.05       0
Bank Sta=4970.2,4974.2
Exp/Cntr=0.3,0.1

Type RM Length L Ch R = 1,850,313,313,313
BEGIN DESCRIPTION:
H21316
END DESCRIPTION:
XS GIS Cut Line= 4
      2479277.75     13849926.12      2480024.31     13849575.41
      2480243.06     13849044.16      2480277.78     13848662.19
#Sta/Elev= 30
  3741.7  492.60  3749.7  492.49  3755.7  490.91  3784.0  489.60  3904.4  488.06
  4012.1  488.29  4635.6  481.88  4712.9  483.29  4736.8  481.86  4791.6  481.20
  4795.5  481.93  4814.1  480.61  4855.4  480.32  4926.1  477.89  4941.4  476.32
  4967.1  476.36  4977.4  472.49  4977.6  471.99  4981.4  472.49  4988.7  477.24
  5010.4  477.49  5027.3  479.77  5065.8  481.60  5096.9  484.09  5200.5  488.02
  5230.6  487.48  5272.4  489.29  5351.1  492.48  5431.4  493.94  5524.6  497.16
#Mann=8,-1,0
  3741.7    0.07       0  4791.6    0.12       0  4855.4    0.07       0
  4941.4    0.12       0  4977.4    0.05       0  4981.4    0.12       0
  5065.8    0.07       0  5272.4    0.05       0
Bank Sta=4977.4,4981.4
Exp/Cntr=0.3,0.1

Type RM Length L Ch R = 1,537,448,448,448
BEGIN DESCRIPTION:
H21315
END DESCRIPTION:
XS GIS Cut Line= 4
      2479399.33     13849964.29      2480361.11     13849596.24
      2480510.42     13849155.27      2480541.67     13848683.06
#Sta/Elev= 30
  3631.1  489.86  3710.4  489.24  3761.2  488.58  4054.6  486.21  4206.4  484.05
  4297.9  484.12  4458.9  483.66  4550.5  482.45  4869.3  479.72  4934.8  476.35
  4940.0  477.23  4957.4  474.88  4966.2  471.48  4971.5  473.04  4976.9  470.33
  4977.2  469.83  4980.9  470.33  4989.5  474.68  5002.9  476.21  5034.3  476.70
  5065.7  479.51  5105.6  479.79  5123.3  481.41  5159.6  482.22  5287.1  487.47
  5387.3  490.39  5407.3  491.85  5417.4  491.42  5565.7  496.63  5599.7  497.61
#Mann=13,-1,0
  3631.1    0.07       0  3710.4    0.05       0  3761.2    0.07       0
  4054.6    0.05       0  4297.9    0.07       0  4458.9    0.05       0
  4550.5    0.07       0  4869.3    0.12       0  4957.4     0.1       0
  4976.9    0.05       0  4980.9     0.1       0  5159.6    0.07       0
  5565.7    0.05       0
Bank Sta=4976.9,4980.9
Exp/Cntr=0.3,0.1

Type RM Length L Ch R = 1,89,0,0,0
BEGIN DESCRIPTION:
H21314
END DESCRIPTION:
XS GIS Cut Line= 4
      2480354.20     13849689.97      2480871.53     13849346.24
      2480927.08     13849068.46      2480916.67     13848773.34
#Sta/Elev= 30
  4306.2  481.73  4479.9  480.98  4562.2  480.47  4584.6  479.24  4663.9  478.49
  4700.5  476.75  4721.6  476.99  4757.6  475.89  4823.4  475.26  4908.0  475.64
  4938.8  474.66  4972.5  474.86  4989.8  473.66  4998.0  470.38  4998.2  469.88
  5002.0  470.38  5010.2  471.85  5018.4  474.51  5030.6  474.13  5101.9  476.03
  5125.5  475.54  5171.4  477.45  5176.5  476.85  5193.7  477.09  5325.9  482.01
  5384.2  484.52  5394.2  485.74  5410.3  485.34  5440.6  486.29  5505.9  488.29
#Mann=8,-1,0
  4306.2    0.07       0  4479.9    0.12       0  4584.6    0.07       0
  4663.9     0.1       0  4998.0    0.05       0  5002.0     0.1       0
  5325.9    0.07       0  5440.6    0.05       0
Bank Sta=4998,5002
Exp/Cntr=0.3,0.1

Chan Stop Cuts=-1