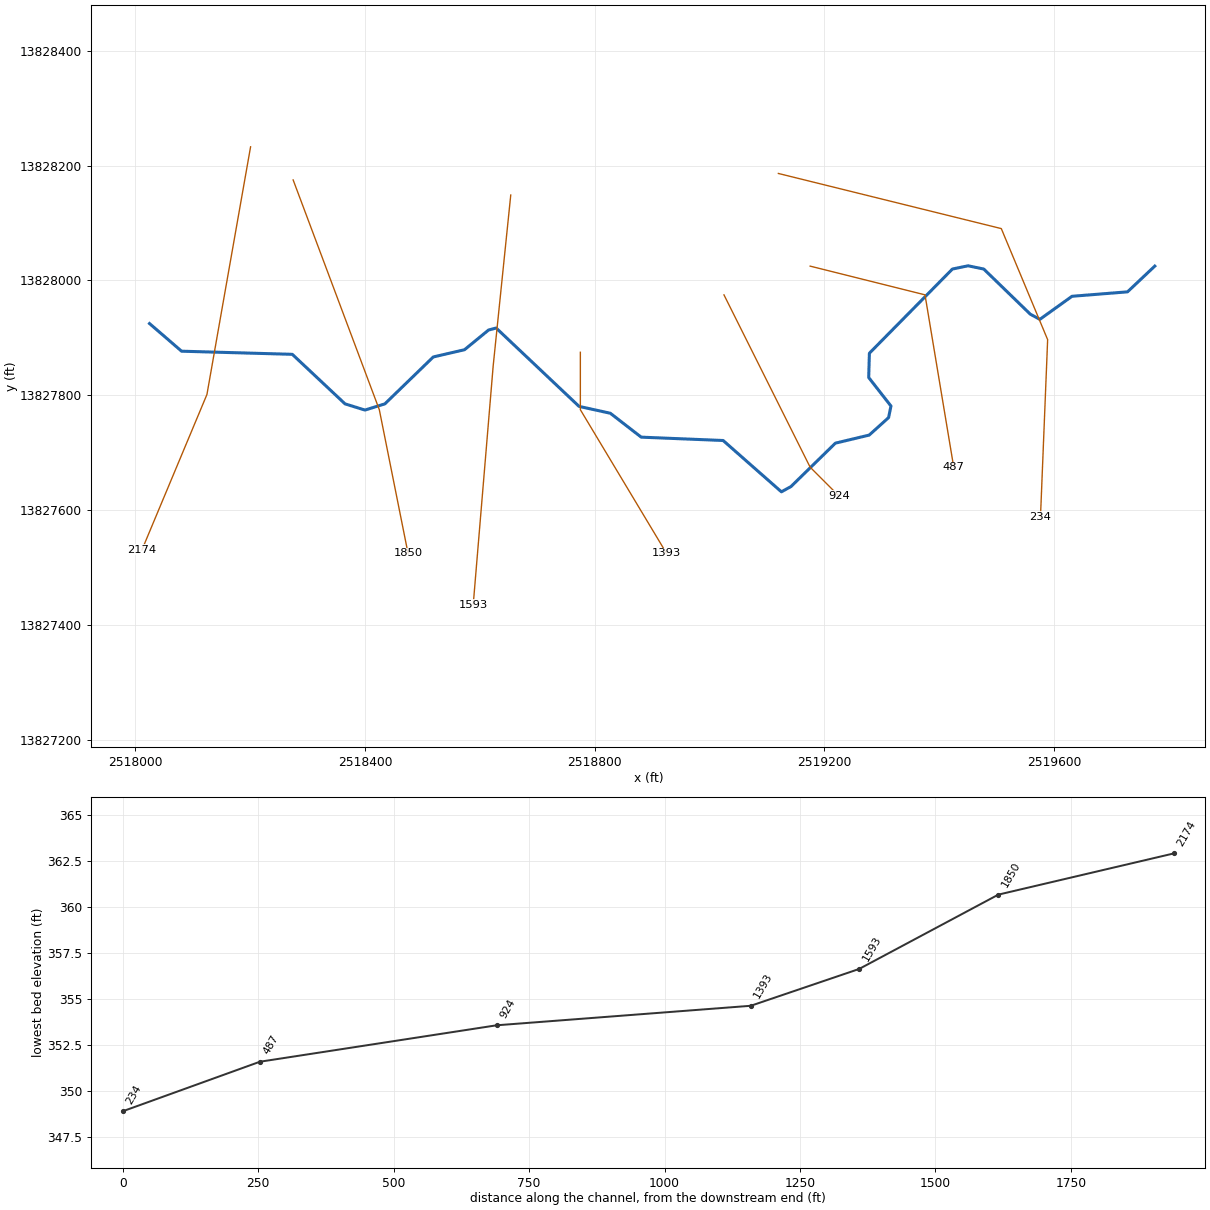
--- StreamM043a.prj (project) ---

Proj Title=StreamM043a Base Level Engineering
Current Plan=p01
Default Exp/Contr=0.3,0.1
English Units
Geom File=g01
Flow File=f01
Plan File=p01
BEGIN DESCRIPTION:
StreamM043a
END DESCRIPTION:

--- StreamM043a.p01 (plan) ---

Plan Title=Multiple Run
Short Identifier=Multiple
Geom File=g01
Flow File=f01
Subcritical Flow
K Sum by GR= 0
Std Step Tol= 0.01
Critical Tol= 0.01
Num of Std Step Trials= 20
Max Error Tol= 0.3
Flow Tol Ratio= 0.001
Split Flow NTrial= 30
Split Flow Tol= 0.02
Split Flow Ratio= 0.02
Log Output Level= 0
Friction Slope Method= 1
Unsteady Friction Slope Method= 2
Unsteady Bridges Friction Slope Method= 1
Parabolic Critical Depth
Global Vel Dist=  1 , 1 , 1
Global Log Level= 0
CheckData=True
Encroach Param= -1, 0, 0, 0
BEGIN DESCRIPTION:
Multiple Run
END DESCRIPTION:

--- StreamM043a.f01 (steady flow) ---

Flow Title=Multiple
Number of Profiles=7
Profile Names=10-year,25-year,50-year,1pct_min,100-year,1pct_plu,500-year
River Rch & RM= StreamM043a,Reach-1,2174
     562     900    1203     781    1558    3109    2584
Boundary for River Rch & Prof#=StreamM043a,Reach-1,1
Up Type=0
Dn Type=3
Dn Slope=0.005
Boundary for River Rch & Prof#=StreamM043a,Reach-1,2
Up Type=0
Dn Type=3
Dn Slope=0.005
Boundary for River Rch & Prof#=StreamM043a,Reach-1,3
Up Type=0
Dn Type=3
Dn Slope=0.005
Boundary for River Rch & Prof#=StreamM043a,Reach-1,4
Up Type=0
Dn Type=3
Dn Slope=0.005
Boundary for River Rch & Prof#=StreamM043a,Reach-1,5
Up Type=0
Dn Type=3
Dn Slope=0.005
Boundary for River Rch & Prof#=StreamM043a,Reach-1,6
Up Type=0
Dn Type=3
Dn Slope=0.005
Boundary for River Rch & Prof#=StreamM043a,Reach-1,7
Up Type=0
Dn Type=3
Dn Slope=0.005

--- StreamM043a.g01 (geometry) ---

Geom Title=Existing Conditions

River Reach=StreamM043a,Reach-1
Reach XY= 30
      2518025.00     13827925.00      2518080.78     13827876.89
      2518273.53     13827871.45      2518365.33     13827785.20
      2518400.00     13827774.42      2518434.67     13827785.19
      2518518.96     13827866.86      2518573.35     13827879.47
      2518615.13     13827913.73      2518628.41     13827917.23
      2518772.70     13827780.83      2518827.17     13827768.86
      2518880.93     13827727.25      2519023.53     13827721.43
      2519125.00     13827632.09      2519141.65     13827641.23
      2519218.99     13827716.80      2519277.85     13827730.85
      2519311.60     13827761.27      2519315.73     13827781.40
      2519276.99     13827831.04      2519278.16     13827873.35
      2519422.71     13828019.93      2519450.00     13828025.58
      2519477.29     13828019.91      2519558.31     13827941.33
      2519574.90     13827932.32      2519630.88     13827972.47
      2519727.55     13827980.22      2519775.00     13828025.00

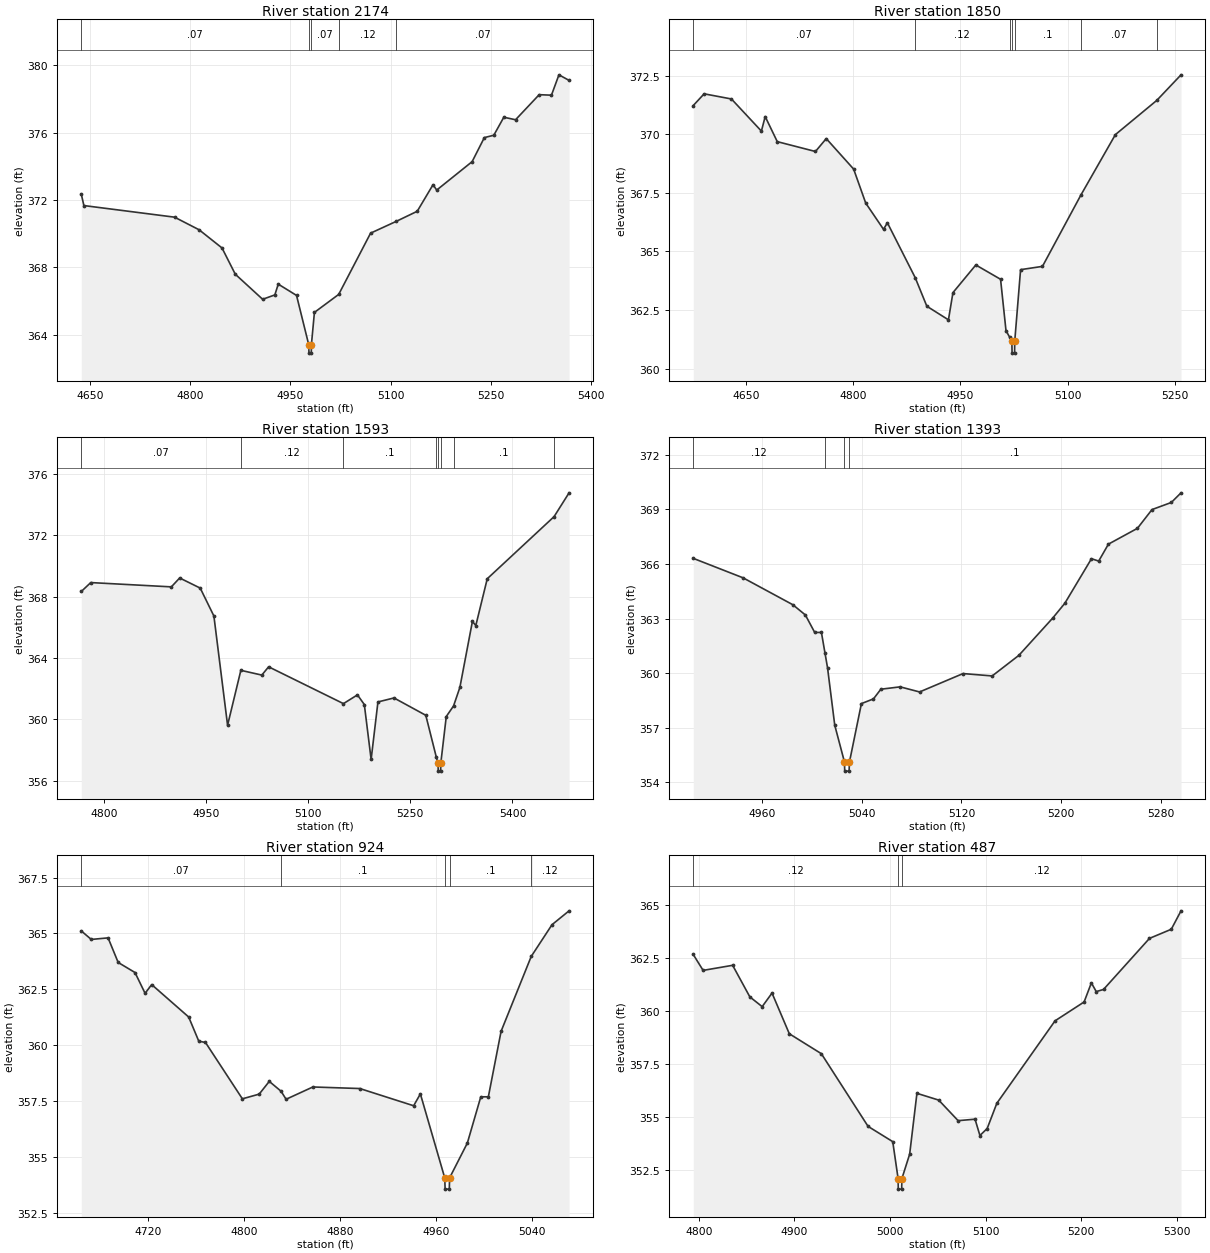
Type RM Length L Ch R = 1,2174,324,324,324
BEGIN DESCRIPTION:
Z21513
END DESCRIPTION:
XS GIS Cut Line= 3
      2518200.88     13828232.72      2518124.87     13827801.44
      2518011.74     13827530.97
#Sta/Elev= 30
  4636.5  372.34  4640.4  371.67  4776.3  370.98  4813.1  370.23  4847.4  369.15
  4867.3  367.59  4908.3  366.10  4926.6  366.36  4931.7  367.00  4959.1  366.33
  4977.4  363.40  4977.7  362.90  4981.2  362.90  4981.4  363.40  4985.9  365.32
  5022.3  366.39  5070.1  370.03  5108.5  370.73  5140.0  371.33  5163.7  372.91
  5169.2  372.59  5222.3  374.28  5240.6  375.71  5254.8  375.85  5269.8  376.92
  5287.4  376.77  5322.8  378.26  5341.2  378.23  5352.4  379.44  5367.6  379.11
#Mann=5,-1,0
  4636.5    0.07       0  4977.4    0.05       0  4981.4    0.07       0
  5022.3    0.12       0  5108.5    0.07       0
Bank Sta=4977.4,4981.4
Exp/Cntr=0.3,0.1

Type RM Length L Ch R = 1,1850,257,257,257
BEGIN DESCRIPTION:
StreamM043a 4.0
END DESCRIPTION:
XS GIS Cut Line= 3
      2518274.99     13828175.04      2518425.00     13827775.00
      2518475.00     13827524.99
#Sta/Elev= 30
  4576.3  371.22  4591.5  371.72  4629.7  371.50  4671.6  370.13  4676.9  370.75
  4693.8  369.68  4747.2  369.26  4762.3  369.81  4800.6  368.51  4817.5  367.06
  4842.4  365.94  4847.8  366.22  4886.7  363.88  4903.0  362.66  4933.2  362.08
  4939.5  363.24  4971.5  364.42  5006.1  363.81  5013.7  361.62  5018.6  361.35
  5021.9  361.16  5022.2  360.66  5025.7  360.66  5025.9  361.16  5034.1  364.22
  5064.7  364.36  5118.4  367.40  5166.7  369.98  5224.6  371.44  5258.5  372.53
#Mann=7,-1,0
  4576.3    0.07       0  4886.7    0.12       0  5018.6     0.1       0
  5021.9    0.05       0  5025.9     0.1       0  5118.4    0.07       0
  5224.6    0.12       0
Bank Sta=5021.9,5025.9
Exp/Cntr=0.3,0.1

Type RM Length L Ch R = 1,1593,200,200,200
BEGIN DESCRIPTION:
H21323
END DESCRIPTION:
XS GIS Cut Line= 3
      2518653.82     13828148.79      2518623.21     13827851.09
      2518588.44     13827435.21
#Sta/Elev= 30
  4766.6  368.33  4780.5  368.91  4898.9  368.63  4911.1  369.21  4941.3  368.55
  4961.4  366.73  4981.5  359.61  5001.0  363.19  5031.8  362.88  5041.8  363.42
  5151.7  361.02  5172.3  361.59  5182.4  360.96  5192.4  357.38  5202.4  361.13
  5226.0  361.39  5272.7  360.26  5288.0  357.56  5290.7  357.12  5291.0  356.62
  5294.5  356.62  5294.7  357.12  5302.8  360.18  5313.5  360.87  5322.8  362.08
  5341.2  366.38  5346.2  366.11  5363.0  369.16  5461.2  373.21  5483.2  374.76
#Mann=8,-1,0
  4766.6    0.07       0  5001.0    0.12       0  5151.7     0.1       0
  5288.0    0.12       0  5290.7    0.05       0  5294.7    0.12       0
  5313.5     0.1       0  5461.2    0.12       0
Bank Sta=5290.7,5294.7
Exp/Cntr=0.3,0.1

Type RM Length L Ch R = 1,1393,469,469,469
BEGIN DESCRIPTION:
StreamM043a 3.0
END DESCRIPTION:
XS GIS Cut Line= 3
      2518775.00     13827875.03      2518775.00     13827775.00
      2518925.01     13827524.98
#Sta/Elev= 30
  4904.7  366.31  4944.7  365.24  4984.7  363.76  4994.7  363.20  5002.2  362.24
  5007.6  362.24  5010.5  361.09  5012.5  360.30  5018.3  357.14  5026.1  355.12
  5026.3  354.62  5029.8  354.62  5030.1  355.12  5039.7  358.33  5049.4  358.59
  5055.3  359.12  5070.8  359.25  5086.4  358.97  5121.3  359.98  5144.7  359.85
  5166.1  360.98  5193.3  363.03  5203.0  363.84  5224.4  366.29  5230.2  366.16
  5238.0  367.09  5261.3  367.96  5273.0  368.99  5288.5  369.38  5296.3  369.91
#Mann=4,-1,0
  4904.7    0.12       0  5010.5     0.1       0  5026.1    0.05       0
  5030.1     0.1       0
Bank Sta=5026.1,5030.1
Exp/Cntr=0.3,0.1

Type RM Length L Ch R = 1,924,437,437,437
BEGIN DESCRIPTION:
StreamM043a 2.0
END DESCRIPTION:
XS GIS Cut Line= 3
      2519025.02     13827974.96      2519175.00     13827675.00
      2519225.02     13827624.98
#Sta/Elev= 30
  4664.5  365.11  4672.8  364.73  4686.8  364.80  4695.2  363.70  4709.2  363.25
  4717.6  362.32  4723.1  362.71  4753.9  361.26  4762.3  360.18  4767.9  360.12
  4798.6  357.60  4812.6  357.81  4821.0  358.38  4830.8  357.94  4835.0  357.58
  4857.3  358.13  4896.4  358.06  4941.2  357.29  4946.8  357.82  4967.1  354.06
  4967.4  353.56  4970.9  353.56  4971.1  354.06  4985.9  355.62  4997.1  357.69
  5003.4  357.69  5014.0  360.62  5039.1  363.97  5056.4  365.39  5070.6  366.01
#Mann=5,-1,0
  4664.5    0.07       0  4830.8     0.1       0  4967.1    0.05       0
  4971.1     0.1       0  5039.1    0.12       0
Bank Sta=4967.1,4971.1
Exp/Cntr=0.3,0.1

Type RM Length L Ch R = 1,487,253,253,253
BEGIN DESCRIPTION:
StreamM043a 1.0
END DESCRIPTION:
XS GIS Cut Line= 3
      2519175.02     13828024.99      2519375.00     13827975.00
      2519425.00     13827674.97
#Sta/Elev= 30
  4794.2  362.65  4804.5  361.90  4835.4  362.14  4853.4  360.65  4866.3  360.19
  4876.6  360.83  4894.7  358.91  4928.2  357.97  4977.1  354.54  5002.9  353.82
  5008.5  352.08  5008.7  351.58  5012.2  351.58  5012.5  352.08  5020.6  353.23
  5028.2  356.10  5051.0  355.78  5071.3  354.81  5089.0  354.88  5094.1  354.11
  5101.7  354.44  5111.8  355.63  5172.7  359.52  5203.1  360.41  5210.7  361.31
  5215.8  360.90  5223.4  361.00  5271.5  363.41  5294.3  363.84  5304.5  364.71
#Mann=3,-1,0
  4794.2    0.12       0  5008.5    0.05       0  5012.5    0.12       0
Bank Sta=5008.5,5012.5
Exp/Cntr=0.3,0.1

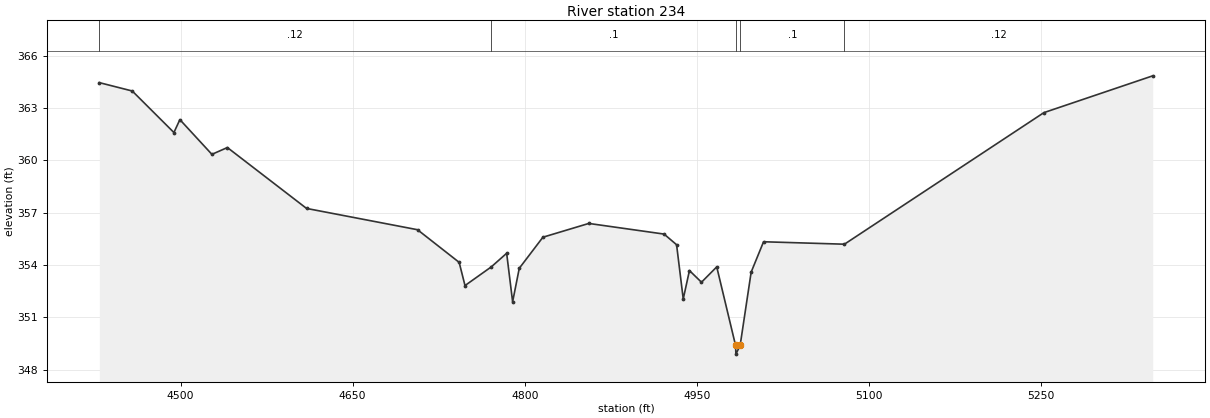
Type RM Length L Ch R = 1,234,0,0,0
BEGIN DESCRIPTION:
H21324
END DESCRIPTION:
XS GIS Cut Line= 4
      2519119.73     13828186.31      2519507.82     13828090.33
      2519588.49     13827896.99      2519576.04     13827588.42
#Sta/Elev= 30
  4429.2  364.45  4457.9  363.97  4494.2  361.59  4499.4  362.33  4527.3  360.34
  4540.8  360.73  4609.8  357.24  4706.5  356.02  4742.8  354.15  4747.9  352.82
  4770.8  353.89  4784.2  354.67  4789.4  351.89  4795.2  353.81  4815.8  355.59
  4855.8  356.38  4921.4  355.77  4932.3  355.16  4938.1  352.05  4943.5  353.68
  4954.0  353.01  4967.3  353.89  4983.7  349.39  4984.0  348.89  4987.7  349.39
  4997.3  353.59  5008.1  355.33  5078.6  355.19  5252.4  362.73  5347.3  364.84
#Mann=5,-1,0
  4429.2    0.12       0  4770.8     0.1       0  4983.7    0.05       0
  4987.7     0.1       0  5078.6    0.12       0
Bank Sta=4983.7,4987.7
Exp/Cntr=0.3,0.1

Chan Stop Cuts=-1