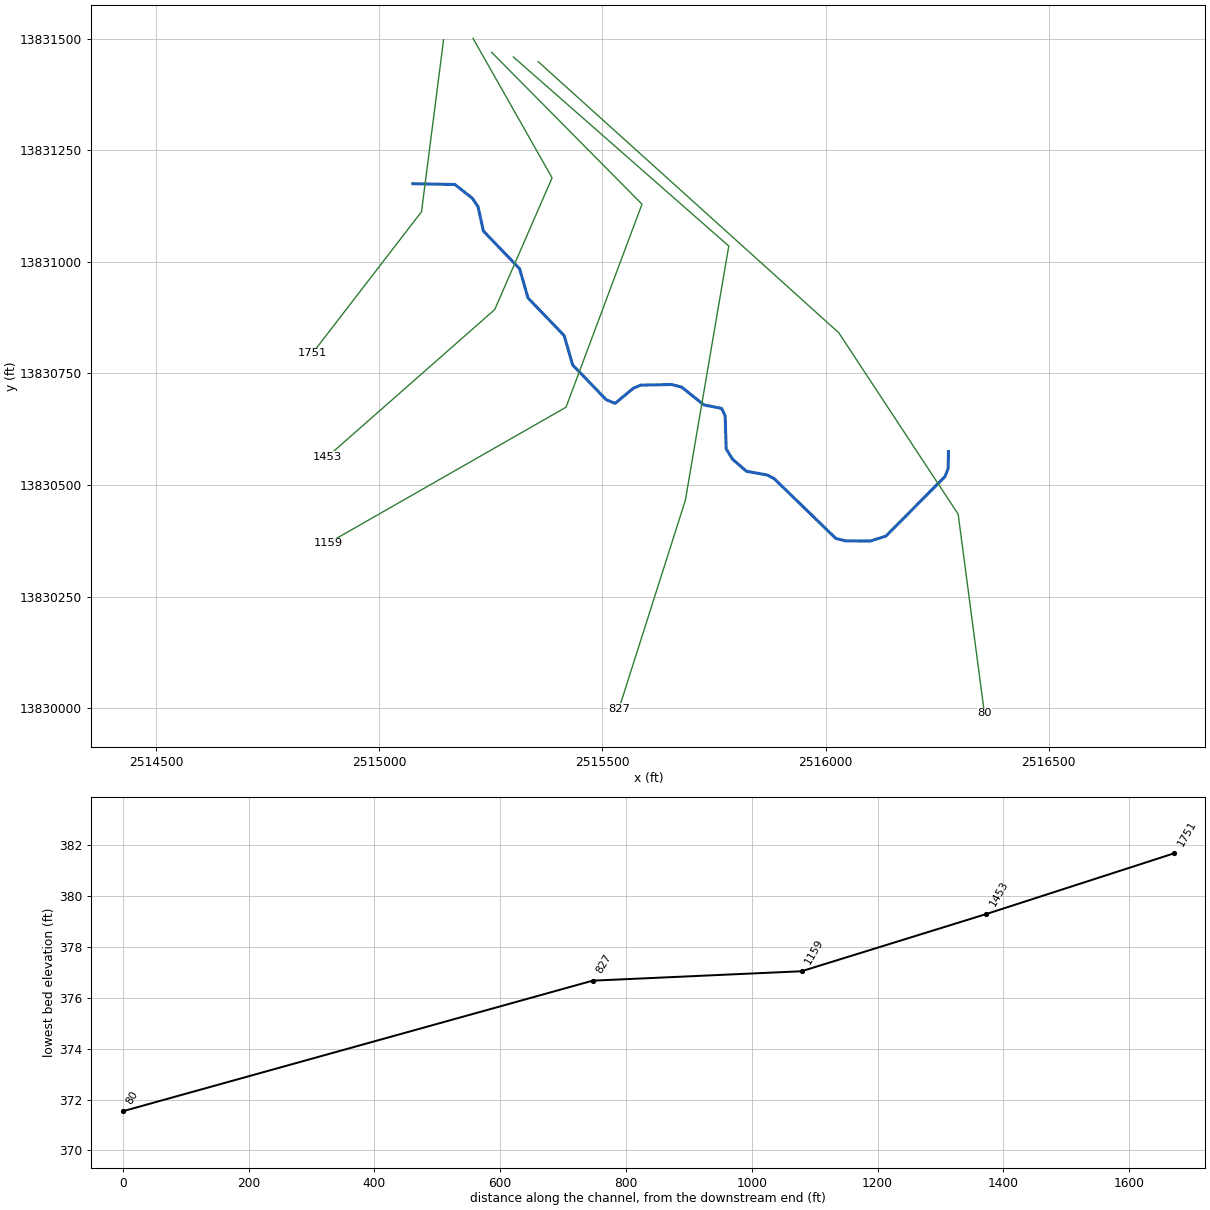
--- StreamM044.prj (project) ---

Proj Title=StreamM044 Base Level Engineering
Current Plan=p01
Default Exp/Contr=0.3,0.1
English Units
Geom File=g01
Flow File=f01
Plan File=p01
BEGIN DESCRIPTION:
StreamM044
END DESCRIPTION:

--- StreamM044.p01 (plan) ---

Plan Title=Multiple Run
Short Identifier=Multiple
Geom File=g01
Flow File=f01
Subcritical Flow
K Sum by GR= 0
Std Step Tol= 0.01
Critical Tol= 0.01
Num of Std Step Trials= 20
Max Error Tol= 0.3
Flow Tol Ratio= 0.001
Split Flow NTrial= 30
Split Flow Tol= 0.02
Split Flow Ratio= 0.02
Log Output Level= 0
Friction Slope Method= 1
Unsteady Friction Slope Method= 2
Unsteady Bridges Friction Slope Method= 1
Parabolic Critical Depth
Global Vel Dist=  1 , 1 , 1
Global Log Level= 0
CheckData=True
Encroach Param= -1, 0, 0, 0
BEGIN DESCRIPTION:
Multiple Run
END DESCRIPTION:

--- StreamM044.f01 (steady flow) ---

Flow Title=Multiple
Number of Profiles=7
Profile Names=10-year,25-year,50-year,1pct_min,100-year,1pct_plu,500-year
River Rch & RM= StreamM044,Reach-1,1751
     656    1048    1400     906    1807    3606    2979
Boundary for River Rch & Prof#=StreamM044,Reach-1,1
Up Type=0
Dn Type=3
Dn Slope=0.005
Boundary for River Rch & Prof#=StreamM044,Reach-1,2
Up Type=0
Dn Type=3
Dn Slope=0.005
Boundary for River Rch & Prof#=StreamM044,Reach-1,3
Up Type=0
Dn Type=3
Dn Slope=0.005
Boundary for River Rch & Prof#=StreamM044,Reach-1,4
Up Type=0
Dn Type=3
Dn Slope=0.005
Boundary for River Rch & Prof#=StreamM044,Reach-1,5
Up Type=0
Dn Type=3
Dn Slope=0.005
Boundary for River Rch & Prof#=StreamM044,Reach-1,6
Up Type=0
Dn Type=3
Dn Slope=0.005
Boundary for River Rch & Prof#=StreamM044,Reach-1,7
Up Type=0
Dn Type=3
Dn Slope=0.005

--- StreamM044.g01 (geometry) ---

Geom Title=Existing Conditions

River Reach=StreamM044,Reach-1
Reach XY= 30
      2515075.00     13831175.00      2515169.45     13831173.23
      2515208.56     13831142.13      2515221.13     13831123.59
      2515233.18     13831068.98      2515314.20     13830984.67
      2515333.18     13830918.96      2515414.20     13830834.67
      2515433.16     13830768.91      2515508.26     13830691.28
      2515528.21     13830682.87      2515568.83     13830716.58
      2515585.48     13830723.72      2515654.91     13830725.10
      2515677.36     13830719.37      2515727.18     13830679.40
      2515766.85     13830671.63      2515774.78     13830654.74
      2515777.11     13830580.80      2515791.31     13830557.90
      2515822.43     13830530.74      2515868.91     13830522.45
      2515884.66     13830514.21      2516022.57     13830380.40
      2516045.06     13830374.78      2516100.04     13830374.49
      2516134.79     13830385.43      2516267.24     13830518.79
      2516274.41     13830536.84      2516275.00     13830575.00

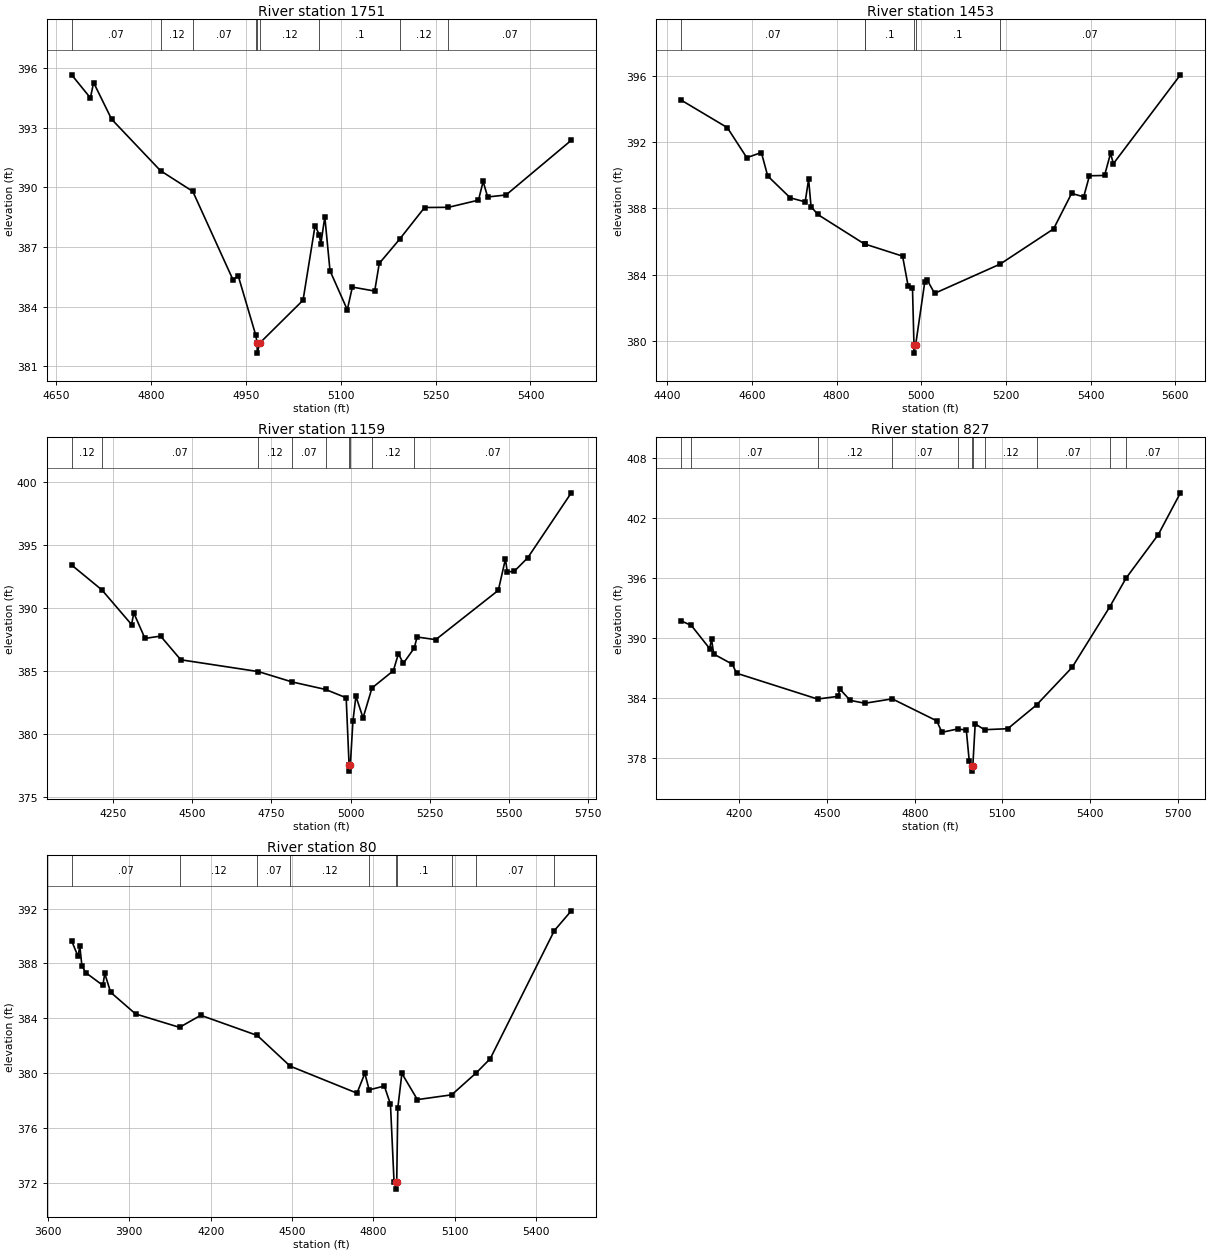
Type RM Length L Ch R = 1,1751,298,298,298
BEGIN DESCRIPTION:
MXS18515
END DESCRIPTION:
XS GIS Cut Line= 3
      2515144.00     13831497.61      2515094.52     13831112.19
      2514849.88     13830794.68
#Sta/Elev= 30
  4675.1  395.66  4704.7  394.50  4709.8  395.27  4738.2  393.43  4815.5  390.84
  4866.5  389.80  4929.8  385.37  4938.5  385.53  4966.1  382.56  4968.1  382.17
  4968.4  381.67  4972.1  382.17  5040.7  384.33  5059.7  388.08  5066.2  387.63
  5068.8  387.16  5075.1  388.52  5083.3  385.81  5110.6  383.85  5118.6  384.99
  5153.9  384.79  5161.1  386.18  5193.1  387.39  5232.7  388.99  5270.4  389.00
  5317.9  389.36  5325.2  390.30  5332.4  389.52  5361.4  389.62  5464.5  392.37
#Mann=9,-1,0
  4675.1    0.07       0  4815.5    0.12       0  4866.5    0.07       0
  4966.1    0.12       0  4968.1    0.05       0  4972.1    0.12       0
  5066.2     0.1       0  5193.1    0.12       0  5270.4    0.07       0
Bank Sta=4968.1,4972.1
Exp/Cntr=0.3,0.1

Type RM Length L Ch R = 1,1453,294,294,294
BEGIN DESCRIPTION:
H21328
END DESCRIPTION:
XS GIS Cut Line= 4
      2515209.97     13831500.66      2515387.06     13831188.15
      2515258.58     13830893.01      2514883.60     13830563.16
#Sta/Elev= 30
  4431.9  394.54  4541.8  392.87  4587.8  391.06  4622.3  391.37  4637.2  389.96
  4690.6  388.64  4725.8  388.40  4733.9  389.76  4739.6  388.12  4755.5  387.64
  4866.6  385.85  4868.0  385.85  4955.9  385.13  4969.0  383.34  4979.3  383.24
  4982.8  379.79  4983.0  379.29  4986.8  379.79  5008.2  383.55  5013.7  383.71
  5031.6  382.89  5186.3  384.65  5312.6  386.77  5355.3  388.91  5383.8  388.70
  5397.4  389.97  5433.1  389.99  5447.3  391.32  5454.0  390.70  5612.4  396.05
#Mann=6,-1,0
  4431.9    0.07       0  4866.6    0.12       0  4868.0     0.1       0
  4982.8    0.05       0  4986.8     0.1       0  5186.3    0.07       0
Bank Sta=4982.8,4986.8
Exp/Cntr=0.3,0.1

Type RM Length L Ch R = 1,1159,332,332,332
BEGIN DESCRIPTION:
H21327
END DESCRIPTION:
XS GIS Cut Line= 4
      2515251.66     13831469.37      2515588.44     13831129.12
      2515418.31     13830674.26      2514884.75     13830369.37
#Sta/Elev= 30
  4118.7  393.42  4214.4  391.44  4308.0  388.69  4315.1  389.61  4350.4  387.59
  4399.9  387.77  4463.5  385.89  4709.0  384.95  4815.1  384.13  4921.3  383.53
  4986.2  382.87  4995.4  377.54  4995.7  377.04  4999.4  377.54  5007.6  381.03
  5017.0  382.99  5039.6  381.27  5067.8  383.65  5135.3  385.02  5151.2  386.36
  5167.0  385.61  5201.5  386.83  5210.2  387.70  5269.2  387.49  5467.0  391.41
  5489.5  393.90  5495.3  392.88  5516.9  392.91  5560.1  394.00  5697.6  399.16
#Mann=9,-1,0
  4118.7    0.12       0  4214.4    0.07       0  4709.0    0.12       0
  4815.1    0.07       0  4921.3     0.1       0  4995.4    0.05       0
  4999.4     0.1       0  5067.8    0.12       0  5201.5    0.07       0
Bank Sta=4995.4,4999.4
Exp/Cntr=0.3,0.1

Type RM Length L Ch R = 1,827,747,747,747
BEGIN DESCRIPTION:
H21326
END DESCRIPTION:
XS GIS Cut Line= 4
      2515300.26     13831458.97      2515782.89     13831035.37
      2515685.67     13830465.93      2515536.81     13829998.60
#Sta/Elev= 30
  3999.1  391.74  4035.3  391.26  4097.8  388.95  4104.4  389.87  4111.8  388.40
  4175.6  387.38  4189.8  386.48  4467.4  383.89  4537.1  384.16  4543.8  384.88
  4578.9  383.76  4629.2  383.47  4722.9  383.91  4875.0  381.71  4893.1  380.56
  4946.4  380.89  4976.4  380.79  4986.5  377.67  4994.7  377.17  4994.9  376.67
  4998.7  377.17  5006.8  381.40  5038.8  380.82  5118.4  380.92  5216.8  383.30
  5338.5  387.06  5466.9  393.10  5523.2  396.00  5633.7  400.37  5709.4  404.55
#Mann=11,-1,0
  3999.1    0.12       0  4035.3    0.07       0  4467.4    0.12       0
  4722.9    0.07       0  4946.4     0.1       0  4994.7    0.05       0
  4998.7     0.1       0  5038.8    0.12       0  5216.8    0.07       0
  5466.9    0.05       0  5523.2    0.07       0
Bank Sta=4994.7,4998.7
Exp/Cntr=0.3,0.1

Type RM Length L Ch R = 1,80,0,0,0
BEGIN DESCRIPTION:
H21325
END DESCRIPTION:
XS GIS Cut Line= 4
      2515355.77     13831448.60      2516029.42     13830840.93
      2516296.78     13830434.68      2516355.59     13829988.40
#Sta/Elev= 30
  3687.1  389.65  3710.6  388.52  3717.3  389.27  3724.8  387.85  3739.0  387.33
  3802.5  386.40  3809.2  387.28  3830.9  385.90  3922.8  384.32  4085.1  383.34
  4163.5  384.22  4372.0  382.75  4493.5  380.51  4740.0  378.54  4769.0  379.99
  4784.9  378.78  4840.9  379.06  4863.5  377.74  4876.8  372.05  4882.6  372.04
  4882.8  371.54  4886.6  372.04  4890.6  377.45  4905.7  379.98  4962.9  378.07
  5089.6  378.42  5180.5  380.03  5231.6  381.05  5468.4  390.40  5530.8  391.84
#Mann=10,-1,0
  3687.1    0.07       0  4085.1    0.12       0  4372.0    0.07       0
  4493.5    0.12       0  4784.9     0.1       0  4882.6    0.05       0
  4886.6     0.1       0  5089.6    0.12       0  5180.5    0.07       0
  5468.4    0.05       0
Bank Sta=4882.6,4886.6
Exp/Cntr=0.3,0.1

Chan Stop Cuts=-1