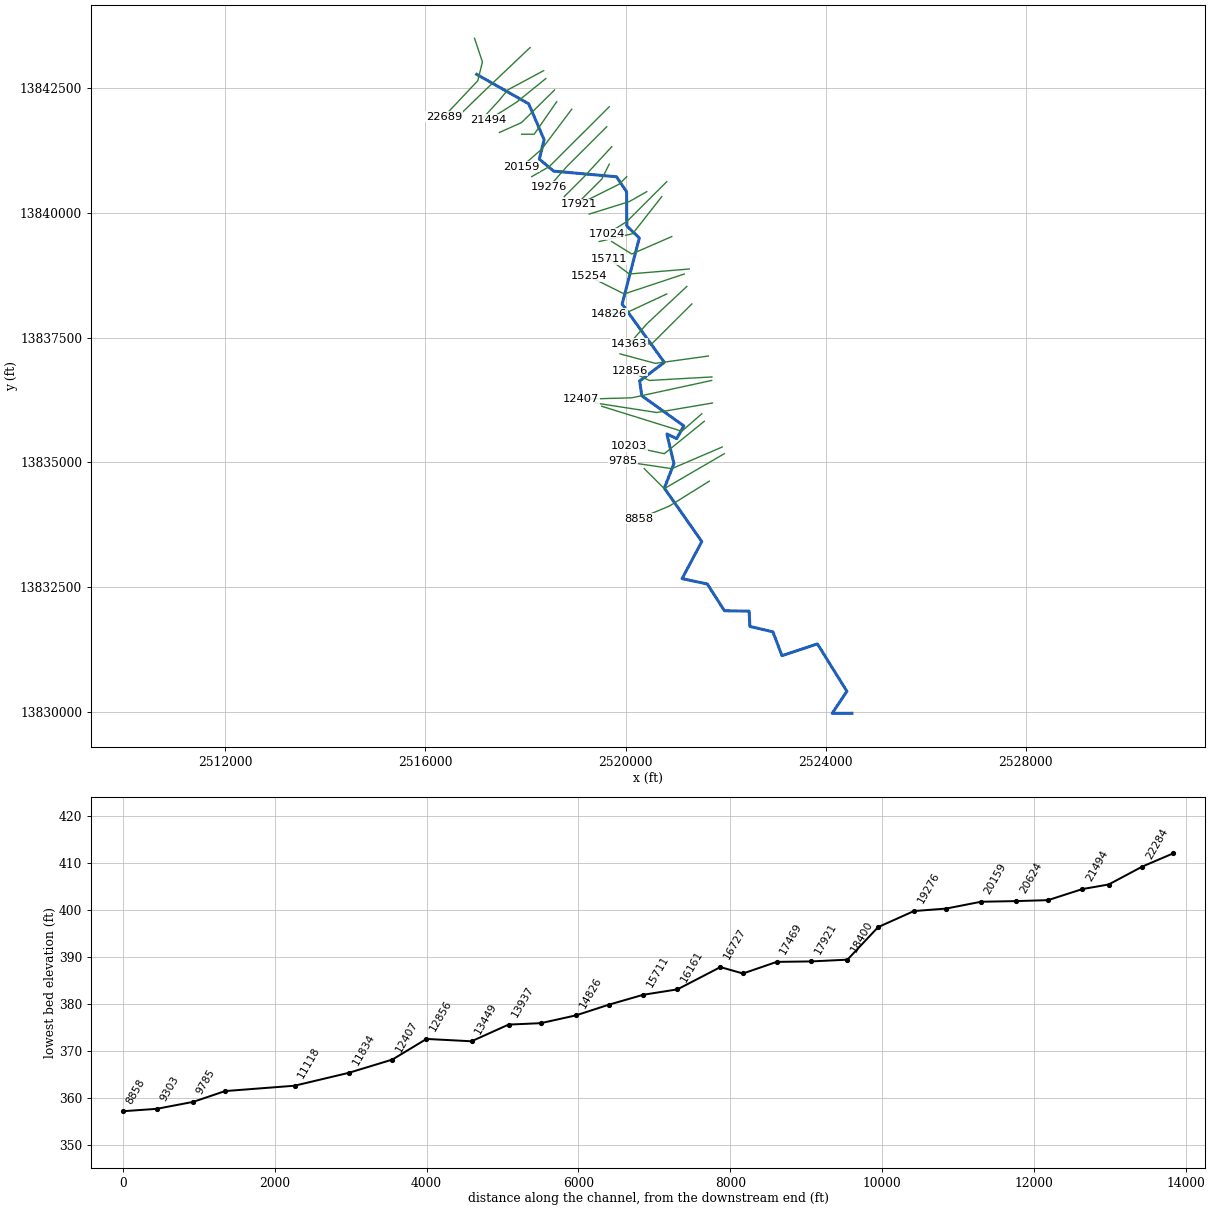
--- StreamM045.prj (project) ---

Proj Title=StreamM045 Base Level Engineering
Current Plan=p01
Default Exp/Contr=0.3,0.1
English Units
Geom File=g01
Flow File=f01
Plan File=p01
Y Axis Title=Elevation
X Axis Title(PF)=Main Channel Distance
X Axis Title(XS)=Station
BEGIN DESCRIPTION:
StreamM045
END DESCRIPTION:
DSS Export Rating Curves= 0
DSS Export Rating Curve Sorted= 0
DSS Export Volume Flow Curves= 0
DXF OffsetX= 0
DXF OffsetY= 0
DXF ScaleX= 1
DXF ScaleY= 10

--- StreamM045.p01 (plan) ---

Plan Title=Multiple Run
Short Identifier=Multiple
Geom File=g01
Flow File=f01
Subcritical Flow
K Sum by GR= 0
Std Step Tol= 0.01
Critical Tol= 0.01
Num of Std Step Trials= 20
Max Error Tol= 0.3
Flow Tol Ratio= 0.001
Split Flow NTrial= 30
Split Flow Tol= 0.02
Split Flow Ratio= 0.02
Log Output Level= 0
Friction Slope Method= 1
Unsteady Friction Slope Method= 2
Unsteady Bridges Friction Slope Method= 1
Parabolic Critical Depth
Global Vel Dist=  1 , 1 , 1
Global Log Level= 0
CheckData=True
Encroach Param= -1, 0, 0, 0
BEGIN DESCRIPTION:
Multiple Run
END DESCRIPTION:

--- StreamM045.f01 (steady flow) ---

Flow Title=Multiple
Number of Profiles=7
Profile Names=10-year,25-year,50-year,1pct_min,100-year,1pct_plu,500-year
River Rch & RM= StreamM045,Reach-1,22689
     456     714     941     601    1200    2394    1930
River Rch & RM= StreamM045,Reach-1,21840
     756    1217    1633    1060    2115    4220    3512
River Rch & RM= StreamM045,Reach-1,17921
     887    1437    1936    1261    2516    5019    4207
River Rch & RM= StreamM045,Reach-1,11834
    1279    2113    2883    1901    3793    7567    6500
River Rch & RM= StreamM045,Reach-1,11118
    1498    2483    3395    2240    4470    8919    7678
Boundary for River Rch & Prof#=StreamM045,Reach-1,1
Up Type=0
Dn Type=3
Dn Slope=0.005
Boundary for River Rch & Prof#=StreamM045,Reach-1,2
Up Type=0
Dn Type=3
Dn Slope=0.005
Boundary for River Rch & Prof#=StreamM045,Reach-1,3
Up Type=0
Dn Type=3
Dn Slope=0.005
Boundary for River Rch & Prof#=StreamM045,Reach-1,4
Up Type=0
Dn Type=3
Dn Slope=0.005
Boundary for River Rch & Prof#=StreamM045,Reach-1,5
Up Type=0
Dn Type=3
Dn Slope=0.005
Boundary for River Rch & Prof#=StreamM045,Reach-1,6
Up Type=0
Dn Type=3
Dn Slope=0.005
Boundary for River Rch & Prof#=StreamM045,Reach-1,7
Up Type=0
Dn Type=3
Dn Slope=0.005

--- StreamM045.g01 (geometry) ---

Geom Title=Existing Conditions
Program Version=4.10

River Reach=StreamM045      ,Reach-1
Reach XY= 30
        2517025.       13842775.      2518064.82      13842184.7
      2518374.14     13841464.69      2518278.44     13841076.25
      2518565.32     13840835.17      2519819.35     13840723.03
      2520021.48     13840423.72      2520026.66     13839736.84
       2520275.4     13839495.27      2519932.79     13838171.58
      2520775.26     13837005.05      2520282.45     13836631.07
      2520325.53     13836335.45      2521165.89     13835731.73
      2521023.14     13835477.83      2520826.98     13835569.38
      2520967.77     13834975.31      2520775.47     13834485.54
      2521524.54     13833414.48      2521130.45     13832671.99
       2521634.7     13832564.26      2521976.44     13832028.54
      2522469.97     13832019.92      2522485.32     13831714.82
      2522945.59     13831605.41      2523126.25     13831128.36
        2523835.     13831364.37       2524423.8     13830414.49
      2524130.45     13829972.53        2524525.       13829975.

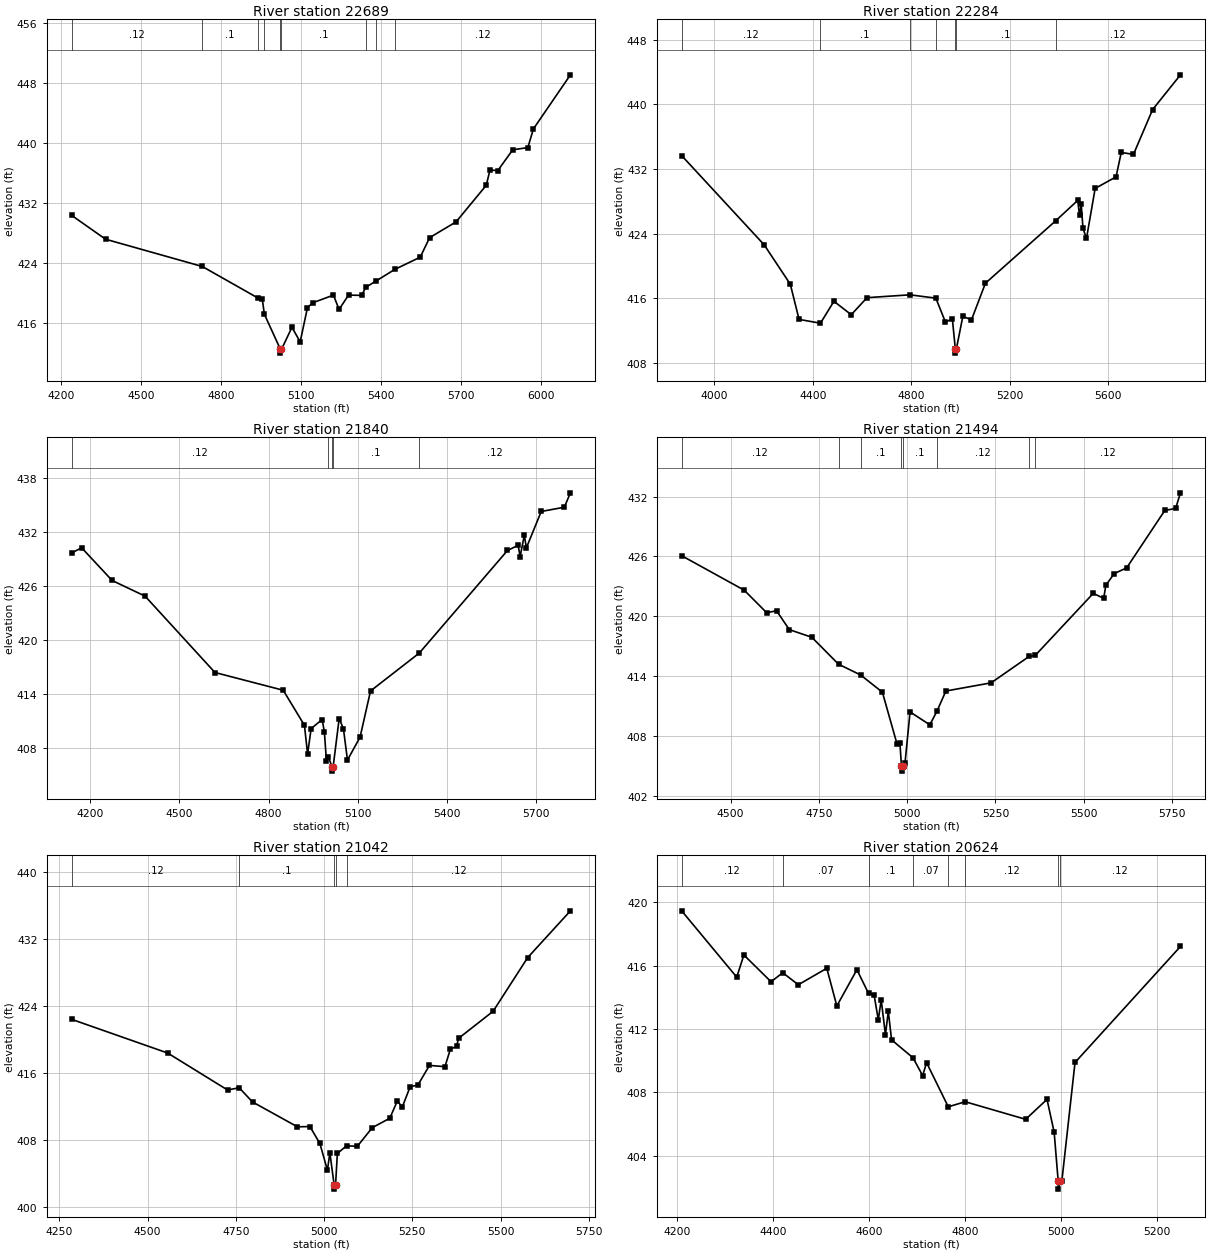
Type RM Length L Ch R = 1 ,22689   ,405,405,405
BEGIN DESCRIPTION:
H21339
END DESCRIPTION:
XS GIS Cut Line= 4
      2516983.26     13843495.95      2517141.01     13843022.69
      2517048.54     13842647.35      2516374.35     13841929.67
#Sta/Elev= 30
  4239.4  430.39  4366.9  427.21  4729.4  423.58    4937   419.4  4954.4  419.21
    4962  417.23  5022.3  412.54  5022.5  412.04  5026.3  412.54  5065.4  415.48
  5096.3  413.54  5123.5  418.08    5143  418.74  5221.1  419.77  5242.1  417.86
  5277.7  419.77  5327.1  419.73  5341.8   420.8  5379.5  421.62  5451.4   423.2
  5546.4  424.82  5581.6  427.42  5680.7  429.52    5794   434.4  5808.2  436.47
  5836.5  436.32  5893.1  439.12  5949.8  439.42  5970.8  441.91  6109.5  449.11
#Mann= 9 ,-1 , 0
  4239.4     .12       0  4729.4      .1       0    4937     .12       0
    4962      .1       0  5022.3     .05       0  5026.3      .1       0
  5341.8     .12       0  5379.5      .1       0  5451.4     .12       0
Bank Sta=5022.3,5026.3
XS Rating Curve= 0 ,0
Exp/Cntr=0.3,0.1

Type RM Length L Ch R = 1 ,22284   ,444,444,444
BEGIN DESCRIPTION:
H21338
END DESCRIPTION:
XS GIS Cut Line= 3
      2518092.93     13843310.97      2517179.09     13842440.65
      2516631.11     13841908.95
#Sta/Elev= 30
  3867.7  433.67  4202.9  422.63  4308.9  417.76  4344.4  413.41  4431.3  412.94
    4486  415.65  4556.4  413.99  4620.3   416.1  4794.7  416.45  4899.9  416.04
  4938.6  413.09  4966.9  413.46  4979.1  409.74  4979.3  409.24  4983.1  409.74
  5009.4  413.78  5044.6  413.36  5101.2  417.89  5386.7  425.61    5476  428.13
  5483.2  426.27  5490.1  427.66  5497.3  424.68  5511.5  423.42  5546.7  429.61
  5631.6  431.04  5652.7  434.06  5702.3  433.82    5780  439.36  5893.2  443.66
#Mann= 7 ,-1 , 0
  3867.7     .12       0  4431.3      .1       0  4794.7     .12       0
  4899.9      .1       0  4979.1     .05       0  4983.1      .1       0
  5386.7     .12       0
Bank Sta=4979.1,4983.1
XS Rating Curve= 0 ,0
Exp/Cntr=0.3,0.1

Type RM Length L Ch R = 1 ,21840   ,346,346,346
BEGIN DESCRIPTION:
H21337
END DESCRIPTION:
XS GIS Cut Line= 4
      2518364.92     13842848.61       2517646.9     13842462.41
      2517472.83     13842250.26      2517075.76     13841815.11
#Sta/Elev= 30
  4137.3  429.64  4171.1  430.22  4273.5  426.59  4384.5  424.85  4619.8  416.37
  4849.5   414.4  4920.9  410.51  4931.5  407.31  4943.4  410.14  4980.4  411.15
    4988   409.8  4994.8  406.59  5001.4  406.99  5013.6  405.92  5013.8  405.42
  5017.6  405.92  5037.8  411.26  5052.2  410.12  5065.7  406.65  5108.1  409.19
  5143.3  414.32  5307.5  418.53  5604.3  429.92  5640.1  430.49  5646.8  429.24
    5661  431.62  5667.8   430.2  5717.8  434.25  5795.5  434.72  5816.1  436.32
#Mann= 5 ,-1 , 0
  4137.3     .12       0  5001.4      .1       0  5013.6     .05       0
  5017.6      .1       0  5307.5     .12       0
Bank Sta=5013.6,5017.6
XS Rating Curve= 0 ,0
Exp/Cntr=0.3,0.1

Type RM Length L Ch R = 1 ,21494   ,452,452,452
BEGIN DESCRIPTION:
H21336
END DESCRIPTION:
XS GIS Cut Line= 3
      2518408.43     13842690.86      2517826.41     13842217.62
      2517266.09     13841864.02
#Sta/Elev= 30
  4361.2  426.07  4538.3  422.61  4602.2  420.34  4629.8  420.55  4666.1  418.65
    4730  417.88  4805.4  415.18    4868   414.1  4929.7  412.37  4971.4  407.14
  4979.3  407.27  4983.7  404.95    4984  404.45  4987.7  404.95  4993.7  405.24
    5008  410.39    5064   409.1    5084  410.45  5109.5  412.49  5237.6  413.31
  5345.2  415.96  5362.5  416.06  5526.9  422.29  5556.5  421.79  5562.4  423.09
    5586  424.27  5621.5  424.85  5729.5  430.61  5760.1  430.81  5773.9  432.38
#Mann= 8 ,-1 , 0
  4361.2     .12       0  4805.4     .07       0    4868      .1       0
  4983.7     .05       0  4987.7      .1       0    5084     .12       0
  5345.2      .1       0  5362.5     .12       0
Bank Sta=4983.7,4987.7
XS Rating Curve= 0 ,0
Exp/Cntr=0.3,0.1

Type RM Length L Ch R = 1 ,21042   ,418,418,418
BEGIN DESCRIPTION:
H21335
END DESCRIPTION:
XS GIS Cut Line= 3
      2518582.53     13842462.41      2517924.32     13841809.65
      2517480.97      13841609.6
#Sta/Elev= 30
  4284.6  422.39  4556.8  418.36  4726.5  413.94  4759.4  414.21  4797.2  412.51
  4924.5  409.54  4959.8  409.57  4988.1  407.55  5009.4  404.35  5016.4  406.44
  5028.5  402.59  5028.8  402.09  5032.5  402.59  5037.6  406.35  5063.6  407.27
  5094.2  407.21  5136.6  409.44  5186.1  410.56  5207.4  412.61  5221.8  411.92
  5243.8  414.33  5265.7  414.53  5298.6  416.88  5342.5  416.73  5357.8  418.82
  5375.4  419.15  5380.9  420.11  5478.9  423.35  5576.9  429.77    5698  435.36
#Mann= 5 ,-1 , 0
  4284.6     .12       0  4759.4      .1       0  5028.5     .05       0
  5032.5      .1       0  5063.6     .12       0
Bank Sta=5028.5,5032.5
XS Rating Curve= 0 ,0
Exp/Cntr=0.3,0.1

Type RM Length L Ch R = 1 ,20624   ,465,465,465
BEGIN DESCRIPTION:
StreamM045 34.0
END DESCRIPTION:
XS GIS Cut Line= 3
      2518625.02     13842225.04        2518175.       13841575.
      2517925.01       13841575.
#Sta/Elev= 30
  4208.7  419.47  4323.6  415.28  4338.5  416.68  4395.2  414.99  4419.6  415.56
    4452   414.8  4511.5  415.84  4532.4  413.46  4574.3  415.75  4598.6  414.25
  4610.1  414.16  4618.9  412.59    4625  413.85  4633.8  411.64  4639.8  413.13
  4646.6  411.32  4691.2  410.19  4711.5  409.06  4719.6  409.88  4764.9  407.09
  4800.2  407.41  4926.3   406.3  4970.9  407.56  4985.8  405.48  4994.2  402.39
  4994.5  401.89  4998.3  402.39  5001.8  402.39  5029.3  409.89  5249.3  417.22
#Mann= 8 ,-1 , 0
  4208.7     .12       0  4419.6     .07       0  4598.6      .1       0
  4691.2     .07       0  4764.9      .1       0  4800.2     .12       0
  4994.2     .05       0  4998.3     .12       0
Bank Sta=4994.2,4998.3
XS Rating Curve= 0 ,0
Exp/Cntr=0.3,0.1

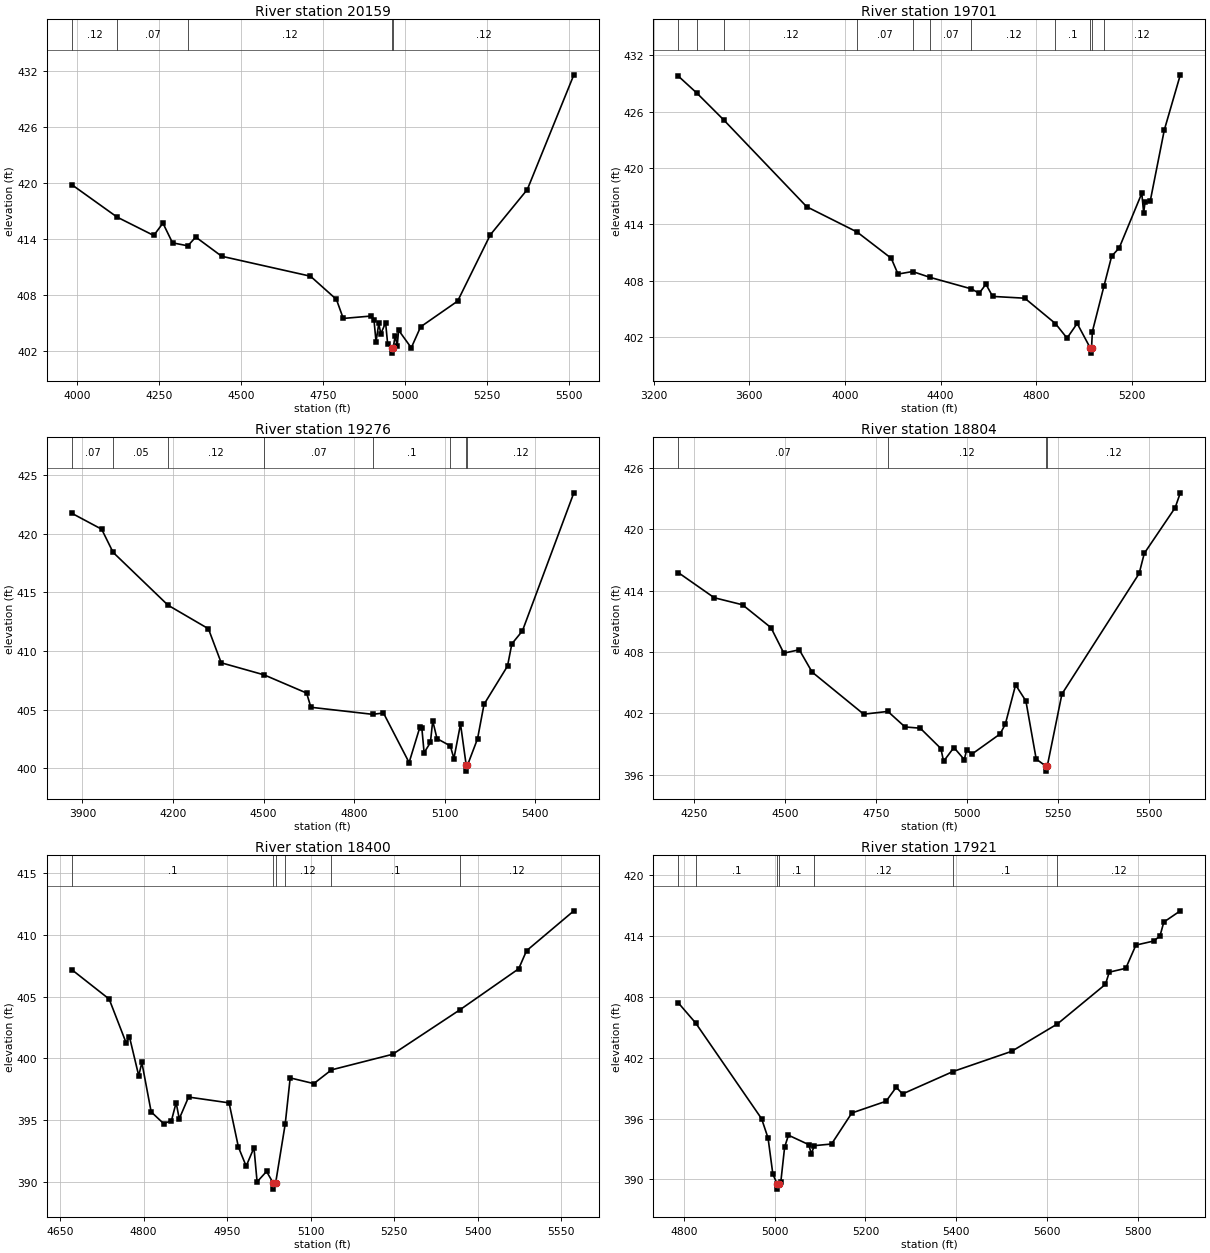
Type RM Length L Ch R = 1 ,20159   ,458,458,458
BEGIN DESCRIPTION:
StreamM045 33.0
END DESCRIPTION:
XS GIS Cut Line= 3
      2518925.01     13842075.02        2518325.       13841275.
      2517925.02     13840925.02
#Sta/Elev= 30
  3984.3  419.82  4122.6  416.34  4234.3  414.37  4262.4  415.69  4291.6  413.58
  4338.4  413.26  4362.4   414.2  4441.6  412.14  4712.4     410  4791.6  407.51
  4812.4  405.47  4897.9  405.73  4906.2   405.3  4912.4  402.97  4920.8  404.93
    4927  403.82  4941.6  405.02  4947.9  402.71  4960.4  402.25  4960.6  401.75
  4964.5  402.25  4970.8  403.64    4977  402.51  4981.2  404.21  5019.9  402.32
  5048.4  404.57  5161.3  407.33    5261  414.44  5373.9   419.3  5515.8   431.6
#Mann= 5 ,-1 , 0
  3984.3     .12       0  4122.6     .07       0  4338.4     .12       0
  4960.4     .05       0  4964.5     .12       0
Bank Sta=4960.4,4964.5
XS Rating Curve= 0 ,0
Exp/Cntr=0.3,0.1

Type RM Length L Ch R = 1 ,19701   ,425,425,425
BEGIN DESCRIPTION:
StreamM045 32.0
END DESCRIPTION:
XS GIS Cut Line= 3
      2519675.02     13842125.02        2518475.       13840925.
        2518125.       13840725.
#Sta/Elev= 30
  3302.9  429.81  3380.6     428  3493.1  425.14  3840.3  415.89    4051   413.2
  4193.9   410.4  4222.2  408.72  4282.9  408.99    4356  408.37  4529.6  407.14
  4561.6  406.67  4589.9  407.64  4618.2  406.34  4752.5  406.15  4880.6  403.45
  4929.3   401.9  4971.7  403.46  5027.4   400.8  5027.7   400.3  5031.6   400.8
  5035.3   402.6  5084.1  407.48  5115.9  410.62  5147.6  411.51  5241.9  417.32
  5249.8  415.25  5255.5  416.35  5277.1  416.47  5336.2  424.07  5403.1  429.94
#Mann= 11 ,-1 , 0
  3302.9     .12       0  3380.6     .07       0  3493.1     .12       0
    4051     .07       0  4282.9     .12       0    4356     .07       0
  4529.6     .12       0  4880.6      .1       0  5027.4     .05       0
  5031.6      .1       0  5084.1     .12       0
Bank Sta=5027.4,5031.6
XS Rating Curve= 0 ,0
Exp/Cntr=0.3,0.1

Type RM Length L Ch R = 1 ,19276   ,472,472,472
BEGIN DESCRIPTION:
StreamM045 31.0
END DESCRIPTION:
XS GIS Cut Line= 3
      2519624.98     13841724.98        2518825.       13840925.
      2518475.03     13840525.04
#Sta/Elev= 30
  3864.6  421.74  3963.6  420.38  4001.4  418.41  4183.2  413.91  4317.1   411.9
  4359.5     409  4501.7  407.97  4642.4  406.42  4656.5  405.21  4860.8  404.61
  4896.9  404.72  4981.8   400.5  5017.3   403.5  5023.9  403.46  5031.5  401.34
  5052.4  402.21    5060  404.06  5074.2  402.54  5118.3  401.92  5130.2  400.84
  5152.1  403.78  5170.9  400.27  5171.1  399.77  5175.1  400.27  5208.5  402.53
  5229.9  405.46  5307.7  408.72    5322  410.61  5357.1  411.72  5527.4  423.48
#Mann= 8 ,-1 , 0
  3864.6     .07       0  4001.4     .05       0  4183.2     .12       0
  4501.7     .07       0  4860.8      .1       0  5118.3     .12       0
  5170.9     .05       0  5175.1     .12       0
Bank Sta=5170.9,5175.1
XS Rating Curve= 0 ,0
Exp/Cntr=0.3,0.1

Type RM Length L Ch R = 1 ,18804   ,404,404,404
BEGIN DESCRIPTION:
StreamM045 30.0
END DESCRIPTION:
XS GIS Cut Line= 3
      2519724.98     13841324.98        2519175.       13840725.
        2518775.       13840325.
#Sta/Elev= 30
  4205.5  415.77  4304.4  413.31  4382.1  412.62  4460.4  410.38  4495.6  407.89
  4538.1  408.22  4573.3  406.04  4715.1  401.92  4781.5  402.19  4828.6  400.67
  4870.5  400.55  4927.2  398.56  4934.6  397.31    4963  398.66  4991.4  397.48
  4998.1  398.42  5012.3  398.01  5090.1  399.99  5104.3  400.95  5132.5  404.78
  5160.8  403.21  5189.1  397.53  5215.2  396.85  5215.5  396.35  5219.6  396.85
  5259.8  403.89    5472  415.68  5486.1  417.65    5571  422.12  5585.1  423.57
#Mann= 4 ,-1 , 0
  4205.5     .07       0  4781.5     .12       0  5215.2     .05       0
  5219.6     .12       0
Bank Sta=5215.2,5219.6
XS Rating Curve= 0 ,0
Exp/Cntr=0.3,0.1

Type RM Length L Ch R = 1 ,18400   ,479,479,479
BEGIN DESCRIPTION:
StreamM045 29.0
END DESCRIPTION:
XS GIS Cut Line= 3
        2519675.       13840975.        2519525.       13840675.
        2519125.       13840275.
#Sta/Elev= 30
  4671.2  407.18  4738.3   404.8    4769  401.23  4774.6  401.77  4791.4  398.59
    4797  399.67  4813.7  395.67  4836.1  394.72  4850.1  394.96  4858.5  396.42
  4864.1  395.11  4880.8  396.87  4953.5   396.4  4970.3  392.82  4984.2  391.28
  4998.2  392.77  5003.8  390.01  5020.8  390.85  5032.6  389.92    5033  389.42
  5037.1  389.92  5054.3   394.7  5063.2  398.42  5105.6  397.96  5137.3  399.07
    5247  400.33  5368.1  403.94  5473.3  407.25  5487.4  408.71  5572.3  411.94
#Mann= 6 ,-1 , 0
  4671.2      .1       0  5032.6     .05       0  5037.1      .1       0
  5054.3     .12       0  5137.3      .1       0  5368.1     .12       0
Bank Sta=5032.6,5037.1
XS Rating Curve= 0 ,0
Exp/Cntr=0.3,0.1

Type RM Length L Ch R = 1 ,17921   ,452,452,452
BEGIN DESCRIPTION:
StreamM045 28.0
END DESCRIPTION:
XS GIS Cut Line= 3
        2520025.       13840725.        2519875.       13840575.
      2519074.96     13840174.98
#Sta/Elev= 30
  4787.5  407.43  4825.8  405.44  4971.3  395.99  4985.5  394.08  4996.1  390.51
  5005.8  389.55  5006.1  389.05  5010.3  389.55  5013.6  389.77    5022  393.19
  5030.4  394.37  5075.1  393.44  5080.7  392.55  5087.8  393.34  5125.4   393.5
  5170.1  396.56  5245.6  397.72    5268   399.1  5281.9  398.44  5393.2  400.65
  5522.3  402.64  5623.4  405.35  5729.1  409.25  5737.5  410.45  5773.9  410.83
  5796.2  413.12  5835.4  413.52  5849.3  414.02  5857.7  415.39  5894.1   416.5
#Mann= 7 ,-1 , 0
  4787.5     .07       0  4825.8      .1       0  5005.8     .05       0
  5010.3      .1       0  5087.8     .12       0  5393.2      .1       0
  5623.4     .12       0
Bank Sta=5005.8,5010.3
XS Rating Curve= 0 ,0
Exp/Cntr=0.3,0.1

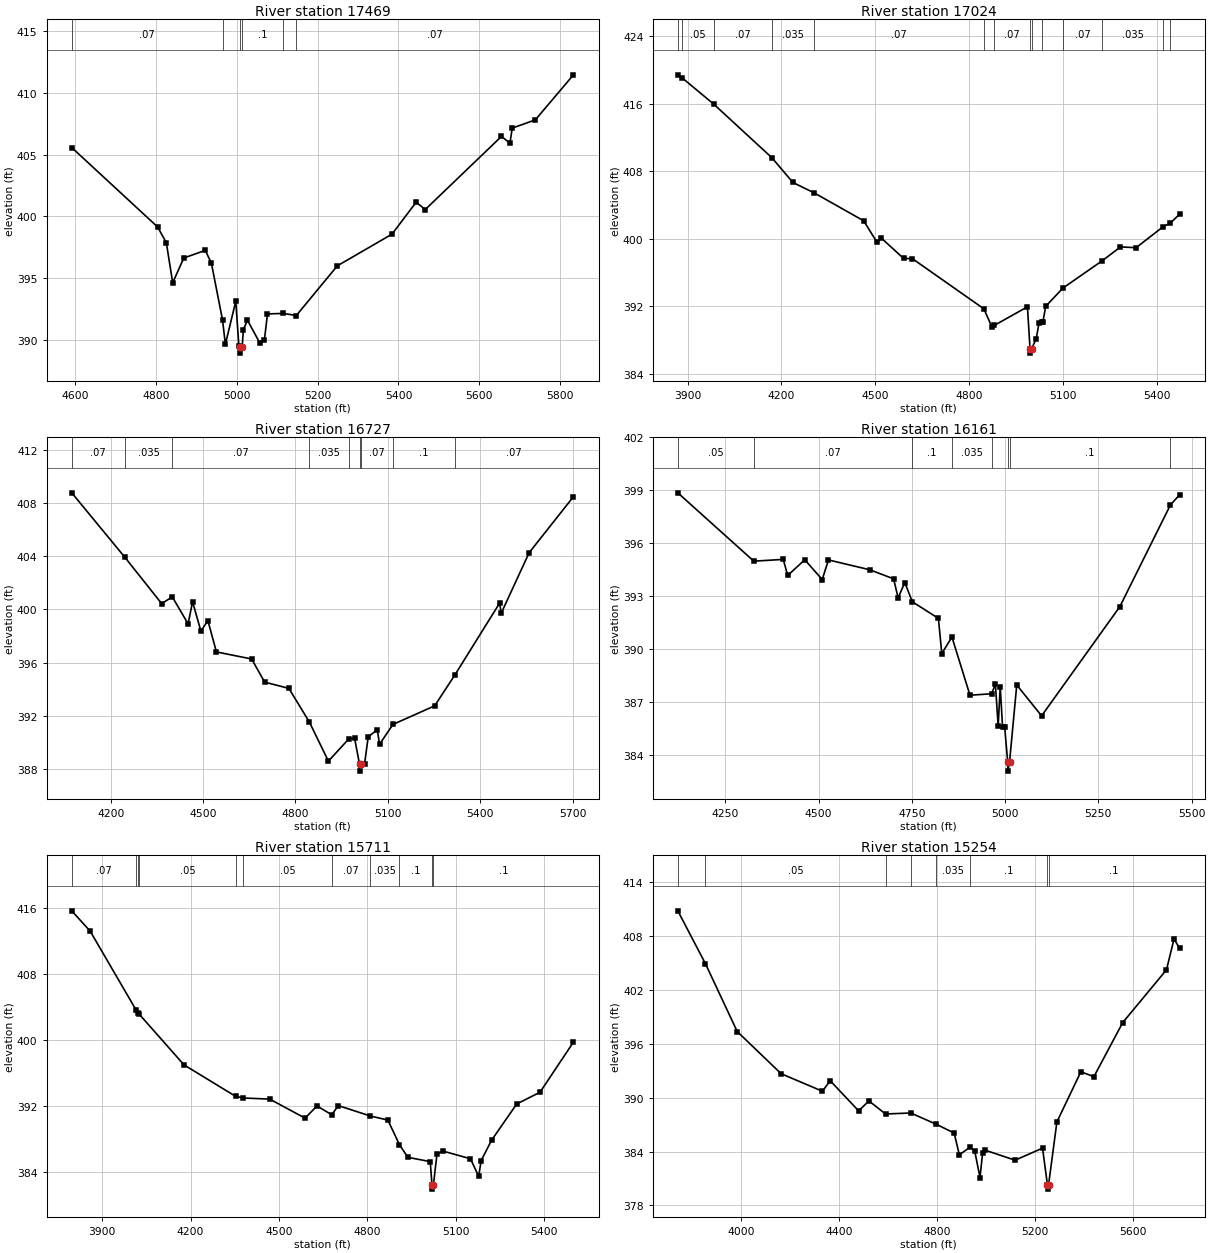
Type RM Length L Ch R = 1 ,17469   ,445,445,445
BEGIN DESCRIPTION:
StreamM045 27.0
END DESCRIPTION:
XS GIS Cut Line= 3
      2520425.03     13840425.01        2520075.       13840225.
        2519275.       13839975.
#Sta/Elev= 30
  4591.6  405.57    4804  399.15  4825.6  397.88  4841.4  394.64  4868.8  396.64
    4922  397.26  4937.2  396.21  4964.7  391.62  4971.7  389.66  4997.4  393.15
  5005.2  389.49  5008.7  389.45    5009  388.95  5013.3  389.45  5016.2  390.85
  5026.2  391.62  5057.6  389.73  5068.1  389.98  5075.9  392.12  5115.4  392.16
  5147.2  391.99  5248.8  396.01    5384  398.57  5443.7  401.15  5466.2  400.56
  5654.8  406.47  5675.7  405.93  5681.5  407.14  5738.6  407.81  5832.9  411.45
#Mann= 6 ,-1 , 0
  4591.6     .07       0  4964.7      .1       0  5008.7     .05       0
  5013.3      .1       0  5115.4     .12       0  5147.2     .07       0
Bank Sta=5008.7,5013.3
XS Rating Curve= 0 ,0
Exp/Cntr=0.3,0.1

Type RM Length L Ch R = 1 ,17024   ,297,297,297
BEGIN DESCRIPTION:
StreamM045 26.0
END DESCRIPTION:
XS GIS Cut Line= 3
      2520825.01     13840625.01        2520025.       13839825.
      2519624.99     13839574.99
#Sta/Elev= 30
    3869  419.42  3881.6   419.1  3983.5  415.96  4169.6  409.61  4236.7  406.68
  4305.1  405.44    4463  402.14  4505.4   399.6  4519.6  400.09  4590.3  397.69
  4618.6  397.66  4847.1  391.72  4873.1  389.54  4880.1  389.76  4986.2  391.96
  4994.5  386.98  4994.9  386.48  4999.2  386.98    5014  388.15  5023.4  390.09
  5031.5  390.22  5035.8  390.22  5044.6  392.02  5099.6  394.18  5225.9  397.43
  5283.4  399.05  5333.5  398.96  5420.3  401.46  5442.1  401.84  5472.1  402.92
#Mann= 14 ,-1 , 0
    3869    .035       0  3881.6     .05       0  3983.5     .07       0
  4169.6    .035       0  4305.1     .07       0  4847.1     .12       0
  4880.1     .07       0  4994.5     .05       0  4999.2     .07       0
  5031.5     .12       0  5099.6     .07       0  5225.9    .035       0
  5420.3     .07       0  5442.1    .035       0
Bank Sta=4994.5,4999.2
XS Rating Curve= 0 ,0
Exp/Cntr=0.3,0.1

Type RM Length L Ch R = 1 ,16727   ,566,566,566
BEGIN DESCRIPTION:
StreamM045 25.0
END DESCRIPTION:
XS GIS Cut Line= 3
      2520724.99     13840324.99      2520144.93     13839584.19
      2519474.96     13839424.99
#Sta/Elev= 30
  4073.4  408.76  4245.7  403.92  4365.5  400.43  4399.9  400.94  4451.3  398.91
  4465.8  400.57  4492.9  398.36  4515.5  399.16  4543.3   396.8  4657.6  396.27
    4700  394.53  4778.6  394.06  4845.4  391.52    4907  388.59  4973.1  390.26
    4992  390.32  5008.2  388.34  5008.6  387.84  5012.9  388.34  5024.5  388.38
  5036.2  390.41  5065.6  390.96  5073.2  389.86  5116.6  391.35  5252.2  392.75
  5317.8  395.07  5463.1  400.47  5468.3  399.71    5559  404.26  5702.9  408.47
#Mann= 9 ,-1 , 0
  4073.4     .07       0  4245.7    .035       0  4399.9     .07       0
  4845.4    .035       0  4973.1     .07       0  5008.2     .05       0
  5012.9     .07       0  5116.6      .1       0  5317.8     .07       0
Bank Sta=5008.2,5012.9
XS Rating Curve= 0 ,0
Exp/Cntr=0.3,0.1

Type RM Length L Ch R = 1 ,16161   ,450,450,450
BEGIN DESCRIPTION:
StreamM045 24.0
END DESCRIPTION:
XS GIS Cut Line= 3
      2520925.01     13839525.01        2520125.       13839175.
      2519725.02     13839424.99
#Sta/Elev= 30
  4122.6  398.86  4326.4  394.99  4405.2  395.09  4417.3  394.18  4462.9  395.07
  4509.7  393.95  4526.5  395.06  4637.6   394.5  4701.1  393.99  4713.2  392.91
  4731.1  393.78  4751.3  392.69  4821.2  391.75  4830.2  389.76  4857.5  390.69
  4905.8   387.4  4963.7  387.48    4974  388.02  4981.4  385.64  4986.9  387.89
  4993.1  385.61  4998.8  385.61    5007   383.6  5007.3   383.1  5011.8   383.6
  5031.2  387.98  5097.8  386.23  5307.7  392.42  5443.3  398.18  5467.5  398.74
#Mann= 8 ,-1 , 0
  4122.6     .05       0  4326.4     .07       0  4751.3      .1       0
  4857.5    .035       0  4963.7      .1       0    5007     .05       0
  5011.8      .1       0  5443.3     .07       0
Bank Sta=5007,5011.8
XS Rating Curve= 0 ,0
Exp/Cntr=0.3,0.1

Type RM Length L Ch R = 1 ,15711   ,457,457,457
BEGIN DESCRIPTION:
StreamM045 23.0
END DESCRIPTION:
XS GIS Cut Line= 3
      2521274.95       13838875.        2520075.       13838775.
      2519675.01     13839074.99
#Sta/Elev= 30
  3796.3  415.64    3859  413.17  4015.4   403.6  4021.7  403.29  4026.4  403.09
  4177.6  396.99  4352.6  393.19  4379.5  392.98  4468.6  392.85    4589  390.54
  4629.1  392.02  4679.4  390.95  4701.9  392.06  4810.7   390.8    4870  390.31
  4909.3  387.34  4937.7   385.8    5014  385.28  5019.9  382.45  5020.2  381.95
  5024.7  382.45  5036.9  386.23  5057.7  386.55  5150.4  385.63  5178.5   383.5
  5186.9   385.4  5222.3  387.87  5307.7  392.26  5386.9  393.68  5500.4  399.75
#Mann= 11 ,-1 , 0
  3796.3     .07       0  4015.4     .05       0  4021.7     .07       0
  4026.4     .05       0  4352.6    .035       0  4379.5     .05       0
  4679.4     .07       0  4810.7    .035       0  4909.3      .1       0
  5019.9     .05       0  5024.7      .1       0
Bank Sta=5019.9,5024.7
XS Rating Curve= 0 ,0
Exp/Cntr=0.3,0.1

Type RM Length L Ch R = 1 ,15254   ,428,428,428
BEGIN DESCRIPTION:
StreamM045 22.0
END DESCRIPTION:
XS GIS Cut Line= 3
      2521175.03     13838775.01        2519975.       13838375.
      2519274.97     13838725.01
#Sta/Elev= 30
  3740.8  410.78  3853.4  404.91  3983.3  397.35  4162.5  392.66  4331.1  390.71
  4362.7  391.88  4478.7  388.53  4520.9  389.63  4588.7  388.18  4691.6  388.29
  4794.5  387.05  4868.7  386.06  4889.8  383.63    4933  384.48    4953  384.01
  4974.1  381.11  4984.7  383.81  4995.2  384.15  5117.5  383.04  5229.4  384.38
  5249.3  380.32  5249.7  379.82  5254.1  380.32    5288   387.3  5385.9  392.88
    5439  392.33  5556.4  398.34  5735.3  404.22    5766  407.65  5788.4  406.63
#Mann= 8 ,-1 , 0
  3740.8     .07       0  3853.4     .05       0  4588.7     .07       0
  4691.6      .1       0  4794.5    .035       0    4933      .1       0
  5249.3     .05       0  5254.1      .1       0
Bank Sta=5249.3,5254.1
XS Rating Curve= 0 ,0
Exp/Cntr=0.3,0.1

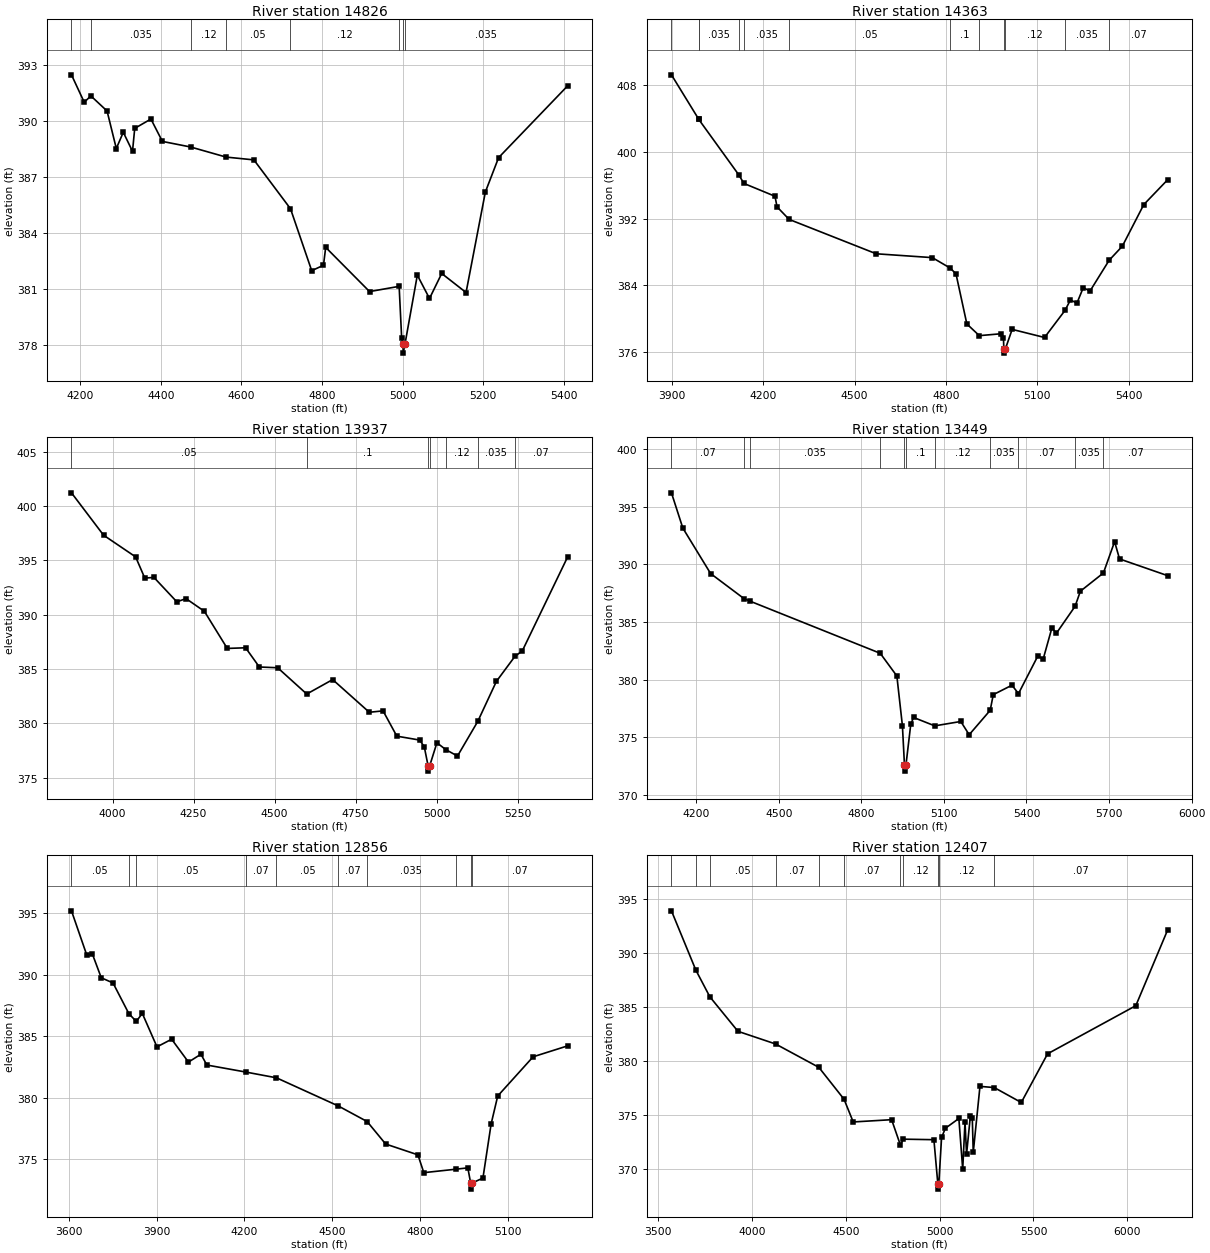
Type RM Length L Ch R = 1 ,14826   ,463,463,463
BEGIN DESCRIPTION:
StreamM045 21.0
END DESCRIPTION:
XS GIS Cut Line= 3
      2520825.03     13838375.01        2520075.       13838025.
      2519674.99       13837975.
#Sta/Elev= 30
  4178.6  392.49  4210.2  391.02  4226.7  391.36  4266.9  390.55  4289.8  388.54
  4307.1  389.41    4330  388.39  4335.5  389.62  4375.7  390.12  4404.1  388.92
  4474.3  388.62  4562.2  388.08  4631.1  387.93  4721.9  385.31  4774.5  381.99
  4803.7  382.28  4809.2  383.24    4918  380.87  4991.4  381.15  4997.6   378.4
  5001.1  378.07  5001.4  377.57    5006  378.07  5036.5  381.75  5066.7   380.5
    5097  381.84  5157.4  380.82  5205.3  386.21  5238.1  388.05  5409.4   391.9
#Mann= 8 ,-1 , 0
  4178.6     .05       0  4226.7    .035       0  4474.3     .12       0
  4562.2     .05       0  4721.9     .12       0  4991.4    .035       0
  5001.1    .035       0    5006    .035       0
Bank Sta=5001.1,5006
XS Rating Curve= 0 ,0
Exp/Cntr=0.3,0.1

Type RM Length L Ch R = 1 ,14363   ,426,426,426
BEGIN DESCRIPTION:
StreamM045 20.0
END DESCRIPTION:
XS GIS Cut Line= 3
      2521224.98     13838524.98        2520425.       13837775.
      2520074.97     13837374.97
#Sta/Elev= 30
  3899.2  409.19  3988.5  403.89  3988.8  403.86  4119.9  397.24  4137.1   396.2
  4238.9  394.67  4245.7   393.4  4285.4   391.9  4571.1  387.79  4755.2  387.33
  4814.3  386.07  4832.9  385.38  4868.5   379.4  4909.3     378  4981.8  378.23
  4988.7  377.69  4989.8  376.41  4990.2  375.91  4994.9  376.41  5017.1  378.75
  5123.4  377.78  5190.4  381.01  5208.4  382.27  5229.7  381.89  5250.6  383.75
  5272.4  383.32  5335.3  387.01  5378.7   388.7    5449  393.67  5527.3  396.64
#Mann= 12 ,-1 , 0
  3899.2     .07       0  3988.5     .05       0  3988.8    .035       0
  4119.9     .05       0  4137.1    .035       0  4285.4     .05       0
  4814.3      .1       0  4909.3     .12       0  4989.8     .05       0
  4994.9     .12       0  5190.4    .035       0  5335.3     .07       0
Bank Sta=4989.8,4994.9
XS Rating Curve= 0 ,0
Exp/Cntr=0.3,0.1

Type RM Length L Ch R = 1 ,13937   ,488,488,488
BEGIN DESCRIPTION:
StreamM045 19.0
END DESCRIPTION:
XS GIS Cut Line= 3
      2521324.98     13838174.98        2520525.       13837375.
      2520125.04       13837375.
#Sta/Elev= 30
  3873.3  401.23  3972.3  397.33  4071.3  395.33  4099.5  393.38  4127.8  393.44
  4198.5  391.19  4226.8  391.49  4283.4  390.32  4354.1   386.9  4410.7  386.96
  4453.1  385.19  4509.7  385.12  4599.4   382.7  4679.4  384.03  4792.5  381.02
  4834.9  381.15  4877.4  378.82  4948.1  378.46  4962.2  377.83  4973.8   376.1
  4974.2   375.6  4978.9   376.1  5001.1  378.21  5028.6  377.58  5064.6  376.99
  5127.2  380.18  5184.6  383.86  5241.9  386.17  5264.6  386.67  5404.6  395.33
#Mann= 7 ,-1 , 0
  3873.3     .05       0  4599.4      .1       0  4973.8     .05       0
  4978.9      .1       0  5028.6     .12       0  5127.2    .035       0
  5241.9     .07       0
Bank Sta=4973.8,4978.9
XS Rating Curve= 0 ,0
Exp/Cntr=0.3,0.1

Type RM Length L Ch R = 1 ,13449   ,593,593,593
BEGIN DESCRIPTION:
H21334
END DESCRIPTION:
XS GIS Cut Line= 3
      2521655.94     13837131.54       2520595.2     13836984.66
      2519889.01     13837174.79
#Sta/Elev= 30
  4110.5  396.21  4151.8  393.15  4252.8   389.2  4373.8  387.03  4397.5  386.79
  4868.8  382.28  4929.2  380.31  4949.4  375.99  4956.9  372.55  4957.3  372.05
  4962.1  372.55  4979.7  376.11  4989.8  376.71  5066.9  375.98  5161.4  376.36
  5191.9  375.21  5268.2  377.33  5279.4  378.69  5347.3  379.51    5371  378.78
  5440.5  382.01  5461.2  381.82  5492.3  384.48  5508.7  384.02  5576.6  386.36
  5595.8  387.67  5679.4  389.25  5720.1  391.97    5738  390.47  5912.7  389.02
#Mann= 11 ,-1 , 0
  4110.5     .07       0  4373.8     .05       0  4397.5    .035       0
  4868.8      .1       0  4956.9     .05       0  4962.1      .1       0
  5066.9     .12       0  5268.2    .035       0    5371     .07       0
  5576.6    .035       0  5679.4     .07       0
Bank Sta=4956.9,4962.1
XS Rating Curve= 0 ,0
Exp/Cntr=0.3,0.1

Type RM Length L Ch R = 1 ,12856   ,449,449,449
BEGIN DESCRIPTION:
H21333
END DESCRIPTION:
XS GIS Cut Line= 3
      2521726.64     13836712.68      2520475.52     13836641.96
       2520079.2     13836837.41
#Sta/Elev= 30
  3609.3   395.2  3661.4  391.61  3681.1  391.66  3711.1  389.75  3751.2  389.33
  3805.4  386.83  3830.6   386.2  3851.3  386.85  3901.4  384.13  3951.5  384.75
  4008.9  382.89  4051.6  383.53  4071.7  382.65  4204.5  382.08  4309.5  381.61
  4520.7  379.32  4619.3  378.05  4682.6  376.22  4792.8  375.34  4812.9  373.89
  4921.7  374.17  4963.3  374.28  4972.9  373.05  4973.3  372.55  4978.1  373.05
  5014.9  373.45  5042.9  377.86  5065.4  380.13  5186.3  383.32  5304.3  384.21
#Mann= 10 ,-1 , 0
  3609.3     .05       0  3805.4     .07       0  3830.6     .05       0
  4204.5     .07       0  4309.5     .05       0  4520.7     .07       0
  4619.3    .035       0  4921.7     .07       0  4972.9     .05       0
  4978.1     .07       0
Bank Sta=4972.9,4978.1
XS Rating Curve= 0 ,0
Exp/Cntr=0.3,0.1

Type RM Length L Ch R = 1 ,12407   ,573,573,573
BEGIN DESCRIPTION:
H21332
END DESCRIPTION:
XS GIS Cut Line= 3
      2521721.19     13836641.96      2520121.95     13836293.83
      2519115.61     13836266.63
#Sta/Elev= 30
  3571.3  393.89  3701.2  388.41  3775.9  385.94  3925.6  382.75    4126  381.58
  4356.5  379.42  4490.8  376.47  4539.6  374.37  4744.3  374.58  4791.5  372.21
  4806.1  372.78  4969.5  372.73  4990.4  368.66  4990.8  368.16  4995.6  368.66
  5010.4  372.94  5030.9  373.79  5102.5  374.69    5123     370  5135.2  374.37
  5143.5  371.39  5163.9  374.94    5174  374.73  5179.1  371.55  5214.9  377.66
    5291  377.55    5435  376.17  5575.1  380.67  6045.2  385.12  6214.7  392.12
#Mann= 11 ,-1 , 0
  3571.3     .05       0  3701.2     .07       0  3775.9     .05       0
    4126     .07       0  4356.5     .05       0  4490.8     .07       0
  4791.5    .035       0  4806.1     .12       0  4990.4     .05       0
  4995.6     .12       0    5291     .07       0
Bank Sta=4990.4,4995.6
XS Rating Curve= 0 ,0
Exp/Cntr=0.3,0.1

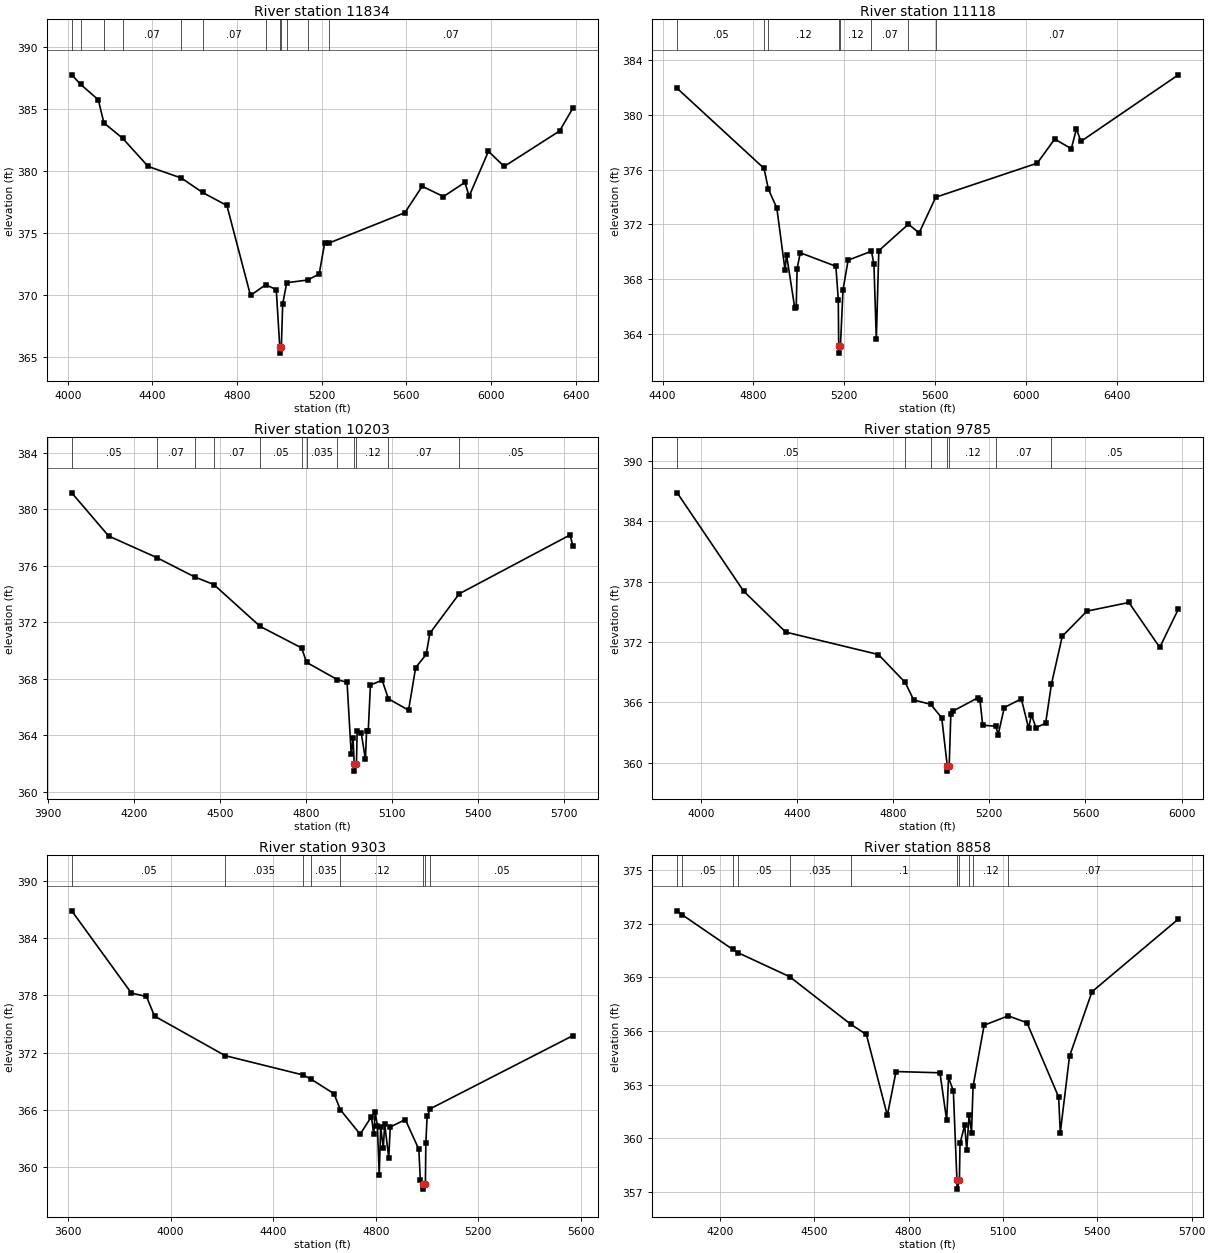
Type RM Length L Ch R = 1 ,11834   ,716,716,716
BEGIN DESCRIPTION:
H21331
END DESCRIPTION:
XS GIS Cut Line= 3
      2521737.52     13836190.47       2520622.4     13836000.08
      2519400.75     13836190.12
#Sta/Elev= 30
  4018.9  387.79  4060.9  387.02  4144.4  385.78  4170.9  383.91    4259  382.68
  4379.9   380.4  4537.4  379.46  4636.9   378.3  4751.9  377.25  4863.5  369.99
  4935.3  370.86  4985.2  370.46  5001.7  365.84  5002.2  365.34  5009.2  365.84
  5015.6  369.32  5034.7  371.02  5134.2  371.24    5188  371.72    5214  374.24
  5234.2  374.22  5592.8  376.67  5674.5   378.8    5775  377.97  5876.2  379.11
  5896.4     378  5987.5  381.62  6061.9   380.4  6323.6  383.26  6386.5   385.1
#Mann= 12 ,-1 , 0
  4018.9     .05       0  4060.9     .07       0  4170.9     .05       0
    4259     .07       0  4537.4     .05       0  4636.9     .07       0
  4935.3     .12       0  5001.7     .05       0  5009.2     .12       0
  5034.7      .1       0  5134.2    .035       0  5234.2     .07       0
Bank Sta=5001.7,5009.2
XS Rating Curve= 0 ,0
Exp/Cntr=0.3,0.1

Type RM Length L Ch R = 1 ,11118   ,915,915,915
BEGIN DESCRIPTION:
StreamM045 16.0
END DESCRIPTION:
XS GIS Cut Line= 3
      2521524.98     13835974.98        2521125.       13835625.
      2519524.99       13836125.
#Sta/Elev= 30
    4464  381.95  4846.5   376.1  4865.7  374.58  4902.9   373.2    4939  368.67
  4945.7  369.78  4981.7  365.92  4988.4  365.93  4992.2  368.74    5006  369.93
  5163.1  368.94  5173.6  366.51  5175.5  363.09    5176  362.59  5183.1  363.09
  5194.5  367.23  5217.1  369.39  5319.9  370.04  5330.7  369.09  5341.2  363.59
  5352.2  370.08  5482.7  372.02  5529.8  371.38    5603  373.99    6050  376.48
    6127  378.24  6200.3  377.54  6222.9  378.99  6242.2  378.07  6671.8  382.94
#Mann= 8 ,-1 , 0
    4464     .05       0  4846.5     .07       0  4865.7     .12       0
  5175.5     .05       0  5183.1     .12       0  5319.9     .07       0
  5482.7    .035       0    5603     .07       0
Bank Sta=5175.5,5183.1
XS Rating Curve= 0 ,0
Exp/Cntr=0.3,0.1

Type RM Length L Ch R = 1 ,10203   ,418,418,418
BEGIN DESCRIPTION:
StreamM045 15.0
END DESCRIPTION:
XS GIS Cut Line= 3
      2521574.98     13835824.98        2520775.       13835175.
      2520075.04     13835324.99
#Sta/Elev= 30
  3983.1  381.18  4111.7  378.12  4279.2  376.59  4412.3  375.21  4478.2  374.68
  4639.8  371.71  4784.6  370.18  4801.4  369.16  4908.7  367.94  4942.7  367.74
  4957.1  362.67  4963.5  363.79  4967.6  361.95  4968.1  361.45  4975.4  361.95
  4977.9  364.28  4992.3  364.12  5006.7  362.28  5010.6  364.26  5016.4  364.26
  5024.1  367.56    5065  367.89  5086.7  366.58    5157  365.77  5181.7  368.79
  5218.4  369.72  5231.2  371.22  5333.4  374.02  5719.5  378.19  5729.7  377.44
#Mann= 12 ,-1 , 0
  3983.1     .05       0  4279.2     .07       0  4412.3     .12       0
  4478.2     .07       0  4639.8     .05       0  4784.6     .12       0
  4801.4    .035       0  4908.7     .12       0  4967.6     .05       0
  4975.4     .12       0  5086.7     .07       0  5333.4     .05       0
Bank Sta=4967.6,4975.4
XS Rating Curve= 0 ,0
Exp/Cntr=0.3,0.1

Type RM Length L Ch R = 1 ,9785    ,482,482,482
BEGIN DESCRIPTION:
StreamM045 14.0
END DESCRIPTION:
XS GIS Cut Line= 3
      2521933.32     13835309.23        2520925.       13834875.
      2519948.98     13835020.78
#Sta/Elev= 30
  3901.8  386.85  4177.8  377.08  4353.4  372.99    4739  370.76  4850.2  367.98
  4885.6  366.24  4956.1  365.81  5002.2  364.47  5025.3  359.66  5025.8  359.16
  5033.2  359.66  5040.1  364.84  5050.2  365.15  5151.3  366.44  5161.4  366.19
  5172.7  363.73  5227.3  363.63  5236.9  362.78  5262.5  365.49  5333.3  366.35
  5363.6  363.43  5375.4  364.76    5394  363.49  5434.4  363.92  5458.7  367.84
  5503.8  372.59  5606.3  375.08  5780.7  375.94  5909.1  371.47  5986.5  375.28
#Mann= 7 ,-1 , 0
  3901.8     .05       0  4850.2    .035       0  4956.1     .12       0
  5025.3     .05       0  5033.2     .12       0  5227.3     .07       0
  5458.7     .05       0
Bank Sta=5025.3,5033.2
XS Rating Curve= 0 ,0
Exp/Cntr=0.3,0.1

Type RM Length L Ch R = 1 ,9303    ,445,445,445
BEGIN DESCRIPTION:
StreamM045 13.0
END DESCRIPTION:
XS GIS Cut Line= 3
      2521975.03     13835175.02        2520775.       13834475.
      2520374.97     13834875.03
#Sta/Elev= 30
  3614.1  386.86  3846.9  378.23  3905.6  377.88    3937  375.82  4212.6  371.67
    4517  369.64  4549.2  369.18  4637.5  367.67  4661.4  366.02  4739.2  363.43
  4783.4  365.28  4792.1  363.41  4797.9  365.75  4806.6   364.3  4813.6  359.19
  4819.4  364.17  4829.3     362  4835.1  364.46  4850.8  360.96  4856.6  364.18
  4915.3  364.97  4968.2  361.84    4974  358.58  4985.8  358.17  4986.3  357.67
  4993.7  358.17  4995.5  362.53  5000.5  365.33  5013.6  366.11  5569.1  373.77
#Mann= 8 ,-1 , 0
  3614.1     .05       0  4212.6    .035       0    4517     .05       0
  4549.2    .035       0  4661.4     .12       0  4985.8     .05       0
  4993.7     .12       0  5013.6     .05       0
Bank Sta=4985.8,4993.7
XS Rating Curve= 0 ,0
Exp/Cntr=0.3,0.1

Type RM Length L Ch R = 1 ,8858    ,430,430,430
BEGIN DESCRIPTION:
StreamM045 12.0
END DESCRIPTION:
XS GIS Cut Line= 3
      2521675.04     13834625.03        2520875.       13834125.
      2520275.04     13833875.02
#Sta/Elev= 30
  4064.4  372.71  4079.4   372.5  4241.3  370.55  4256.5  370.38  4421.9  369.03
  4616.3  366.37  4665.9   365.8  4732.5  361.28  4760.2  363.73  4899.9  363.66
  4921.2     361  4927.1   363.4  4942.4  362.64  4953.8  357.66  4954.3  357.16
  4961.7  357.66  4963.6  359.72  4978.4  360.73  4984.9  359.35  4992.7  361.31
  5000.2  360.32  5005.1   362.9  5040.3  366.32  5116.8  366.84  5176.3  366.46
  5277.1  362.31  5282.5  360.32  5311.7  364.58  5383.2  368.19  5657.8  372.25
#Mann= 11 ,-1 , 0
  4064.4    .035       0  4079.4     .05       0  4241.3    .035       0
  4256.5     .05       0  4421.9    .035       0  4616.3      .1       0
  4953.8     .05       0  4961.7      .1       0  4992.7     .07       0
  5005.1     .12       0  5116.8     .07       0
Bank Sta=4953.8,4961.7
XS Rating Curve= 0 ,0
Exp/Cntr=0.3,0.1