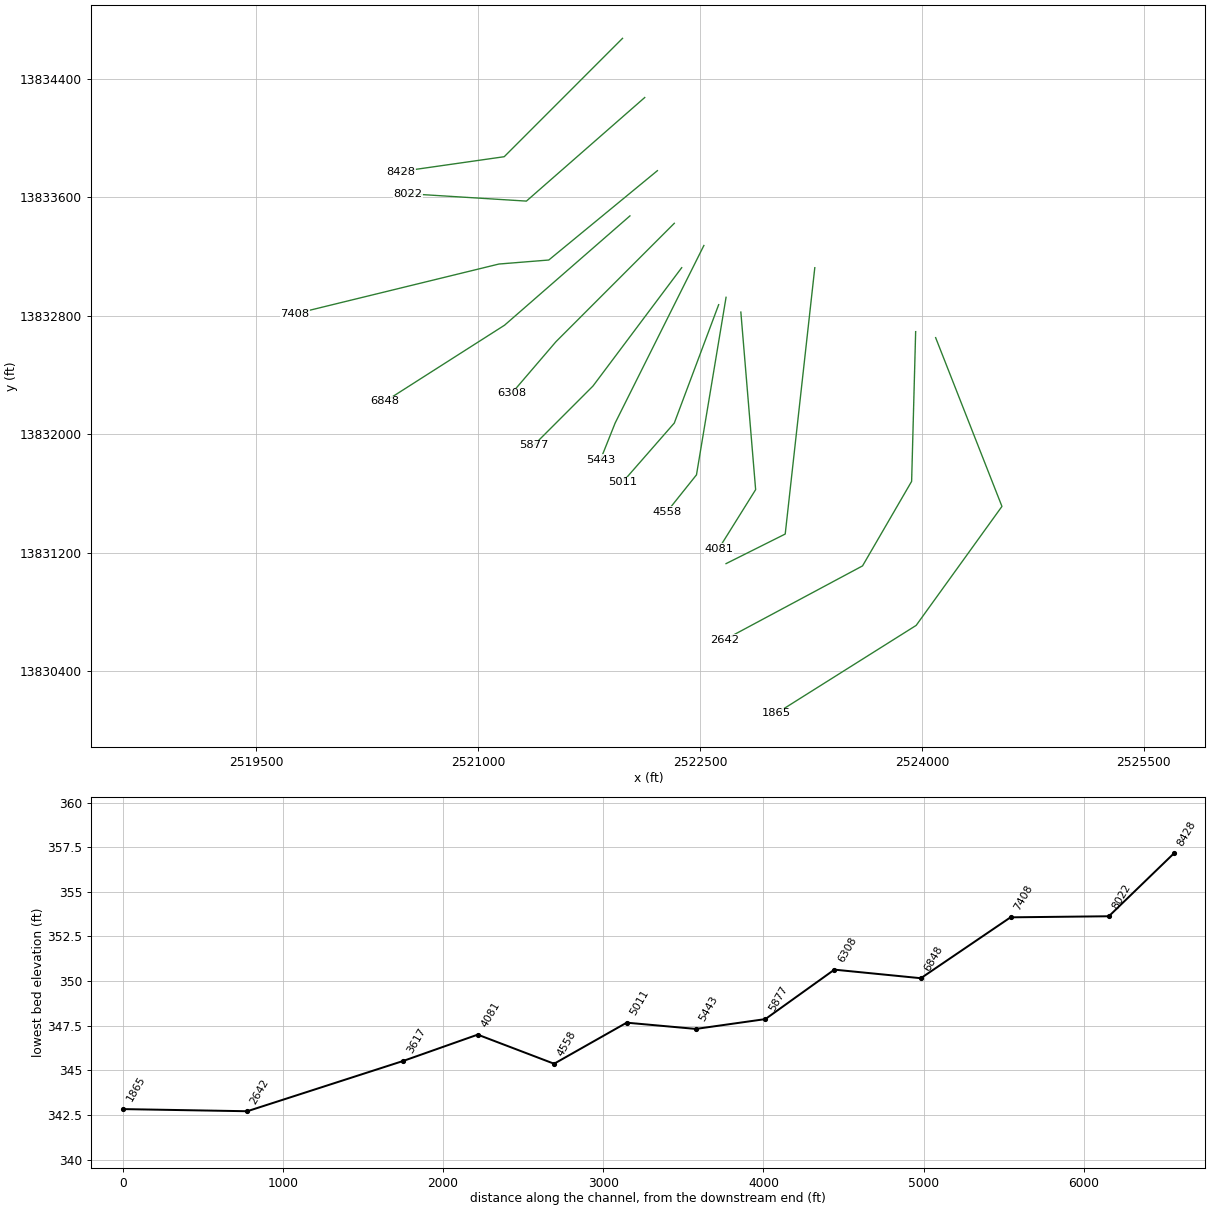
HEC-RAS study StreamM045.prj: StreamM045 Base Level Engineering

--- StreamM045.g01 (geometry) --- (continued)

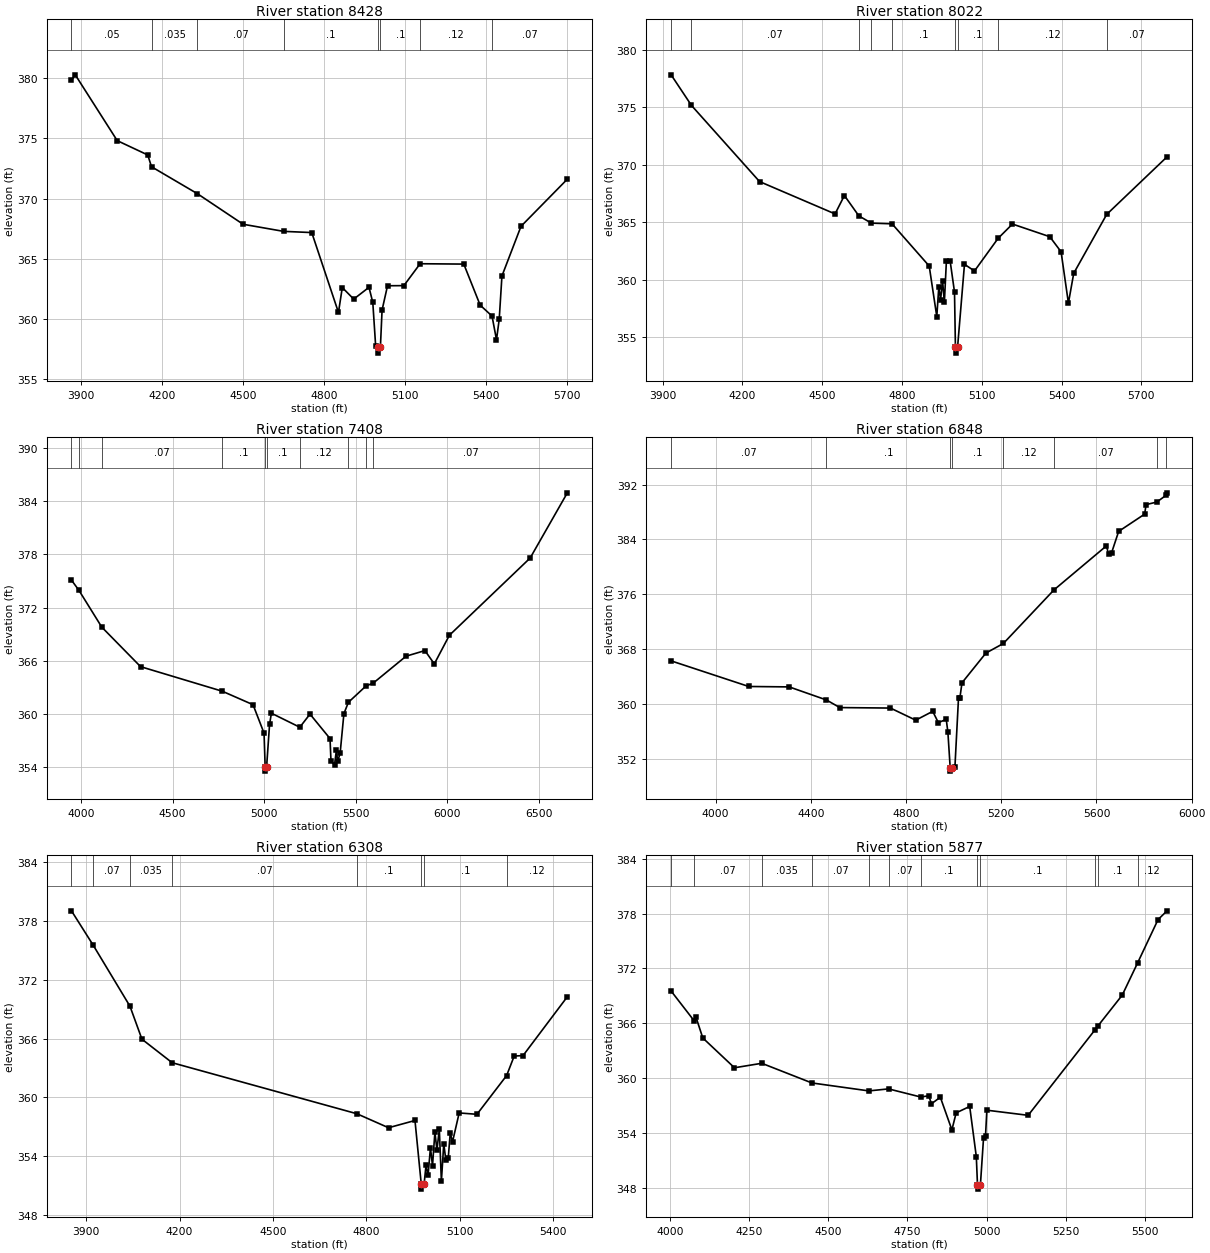
Type RM Length L Ch R = 1 ,8428    ,406,406,406
BEGIN DESCRIPTION:
StreamM045 11.0
END DESCRIPTION:
XS GIS Cut Line= 3
      2521974.99     13834674.99        2521175.       13833875.
      2520474.96     13833774.99
#Sta/Elev= 30
  3864.2  379.84  3878.3  380.28  4033.9  374.81    4147  373.62    4161  372.64
  4331.1   370.4  4500.6  367.86  4650.6  367.27  4755.1  367.17  4854.1  360.53
  4868.3   362.6  4910.7  361.64  4967.3  362.62  4981.4  361.36    4992  357.74
  5001.7  357.65  5002.2  357.15  5009.6  357.65  5015.8  360.73    5036  362.75
  5096.6  362.76  5156.9  364.58  5318.8  364.55  5379.4  361.14  5423.5  360.23
    5440  358.26  5450.1  359.96  5460.2  363.56  5530.9  367.69  5702.7  371.61
#Mann= 8 ,-1 , 0
  3864.2     .05       0    4161    .035       0  4331.1     .07       0
  4650.6      .1       0  5001.7     .05       0  5009.6      .1       0
  5156.9     .12       0  5423.5     .07       0
Bank Sta=5001.7,5009.6
XS Rating Curve= 0 ,0
Exp/Cntr=0.3,0.1

Type RM Length L Ch R = 1 ,8022    ,614,614,614
BEGIN DESCRIPTION:
StreamM045 10.0
END DESCRIPTION:
XS GIS Cut Line= 3
      2522124.96     13834274.97        2521325.       13833575.
      2520525.03       13833625.
#Sta/Elev= 30
  3932.1  377.82  4008.6  375.16  4264.7  368.54  4548.5  365.73  4583.6  367.33
  4637.9  365.56  4685.1  364.93  4762.8  364.87  4902.5   361.2    4931  356.81
  4938.6  359.39  4945.2  358.28  4952.8   359.9  4959.5  358.04  4967.1  361.61
  4981.3  361.62  4997.6  358.94  5001.1  354.13  5001.6  353.63  5009.1  354.13
  5035.1  361.35  5072.7  360.77  5161.6  363.61  5215.5  364.85  5355.8  363.75
  5398.3  362.44  5425.9  357.98  5445.9  360.57  5569.9  365.69  5796.6  370.69
#Mann= 9 ,-1 , 0
  3932.1    .035       0  4008.6     .07       0  4637.9      .1       0
  4685.1     .07       0  4762.8      .1       0  5001.1     .05       0
  5009.1      .1       0  5161.6     .12       0  5569.9     .07       0
Bank Sta=5001.1,5009.1
XS Rating Curve= 0 ,0
Exp/Cntr=0.3,0.1

Type RM Length L Ch R = 1 ,7408    ,560,560,560
BEGIN DESCRIPTION:
H21330
END DESCRIPTION:
XS GIS Cut Line= 4
      2522210.78      13833780.7      2521476.42      13833176.9
      2521139.16      13833149.7      2519758.76     13832812.75
#Sta/Elev= 30
  3947.6  375.11  3988.6  373.95  4113.2  369.81  4325.3  365.35  4771.8  362.58
  4939.9  361.06  5000.1  357.85  5006.1  354.07  5006.6  353.57  5014.1  354.07
  5030.2  358.83  5040.2   360.1  5195.5  358.52  5251.2     360  5360.6  357.24
  5365.8  354.75  5385.1  354.25  5395.4  355.92  5402.3  354.67  5415.9  355.59
  5436.5  360.05  5461.1  361.33  5557.1  363.17  5597.1   363.5  5776.2  366.53
  5879.2  367.16  5930.6  365.66    6013  368.89  6454.4   377.6  6657.6  384.95
#Mann= 10 ,-1 , 0
  3947.6     .07       0  3988.6    .035       0  4113.2     .07       0
  4771.8      .1       0  5006.1     .05       0  5014.1      .1       0
  5195.5     .12       0  5461.1     .07       0  5557.1     .12       0
  5597.1     .07       0
Bank Sta=5006.1,5014.1
XS Rating Curve= 0 ,0
Exp/Cntr=0.3,0.1

Type RM Length L Ch R = 1 ,6848    ,540,540,540
BEGIN DESCRIPTION:
StreamM045 9.0
END DESCRIPTION:
XS GIS Cut Line= 3
      2522025.02     13833475.02      2521177.24     13832736.29
      2520368.77     13832220.82
#Sta/Elev= 30
  3813.1  366.26  4139.2  362.52  4309.2  362.46  4465.7  360.55  4521.8  359.44
  4734.5  359.37  4840.8   357.6  4912.1  358.89  4935.8  357.24  4968.9  357.72
  4975.8  355.87  4985.5  350.66    4986  350.16  4994.6  350.66  5005.3   350.7
  5020.5  360.85  5026.4  360.89  5035.1  363.06  5135.6   367.4  5208.9   368.8
  5421.4  376.62  5641.7  383.05    5651  381.86  5663.7  382.06  5693.3  385.17
  5802.5  387.69  5808.4  389.08  5853.4  389.45  5891.7  390.42  5896.4   390.8
#Mann= 8 ,-1 , 0
  3813.1     .07       0  4465.7      .1       0  4985.5     .05       0
  4994.6      .1       0  5208.9     .12       0  5421.4     .07       0
  5853.4     .12       0  5891.7     .07       0
Bank Sta=4985.5,4994.6
XS Rating Curve= 0 ,0
Exp/Cntr=0.3,0.1

Type RM Length L Ch R = 1 ,6308    ,431,431,431
BEGIN DESCRIPTION:
StreamM045 8.0
END DESCRIPTION:
XS GIS Cut Line= 3
      2522325.01     13833425.01        2521525.       13832625.
      2521224.97     13832274.97
#Sta/Elev= 30
  3852.8  379.02  3922.9   375.5  4040.7  369.29  4079.1  365.93  4176.2  363.53
  4769.1  358.33    4871   356.9  4955.9  357.64  4976.1  351.14  4976.6  350.64
  4985.2  351.14  4991.3  353.06  4997.9  352.04  5005.6  354.86  5012.2  353.03
  5019.9  356.47  5026.4  354.62  5034.1  356.76  5040.7  351.45  5048.4  355.29
    5055  353.59  5062.7   353.8  5069.2  356.38  5076.4  355.45  5097.8  358.41
  5154.9  358.27  5250.2  362.22  5274.5  364.21    5303  364.26  5445.2  370.26
#Mann= 8 ,-1 , 0
  3852.8     .12       0  3922.9     .07       0  4040.7    .035       0
  4176.2     .07       0  4769.1      .1       0  4976.1     .05       0
  4985.2      .1       0  5250.2     .12       0
Bank Sta=4976.1,4985.2
XS Rating Curve= 0 ,0
Exp/Cntr=0.3,0.1

Type RM Length L Ch R = 1 ,5877    ,434,434,434
BEGIN DESCRIPTION:
StreamM045 7.0
END DESCRIPTION:
XS GIS Cut Line= 3
      2522375.02     13833125.03        2521775.       13832325.
      2521375.02     13831925.02
#Sta/Elev= 30
  4003.9  369.53  4076.3  366.29  4082.1   366.7  4103.9   364.4  4203.9  361.14
  4290.1  361.63  4448.3  359.48  4628.3  358.61  4690.3  358.83  4792.3  357.94
  4817.5  358.08  4825.8   357.2  4853.9  357.92  4890.4  354.35  4903.9  356.21
  4946.6  356.91  4967.5  351.43  4971.2  348.37  4971.7  347.87  4980.5  348.37
  4990.4  353.49  4996.6  353.71  5000.8   356.5  5131.2  355.94  5341.2  365.24
  5352.6  365.76  5428.2  369.08  5476.7   372.6  5541.3  377.34  5569.6   378.3
#Mann= 12 ,-1 , 0
  4003.9     .12       0  4076.3     .07       0  4290.1    .035       0
  4448.3     .07       0  4628.3     .12       0  4690.3     .07       0
  4792.3      .1       0  4971.2     .05       0  4980.5      .1       0
  5341.2     .07       0  5352.6      .1       0  5476.7     .12       0
Bank Sta=4971.2,4980.5
XS Rating Curve= 0 ,0
Exp/Cntr=0.3,0.1

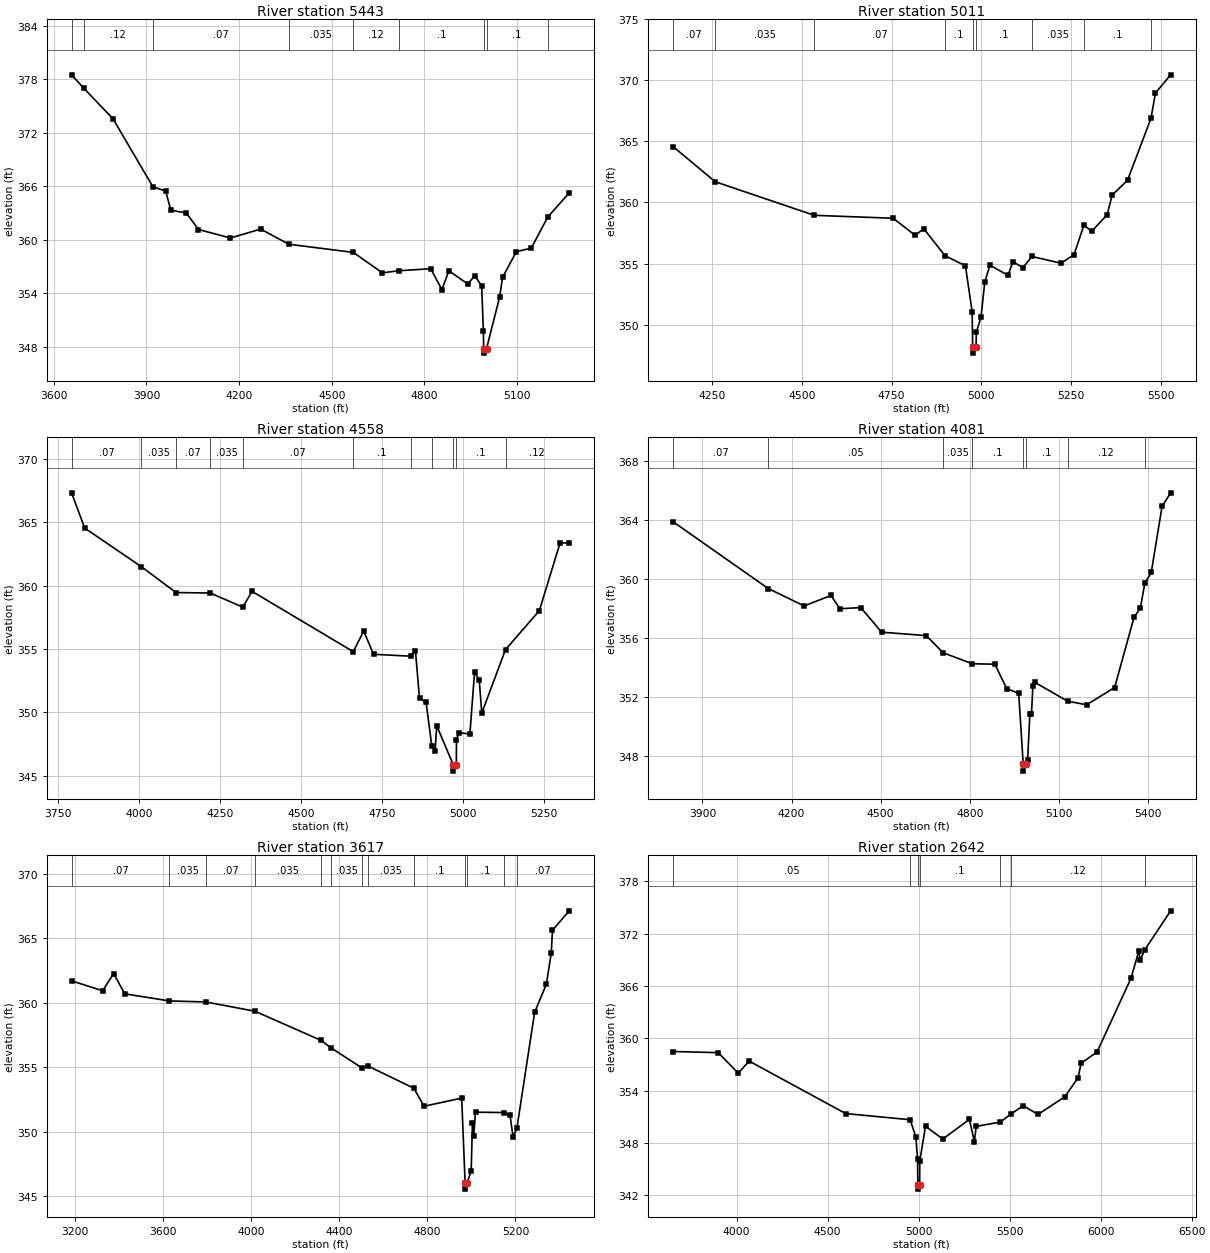
Type RM Length L Ch R = 1 ,5443    ,432,432,432
BEGIN DESCRIPTION:
StreamM045 6.0
END DESCRIPTION:
XS GIS Cut Line= 3
      2522525.01     13833275.01        2521925.       13832075.
      2521825.01     13831825.01
#Sta/Elev= 30
  3657.7  378.48  3696.9  376.99  3791.9  373.56  3921.1  365.94  3962.4  365.47
  3979.2  363.32  4029.5  363.01  4068.6  361.16    4172  360.21  4269.8  361.21
  4361.3  359.51  4569.8   358.6  4663.9  356.31  4719.2  356.55  4820.5  356.77
  4856.8  354.43  4879.2  356.54  4940.7  355.06    4963     356  4985.4  354.85
    4991  349.79  4991.9  347.82  4992.4  347.32  5001.2  347.82  5043.8  353.63
  5053.2  355.81  5097.6  358.67  5146.1  359.08  5199.7  362.57  5268.6  365.25
#Mann= 9 ,-1 , 0
  3657.7    .035       0  3696.9     .12       0  3921.1     .07       0
  4361.3    .035       0  4569.8     .12       0  4719.2      .1       0
  4991.9     .05       0  5001.2      .1       0  5199.7     .12       0
Bank Sta=4991.9,5001.2
XS Rating Curve= 0 ,0
Exp/Cntr=0.3,0.1

Type RM Length L Ch R = 1 ,5011    ,453,453,453
BEGIN DESCRIPTION:
StreamM045 5.0
END DESCRIPTION:
XS GIS Cut Line= 3
      2522624.99     13832874.96        2522325.       13832075.
      2521974.98     13831674.98
#Sta/Elev= 30
  4141.6  364.58  4258.9   361.7  4534.8  358.95  4754.8  358.71  4815.3  357.32
  4840.2  357.84  4899.2  355.64  4955.9  354.82  4974.6  351.06  4976.1  348.17
  4976.6  347.67  4985.5  348.17  4986.2  349.39  4999.3  350.61  5009.7  353.47
    5024  354.87  5074.3  354.04  5088.5  355.15    5116  354.66    5141  355.58
  5222.3  355.03  5258.4  355.73  5285.9  358.15  5307.7  357.64  5350.5     359
  5364.7  360.61  5407.4  361.82  5472.7  366.89  5485.2  368.96  5527.5  370.45
#Mann= 9 ,-1 , 0
  4141.6     .07       0  4258.9    .035       0  4534.8     .07       0
  4899.2      .1       0  4976.1     .05       0  4985.5      .1       0
    5141    .035       0  5285.9      .1       0  5472.7     .12       0
Bank Sta=4976.1,4985.5
XS Rating Curve= 0 ,0
Exp/Cntr=0.3,0.1

Type RM Length L Ch R = 1 ,4558    ,477,477,477
BEGIN DESCRIPTION:
StreamM045 4.0
END DESCRIPTION:
XS GIS Cut Line= 3
        2522675.       13832925.        2522475.       13831725.
      2522275.01     13831475.01
#Sta/Elev= 30
  3791.9  367.31  3832.5  364.53  4007.9  361.48  4114.5  359.45  4220.4  359.41
  4320.6   358.3  4349.5  359.54  4661.9  354.79  4694.2  356.41  4724.6  354.58
  4840.7  354.43  4853.9  354.86  4866.5  351.11  4886.8   350.8  4904.3  347.39
  4914.7  346.96  4919.8  348.94  4970.8  345.87  4971.3  345.37  4980.3  345.87
  4980.6  347.84  4988.2  348.41  5022.1  348.29  5036.5  353.17  5050.9  352.57
  5058.9  349.95  5132.1  354.95  5236.6  358.02  5300.6  363.36  5328.6  363.36
#Mann= 11 ,-1 , 0
  3791.9     .07       0  4007.9    .035       0  4114.5     .07       0
  4220.4    .035       0  4320.6     .07       0  4661.9      .1       0
  4840.7     .12       0  4904.3      .1       0  4970.8     .05       0
  4980.3      .1       0  5132.1     .12       0
Bank Sta=4970.8,4980.3
XS Rating Curve= 0 ,0
Exp/Cntr=0.3,0.1

Type RM Length L Ch R = 1 ,4081    ,464,464,464
BEGIN DESCRIPTION:
StreamM045 3.0
END DESCRIPTION:
XS GIS Cut Line= 3
        2522775.     13832824.96        2522875.       13831625.
      2522625.01     13831225.02
#Sta/Elev= 30
  3800.9  363.91  4121.5  359.38  4242.4   358.2  4332.7  358.91  4362.8  358.01
    4433  358.09  4503.3  356.42  4653.8  356.19  4710.1  355.03  4808.6  354.28
  4884.6  354.25  4924.7  352.59  4964.9  352.28  4980.1   347.5  4980.6     347
  4989.8   347.5    4995  347.75  5002.5  350.86    5008  350.86  5012.7   352.8
  5018.6  353.03  5129.7  351.74  5193.7   351.5    5288  352.67  5353.5  357.44
  5374.7  358.05  5389.5  359.73  5411.3  360.47  5447.8  364.95  5476.7  365.87
#Mann= 8 ,-1 , 0
  3800.9     .07       0  4121.5     .05       0  4710.1    .035       0
  4808.6      .1       0  4980.1     .05       0  4989.8      .1       0
  5129.7     .12       0  5389.5     .07       0
Bank Sta=4980.1,4989.8
XS Rating Curve= 0 ,0
Exp/Cntr=0.3,0.1

Type RM Length L Ch R = 1 ,3617    ,975,975,975
BEGIN DESCRIPTION:
StreamM045 2.0
END DESCRIPTION:
XS GIS Cut Line= 3
        2523275.     13833125.01        2523075.       13831325.
        2522675.       13831125.
#Sta/Elev= 30
  3185.2  361.69  3326.1  360.92  3376.4  362.25  3426.7  360.68  3629.7  360.13
  3794.7  360.05  4017.8  359.33  4316.2  357.08    4363  356.49  4504.3  354.92
  4531.9  355.07  4738.7  353.36    4785  351.96    4956  352.59  4971.3  346.03
  4971.8  345.53  4981.1  346.03  4999.1  346.97  5004.7  350.64  5010.3  349.66
  5018.6   351.5  5148.3  351.47  5175.2  351.28  5189.1  349.57  5206.2  350.24
    5287  359.25  5340.1  361.42  5362.4  363.84    5368  365.61  5443.5  367.12
#Mann= 13 ,-1 , 0
  3185.2     .07       0  3629.7    .035       0  3794.7     .07       0
  4017.8    .035       0  4316.2     .05       0    4363    .035       0
  4504.3     .05       0  4531.9    .035       0  4738.7      .1       0
  4971.3     .05       0  4981.1      .1       0  5148.3     .12       0
  5206.2     .07       0
Bank Sta=4971.3,4981.1
XS Rating Curve= 0 ,0
Exp/Cntr=0.3,0.1

Type RM Length L Ch R = 1 ,2642    ,777,777,777
BEGIN DESCRIPTION:
H21329
END DESCRIPTION:
XS GIS Cut Line= 4
      2523956.91      13832692.8      2523929.71     13831680.99
      2523597.89     13831109.83      2522662.88      13830609.7
#Sta/Elev= 30
  3651.5  358.48  3899.4  358.35  4009.4     356  4069.5  357.38  4599.6  351.37
  4954.1  350.66  4985.1  348.66  4994.4   346.2  4995.9  343.21  4996.4  342.71
  5005.9  343.21  5006.7  345.95  5038.1  349.91  5133.2  348.45    5279   350.7
  5306.7  348.14  5316.3   349.9  5448.4  350.39  5505.4  351.28  5574.8  352.27
  5656.4  351.27  5803.8   353.3  5876.3   355.5  5892.6  357.13  5980.4  358.43
  6166.5  366.86  6210.4  370.04  6216.1  368.92  6242.2  370.13  6384.6   374.6
#Mann= 7 ,-1 , 0
  3651.5     .05       0  4954.1      .1       0  4995.9     .05       0
  5005.9      .1       0  5448.4    .035       0  5505.4     .12       0
  6242.2     .07       0
Bank Sta=4995.9,5005.9
XS Rating Curve= 0 ,0
Exp/Cntr=0.3,0.1

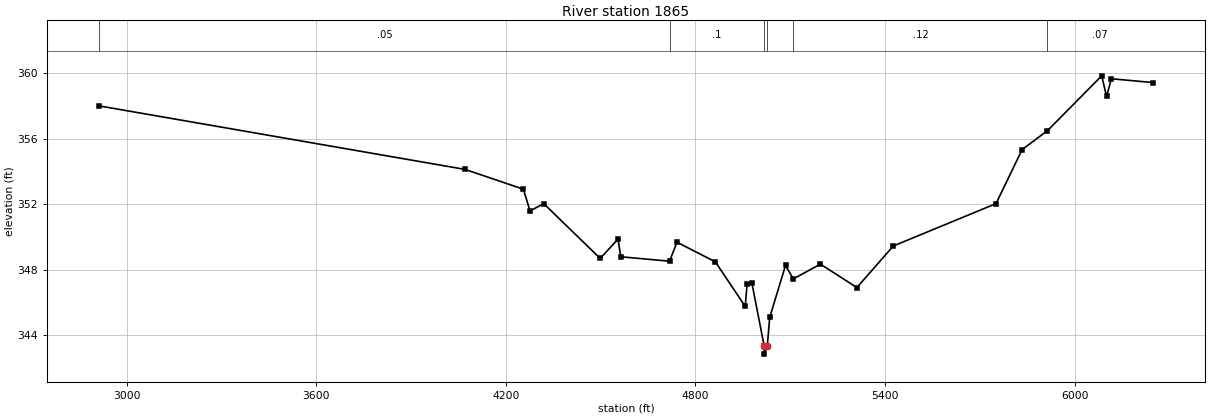
Type RM Length L Ch R = 1 ,1865    ,0,0,0
BEGIN DESCRIPTION:
H21340
END DESCRIPTION:
XS GIS Cut Line= 4
      2524092.03     13832652.19       2524540.4     13831511.78
      2523960.43     13830707.61      2523014.93     13830113.02
#Sta/Elev= 30
  2913.6     358  4071.1  354.12  4255.7  352.91  4276.6  351.58    4320  352.03
  4498.7  348.68  4555.2  349.86  4563.7  348.78  4718.3  348.51  4741.7  349.67
  4863.2  348.47  4957.6  345.75  4963.8  347.14  4978.5   347.2  5017.6  343.33
  5018.1  342.83  5027.6  343.33  5035.1  345.07  5085.2  348.25  5109.9  347.43
  5195.6  348.33    5311   346.9  5426.4  349.44  5751.5  352.03  5833.9  355.33
  5914.3  356.49  6085.9  359.84  6101.2  358.58  6116.5  359.66  6247.4  359.43
#Mann= 6 ,-1 , 0
  2913.6     .05       0  4718.3      .1       0  5017.6     .05       0
  5027.6      .1       0  5109.9     .12       0  5914.3     .07       0
Bank Sta=5017.6,5027.6
XS Rating Curve= 0 ,0
Exp/Cntr=0.3,0.1

Chan Stop Cuts=-1
Use User Specified Reach Order=0
Composite Channel Slope=5