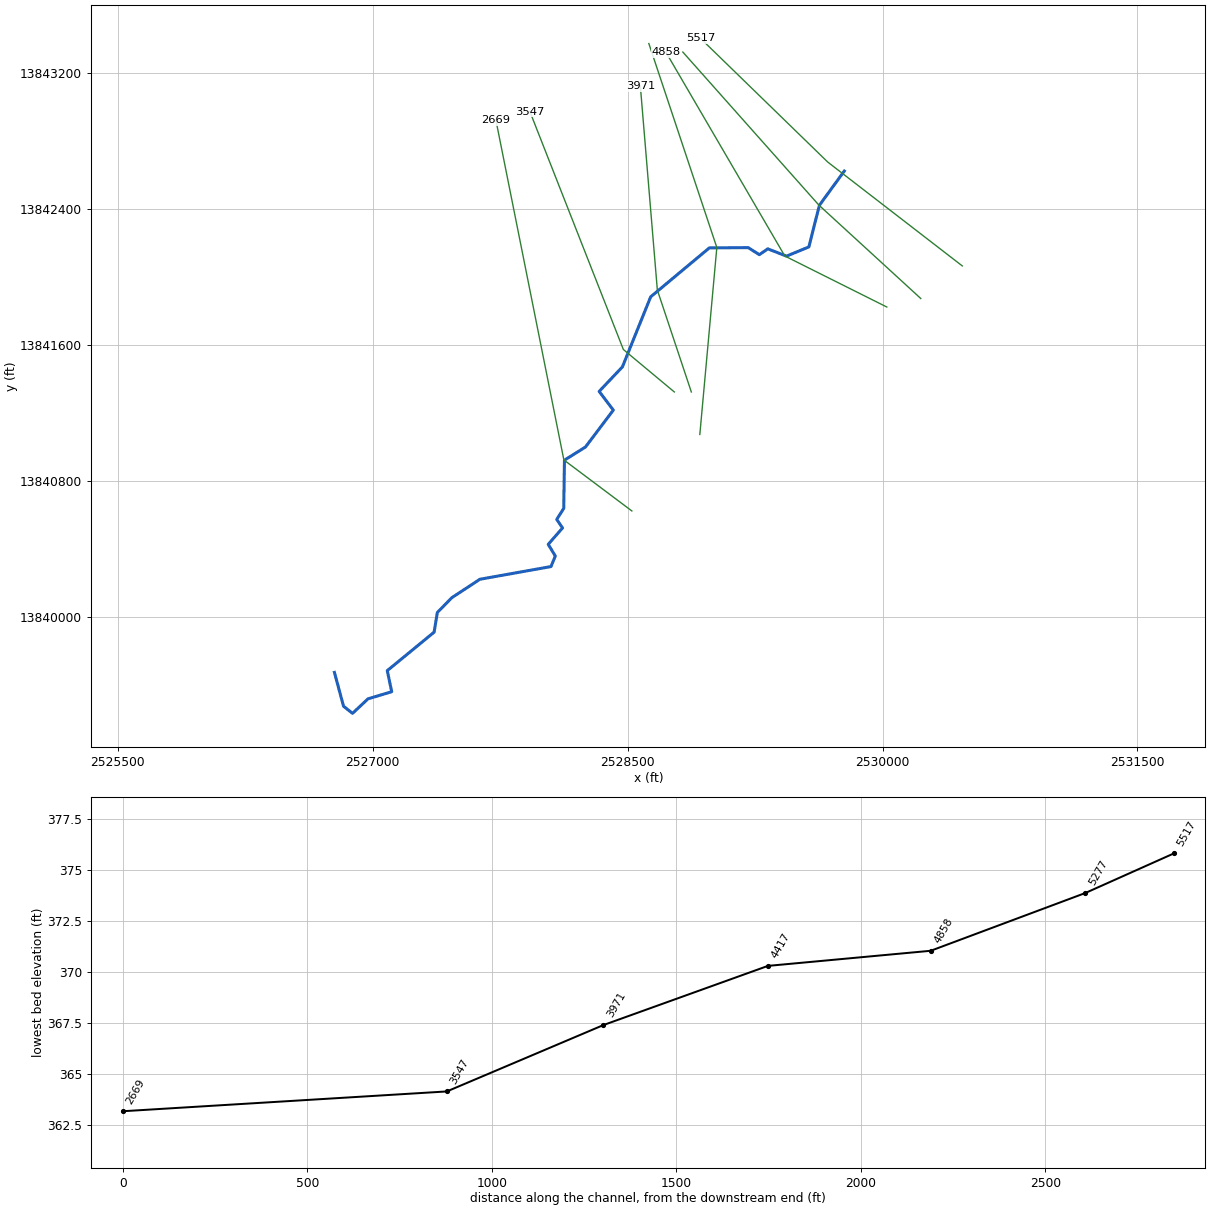
--- StreamM046.prj (project) ---

Proj Title=StreamM046 Base Level Engineering
Current Plan=p01
Default Exp/Contr=0.3,0.1
English Units
Geom File=g01
Flow File=f01
Plan File=p01
BEGIN DESCRIPTION:
StreamM046
END DESCRIPTION:

--- StreamM046.p01 (plan) ---

Plan Title=Multiple Run
Short Identifier=Multiple
Geom File=g01
Flow File=f01
Subcritical Flow
K Sum by GR= 0
Std Step Tol= 0.01
Critical Tol= 0.01
Num of Std Step Trials= 20
Max Error Tol= 0.3
Flow Tol Ratio= 0.001
Split Flow NTrial= 30
Split Flow Tol= 0.02
Split Flow Ratio= 0.02
Log Output Level= 0
Friction Slope Method= 1
Unsteady Friction Slope Method= 2
Unsteady Bridges Friction Slope Method= 1
Parabolic Critical Depth
Global Vel Dist=  1 , 1 , 1
Global Log Level= 0
CheckData=True
Encroach Param= -1, 0, 0, 0
BEGIN DESCRIPTION:
Multiple Run
END DESCRIPTION:

--- StreamM046.f01 (steady flow) ---

Flow Title=Multiple
Number of Profiles=7
Profile Names=10-year,25-year,50-year,1pct_min,100-year,1pct_plu,500-year
River Rch & RM= StreamM046,Reach-1,5517
     668    1072    1436     932    1859    3710    3085
River Rch & RM= StreamM046,Reach-1,4417
     897    1459    1971    1288    2571    5129    4328
Boundary for River Rch & Prof#=StreamM046,Reach-1,1
Up Type=0
Dn Type=3
Dn Slope=0.005
Boundary for River Rch & Prof#=StreamM046,Reach-1,2
Up Type=0
Dn Type=3
Dn Slope=0.005
Boundary for River Rch & Prof#=StreamM046,Reach-1,3
Up Type=0
Dn Type=3
Dn Slope=0.005
Boundary for River Rch & Prof#=StreamM046,Reach-1,4
Up Type=0
Dn Type=3
Dn Slope=0.005
Boundary for River Rch & Prof#=StreamM046,Reach-1,5
Up Type=0
Dn Type=3
Dn Slope=0.005
Boundary for River Rch & Prof#=StreamM046,Reach-1,6
Up Type=0
Dn Type=3
Dn Slope=0.005
Boundary for River Rch & Prof#=StreamM046,Reach-1,7
Up Type=0
Dn Type=3
Dn Slope=0.005

--- StreamM046.g01 (geometry) ---

Geom Title=Existing Conditions

River Reach=StreamM046,Reach-1
Reach XY= 30
      2529775.00     13842625.00      2529628.55     13842423.53
      2529566.54     13842178.50      2529435.05     13842124.24
      2529324.90     13842167.20      2529275.10     13842132.79
      2529209.84     13842174.35      2528980.93     13842172.76
      2528635.76     13841884.68      2528469.47     13841472.57
      2528332.61     13841328.33      2528416.03     13841218.33
      2528252.13     13841001.17      2528128.45     13840923.75
      2528124.35     13840640.16      2528082.81     13840574.90
      2528117.43     13840525.00      2528032.85     13840428.41
      2528074.85     13840359.58      2528049.15     13840297.71
      2527630.86     13840222.93      2527465.30     13840114.23
      2527380.52     13840027.44      2527361.60     13839911.70
      2527085.98     13839685.37      2527112.04     13839561.37
      2526972.58     13839519.44      2526881.49     13839433.90
      2526828.61     13839476.00      2526775.00     13839675.00

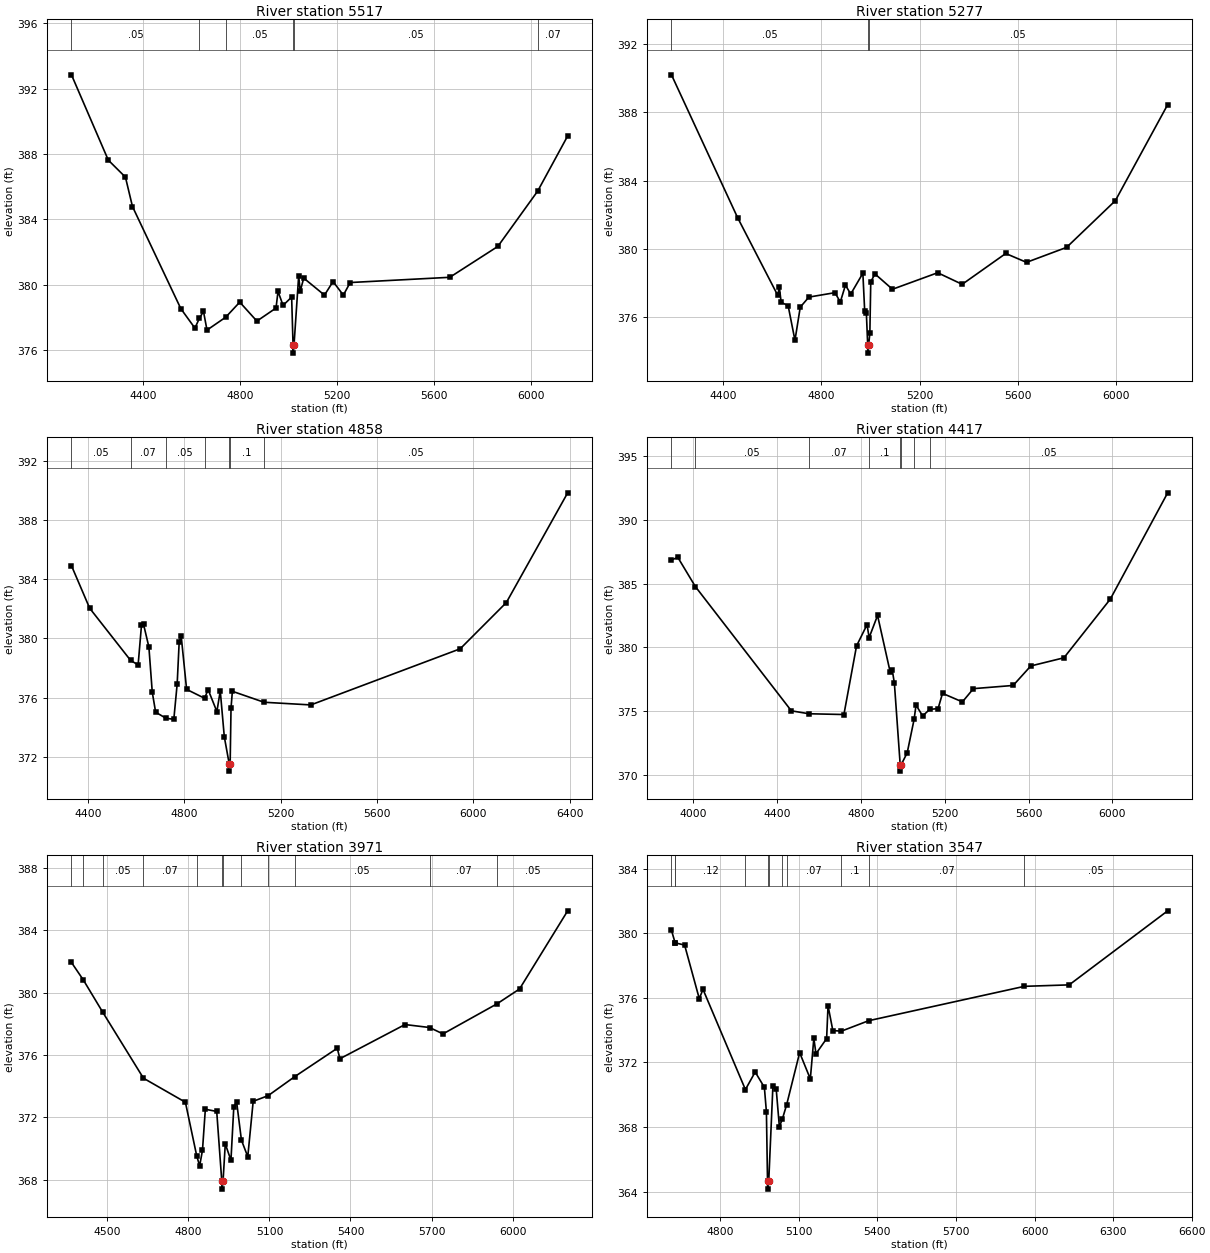
Type RM Length L Ch R = 1,5517,240,240,240
BEGIN DESCRIPTION:
H21341
END DESCRIPTION:
XS GIS Cut Line= 3
      2530469.25     13842066.68      2529677.57     13842677.80
      2528928.82     13843405.75
#Sta/Elev= 30
  4106.6  392.84  4258.3  387.62  4328.9  386.58  4357.9  384.78  4557.2  378.53
  4615.2  377.34  4633.8  377.95  4650.5  378.36  4665.0  377.22  4742.2  378.01
  4799.9  378.93  4870.5  377.77  4949.4  378.57  4957.5  379.59  4978.4  378.73
  5013.7  379.24  5019.5  376.31  5019.8  375.81  5023.5  376.31  5042.7  380.54
  5049.0  379.60  5063.5  380.40  5149.0  379.36  5184.3  380.19  5226.7  379.36
  5255.0  380.13  5665.3  380.45  5863.3  382.34  6027.2  385.72  6151.0  389.10
#Mann=6,-1,0
  4106.6    0.05       0  4633.8    0.07       0  4742.2    0.05       0
  5019.5    0.05       0  5023.5    0.05       0  6027.2    0.07       0
Bank Sta=5019.5,5023.5
Exp/Cntr=0.3,0.1

Type RM Length L Ch R = 1,5277,419,419,419
BEGIN DESCRIPTION:
StreamM046 6.0
END DESCRIPTION:
XS GIS Cut Line= 3
      2530224.97     13841875.03      2529625.00     13842425.00
      2528824.97     13843325.03
#Sta/Elev= 30
  4190.3  390.21  4459.4  381.82  4622.2  377.27  4629.0  377.74  4636.4  376.85
  4664.7  376.66  4692.5  374.62  4714.1  376.57  4749.2  377.16  4855.3  377.42
  4876.9  376.87  4897.8  377.86  4919.4  377.34  4968.7  378.56  4976.1  376.34
  4982.9  376.23  4988.3  374.37  4988.6  373.87  4992.3  374.37  4997.1  375.03
  5000.8  378.06  5018.0  378.52  5089.1  377.62  5273.0  378.59  5372.6  377.91
  5549.8  379.72  5634.3  379.20  5797.4  380.08  5995.5  382.82  6208.4  388.46
#Mann=3,-1,0
  4190.3    0.05       0  4988.3    0.05       0  4992.3    0.05       0
Bank Sta=4988.3,4992.3
Exp/Cntr=0.3,0.1

Type RM Length L Ch R = 1,4858,441,441,441
BEGIN DESCRIPTION:
StreamM046 5.0
END DESCRIPTION:
XS GIS Cut Line= 3
      2530025.00     13841825.00      2529425.00     13842125.00
      2528724.98     13843325.03
#Sta/Elev= 30
  4330.9  384.91  4406.4  382.04  4576.2  378.52  4607.6  378.21  4621.6  380.90
  4630.0  380.96  4652.3  379.42  4666.3  376.37  4680.3  375.02  4723.2  374.61
  4755.8  374.54  4769.7  376.92  4778.1  379.77  4786.5  380.14  4808.9  376.56
  4883.4  375.96  4898.3  376.54  4934.6  375.06  4948.6  376.46  4965.4  373.36
  4985.7  371.54  4986.0  371.04  4989.7  371.54  4993.3  375.30  4998.9  376.43
  5130.4  375.69  5324.6  375.51  5944.8  379.30  6136.3  382.42  6391.0  389.83
#Mann=7,-1,0
  4330.9    0.05       0  4576.2    0.07       0  4723.2    0.05       0
  4883.4     0.1       0  4985.7    0.05       0  4989.7     0.1       0
  5130.4    0.05       0
Bank Sta=4985.7,4989.7
Exp/Cntr=0.3,0.1

Type RM Length L Ch R = 1,4417,446,446,446
BEGIN DESCRIPTION:
StreamM046 4.0
END DESCRIPTION:
XS GIS Cut Line= 3
      2528925.00     13841074.97      2529025.00     13842175.00
      2528624.99     13843375.02
#Sta/Elev= 30
  3895.0  386.86  3925.2  387.07  4008.9  384.78  4467.4  375.03  4551.6  374.80
  4718.4  374.74  4778.7  380.12  4828.9  381.79  4838.8  380.77  4879.1  382.51
  4939.3  378.08  4949.4  378.22  4959.4  377.20  4987.2  370.80  4987.6  370.30
  4991.8  370.80  5020.7  371.74  5053.6  374.36  5062.8  375.48  5094.4  374.63
  5127.8  375.14  5168.2  375.21  5189.3  376.40  5284.2  375.73  5336.9  376.77
  5526.6  377.02  5610.9  378.55  5769.1  379.19  5990.4  383.79  6264.5  392.13
#Mann=8,-1,0
  3895.0    0.12       0  4008.9    0.05       0  4551.6    0.07       0
  4838.8     0.1       0  4987.2    0.05       0  4991.8     0.1       0
  5053.6    0.07       0  5127.8    0.05       0
Bank Sta=4987.2,4991.8
Exp/Cntr=0.3,0.1

Type RM Length L Ch R = 1,3971,424,424,424
BEGIN DESCRIPTION:
StreamM046 3.0
END DESCRIPTION:
XS GIS Cut Line= 3
      2528875.01     13841324.96      2528675.00     13841925.00
      2528575.00     13843125.04
#Sta/Elev= 30
  4367.2  381.93  4411.4  380.80  4482.6  378.75  4633.7  374.51  4788.9  372.97
  4830.7  369.54  4841.6  368.89  4852.1  369.89  4862.7  372.52  4904.8  372.38
  4923.6  367.90  4924.0  367.40  4928.2  367.90  4936.5  370.30  4957.5  369.25
  4968.1  372.68  4978.6  372.98  4996.3  370.54  5019.8  369.48  5039.8  373.03
  5095.0  373.39  5193.5  374.61  5350.9  376.43  5360.9  375.76  5601.8  377.95
  5692.8  377.76  5742.3  377.35  5942.5  379.28  6025.7  380.23  6203.9  385.24
#Mann=12,-1,0
  4367.2    0.05       0  4411.4    0.07       0  4482.6    0.05       0
  4633.7    0.07       0  4830.7    0.12       0  4923.6    0.05       0
  4928.2    0.12       0  4996.3     0.1       0  5095.0    0.07       0
  5193.5    0.05       0  5692.8    0.07       0  5942.5    0.05       0
Bank Sta=4923.6,4928.2
Exp/Cntr=0.3,0.1

Type RM Length L Ch R = 1,3547,878,878,878
BEGIN DESCRIPTION:
StreamM046 2.0
END DESCRIPTION:
XS GIS Cut Line= 3
      2528774.99     13841325.00      2528475.00     13841575.00
      2527924.99     13842975.03
#Sta/Elev= 30
  4613.7  380.19  4627.7  379.41  4628.7  379.41  4663.8  379.28  4719.8  375.96
  4734.1  376.53  4896.0  370.32  4933.3  371.41  4968.4  370.46  4976.2  368.94
  4980.4  364.65  4980.7  364.15  4985.1  364.65  5001.0  370.54  5013.7  370.33
  5025.7  368.02  5037.4  368.51  5053.1  369.36  5103.1  372.61  5143.9  370.98
  5157.3  373.50  5165.4  372.54  5206.1  373.48  5211.5  375.52  5229.8  373.98
  5262.2  373.94  5366.7  374.59  5961.3  376.72  6132.3  376.81  6508.4  381.40
#Mann=11,-1,0
  4613.7    0.12       0  4627.7    0.07       0  4628.7    0.12       0
  4896.0    0.07       0  4980.4    0.05       0  4985.1    0.07       0
  5037.4    0.12       0  5053.1    0.07       0  5262.2     0.1       0
  5366.7    0.07       0  5961.3    0.05       0
Bank Sta=4980.4,4985.1
Exp/Cntr=0.3,0.1

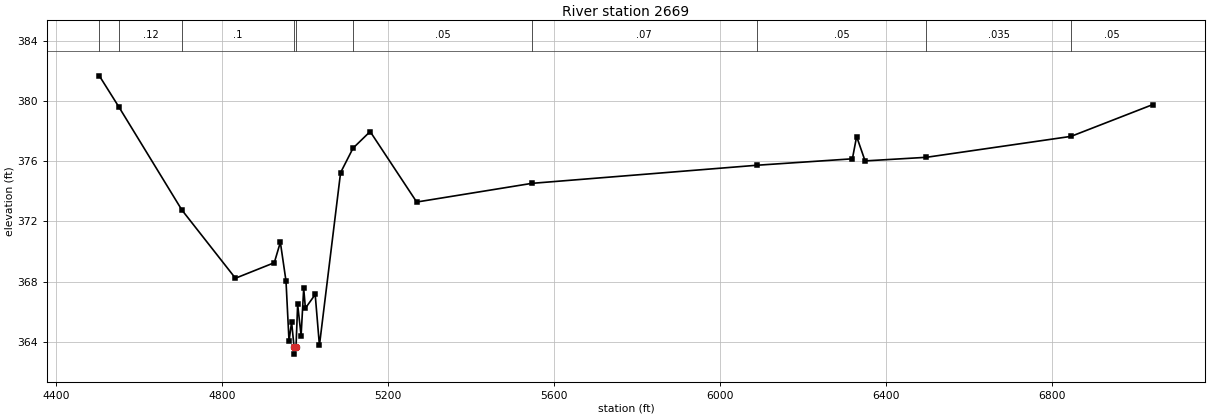
Type RM Length L Ch R = 1,2669,0,0,0
BEGIN DESCRIPTION:
StreamM046 1.0
END DESCRIPTION:
XS GIS Cut Line= 3
      2528524.97     13840625.02      2528125.00     13840925.00
      2527725.00     13842925.02
#Sta/Elev= 30
  4503.9  381.66  4551.3  379.58  4702.9  372.75  4832.0  368.22  4925.7  369.25
  4940.3  370.61  4953.9  368.04  4961.2  364.05  4967.4  365.31  4973.3  363.68
  4973.7  363.18  4978.1  363.68  4982.0  366.48  4990.3  364.41  4996.6  367.54
  5000.7  366.23  5024.3  367.14  5034.5  363.76  5085.5  375.23  5115.6  376.86
  5156.8  377.96  5269.0  373.28  5546.7  374.52  6088.3  375.72  6319.4  376.15
  6329.6  377.63  6350.0  376.01  6497.9  376.25  6846.6  377.64  7043.5  379.75
#Mann=10,-1,0
  4503.9   0.035       0  4551.3    0.12       0  4702.9     0.1       0
  4973.3    0.05       0  4978.1     0.1       0  5115.6    0.05       0
  5546.7    0.07       0  6088.3    0.05       0  6497.9   0.035       0
  6846.6    0.05       0
Bank Sta=4973.3,4978.1
Exp/Cntr=0.3,0.1

Chan Stop Cuts=-1