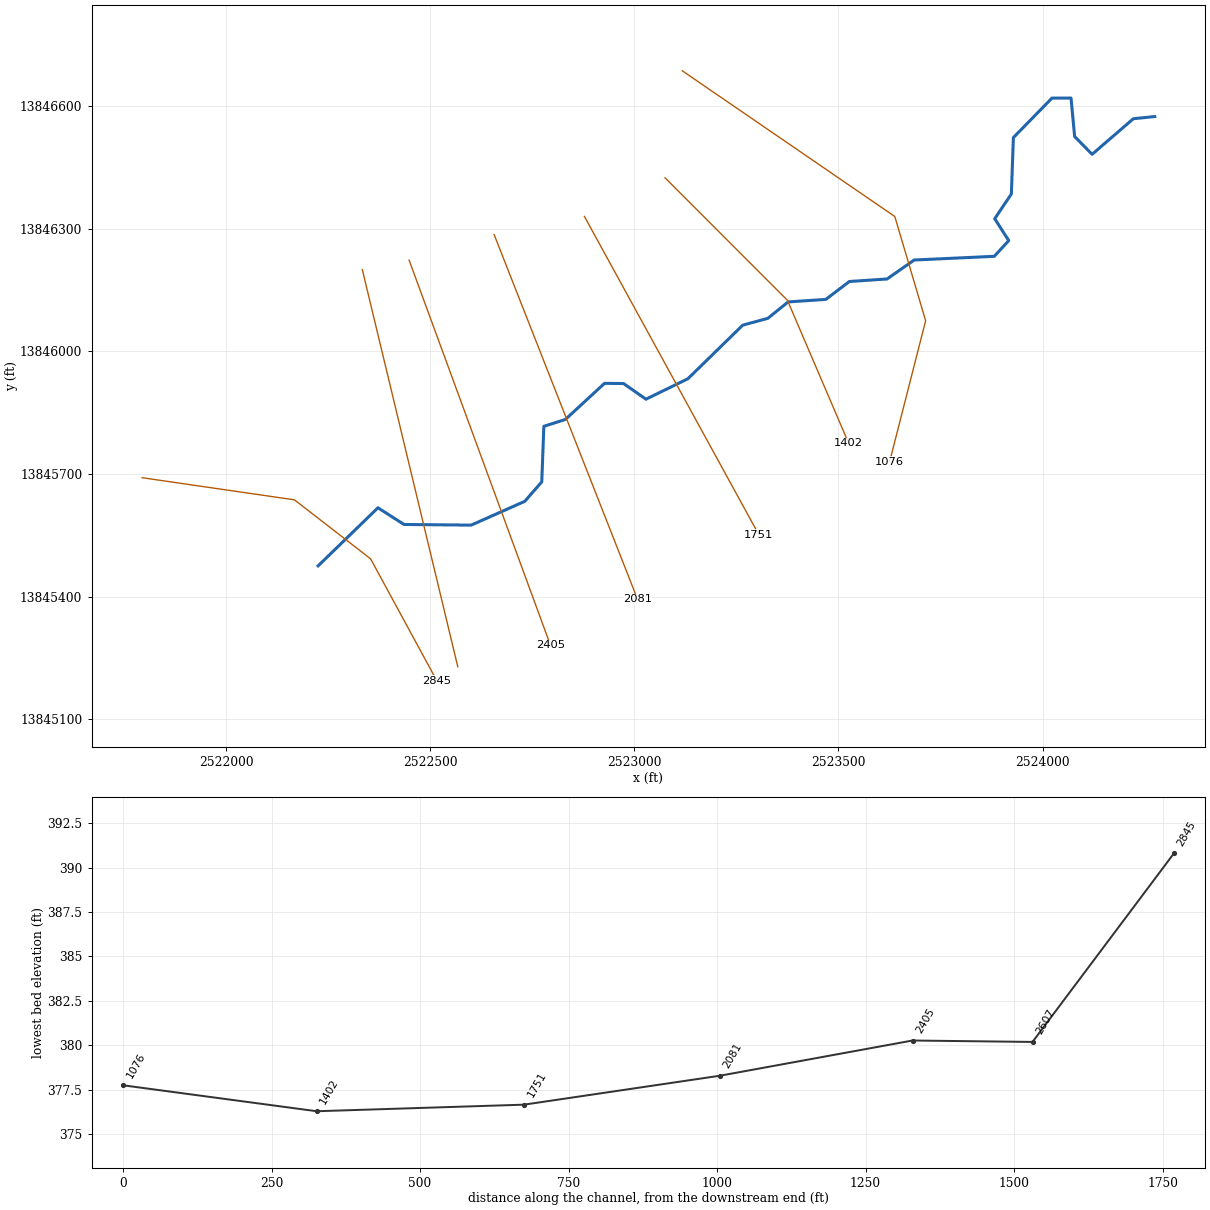
--- StreamM048.prj (project) ---

Proj Title=StreamM048 Base Level Engineering
Current Plan=p01
Default Exp/Contr=0.3,0.1
English Units
Geom File=g01
Flow File=f01
Plan File=p01
BEGIN DESCRIPTION:
StreamM048
END DESCRIPTION:

--- StreamM048.p01 (plan) ---

Plan Title=Multiple Run
Short Identifier=Multiple
Geom File=g01
Flow File=f01
Subcritical Flow
K Sum by GR= 0
Std Step Tol= 0.01
Critical Tol= 0.01
Num of Std Step Trials= 20
Max Error Tol= 0.3
Flow Tol Ratio= 0.001
Split Flow NTrial= 30
Split Flow Tol= 0.02
Split Flow Ratio= 0.02
Log Output Level= 0
Friction Slope Method= 1
Unsteady Friction Slope Method= 2
Unsteady Bridges Friction Slope Method= 1
Parabolic Critical Depth
Global Vel Dist=  1 , 1 , 1
Global Log Level= 0
CheckData=True
Encroach Param= -1, 0, 0, 0
BEGIN DESCRIPTION:
Multiple Run
END DESCRIPTION:

--- StreamM048.f01 (steady flow) ---

Flow Title=Multiple
Number of Profiles=7
Profile Names=10-year,25-year,50-year,1pct_min,100-year,1pct_plu,500-year
River Rch & RM= StreamM048,Reach-1,2845
     526     831    1102     708    1413    2820    2299
Boundary for River Rch & Prof#=StreamM048,Reach-1,1
Up Type=0
Dn Type=3
Dn Slope=0.005
Boundary for River Rch & Prof#=StreamM048,Reach-1,2
Up Type=0
Dn Type=3
Dn Slope=0.005
Boundary for River Rch & Prof#=StreamM048,Reach-1,3
Up Type=0
Dn Type=3
Dn Slope=0.005
Boundary for River Rch & Prof#=StreamM048,Reach-1,4
Up Type=0
Dn Type=3
Dn Slope=0.005
Boundary for River Rch & Prof#=StreamM048,Reach-1,5
Up Type=0
Dn Type=3
Dn Slope=0.005
Boundary for River Rch & Prof#=StreamM048,Reach-1,6
Up Type=0
Dn Type=3
Dn Slope=0.005
Boundary for River Rch & Prof#=StreamM048,Reach-1,7
Up Type=0
Dn Type=3
Dn Slope=0.005

--- StreamM048.g01 (geometry) ---

Geom Title=Existing Conditions

River Reach=StreamM048,Reach-1
Reach XY= 30
      2522225.00     13845475.00      2522371.58     13845617.21
      2522435.43     13845576.39      2522600.09     13845574.79
      2522731.39     13845633.00      2522773.00     13845680.68
      2522778.08     13845816.70      2522830.69     13845833.33
      2522926.65     13845921.83      2522973.35     13845921.42
      2523028.31     13845883.07      2523131.05     13845933.12
      2523265.32     13846064.24      2523327.17     13846081.14
      2523376.58     13846121.18      2523469.03     13846127.35
      2523526.60     13846171.15      2523619.02     13846177.36
      2523685.50     13846223.78      2523881.82     13846232.81
      2523917.13     13846271.38      2523882.81     13846324.89
      2523923.61     13846385.44      2523928.54     13846523.55
      2524023.09     13846620.10      2524069.74     13846620.40
      2524078.64     13846526.09      2524121.38     13846482.47
      2524222.48     13846569.65      2524275.00     13846575.00

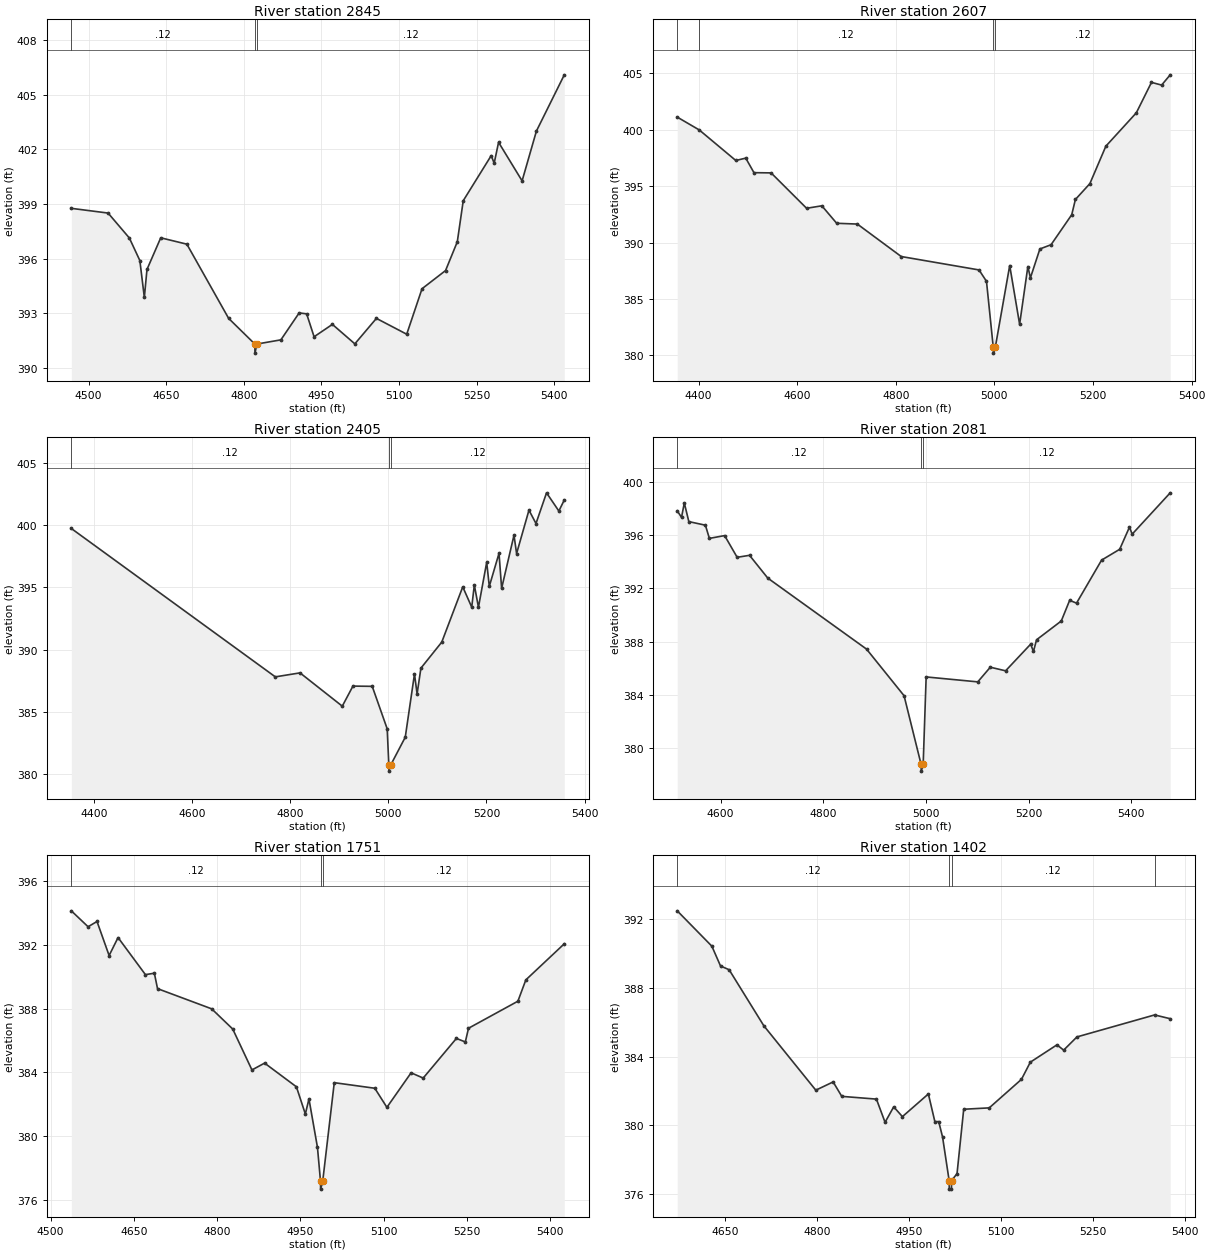
Type RM Length L Ch R = 1,2845,238,238,238
BEGIN DESCRIPTION:
H21347
END DESCRIPTION:
XS GIS Cut Line= 4
      2521793.92     13845690.83      2522167.04     13845636.67
      2522353.62     13845492.22      2522516.11     13845193.32
#Sta/Elev= 30
  4466.5  398.76  4537.6  398.50  4578.7  397.13  4599.0  395.89  4607.7  393.86
  4612.8  395.40  4639.4  397.14  4689.9  396.79  4770.7  392.71  4821.3  391.30
  4821.6  390.80  4825.3  391.30  4871.7  391.53  4907.0  393.01  4921.5  392.96
  4935.9  391.70  4971.3  392.38  5014.7  391.31  5056.4  392.71  5115.0  391.84
  5144.6  394.34  5190.1  395.34  5212.8  396.92  5224.3  399.18  5278.4  401.66
  5284.1  401.24  5292.6  402.39  5338.1  400.27  5365.8  403.01  5419.7  406.10
#Mann=3,-1,0
  4466.5    0.12       0  4821.3    0.05       0  4825.3    0.12       0
Bank Sta=4821.3,4825.3
Exp/Cntr=0.3,0.1

Type RM Length L Ch R = 1,2607,202,202,202
BEGIN DESCRIPTION:
H21346
END DESCRIPTION:
XS GIS Cut Line= 2
      2522333.33     13846200.13      2522567.24     13845228.07
#Sta/Elev= 30
  4356.7  401.13  4401.4  399.99  4475.5  397.28  4495.7  397.49  4512.3  396.20
  4547.1  396.18  4619.1  393.04  4650.0  393.26  4680.1  391.71  4722.0  391.64
  4811.0  388.76  4968.8  387.57  4983.9  386.56  4997.7  380.69  4997.9  380.19
  5001.7  380.69  5031.0  387.96  5051.1  382.75  5067.8  387.87  5073.0  386.87
  5092.2  389.43  5114.9  389.81  5156.8  392.47  5164.2  393.82  5193.6  395.23
  5226.0  398.55  5287.8  401.51  5318.5  404.21  5339.1  403.97  5356.5  404.88
#Mann=4,-1,0
  4356.7    0.07       0  4401.4    0.12       0  4997.7    0.05       0
  5001.7    0.12       0
Bank Sta=4997.7,5001.7
Exp/Cntr=0.3,0.1

Type RM Length L Ch R = 1,2405,324,324,324
BEGIN DESCRIPTION:
H21345
END DESCRIPTION:
XS GIS Cut Line= 2
      2522447.92     13846223.52      2522794.27     13845280.83
#Sta/Elev= 30
  4354.3  399.73  4769.9  387.83  4820.2  388.15  4906.3  385.48  4928.0  387.09
  4967.3  387.07  4997.8  383.66  5001.1  380.77  5001.3  380.27  5005.1  380.77
  5034.6  382.99  5053.4  388.06  5058.7  386.46  5066.5  388.53  5109.0  390.62
  5151.7  395.05  5170.0  393.42  5175.3  395.20  5183.7  393.41  5200.5  397.02
  5205.8  395.09  5225.6  397.74  5230.9  394.93  5256.1  399.19  5261.4  397.72
  5286.6  401.20  5300.9  400.13  5322.4  402.59  5347.5  401.13  5358.6  402.02
#Mann=3,-1,0
  4354.3    0.12       0  5001.1    0.05       0  5005.1    0.12       0
Bank Sta=5001.1,5005.1
Exp/Cntr=0.3,0.1

Type RM Length L Ch R = 1,2081,330,330,330
BEGIN DESCRIPTION:
H21344
END DESCRIPTION:
XS GIS Cut Line= 2
      2522656.24     13846286.05      2523007.80     13845392.84
#Sta/Elev= 30
  4515.7  397.83  4524.1  397.34  4529.5  398.42  4538.3  397.02  4570.6  396.75
  4578.3  395.76  4608.0  395.97  4632.4  394.34  4656.5  394.49  4692.0  392.78
  4884.3  387.45  4957.4  383.95  4990.6  378.79  4990.8  378.29  4994.6  378.79
  5000.4  385.36  5100.9  384.99  5125.3  386.09  5155.1  385.82  5203.9  387.82
  5209.3  387.27  5215.4  388.15  5263.5  389.56  5279.8  391.11  5293.2  390.90
  5342.0  394.13  5377.2  394.94  5396.2  396.60  5401.6  396.08  5475.6  399.18
#Mann=3,-1,0
  4515.7    0.12       0  4990.6    0.05       0  4994.6    0.12       0
Bank Sta=4990.6,4994.6
Exp/Cntr=0.3,0.1

Type RM Length L Ch R = 1,1751,349,349,349
BEGIN DESCRIPTION:
H21343
END DESCRIPTION:
XS GIS Cut Line= 2
      2522877.59     13846330.32      2523304.68     13845551.66
#Sta/Elev= 30
  4537.5  394.15  4567.7  393.15  4583.8  393.48  4605.6  391.34  4621.7  392.47
  4671.0  390.14  4687.1  390.23  4692.8  389.26  4790.4  387.99  4828.3  386.72
  4862.9  384.15  4885.7  384.58  4943.0  383.09  4959.1  381.38  4965.6  382.33
  4980.9  379.29  4986.4  377.16  4986.6  376.66  4990.4  377.16  5011.2  383.35
  5084.2  383.00  5106.0  381.80  5149.6  383.97  5171.4  383.64  5231.2  386.13
  5247.3  385.91  5253.0  386.77  5342.0  388.47  5356.3  389.81  5425.6  392.08
#Mann=3,-1,0
  4537.5    0.12       0  4986.4    0.05       0  4990.4    0.12       0
Bank Sta=4986.4,4990.4
Exp/Cntr=0.3,0.1

Type RM Length L Ch R = 1,1402,326,326,326
BEGIN DESCRIPTION:
StreamM048 1.0
END DESCRIPTION:
XS GIS Cut Line= 3
      2523075.01     13846424.99      2523375.00     13846125.00
      2523524.98     13845775.04
#Sta/Elev= 30
  4571.6  392.49  4628.2  390.43  4642.3  389.28  4656.4  389.06  4713.0  385.80
  4797.9  382.05  4826.2  382.53  4840.3  381.69  4896.9  381.53  4911.0  380.18
  4925.1  381.08  4939.3  380.51  4981.7  381.83  4992.3  380.22  4998.6  380.22
  5004.9  379.32  5015.6  376.79  5015.9  376.29  5019.4  376.29  5019.6  376.79
  5028.5  377.19  5039.4  380.94  5081.1  381.02  5133.7  382.68  5148.2  383.68
  5191.7  384.69  5202.6  384.38  5224.3  385.15  5351.1  386.43  5376.6  386.21
#Mann=4,-1,0
  4571.6    0.12       0  5015.6    0.05       0  5019.6    0.12       0
  5351.1    0.07       0
Bank Sta=5015.6,5019.6
Exp/Cntr=0.3,0.1

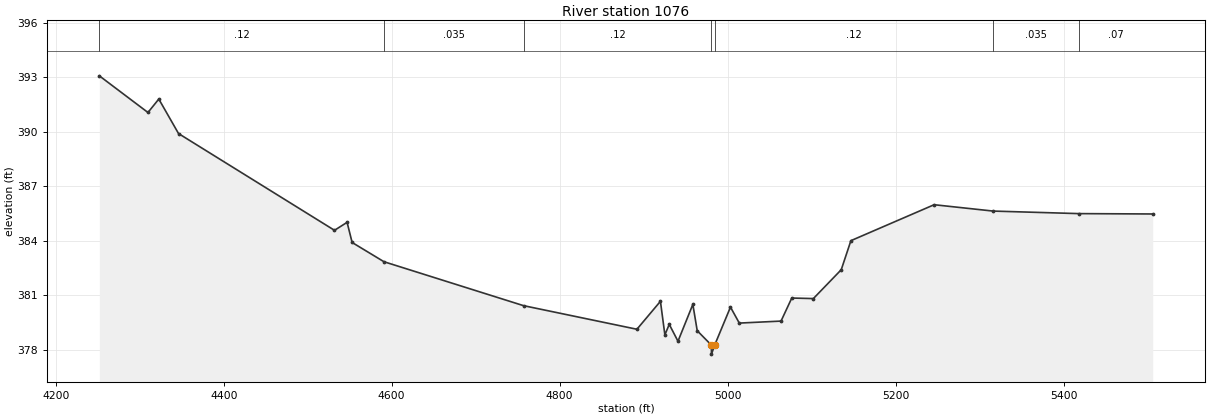
Type RM Length L Ch R = 1,1076,0,0,0
BEGIN DESCRIPTION:
H21342
END DESCRIPTION:
XS GIS Cut Line= 4
      2523117.20     13846687.06      2523638.02     13846330.30
      2523713.54     13846075.09      2523625.16     13845729.35
#Sta/Elev= 30
  4251.9  393.08  4309.8  391.06  4322.7  391.80  4346.2  389.90  4531.9  384.57
  4546.9  385.01  4552.9  383.90  4590.8  382.84  4757.0  380.42  4892.0  379.12
  4920.0  380.66  4925.3  378.81  4930.5  379.39  4940.9  378.46  4958.6  380.49
  4963.8  379.04  4980.6  378.25  4980.8  377.75  4984.6  378.25  5003.4  380.34
  5013.9  379.46  5063.6  379.57  5076.4  380.84  5102.1  380.81  5135.3  382.40
  5146.8  384.00  5245.9  385.98  5316.1  385.63  5418.3  385.49  5506.2  385.47
#Mann=7,-1,0
  4251.9    0.12       0  4590.8   0.035       0  4757.0    0.12       0
  4980.6    0.05       0  4984.6    0.12       0  5316.1   0.035       0
  5418.3    0.07       0
Bank Sta=4980.6,4984.6
Exp/Cntr=0.3,0.1

Chan Stop Cuts=-1