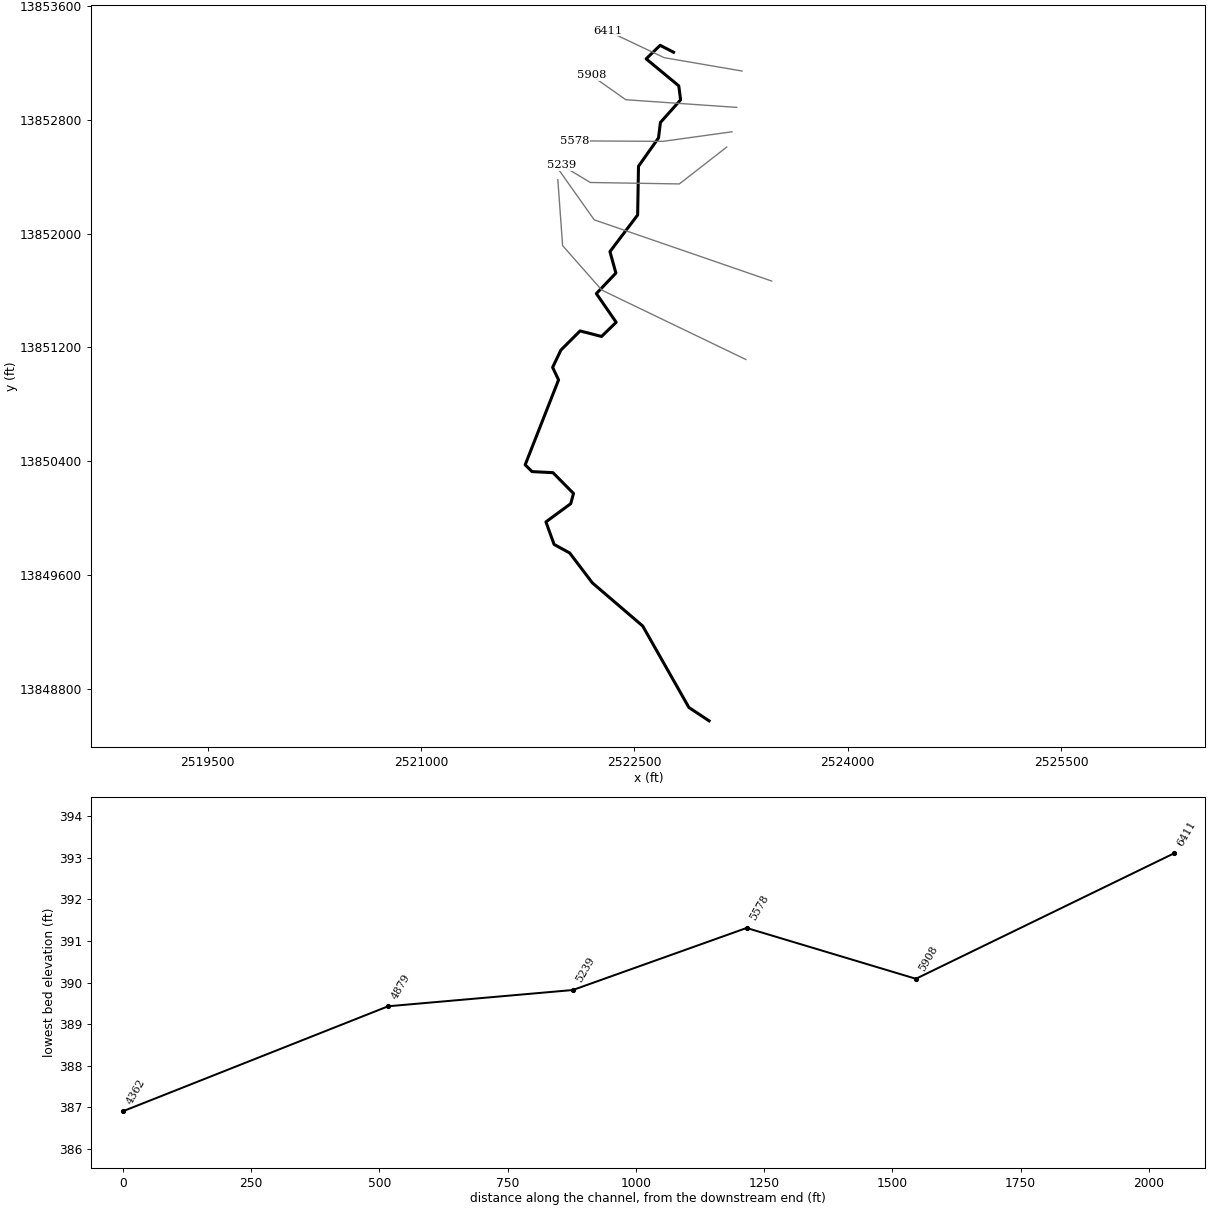
--- StreamM049.prj (project) ---

Proj Title=StreamM049 Base Level Engineering
Current Plan=p01
Default Exp/Contr=0.3,0.1
English Units
Geom File=g01
Flow File=f01
Plan File=p01
BEGIN DESCRIPTION:
StreamM049
END DESCRIPTION:

--- StreamM049.p01 (plan) ---

Plan Title=Multiple Run
Short Identifier=Multiple
Geom File=g01
Flow File=f01
Subcritical Flow
K Sum by GR= 0
Std Step Tol= 0.01
Critical Tol= 0.01
Num of Std Step Trials= 20
Max Error Tol= 0.3
Flow Tol Ratio= 0.001
Split Flow NTrial= 30
Split Flow Tol= 0.02
Split Flow Ratio= 0.02
Log Output Level= 0
Friction Slope Method= 1
Unsteady Friction Slope Method= 2
Unsteady Bridges Friction Slope Method= 1
Parabolic Critical Depth
Global Vel Dist=  1 , 1 , 1
Global Log Level= 0
CheckData=True
Encroach Param= -1, 0, 0, 0
BEGIN DESCRIPTION:
Multiple Run
END DESCRIPTION:

--- StreamM049.f01 (steady flow) ---

Flow Title=Multiple
Number of Profiles=7
Profile Names=10-year,25-year,50-year,1pct_min,100-year,1pct_plu,500-year
River Rch & RM= StreamM049,Reach-1,6411
     485     758     997     636    1269    2532    2031
River Rch & RM= StreamM049,Reach-1,4879
     711    1130    1502     965    1926    3843    3136
Boundary for River Rch & Prof#=StreamM049,Reach-1,1
Up Type=0
Dn Type=3
Dn Slope=0.005
Boundary for River Rch & Prof#=StreamM049,Reach-1,2
Up Type=0
Dn Type=3
Dn Slope=0.005
Boundary for River Rch & Prof#=StreamM049,Reach-1,3
Up Type=0
Dn Type=3
Dn Slope=0.005
Boundary for River Rch & Prof#=StreamM049,Reach-1,4
Up Type=0
Dn Type=3
Dn Slope=0.005
Boundary for River Rch & Prof#=StreamM049,Reach-1,5
Up Type=0
Dn Type=3
Dn Slope=0.005
Boundary for River Rch & Prof#=StreamM049,Reach-1,6
Up Type=0
Dn Type=3
Dn Slope=0.005
Boundary for River Rch & Prof#=StreamM049,Reach-1,7
Up Type=0
Dn Type=3
Dn Slope=0.005

--- StreamM049.g01 (geometry) ---

Geom Title=Existing Conditions

River Reach=StreamM049,Reach-1
Reach XY= 30
      2522775.00     13853275.00      2522680.95     13853323.46
      2522582.58     13853228.35      2522811.81     13853038.65
      2522824.77     13852940.22      2522682.86     13852781.17
      2522669.46     13852672.58      2522528.75     13852473.45
      2522522.76     13852130.93      2522328.13     13851873.37
      2522369.91     13851722.70      2522232.59     13851578.33
      2522371.91     13851376.63      2522269.12     13851276.96
      2522118.26     13851315.87      2521983.14     13851181.06
      2521925.14     13851059.59      2521966.93     13850971.69
      2521732.18     13850374.67      2521780.45     13850327.06
      2521927.45     13850319.53      2522071.91     13850173.35
      2522052.32     13850101.49      2521878.04     13849973.58
      2521935.63     13849815.00      2522045.08     13849755.21
      2522204.62     13849544.84      2522558.36     13849241.71
      2522883.13     13848668.93      2523025.00     13848575.00

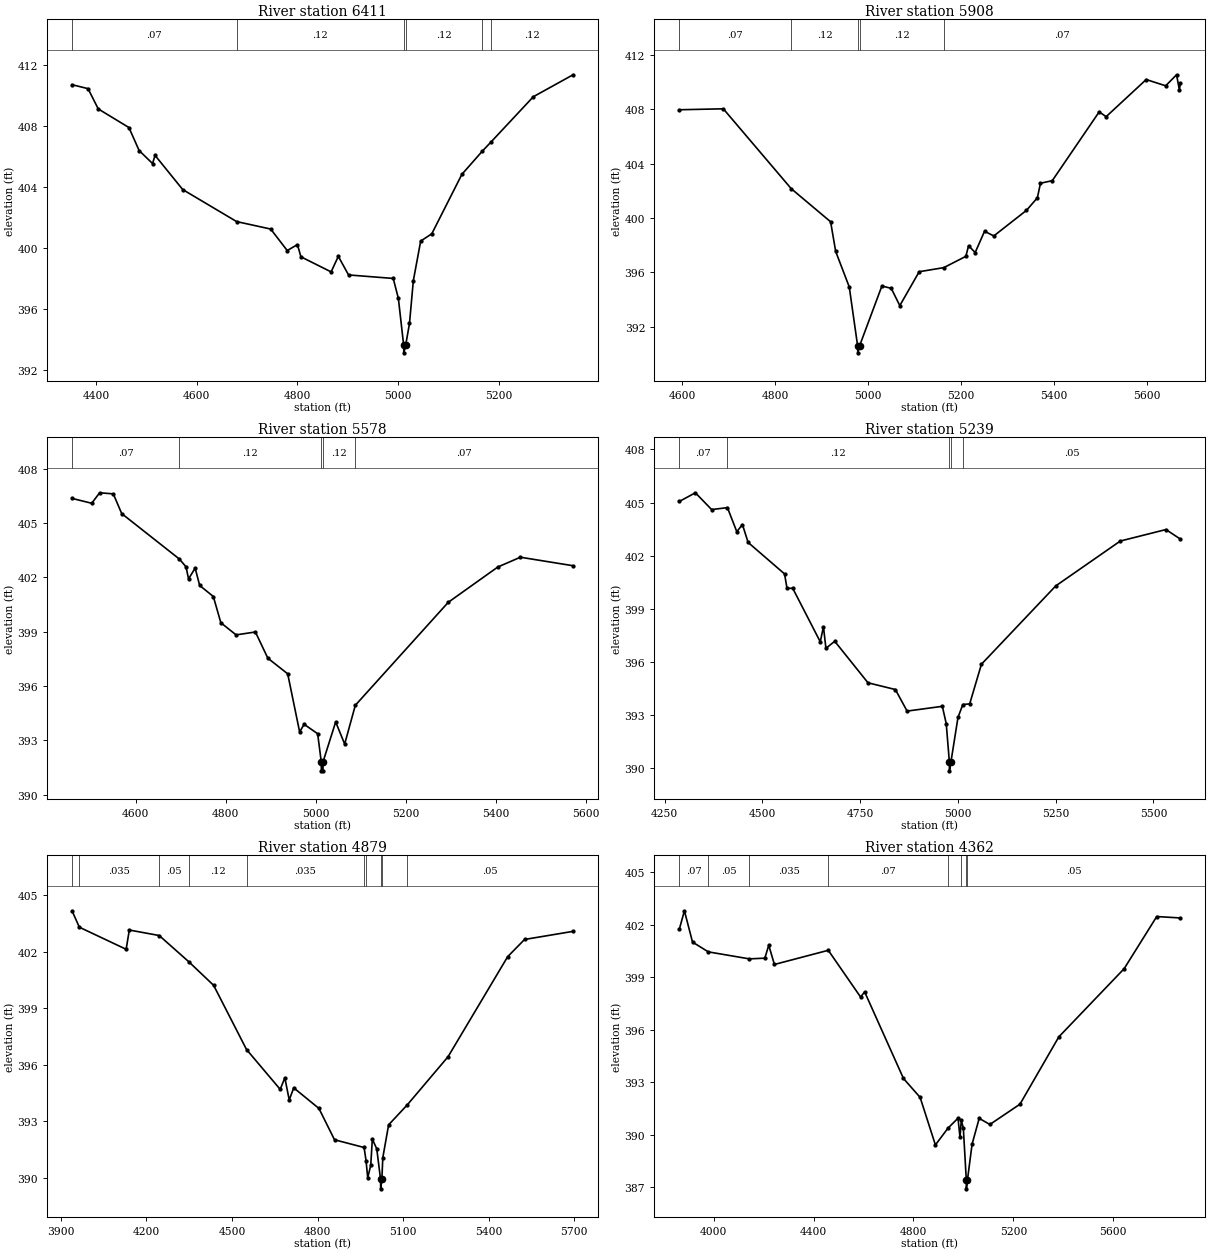
Type RM Length L Ch R = 1,6411,503,503,503
BEGIN DESCRIPTION:
H21353
END DESCRIPTION:
XS GIS Cut Line= 3
      2523256.37     13853142.71      2522708.24     13853236.87
      2522311.50     13853425.15
#Sta/Elev= 30
  4352.1  410.69  4383.9  410.43  4404.2  409.10  4465.1  407.88  4485.4  406.37
  4512.0  405.52  4517.1  406.05  4572.0  403.81  4679.1  401.71  4746.8  401.22
  4779.6  399.81  4799.9  400.20  4806.8  399.40  4866.8  398.41  4881.1  399.43
  4901.4  398.21  4990.2  397.98  5000.4  396.67  5010.9  393.60  5011.2  393.10
  5014.9  393.60  5022.5  395.03  5030.1  397.83  5044.7  400.43  5066.8  400.91
  5126.6  404.81  5166.9  406.32  5185.0  406.95  5268.5  409.90  5347.4  411.34
#Mann=6,-1,0
  4352.1    0.07       0  4679.1    0.12       0  5010.9    0.05       0
  5014.9    0.12       0  5166.9   0.035       0  5185.0    0.12       0
Bank Sta=5010.9,5014.9
Exp/Cntr=0.3,0.1

Type RM Length L Ch R = 1,5908,330,330,330
BEGIN DESCRIPTION:
H21352
END DESCRIPTION:
XS GIS Cut Line= 3
      2523219.30     13852887.17      2522439.24     13852940.97
      2522198.61     13853111.42
#Sta/Elev= 30
  4594.2  407.95  4688.7  408.02  4834.7  402.15  4919.3  399.72  4930.2  397.54
  4959.4  394.93  4977.4  390.59  4977.7  390.09  4981.4  390.59  5029.5  395.00
  5049.6  394.83  5068.0  393.56  5109.7  396.05  5162.5  396.35  5210.0  397.18
  5215.8  397.96  5230.0  397.46  5250.1  399.02  5270.1  398.68  5340.3  400.56
  5363.7  401.48  5370.3  402.55  5395.7  402.74  5496.6  407.80  5511.4  407.44
  5597.6  410.17  5639.4  409.71  5662.8  410.52  5668.9  409.41  5671.0  409.89
#Mann=5,-1,0
  4594.2    0.07       0  4834.7    0.12       0  4977.4    0.05       0
  4981.4    0.12       0  5162.5    0.07       0
Bank Sta=4977.4,4981.4
Exp/Cntr=0.3,0.1

Type RM Length L Ch R = 1,5578,339,339,339
BEGIN DESCRIPTION:
H21351
END DESCRIPTION:
XS GIS Cut Line= 3
      2523185.70     13852715.67      2522701.52     13852648.43
      2522078.05     13852651.78
#Sta/Elev= 30
  4458.9  406.36  4502.6  406.09  4520.2  406.67  4550.5  406.61  4569.2  405.52
  4697.2  403.01  4712.0  402.58  4717.6  401.91  4732.2  402.51  4742.3  401.55
  4772.6  400.94  4789.3  399.49  4823.1  398.82  4866.0  398.98  4893.7  397.53
  4937.7  396.67  4964.2  393.46  4974.2  393.88  5004.2  393.36  5012.2  391.81
  5012.5  391.31  5016.0  391.31  5016.2  391.81  5044.2  394.01  5064.2  392.79
  5087.8  394.93  5294.2  400.62  5404.2  402.57  5454.3  403.11  5571.2  402.64
#Mann=5,-1,0
  4458.9    0.07       0  4697.2    0.12       0  5012.2    0.05       0
  5016.2    0.12       0  5087.8    0.07       0
Bank Sta=5012.2,5016.2
Exp/Cntr=0.3,0.1

Type RM Length L Ch R = 1,5239,360,360,360
BEGIN DESCRIPTION:
H21350
END DESCRIPTION:
XS GIS Cut Line= 4
      2523148.70     13852608.05      2522815.84     13852349.16
      2522190.42     13852359.25      2521989.58     13852479.75
#Sta/Elev= 30
  4287.4  405.06  4328.4  405.55  4370.0  404.60  4410.4  404.71  4434.3  403.35
  4448.8  403.75  4463.3  402.74  4556.5  400.96  4562.8  400.14  4577.3  400.15
  4647.8  397.12  4656.0  397.97  4662.3  396.75  4684.8  397.15  4769.9  394.80
  4839.9  394.42  4869.9  393.20  4960.0  393.47  4970.0  392.49  4978.0  390.32
  4978.2  389.82  4982.0  390.32  5000.0  392.84  5012.4  393.57  5030.0  393.61
  5060.0  395.85  5250.0  400.28  5415.2  402.82  5531.9  403.47  5568.8  402.93
#Mann=5,-1,0
  4287.4    0.07       0  4410.4    0.12       0  4978.0    0.05       0
  4982.0    0.12       0  5012.4    0.05       0
Bank Sta=4978,4982
Exp/Cntr=0.3,0.1

Type RM Length L Ch R = 1,4879,517,517,517
BEGIN DESCRIPTION:
H21349
END DESCRIPTION:
XS GIS Cut Line= 3
      2523464.80     13851666.58      2522217.32     13852096.97
      2521965.11     13852453.43
#Sta/Elev= 30
  3939.2  404.16  3964.8  403.29  4128.9  402.12  4140.0  403.14  4244.7  402.85
  4348.5  401.46  4435.6  400.21  4550.9  396.81  4668.9  394.70  4685.2  395.31
  4700.6  394.14  4716.4  394.78  4804.7  393.69  4859.3  392.03  4963.0  391.62
  4969.8  390.93  4975.7  390.02  4986.3  390.67  4991.9  392.06  5007.4  391.55
  5020.8  389.93  5021.1  389.43  5025.3  389.93  5028.6  391.08  5049.0  392.82
  5114.5  393.88  5257.4  396.43  5466.4  401.73  5525.5  402.64  5695.5  403.07
#Mann=10,-1,0
  3939.2    0.05       0  3964.8   0.035       0  4244.7    0.05       0
  4348.5    0.12       0  4550.9   0.035       0  4963.0    0.12       0
  4969.8   0.035       0  5020.8   0.035       0  5025.3   0.035       0
  5114.5    0.05       0
Bank Sta=5020.8,5025.3
Exp/Cntr=0.3,0.1

Type RM Length L Ch R = 1,4362,0,0,0
BEGIN DESCRIPTION:
H21348
END DESCRIPTION:
XS GIS Cut Line= 4
      2523283.28     13851115.10      2522271.12     13851602.68
      2521995.39     13851915.40      2521961.77     13852379.39
#Sta/Elev= 30
  3862.9  401.76  3883.2  402.81  3915.6  401.02  3978.9  400.46  4143.1  400.06
  4205.1  400.10  4220.8  400.84  4243.4  399.74  4459.1  400.55  4588.3  397.88
  4604.7  398.17  4760.1  393.22  4826.7  392.14  4887.9  389.42  4938.3  390.38
  4978.4  390.95  4986.4  389.85  4991.5  390.82  4999.7  390.39  5011.6  387.41
  5011.9  386.91  5016.1  387.41  5034.8  389.47  5063.2  390.94  5105.9  390.59
  5226.4  391.75  5382.0  395.60  5643.5  399.50  5773.9  402.48  5868.5  402.40
#Mann=8,-1,0
  3862.9    0.07       0  3978.9    0.05       0  4143.1   0.035       0
  4459.1    0.07       0  4938.3    0.12       0  4991.5    0.05       0
  5011.6    0.05       0  5016.1    0.05       0
Bank Sta=5011.6,5016.1
Exp/Cntr=0.3,0.1

Chan Stop Cuts=-1