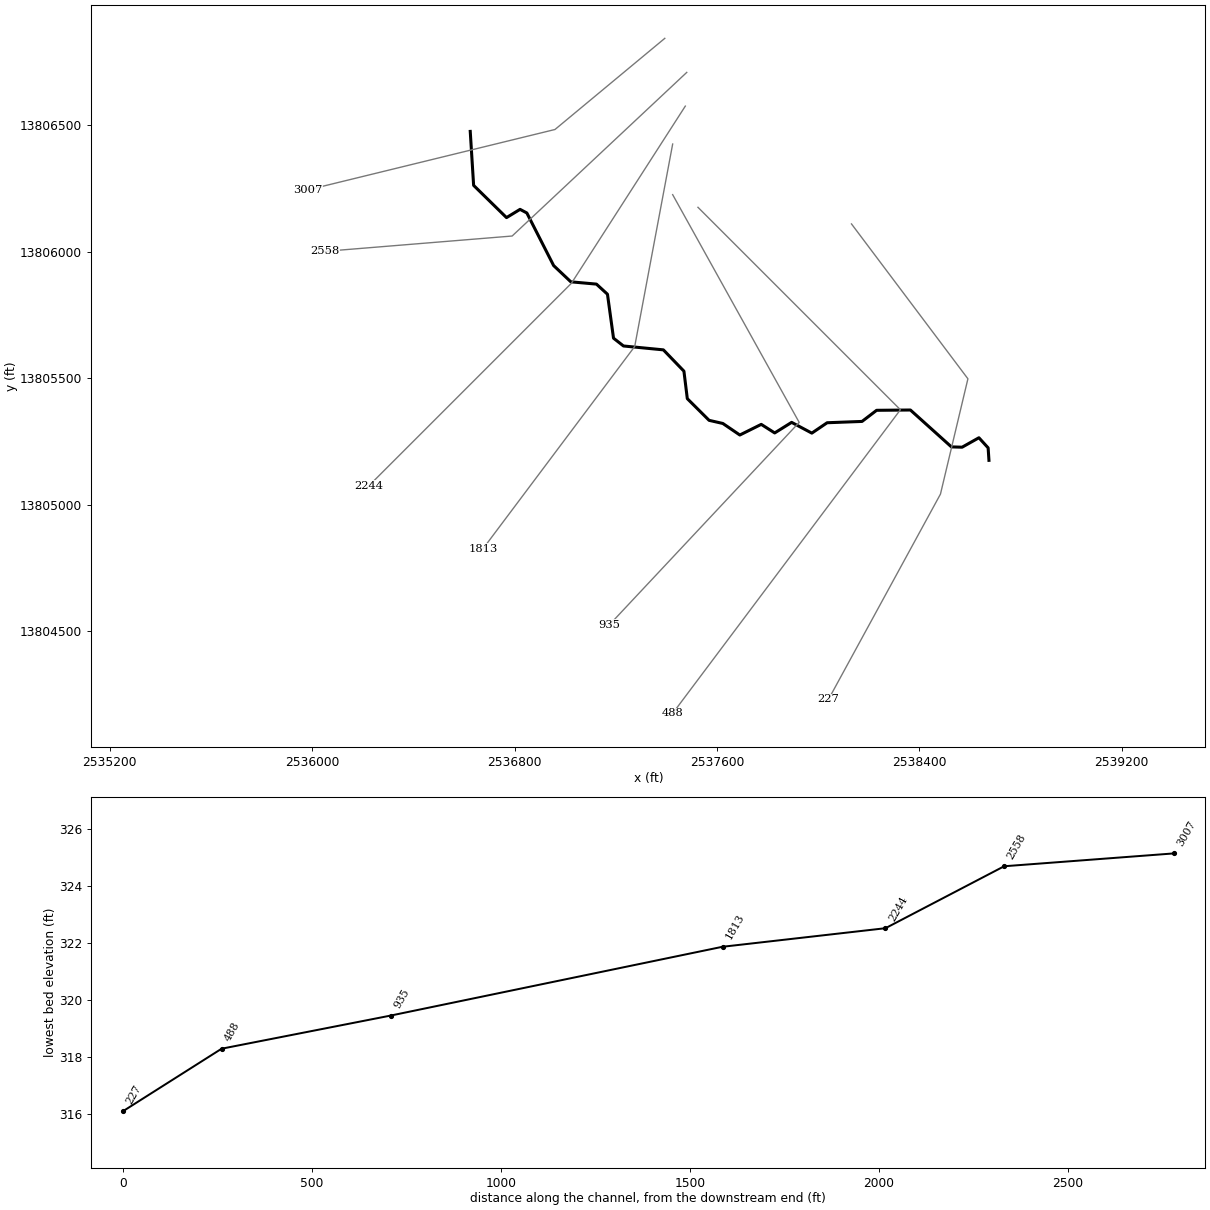
--- StreamM04A.prj (project) ---

Proj Title=StreamM04A Base Level Engineering
Current Plan=p01
Default Exp/Contr=0.3,0.1
English Units
Geom File=g01
Flow File=f01
Plan File=p01
BEGIN DESCRIPTION:
StreamM04A
END DESCRIPTION:

--- StreamM04A.p01 (plan) ---

Plan Title=Multiple Run
Short Identifier=Multiple
Geom File=g01
Flow File=f01
Subcritical Flow
K Sum by GR= 0
Std Step Tol= 0.01
Critical Tol= 0.01
Num of Std Step Trials= 20
Max Error Tol= 0.3
Flow Tol Ratio= 0.001
Split Flow NTrial= 30
Split Flow Tol= 0.02
Split Flow Ratio= 0.02
Log Output Level= 0
Friction Slope Method= 1
Unsteady Friction Slope Method= 2
Unsteady Bridges Friction Slope Method= 1
Parabolic Critical Depth
Global Vel Dist=  1 , 1 , 1
Global Log Level= 0
CheckData=True
Encroach Param= -1, 0, 0, 0
BEGIN DESCRIPTION:
Multiple Run
END DESCRIPTION:

--- StreamM04A.f01 (steady flow) ---

Flow Title=Multiple
Number of Profiles=7
Profile Names=10-year,25-year,50-year,1pct_min,100-year,1pct_plu,500-year
River Rch & RM= StreamM04A,Reach-1,3007
     754    1200    1597    1029    2053    4095    3353
Boundary for River Rch & Prof#=StreamM04A,Reach-1,1
Up Type=0
Dn Type=3
Dn Slope=0.005
Boundary for River Rch & Prof#=StreamM04A,Reach-1,2
Up Type=0
Dn Type=3
Dn Slope=0.005
Boundary for River Rch & Prof#=StreamM04A,Reach-1,3
Up Type=0
Dn Type=3
Dn Slope=0.005
Boundary for River Rch & Prof#=StreamM04A,Reach-1,4
Up Type=0
Dn Type=3
Dn Slope=0.005
Boundary for River Rch & Prof#=StreamM04A,Reach-1,5
Up Type=0
Dn Type=3
Dn Slope=0.005
Boundary for River Rch & Prof#=StreamM04A,Reach-1,6
Up Type=0
Dn Type=3
Dn Slope=0.005
Boundary for River Rch & Prof#=StreamM04A,Reach-1,7
Up Type=0
Dn Type=3
Dn Slope=0.005

--- StreamM04A.g01 (geometry) ---

Geom Title=Existing Conditions

River Reach=StreamM04A,Reach-1
Reach XY= 30
      2536625.00     13806475.00      2536638.37     13806261.68
      2536768.34     13806134.31      2536821.85     13806166.92
      2536848.71     13806152.64      2536954.58     13805944.76
      2537022.56     13805880.52      2537123.75     13805871.49
      2537167.32     13805831.52      2537191.24     13805657.77
      2537230.65     13805626.98      2537388.35     13805611.64
      2537469.48     13805527.44      2537482.86     13805418.81
      2537568.93     13805333.13      2537623.26     13805320.75
      2537690.41     13805275.13      2537775.08     13805317.18
      2537828.23     13805283.32      2537895.16     13805325.10
      2537974.99     13805282.59      2538035.44     13805323.61
      2538173.43     13805328.79      2538230.94     13805372.75
      2538364.56     13805373.96      2538526.65     13805228.16
      2538568.96     13805226.97      2538635.31     13805264.28
      2538671.73     13805224.37      2538675.00     13805175.00

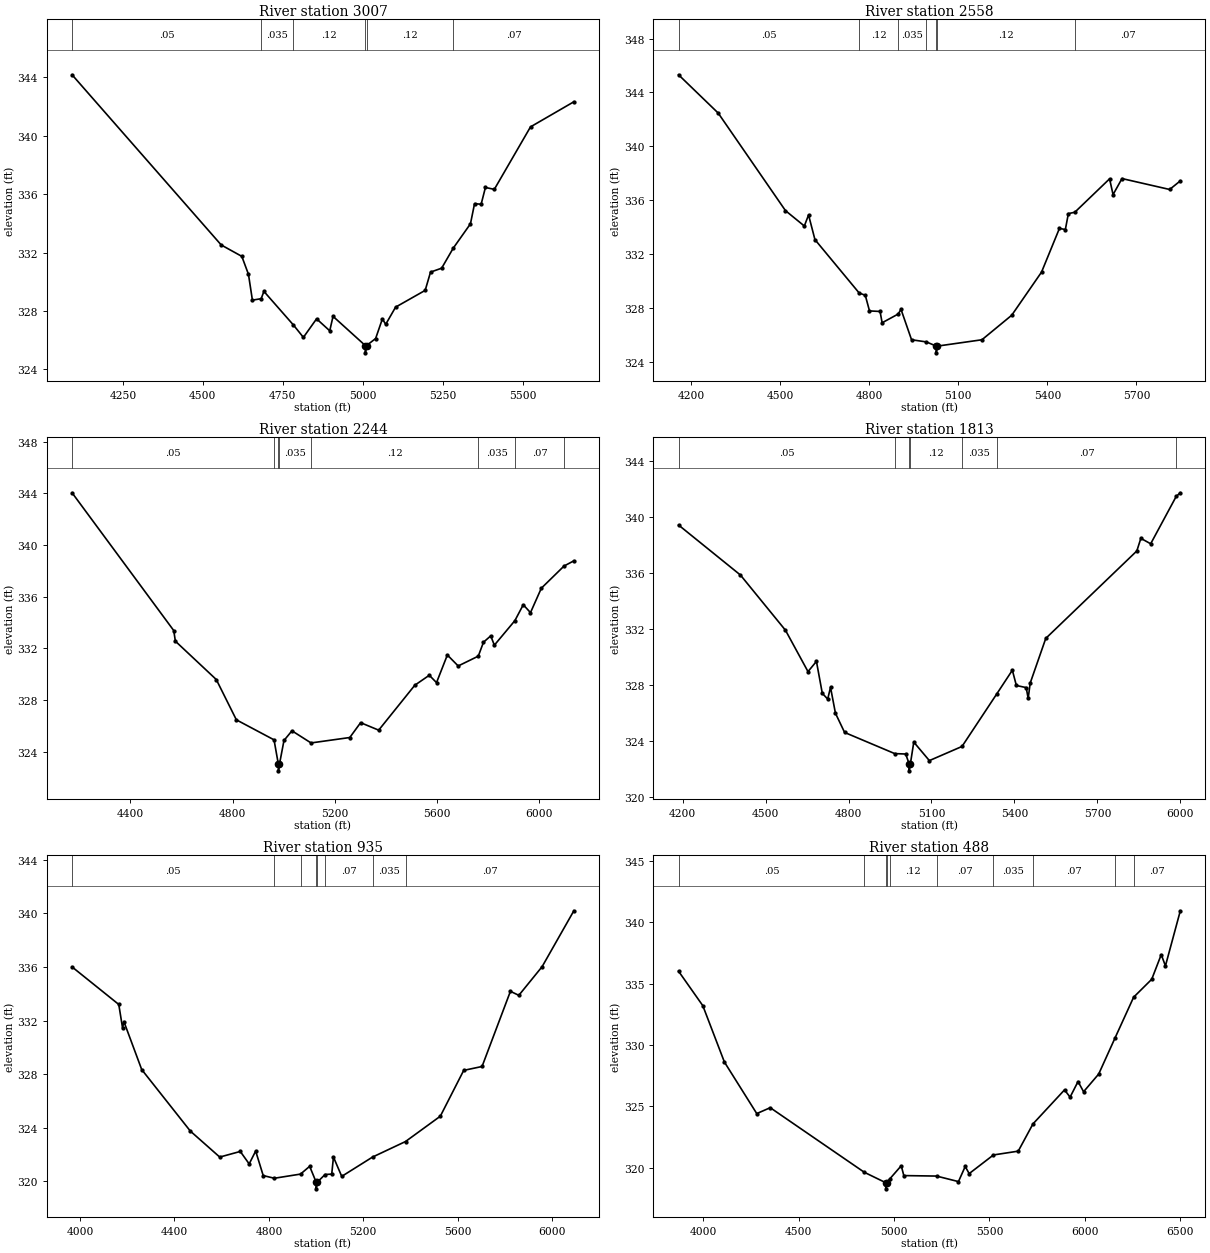
Type RM Length L Ch R = 1,3007,449,449,449
BEGIN DESCRIPTION:
H21355
END DESCRIPTION:
XS GIS Cut Line= 3
      2537393.94     13806842.81      2536959.89     13806482.55
      2535983.32     13806243.84
#Sta/Elev= 30
  4091.1  344.18  4557.6  332.52  4622.0  331.74  4642.8  330.51  4655.1  328.74
  4682.6  328.84  4691.1  329.34  4783.3  327.04  4814.6  326.19  4855.8  327.46
  4897.0  326.64  4907.3  327.63  5008.2  325.63  5008.5  325.13  5012.2  325.63
  5040.5  326.11  5061.7  327.46  5072.0  327.08  5102.9  328.26  5195.5  329.41
  5212.2  330.66  5247.0  330.93  5283.2  332.30  5337.1  333.97  5349.9  335.35
  5370.5  335.31  5383.9  336.46  5411.7  336.33  5524.9  340.61  5660.5  342.33
#Mann=6,-1,0
  4091.1    0.05       0  4682.6   0.035       0  4783.3    0.12       0
  5008.2    0.05       0  5012.2    0.12       0  5283.2    0.07       0
Bank Sta=5008.2,5012.2
Exp/Cntr=0.3,0.1

Type RM Length L Ch R = 1,2558,314,314,314
BEGIN DESCRIPTION:
StreamM04A 5.0
END DESCRIPTION:
XS GIS Cut Line= 3
      2537480.69     13806708.22      2536790.62     13806061.55
      2536049.22     13806000.85
#Sta/Elev= 30
  4158.0  345.31  4291.5  342.47  4518.1  335.23  4581.6  334.09  4595.8  334.91
  4617.3  333.08  4766.2  329.12  4786.8  328.95  4801.0  327.79  4836.6  327.75
  4843.5  326.91  4897.7  327.56  4907.0  327.91  4942.6  325.65  4992.7  325.49
  5025.6  325.18  5025.9  324.68  5029.7  325.18  5179.6  325.65  5279.9  327.47
  5380.3  330.67  5440.5  333.91  5460.5  333.83  5470.6  335.01  5492.2  335.11
  5609.4  337.59  5621.1  336.42  5651.2  337.61  5811.7  336.80  5847.6  337.44
#Mann=7,-1,0
  4158.0    0.05       0  4766.2    0.12       0  4897.7   0.035       0
  4992.7    0.12       0  5025.6    0.05       0  5029.7    0.12       0
  5492.2    0.07       0
Bank Sta=5025.6,5029.7
Exp/Cntr=0.3,0.1

Type RM Length L Ch R = 1,2244,431,431,431
BEGIN DESCRIPTION:
StreamM04A 4.0
END DESCRIPTION:
XS GIS Cut Line= 3
      2537474.98     13806574.96      2537025.00     13805875.00
      2536224.99     13805074.99
#Sta/Elev= 30
  4171.9  344.04  4569.8  333.37  4576.1  332.55  4736.2  329.58  4814.8  326.46
  4962.2  324.91  4979.2  323.01  4979.4  322.51  4983.3  323.01  5001.1  324.86
  5032.3  325.61  5107.0  324.67  5258.6  325.09  5301.0  326.24  5371.7  325.66
  5513.1  329.14  5569.7  329.91  5598.0  329.34  5640.4  331.48  5682.8  330.63
  5761.4  331.39  5781.8  332.47  5810.1  332.96  5824.3  332.24  5904.6  334.14
  5937.4  335.37  5965.7  334.76  6008.1  336.65  6097.1  338.37  6135.4  338.77
#Mann=8,-1,0
  4171.9    0.05       0  4962.2   0.035       0  4979.2   0.035       0
  4983.3   0.035       0  5107.0    0.12       0  5761.4   0.035       0
  5904.6    0.07       0  6097.1    0.05       0
Bank Sta=4979.2,4983.3
Exp/Cntr=0.3,0.1

Type RM Length L Ch R = 1,1813,878,878,878
BEGIN DESCRIPTION:
StreamM04A 3.0
END DESCRIPTION:
XS GIS Cut Line= 3
      2537425.00     13806425.00      2537275.00     13805625.00
      2536675.03     13804825.03
#Sta/Elev= 30
  4185.6  339.40  4409.4  335.83  4572.2  331.89  4653.6  328.94  4684.1  329.67
  4705.3  327.39  4724.8  326.98  4735.0  327.82  4752.8  325.97  4785.9  324.60
  4967.1  323.09  5006.8  323.06  5019.1  322.36  5019.4  321.86  5023.7  322.36
  5036.0  323.91  5092.3  322.59  5210.3  323.60  5336.0  327.35  5392.3  329.04
  5406.8  327.95  5442.3  327.80  5449.5  327.03  5456.8  328.12  5513.1  331.31
  5842.3  337.55  5856.8  338.45  5892.3  338.06  5984.9  341.45  5999.5  341.70
#Mann=7,-1,0
  4185.6    0.05       0  4967.1    0.12       0  5019.1    0.05       0
  5023.7    0.12       0  5210.3   0.035       0  5336.0    0.07       0
  5984.9   0.035       0
Bank Sta=5019.1,5023.7
Exp/Cntr=0.3,0.1

Type RM Length L Ch R = 1,935,447,447,447
BEGIN DESCRIPTION:
StreamM04A 2.0
END DESCRIPTION:
XS GIS Cut Line= 3
      2537425.00     13806225.00      2537925.00     13805325.00
      2537175.03     13804525.04
#Sta/Elev= 30
  3966.1  336.01  4164.0  333.21  4180.0  331.46  4185.7  331.93  4261.2  328.35
  4467.2  323.76  4591.8  321.82  4678.8  322.24  4716.5  321.31  4744.0  322.27
  4776.0  320.44  4823.2  320.24  4934.0  320.55  4972.8  321.13  5000.3  319.95
  5000.7  319.45  5005.1  319.95  5038.2  320.52  5066.3  320.55  5073.6  321.82
  5108.7  320.38  5239.1  321.82  5378.9  322.98  5526.4  324.87  5625.5  328.29
  5703.2  328.58  5823.4  334.19  5859.0  333.89  5957.7  336.03  6092.2  340.20
#Mann=8,-1,0
  3966.1    0.05       0  4823.2   0.035       0  4934.0    0.12       0
  5000.3    0.05       0  5005.1    0.12       0  5038.2    0.07       0
  5239.1   0.035       0  5378.9    0.07       0
Bank Sta=5000.3,5005.1
Exp/Cntr=0.3,0.1

Type RM Length L Ch R = 1,488,261,261,261
BEGIN DESCRIPTION:
StreamM04A 1.0
END DESCRIPTION:
XS GIS Cut Line= 3
      2537524.97     13806175.03      2538325.00     13805375.00
      2537425.01     13804175.01
#Sta/Elev= 30
  3869.3  336.02  3996.6  333.21  4109.8  328.62  4279.5  324.42  4350.2  324.90
  4843.4  319.64  4955.9  318.79  4956.2  318.29  4960.7  318.79  4978.8  319.13
  5037.2  320.17  5050.7  319.37  5222.4  319.33  5337.2  318.88  5372.6  320.11
  5393.4  319.53  5520.7  321.05  5650.7  321.36  5728.0  323.58  5893.4  326.35
  5922.6  325.76  5964.3  327.03  5993.4  326.20  6072.6  327.64  6158.6  330.59
  6255.8  333.90  6350.7  335.36  6400.7  337.37  6422.6  336.45  6500.7  340.94
#Mann=10,-1,0
  3869.3    0.05       0  4843.4   0.035       0  4955.9    0.05       0
  4960.7   0.035       0  4978.8    0.12       0  5222.4    0.07       0
  5520.7   0.035       0  5728.0    0.07       0  6158.6    0.12       0
  6255.8    0.07       0
Bank Sta=4955.9,4960.7
Exp/Cntr=0.3,0.1

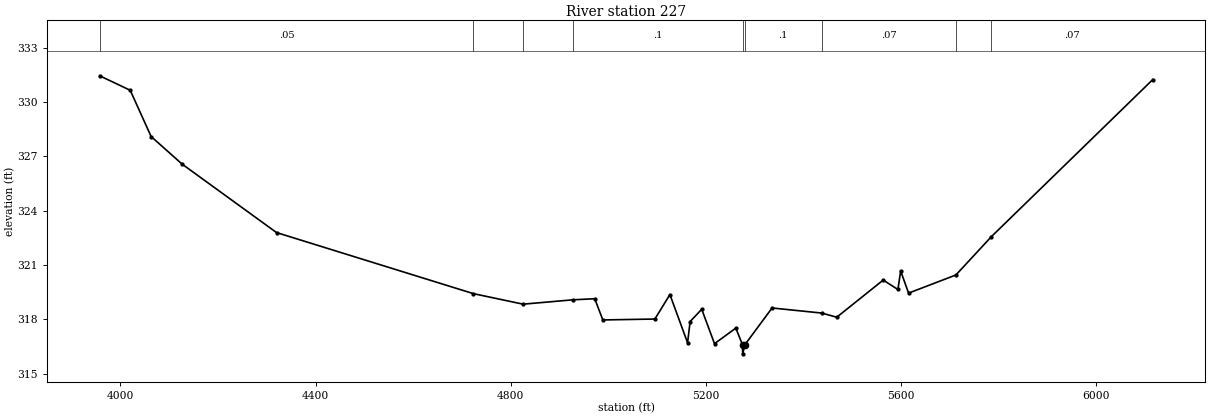
Type RM Length L Ch R = 1,227,0,0,0
BEGIN DESCRIPTION:
H21354
END DESCRIPTION:
XS GIS Cut Line= 4
      2538131.74     13806109.32      2538591.83     13805497.31
      2538483.33     13805041.58      2538040.64     13804230.00
#Sta/Elev= 30
  3957.3  331.44  4020.0  330.64  4062.8  328.09  4126.2  326.57  4319.9  322.79
  4723.5  319.42  4825.3  318.84  4927.2  319.08  4972.1  319.14  4988.7  317.97
  5095.4  318.02  5126.2  319.37  5162.4  316.71  5167.6  317.88  5191.4  318.56
  5217.6  316.66  5261.3  317.52  5275.0  316.60  5275.4  316.10  5279.8  316.60
  5335.6  318.63  5437.2  318.35  5468.2  318.12  5563.4  320.17  5593.5  319.65
  5599.2  320.67  5615.4  319.45  5712.4  320.45  5785.3  322.57  6115.9  331.23
#Mann=9,-1,0
  3957.3    0.05       0  4723.5   0.035       0  4825.3    0.12       0
  4927.2     0.1       0  5275.0    0.05       0  5279.8     0.1       0
  5437.2    0.07       0  5712.4    0.12       0  5785.3    0.07       0
Bank Sta=5275,5279.8
Exp/Cntr=0.3,0.1

Chan Stop Cuts=-1