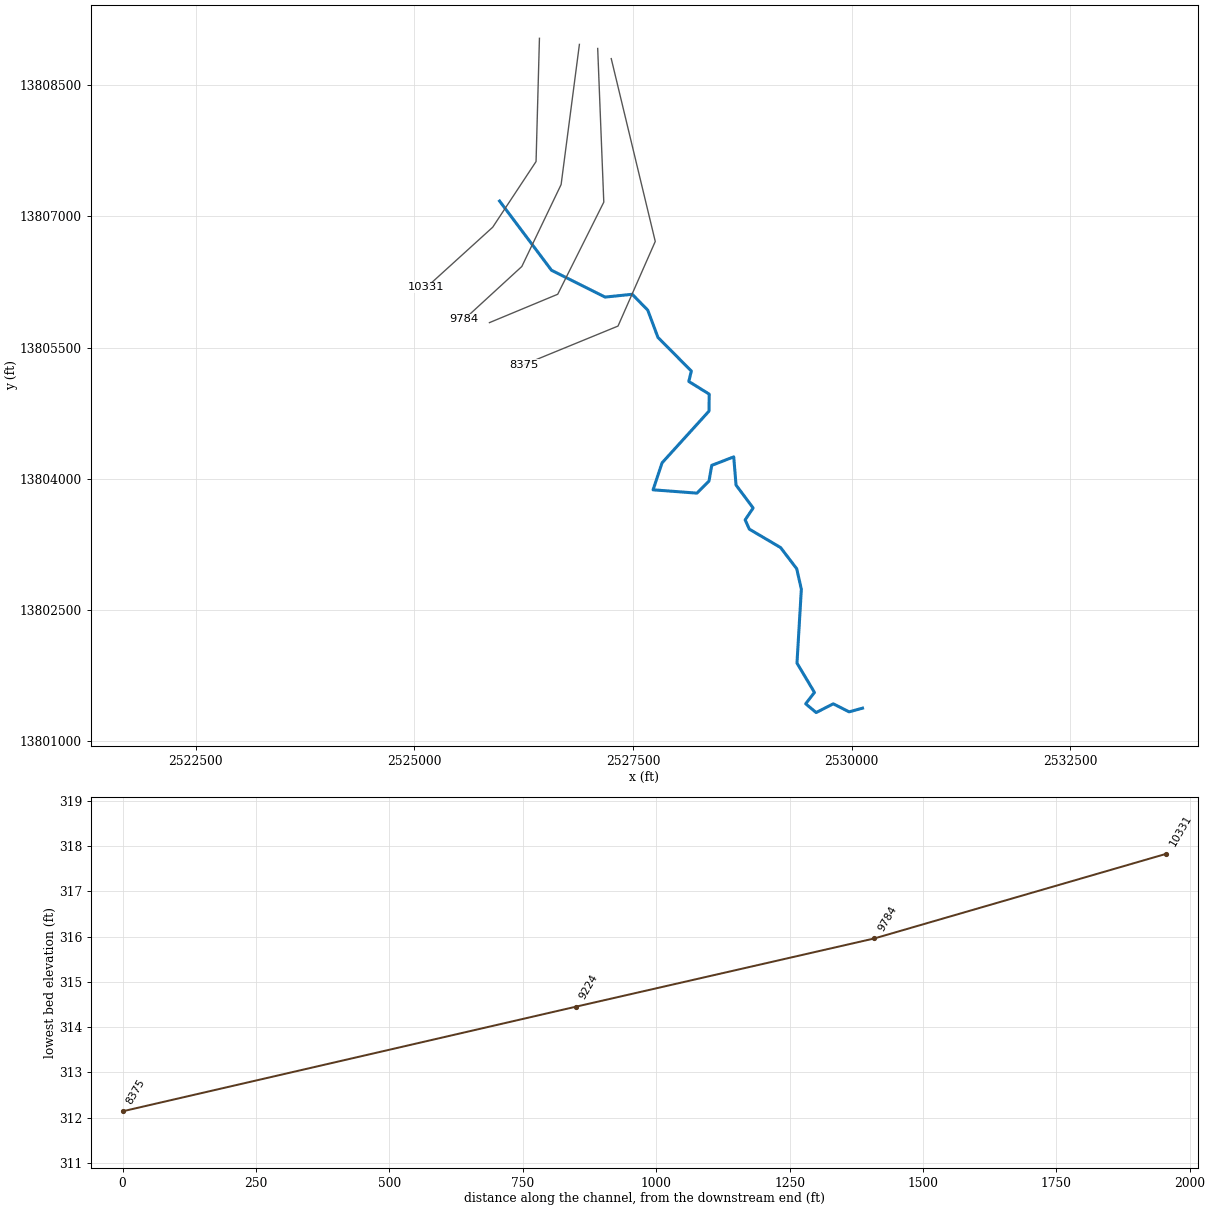
--- StreamM05.prj (project) ---

Proj Title=StreamM05 Base Level Engineering
Current Plan=p01
Default Exp/Contr=0.3,0.1
English Units
Geom File=g01
Flow File=f01
Plan File=p01
Y Axis Title=Elevation
X Axis Title(PF)=Main Channel Distance
X Axis Title(XS)=Station
BEGIN DESCRIPTION:
StreamM05
END DESCRIPTION:
DSS Export Rating Curves= 0
DSS Export Rating Curve Sorted= 0
DSS Export Volume Flow Curves= 0
DXF OffsetX= 0
DXF OffsetY= 0
DXF ScaleX= 1
DXF ScaleY= 10

--- StreamM05.p01 (plan) ---

Plan Title=Multiple Run
Short Identifier=Multiple
Geom File=g01
Flow File=f01
Subcritical Flow
K Sum by GR= 0
Std Step Tol= 0.01
Critical Tol= 0.01
Num of Std Step Trials= 20
Max Error Tol= 0.3
Flow Tol Ratio= 0.001
Split Flow NTrial= 30
Split Flow Tol= 0.02
Split Flow Ratio= 0.02
Log Output Level= 0
Friction Slope Method= 1
Unsteady Friction Slope Method= 2
Unsteady Bridges Friction Slope Method= 1
Parabolic Critical Depth
Global Vel Dist=  1 , 1 , 1
Global Log Level= 0
CheckData=True
Encroach Param= -1, 0, 0, 0
BEGIN DESCRIPTION:
Multiple Run
END DESCRIPTION:

--- StreamM05.f01 (steady flow) ---

Flow Title=Multiple
Number of Profiles=7
Profile Names=10-year,25-year,50-year,1pct_min,100-year,1pct_plu,500-year
River Rch & RM= StreamM05,Reach-1,10331
     671    1070    1427     921    1838    3668    3019
River Rch & RM= StreamM05,Reach-1,9784
     864    1387    1855    1199    2392    4773    3941
Boundary for River Rch & Prof#=StreamM05,Reach-1,1
Up Type=0
Dn Type=3
Dn Slope=0.005
Boundary for River Rch & Prof#=StreamM05,Reach-1,2
Up Type=0
Dn Type=3
Dn Slope=0.005
Boundary for River Rch & Prof#=StreamM05,Reach-1,3
Up Type=0
Dn Type=3
Dn Slope=0.005
Boundary for River Rch & Prof#=StreamM05,Reach-1,4
Up Type=0
Dn Type=3
Dn Slope=0.005
Boundary for River Rch & Prof#=StreamM05,Reach-1,5
Up Type=0
Dn Type=3
Dn Slope=0.005
Boundary for River Rch & Prof#=StreamM05,Reach-1,6
Up Type=0
Dn Type=3
Dn Slope=0.005
Boundary for River Rch & Prof#=StreamM05,Reach-1,7
Up Type=0
Dn Type=3
Dn Slope=0.005

--- StreamM05.g01 (geometry) ---

Geom Title=Existing Conditions
Program Version=4.10

River Reach=StreamM05       ,Reach-1
Reach XY= 30
        2525975.       13807175.      2526568.95     13806383.16
      2527181.11      13806076.8      2527491.76     13806108.57
      2527669.17      13805927.3      2527785.76     13805615.32
      2528167.48     13805231.04      2528138.53      13805111.6
      2528371.94     13804966.72      2528369.54     13804772.55
      2527833.16     13804181.05      2527730.35     13803872.23
      2528231.67      13803834.3      2528369.53     13803972.55
      2528401.03     13804152.19       2528652.3     13804249.16
      2528678.75     13803926.55      2528874.45     13803664.36
      2528782.78      13803528.4       2528830.7     13803422.46
       2529188.3      13803211.6      2529372.75     13802969.07
      2529425.45     13802735.19      2529375.52     13801890.22
      2529575.49     13801554.85        2529475.       13801425.
      2529595.05     13801324.77      2529790.22     13801424.76
      2529971.59     13801332.77        2530125.       13801375.

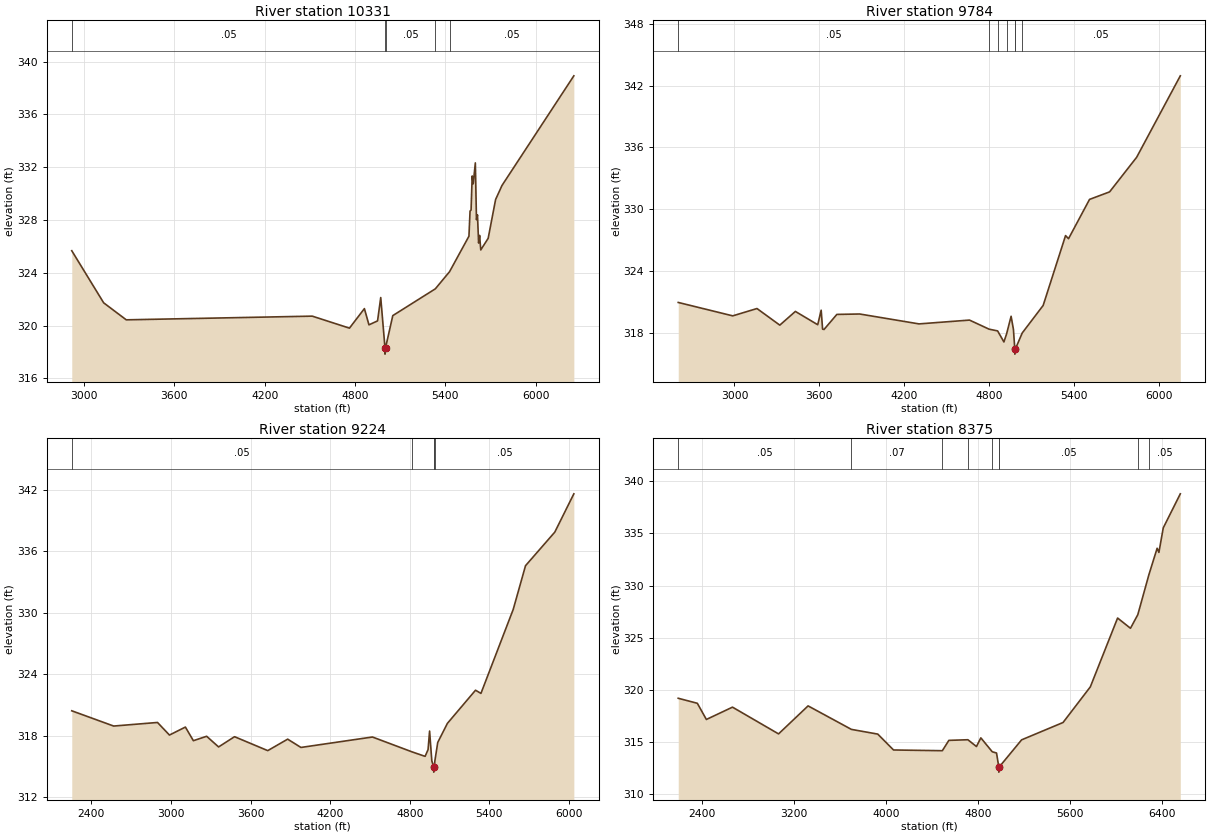
Type RM Length L Ch R = 1 ,10331   ,547,547,547
BEGIN DESCRIPTION:
H21359
END DESCRIPTION:
XS GIS Cut Line= 4
      2526430.72     13809036.69        2526392.     13807627.14
      2525896.33      13806875.9      2525138.66     13806187.81
#Sta/Elev= 30
  2919.3  325.67  3131.1  321.72  3281.1  320.43  4516.1  320.71    4763   319.8
  4862.3  321.28  4892.5  320.05  4949.7  320.35  4970.7  322.12  4998.8  318.33
  4999.1  317.83    5003  318.33  5050.8  320.75  5333.2  322.78  5427.7  324.08
  5556.4  326.77  5563.8  328.68  5570.5  328.75    5578  331.34  5584.7  330.74
  5598.9  332.33  5606.4  328.02  5613.1  328.39  5620.6  326.25  5627.3  326.83
  5634.8  325.73  5684.1  326.61  5733.4  329.55    5776  330.62  6252.9  338.93
#Mann= 5 ,-1 , 0
  2919.3     .05       0  4998.8     .05       0    5003     .05       0
  5333.2    .035       0  5427.7     .05       0
Bank Sta=4998.8,5003
XS Rating Curve= 0 ,0
Exp/Cntr=0.3,0.1

Type RM Length L Ch R = 1 ,9784    ,560,560,560
BEGIN DESCRIPTION:
H21358
END DESCRIPTION:
XS GIS Cut Line= 4
      2526887.67     13808967.02      2526678.55     13807363.82
      2526229.36     13806426.71      2525571.03     13805822.59
#Sta/Elev= 30
  2602.3  320.97  2987.6  319.67    3159  320.38  3320.4  318.77  3430.5   320.1
  3588.5  318.81  3612.8  320.22  3622.9  318.38    3633  318.35  3723.7  319.81
  3885.1  319.85  4304.6  318.89  4661.4  319.26  4799.8  318.38  4860.3  318.21
  4904.8  317.14  4923.6  317.92  4955.6  319.63  4971.9  318.37  4981.7  316.46
    4982  315.96  4985.9  316.46  5034.2  318.01  5182.2  320.68  5340.5  327.45
  5361.5  327.15  5510.1  330.96  5651.9  331.69    5843  335.04  6151.8  342.94
#Mann= 7 ,-1 , 0
  2602.3     .05       0  4799.8    .035       0  4860.3     .05       0
  4923.6    .035       0  4981.7    .035       0  4985.9    .035       0
  5034.2     .05       0
Bank Sta=4981.7,4985.9
XS Rating Curve= 0 ,0
Exp/Cntr=0.3,0.1

Type RM Length L Ch R = 1 ,9224    ,849,849,849
BEGIN DESCRIPTION:
H21357
END DESCRIPTION:
XS GIS Cut Line= 4
      2527096.77     13808920.47      2527166.47     13807162.46
      2526639.83     13806109.17      2525858.77     13805784.38
#Sta/Elev= 30
  2253.3  320.44    2569  318.95  2899.3   319.3  2989.4  318.07  3109.4  318.85
  3169.5  317.52  3269.6  317.95  3359.6  316.91  3479.7  317.91  3729.9  316.55
    3880  317.67  3980.1  316.86  4518.8  317.88  4818.9  316.42  4915.5  315.99
  4937.8  316.65  4949.3  318.46    4966  315.56  4980.4  314.95  4980.7  314.45
  4984.7  314.95  4989.6  315.59  5010.8  317.35  5083.4  319.21  5295.4  322.45
  5336.3  322.14  5579.4  330.34  5672.1  334.61  5892.7  337.89  6036.2  341.63
#Mann= 5 ,-1 , 0
  2253.3     .05       0  4818.9     .12       0  4980.4     .05       0
  4984.7     .12       0  4989.6     .05       0
Bank Sta=4980.4,4984.7
XS Rating Curve= 0 ,0
Exp/Cntr=0.3,0.1

Type RM Length L Ch R = 1 ,8375    ,0,0,0
BEGIN DESCRIPTION:
H21356
END DESCRIPTION:
XS GIS Cut Line= 4
      2527251.67     13808804.31      2527755.07     13806713.26
      2527329.11     13805745.17      2526252.56     13805303.71
#Sta/Elev= 30
  2190.5  319.21  2356.9  318.73  2435.6  317.18  2662.9  318.36  3064.1   315.8
  3321.2  318.48  3698.5  316.23  3928.1  315.78  4065.1  314.26  4490.3  314.19
    4547  315.18  4712.8  315.24  4787.3  314.59  4825.6  315.42  4924.8  314.09
  4962.1  313.97  4981.8  312.64  4982.1  312.14  4986.2  312.64  5180.6  315.23
  5541.4  316.89  5778.9   320.3  6016.4  326.89  6128.6  325.91  6192.4  327.21
  6288.8  331.03  6360.7  333.57  6376.1  333.17    6414  335.52  6562.5  338.78
#Mann= 9 ,-1 , 0
  2190.5     .05       0  3698.5     .07       0  4490.3     .05       0
  4712.8     .07       0  4924.8     .05       0  4981.8     .05       0
  4986.2     .05       0  6192.4    .035       0  6288.8     .05       0
Bank Sta=4981.8,4986.2
XS Rating Curve= 0 ,0
Exp/Cntr=0.3,0.1

Chan Stop Cuts=-1
Use User Specified Reach Order=0
Composite Channel Slope=5