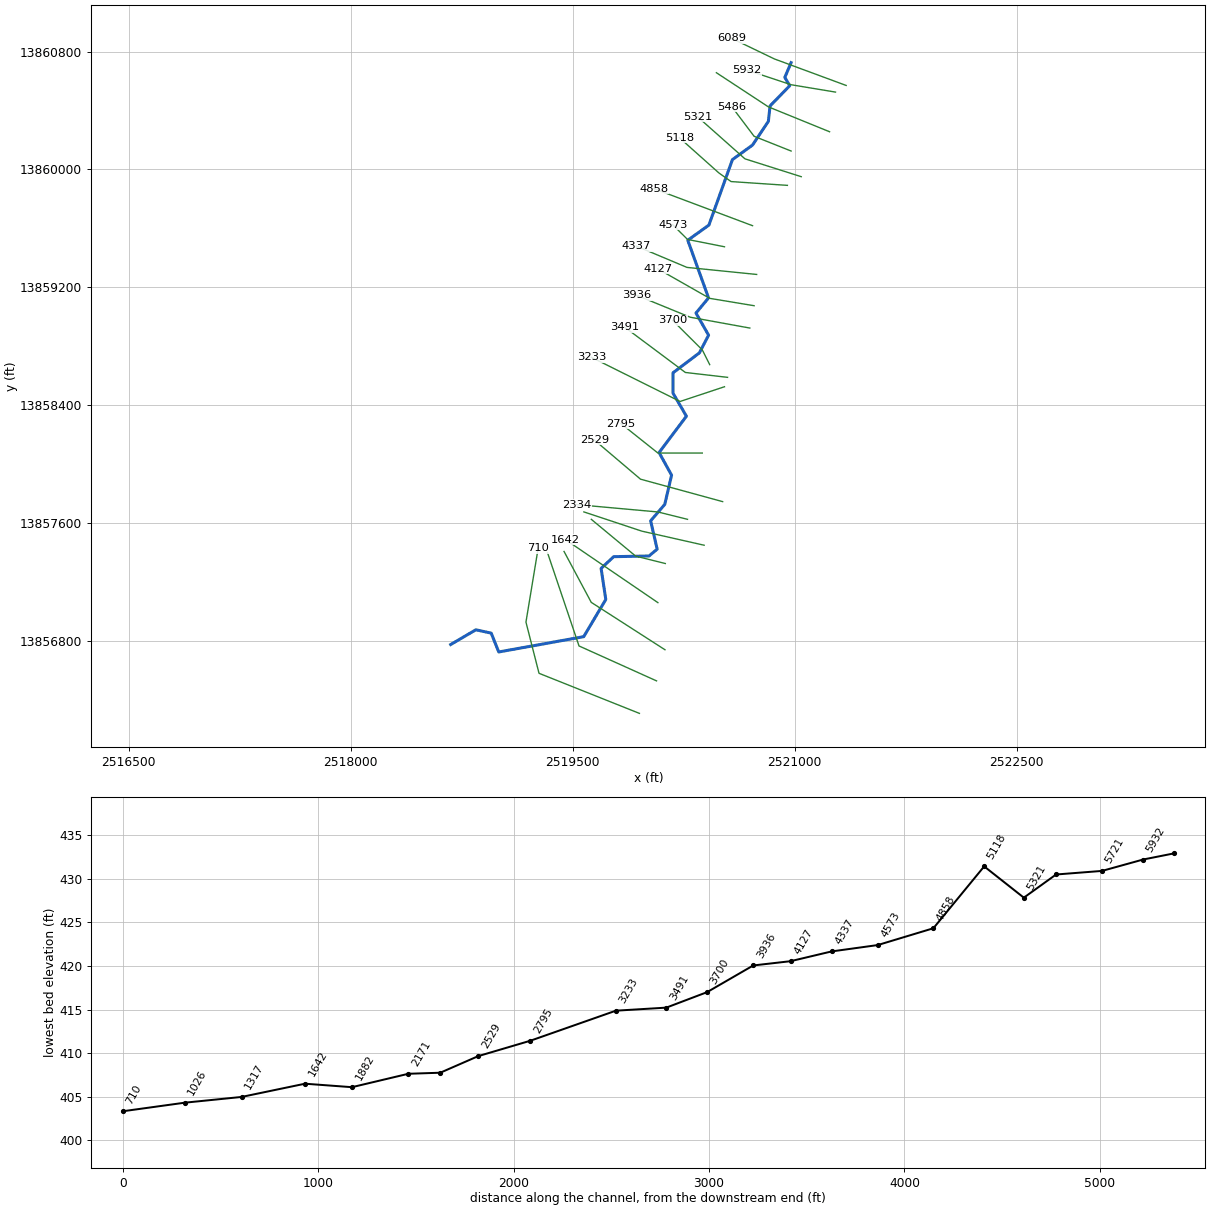
--- StreamM050.prj (project) ---

Proj Title=StreamM050 Base Level Engineering
Current Plan=p01
Default Exp/Contr=0.3,0.1
English Units
Geom File=g01
Flow File=f01
Plan File=p01
BEGIN DESCRIPTION:
StreamM050
END DESCRIPTION:

--- StreamM050.p01 (plan) ---

Plan Title=Multiple Run
Short Identifier=Multiple
Geom File=g01
Flow File=f01
Subcritical Flow
K Sum by GR= 0
Std Step Tol= 0.01
Critical Tol= 0.01
Num of Std Step Trials= 20
Max Error Tol= 0.3
Flow Tol Ratio= 0.001
Split Flow NTrial= 30
Split Flow Tol= 0.02
Split Flow Ratio= 0.02
Log Output Level= 0
Friction Slope Method= 1
Unsteady Friction Slope Method= 2
Unsteady Bridges Friction Slope Method= 1
Parabolic Critical Depth
Global Vel Dist=  1 , 1 , 1
Global Log Level= 0
CheckData=True
Encroach Param= -1, 0, 0, 0
BEGIN DESCRIPTION:
Multiple Run
END DESCRIPTION:

--- StreamM050.f01 (steady flow) ---

Flow Title=Multiple
Number of Profiles=7
Profile Names=10-year,25-year,50-year,1pct_min,100-year,1pct_plu,500-year
River Rch & RM= StreamM050,Reach-1,6089
     397     615     804     510    1018    2032    1613
Boundary for River Rch & Prof#=StreamM050,Reach-1,1
Up Type=0
Dn Type=3
Dn Slope=0.005
Boundary for River Rch & Prof#=StreamM050,Reach-1,2
Up Type=0
Dn Type=3
Dn Slope=0.005
Boundary for River Rch & Prof#=StreamM050,Reach-1,3
Up Type=0
Dn Type=3
Dn Slope=0.005
Boundary for River Rch & Prof#=StreamM050,Reach-1,4
Up Type=0
Dn Type=3
Dn Slope=0.005
Boundary for River Rch & Prof#=StreamM050,Reach-1,5
Up Type=0
Dn Type=3
Dn Slope=0.005
Boundary for River Rch & Prof#=StreamM050,Reach-1,6
Up Type=0
Dn Type=3
Dn Slope=0.005
Boundary for River Rch & Prof#=StreamM050,Reach-1,7
Up Type=0
Dn Type=3
Dn Slope=0.005

--- StreamM050.g01 (geometry) ---

Geom Title=Existing Conditions

River Reach=StreamM050,Reach-1
Reach XY= 30
      2520975.00     13860725.00      2520932.58     13860624.93
      2520965.72     13860568.33      2520832.86     13860431.17
      2520821.37     13860326.50      2520714.23     13860165.30
      2520578.51     13860066.52      2520419.58     13859622.33
      2520276.89     13859519.29      2520417.11     13859128.21
      2520332.31     13859025.09      2520417.50     13858875.00
      2520355.24     13858754.87      2520176.97     13858619.32
      2520177.23     13858480.93      2520267.71     13858324.91
      2520083.02     13858078.31      2520167.47     13857925.01
      2520121.44     13857726.47      2520025.94     13857614.52
      2520070.03     13857422.41      2520014.76     13857375.99
      2519776.44     13857371.46      2519691.28     13857291.74
      2519722.94     13857080.86      2519573.75     13856828.51
      2518999.61     13856724.59      2518949.00     13856852.35
      2518845.06     13856875.22      2518675.00     13856775.00

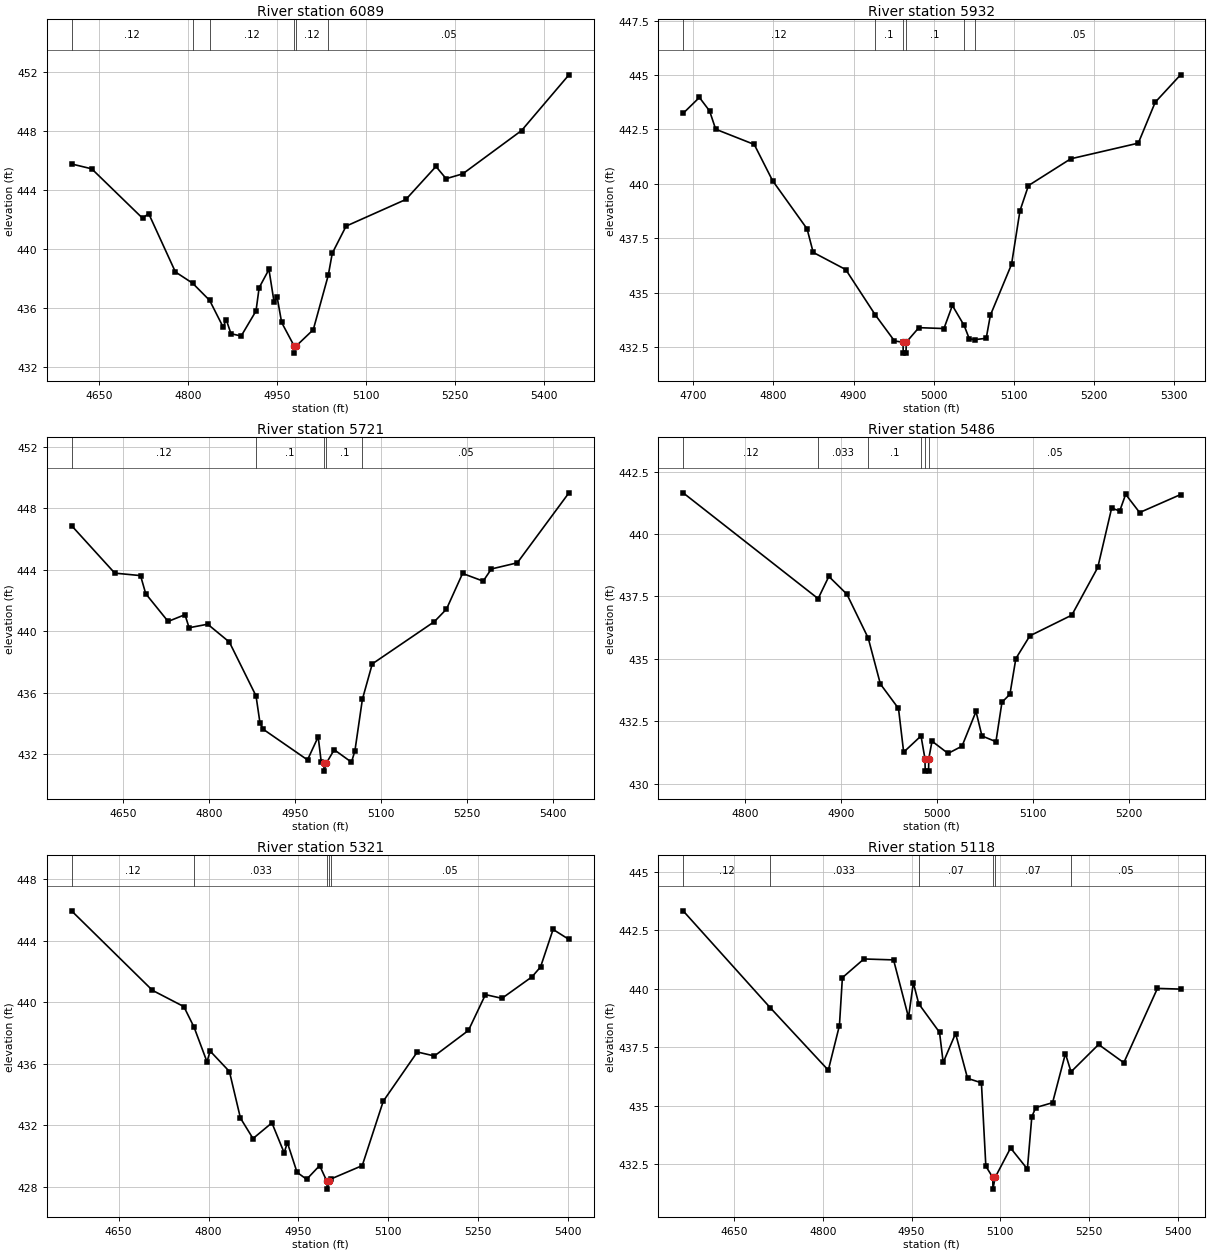
Type RM Length L Ch R = 1,6089,157,157,157
BEGIN DESCRIPTION:
H21372
END DESCRIPTION:
XS GIS Cut Line= 3
      2521346.85     13860570.17      2520861.66     13860750.27
      2520573.13     13860889.94
#Sta/Elev= 30
  4603.7  445.76  4637.7  445.43  4723.3  442.08  4733.7  442.39  4778.7  438.43
  4807.6  437.67  4836.4  436.50  4859.1  434.69  4864.4  435.19  4872.3  434.24
  4889.5  434.08  4914.5  435.78  4919.8  437.36  4936.3  438.60  4944.9  436.40
  4950.2  436.70  4957.7  435.00  4978.6  433.42  4978.8  432.92  4982.6  433.42
  5011.0  434.51  5036.3  438.21  5043.0  439.70  5066.3  441.54  5167.0  443.35
  5217.7  445.59  5234.8  444.76  5262.9  445.09  5362.0  448.03  5441.8  451.81
#Mann=6,-1,0
  4603.7    0.12       0  4807.6     0.1       0  4836.4    0.12       0
  4978.6    0.05       0  4982.6    0.12       0  5036.3    0.05       0
Bank Sta=4978.6,4982.6
Exp/Cntr=0.3,0.1

Type RM Length L Ch R = 1,5932,211,211,211
BEGIN DESCRIPTION:
StreamM050 10.0
END DESCRIPTION:
XS GIS Cut Line= 3
      2521275.03     13860524.99      2520975.00     13860575.00
      2520675.00     13860675.00
#Sta/Elev= 30
  4687.4  443.24  4707.7  443.97  4720.4  443.35  4728.0  442.51  4776.1  441.81
  4798.9  440.15  4842.0  437.93  4849.6  436.85  4890.2  436.06  4927.2  433.97
  4951.0  432.78  4961.7  432.72  4961.9  432.22  4965.4  432.22  4965.7  432.72
  4981.4  433.39  5012.7  433.35  5023.2  434.41  5037.9  433.49  5044.3  432.88
  5050.9  432.84  5065.4  432.90  5070.6  433.96  5097.0  436.30  5107.5  438.76
  5118.1  439.92  5170.8  441.15  5255.1  441.87  5276.2  443.75  5307.8  445.01
#Mann=6,-1,0
  4687.4    0.12       0  4927.2     0.1       0  4961.7    0.05       0
  4965.7     0.1       0  5037.9    0.12       0  5050.9    0.05       0
Bank Sta=4961.7,4965.7
Exp/Cntr=0.3,0.1

Type RM Length L Ch R = 1,5721,235,235,235
BEGIN DESCRIPTION:
H21371
END DESCRIPTION:
XS GIS Cut Line= 3
      2521234.77     13860255.85      2520821.23     13860424.94
      2520470.12     13860656.56
#Sta/Elev= 30
  4560.7  446.87  4636.1  443.78  4681.0  443.62  4690.1  442.44  4729.1  440.64
  4758.5  441.08  4765.7  440.23  4798.1  440.46  4835.9  439.30  4882.4  435.80
  4889.4  434.02  4895.4  433.62  4972.2  431.64  4990.8  433.14  4996.2  431.48
  5000.7  431.41  5001.0  430.91  5004.7  431.41  5018.8  432.30  5048.9  431.49
  5054.9  432.24  5067.9  435.58  5085.1  437.88  5193.5  440.63  5214.5  441.44
  5242.6  443.76  5278.5  443.26  5292.8  444.05  5338.0  444.45  5428.1  449.00
#Mann=5,-1,0
  4560.7    0.12       0  4882.4     0.1       0  5000.7    0.05       0
  5004.7     0.1       0  5067.9    0.05       0
Bank Sta=5000.7,5004.7
Exp/Cntr=0.3,0.1

Type RM Length L Ch R = 1,5486,165,165,165
BEGIN DESCRIPTION:
StreamM050 9.0
END DESCRIPTION:
XS GIS Cut Line= 3
      2520974.96     13860125.01      2520725.00     13860225.00
      2520575.01     13860424.98
#Sta/Elev= 30
  4735.1  441.65  4876.0  437.41  4887.2  438.30  4906.0  437.59  4928.3  435.83
  4941.0  433.99  4959.9  433.01  4965.3  431.26  4983.4  431.91  4987.5  431.00
  4987.8  430.50  4991.3  430.50  4991.5  431.00  4994.9  431.70  5011.6  431.21
  5026.2  431.50  5040.8  432.89  5047.0  431.91  5061.6  431.68  5067.9  433.26
  5076.2  433.58  5082.4  435.01  5097.0  435.92  5140.8  436.75  5167.9  438.66
  5182.4  441.04  5190.8  440.92  5197.0  441.59  5211.6  440.86  5254.3  441.58
#Mann=6,-1,0
  4735.1    0.12       0  4876.0   0.033       0  4928.3     0.1       0
  4983.4    0.05       0  4987.5    0.05       0  4991.5    0.05       0
Bank Sta=4987.5,4991.5
Exp/Cntr=0.3,0.1

Type RM Length L Ch R = 1,5321,203,203,203
BEGIN DESCRIPTION:
H21370
END DESCRIPTION:
XS GIS Cut Line= 3
      2521043.60     13859950.74      2520663.16     13860072.04
      2520341.51     13860358.77
#Sta/Elev= 30
  4571.4  445.94  4706.4  440.77  4758.9  439.71  4775.9  438.37  4797.5  436.12
  4802.7  436.82  4834.9  435.49  4853.3  432.46  4874.3  431.13  4905.8  432.15
  4926.3  430.20  4931.6  430.87  4947.8  428.93  4963.8  428.48  4985.5  429.37
  4997.7  428.34  4998.0  427.84  5001.7  428.34  5003.7  428.49  5056.6  429.37
  5091.7  433.56  5148.5  436.76  5177.0  436.50  5233.8  438.16  5262.2  440.49
  5289.8  440.25  5340.0  441.65  5354.2  442.29  5375.1  444.73  5401.6  444.08
#Mann=5,-1,0
  4571.4    0.12       0  4775.9   0.033       0  4997.7   0.033       0
  5001.7   0.033       0  5003.7    0.05       0
Bank Sta=4997.7,5001.7
Exp/Cntr=0.3,0.1

Type RM Length L Ch R = 1,5118,260,260,260
BEGIN DESCRIPTION:
StreamM050 8.0
END DESCRIPTION:
XS GIS Cut Line= 4
      2520949.89     13859891.92      2520569.42     13859917.65
      2520486.71     13859976.47      2520220.17     13860215.43
#Sta/Elev= 30
  4563.9  443.34  4710.9  439.20  4809.3  436.52  4828.1  438.43  4833.1  440.48
  4869.5  441.28  4919.6  441.24  4944.9  438.78  4953.0  440.26  4962.2  439.36
  4997.3  438.14  5003.5  436.85  5024.4  438.09  5044.7  436.17  5068.1  435.98
  5075.6  432.41  5087.3  431.93  5087.6  431.43  5091.3  431.93  5117.4  433.19
  5145.8  432.29  5153.3  434.53  5160.0  434.92  5188.4  435.13  5210.1  437.23
  5219.6  436.45  5266.2  437.62  5308.8  436.84  5365.6  440.02  5404.7  439.99
#Mann=6,-1,0
  4563.9    0.12       0  4710.9   0.033       0  4962.2    0.07       0
  5087.3    0.05       0  5091.3    0.07       0  5219.6    0.05       0
Bank Sta=5087.3,5091.3
Exp/Cntr=0.3,0.1

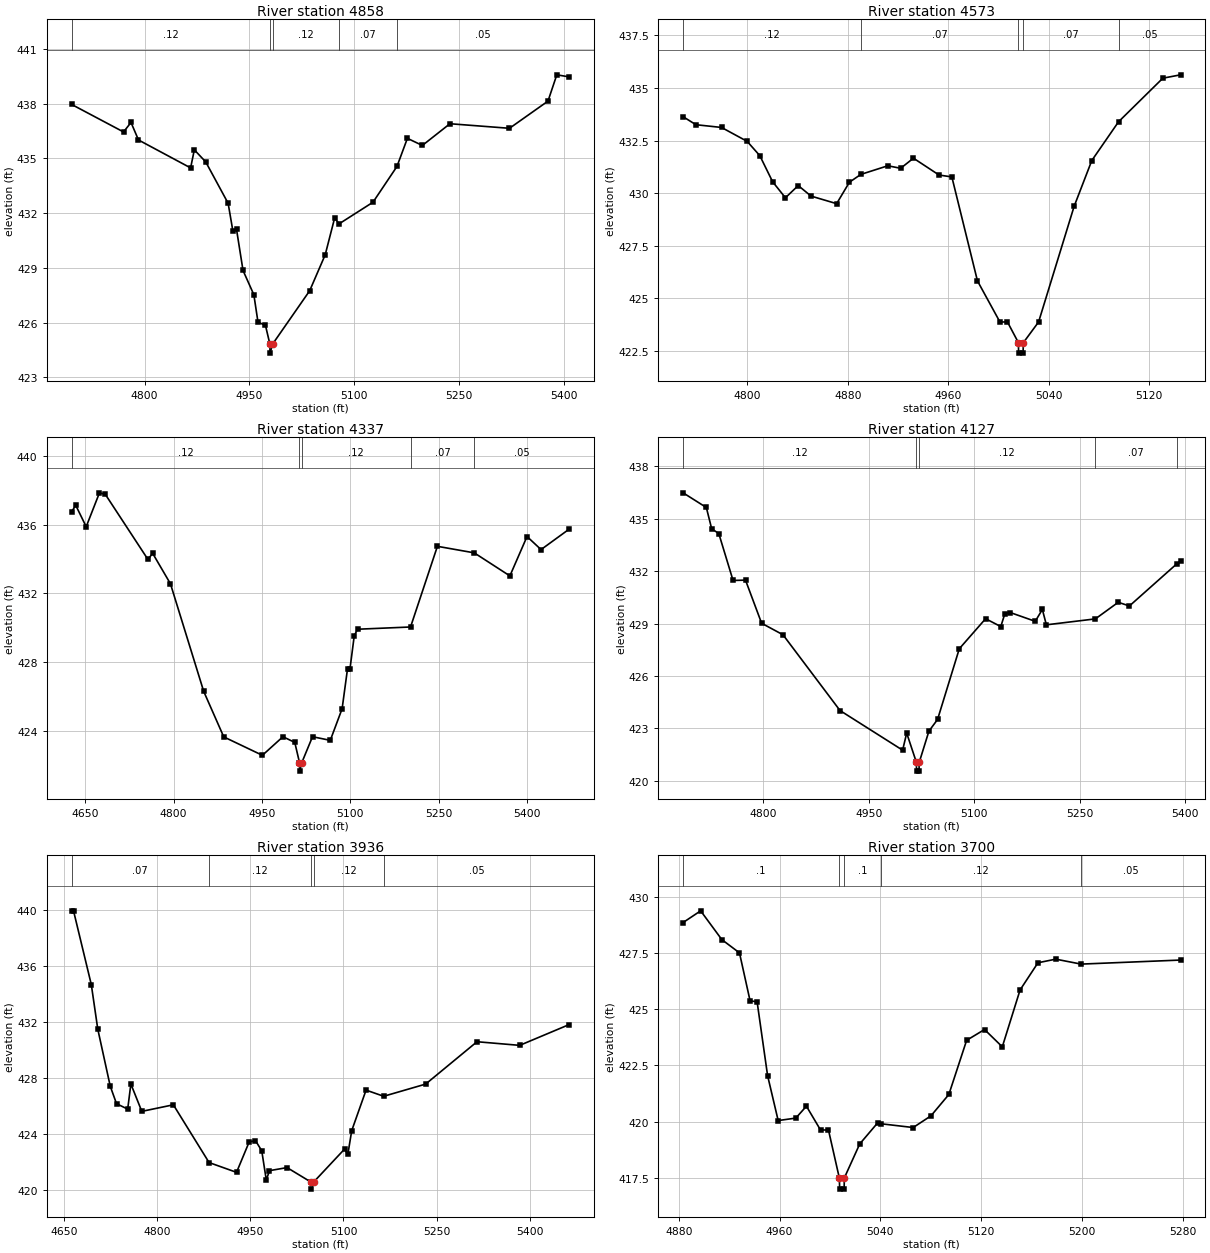
Type RM Length L Ch R = 1,4858,285,285,285
BEGIN DESCRIPTION:
H21369
END DESCRIPTION:
XS GIS Cut Line= 2
      2520714.63     13859618.05      2520048.68     13859869.38
#Sta/Elev= 30
  4695.4  437.96  4769.8  436.45  4780.5  436.97  4791.2  436.01  4865.8  434.48
  4871.1  435.47  4887.4  434.81  4919.5  432.54  4926.2  431.04  4931.5  431.11
  4940.8  428.86  4956.3  427.53  4962.2  426.03  4972.9  425.85  4979.2  424.83
  4979.4  424.33  4983.2  424.83  5036.2  427.75  5058.4  429.72  5071.8  431.72
  5078.5  431.42  5126.8  432.60  5161.1  434.56  5176.0  436.10  5197.4  435.71
  5236.9  436.90  5322.1  436.65  5377.2  438.14  5389.8  439.58  5407.2  439.47
#Mann=5,-1,0
  4695.4    0.12       0  4979.2    0.05       0  4983.2    0.12       0
  5078.5    0.07       0  5161.1    0.05       0
Bank Sta=4979.2,4983.2
Exp/Cntr=0.3,0.1

Type RM Length L Ch R = 1,4573,236,236,236
BEGIN DESCRIPTION:
StreamM050 7.0
END DESCRIPTION:
XS GIS Cut Line= 3
      2520524.96     13859475.01      2520275.00     13859525.00
      2520175.02     13859624.98
#Sta/Elev= 30
  4748.8  433.63  4759.0  433.25  4779.4  433.12  4799.8  432.46  4809.9  431.78
  4820.1  430.54  4830.3  429.78  4840.5  430.36  4850.7  429.86  4871.1  429.50
  4881.3  430.52  4890.4  430.89  4911.9  431.30  4922.1  431.18  4932.3  431.66
  4952.7  430.86  4962.9  430.77  4983.3  425.83  5001.2  423.88  5007.2  423.88
  5015.9  422.90  5016.1  422.40  5019.6  422.40  5019.9  422.90  5032.0  423.88
  5060.3  429.37  5074.4  431.55  5095.7  433.39  5131.0  435.46  5145.1  435.62
#Mann=5,-1,0
  4748.8    0.12       0  4890.4    0.07       0  5015.9    0.05       0
  5019.9    0.07       0  5095.7    0.05       0
Bank Sta=5015.9,5019.9
Exp/Cntr=0.3,0.1

Type RM Length L Ch R = 1,4337,210,210,210
BEGIN DESCRIPTION:
H21368
END DESCRIPTION:
XS GIS Cut Line= 3
      2520742.14     13859287.21      2520271.66     13859335.00
      2519929.17     13859479.68
#Sta/Elev= 30
  4626.7  436.75  4633.9  437.12  4651.6  435.88  4674.1  437.85  4684.1  437.76
  4756.4  433.98  4764.5  434.33  4794.7  432.56  4851.1  426.31  4885.2  423.66
  4950.8  422.59  4985.7  423.67  5005.8  423.34  5013.8  422.17  5014.1  421.67
  5017.8  422.17  5035.9  423.67  5066.1  423.46  5086.2  425.30  5095.4  427.63
  5099.6  427.63  5106.8  429.54  5112.4  429.92  5202.4  430.05  5248.0  434.74
  5310.6  434.36  5371.1  433.02  5400.2  435.31  5424.0  434.55  5471.4  435.73
#Mann=5,-1,0
  4626.7    0.12       0  5013.8    0.05       0  5017.8    0.12       0
  5202.4    0.07       0  5310.6    0.05       0
Bank Sta=5013.8,5017.8
Exp/Cntr=0.3,0.1

Type RM Length L Ch R = 1,4127,191,191,191
BEGIN DESCRIPTION:
StreamM050 6.0
END DESCRIPTION:
XS GIS Cut Line= 3
      2520725.03     13859074.99      2520425.00     13859125.00
      2520074.99     13859325.01
#Sta/Elev= 30
  4685.9  436.49  4718.9  435.65  4726.5  434.43  4736.6  434.16  4756.9  431.47
  4774.6  431.49  4797.5  429.02  4827.9  428.36  4909.0  424.02  4998.0  421.75
  5003.8  422.73  5017.6  421.05  5017.8  420.55  5021.3  420.55  5021.6  421.05
  5035.4  422.84  5047.7  423.51  5078.6  427.56  5116.0  429.28  5137.6  428.83
  5143.4  429.57  5151.3  429.63  5186.6  429.13  5196.7  429.81  5202.4  428.93
  5272.1  429.27  5304.6  430.22  5320.5  430.01  5387.5  432.41  5393.2  432.58
#Mann=5,-1,0
  4685.9    0.12       0  5017.6    0.05       0  5021.6    0.12       0
  5272.1    0.07       0  5387.5    0.05       0
Bank Sta=5017.6,5021.6
Exp/Cntr=0.3,0.1

Type RM Length L Ch R = 1,3936,236,236,236
BEGIN DESCRIPTION:
H21367
END DESCRIPTION:
XS GIS Cut Line= 3
      2520696.25     13858923.28      2520293.71     13858996.80
      2519931.62     13859145.68
#Sta/Elev= 30
  4662.3  439.96  4665.5  439.96  4694.1  434.69  4704.5  431.51  4724.6  427.42
  4734.7  426.17  4752.7  425.78  4757.8  427.58  4775.4  425.62  4826.2  426.09
  4883.7  421.96  4927.9  421.26  4948.2  423.43  4958.4  423.53  4968.5  422.80
  4975.8  420.71  4980.9  421.38  5009.2  421.60  5047.9  420.56  5048.1  420.06
  5051.9  420.56  5101.7  422.92  5107.1  422.55  5113.3  424.24  5136.4  427.14
  5164.8  426.70  5232.3  427.57  5315.0  430.60  5383.7  430.34  5463.0  431.82
#Mann=5,-1,0
  4662.3    0.07       0  4883.7    0.12       0  5047.9    0.05       0
  5051.9    0.12       0  5164.8    0.05       0
Bank Sta=5047.9,5051.9
Exp/Cntr=0.3,0.1

Type RM Length L Ch R = 1,3700,209,209,209
BEGIN DESCRIPTION:
StreamM050 5.0
END DESCRIPTION:
XS GIS Cut Line= 3
      2520424.99     13858675.03      2520375.00     13858775.00
      2520175.01     13858974.99
#Sta/Elev= 30
  4883.5  428.86  4897.4  429.38  4914.2  428.10  4928.2  427.51  4936.6  425.38
  4942.2  425.33  4950.5  422.05  4958.9  420.05  4972.9  420.16  4981.3  420.69
  4992.5  419.63  4998.8  419.63  5007.4  417.50  5007.7  417.00  5011.2  417.00
  5011.4  417.50  5023.6  419.01  5037.7  419.94  5040.1  419.91  5066.0  419.74
  5080.1  420.26  5094.3  421.21  5108.4  423.62  5122.6  424.10  5136.7  423.33
  5150.8  425.86  5165.0  427.07  5179.1  427.23  5199.2  427.01  5278.1  427.19
#Mann=5,-1,0
  4883.5     0.1       0  5007.4    0.05       0  5011.4     0.1       0
  5040.1    0.12       0  5199.2    0.05       0
Bank Sta=5007.4,5011.4
Exp/Cntr=0.3,0.1

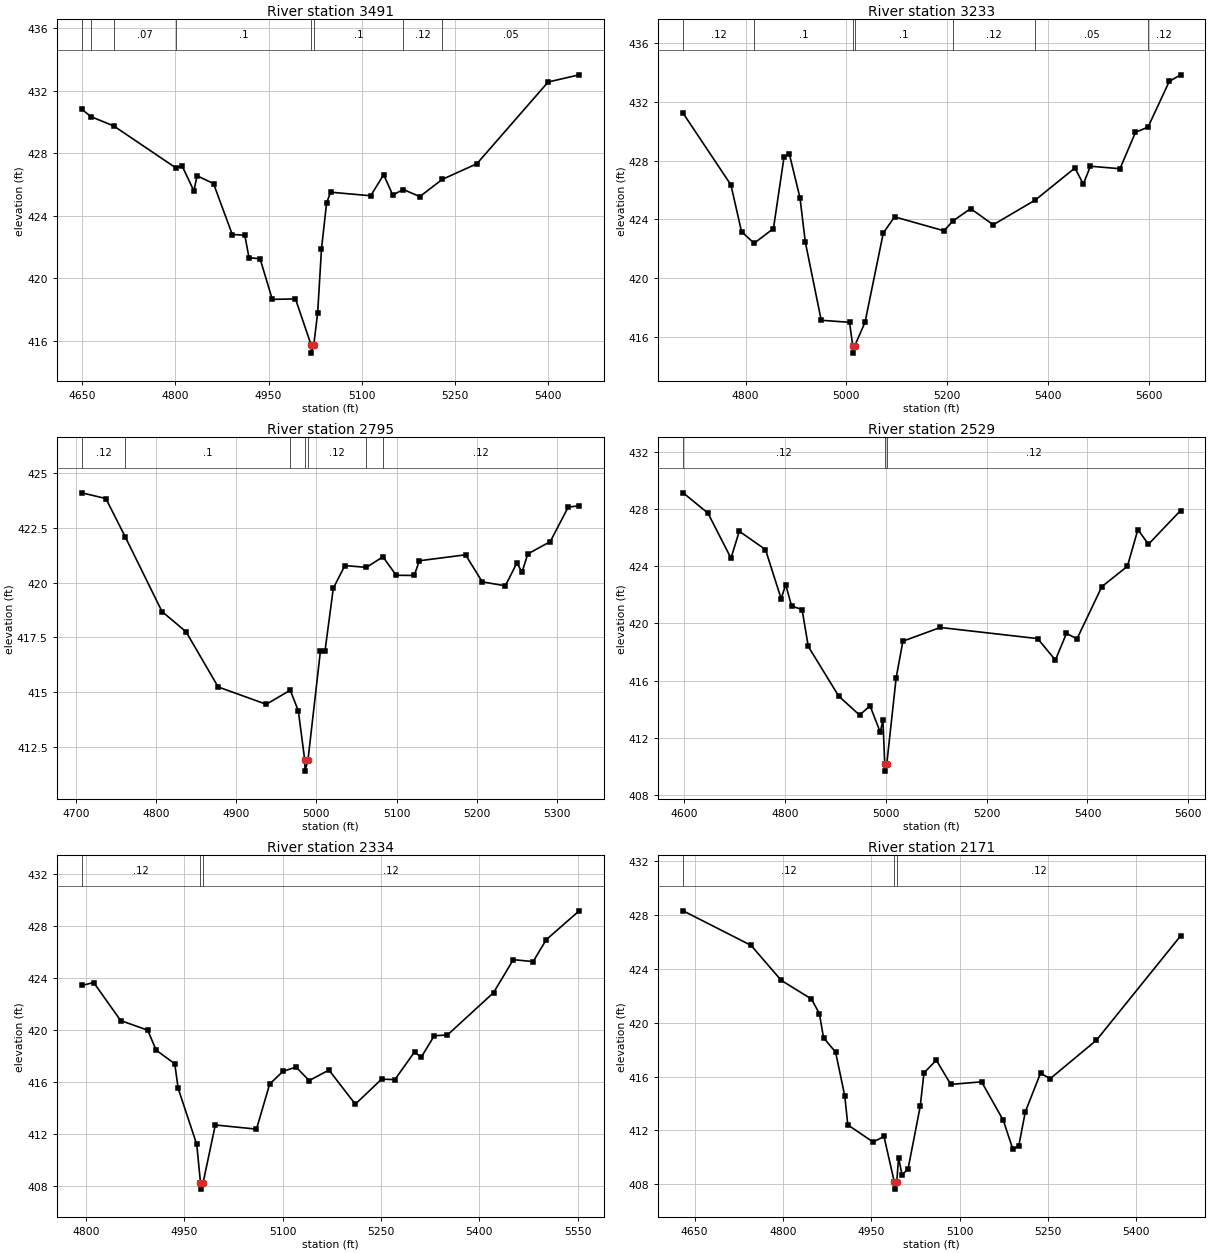
Type RM Length L Ch R = 1,3491,258,258,258
BEGIN DESCRIPTION:
H21366
END DESCRIPTION:
XS GIS Cut Line= 3
      2520545.49     13858588.76      2520260.63     13858621.84
      2519849.89     13858929.89
#Sta/Elev= 30
  4649.5  430.82  4664.5  430.35  4700.8  429.76  4800.3  427.09  4811.1  427.18
  4829.9  425.60  4834.9  426.57  4861.4  426.07  4891.6  422.81  4911.7  422.77
  4918.5  421.33  4936.3  421.26  4956.0  418.66  4993.3  418.69  5018.6  415.72
  5018.8  415.22  5022.6  415.72  5028.9  417.77  5035.1  421.88  5043.3  424.82
  5049.7  425.52  5114.3  425.29  5135.1  426.64  5149.7  425.34  5166.7  425.69
  5193.3  425.24  5229.5  426.34  5285.1  427.34  5399.7  432.57  5449.7  433.03
#Mann=8,-1,0
  4649.5    0.07       0  4664.5    0.12       0  4700.8    0.07       0
  4800.3     0.1       0  5018.6    0.05       0  5022.6     0.1       0
  5166.7    0.12       0  5229.5    0.05       0
Bank Sta=5018.6,5022.6
Exp/Cntr=0.3,0.1

Type RM Length L Ch R = 1,3233,438,438,438
BEGIN DESCRIPTION:
StreamM050 4.0
END DESCRIPTION:
XS GIS Cut Line= 3
      2520524.96     13858524.99      2520225.00     13858425.00
      2519625.01     13858725.00
#Sta/Elev= 30
  4676.1  431.22  4770.9  426.34  4792.0  423.15  4817.0  422.36  4855.3  423.36
  4876.3  428.23  4886.9  428.44  4908.0  425.45  4918.5  422.45  4950.1  417.11
  5006.3  416.97  5012.6  415.37  5012.9  414.87  5016.6  415.37  5037.0  416.97
  5073.3  423.06  5095.7  424.16  5193.5  423.21  5211.9  423.89  5246.6  424.72
  5291.4  423.62  5375.1  425.31  5453.5  427.49  5470.2  426.39  5484.2  427.61
  5542.9  427.44  5573.7  429.92  5598.6  430.28  5640.7  433.39  5663.1  433.84
#Mann=7,-1,0
  4676.1    0.12       0  4817.0     0.1       0  5012.6    0.05       0
  5016.6     0.1       0  5211.9    0.12       0  5375.1    0.05       0
  5598.6    0.12       0
Bank Sta=5012.6,5016.6
Exp/Cntr=0.3,0.1

Type RM Length L Ch R = 1,2795,266,266,266
BEGIN DESCRIPTION:
StreamM050 3.0
END DESCRIPTION:
XS GIS Cut Line= 3
      2520375.00     13858075.00      2520075.00     13858075.00
      2519824.97     13858275.03
#Sta/Elev= 30
  4707.5  424.08  4737.5  423.82  4761.5  422.09  4807.5  418.68  4837.5  417.76
  4877.5  415.25  4937.5  414.46  4967.4  415.10  4977.5  414.16  4985.5  411.92
  4985.8  411.42  4989.5  411.92  5005.0  416.87  5010.7  416.87  5021.1  419.74
  5035.5  420.77  5062.4  420.69  5083.0  421.17  5099.5  420.33  5122.0  420.32
  5128.4  420.99  5186.0  421.26  5206.8  420.03  5235.6  419.85  5250.0  420.89
  5256.4  420.47  5263.6  421.30  5291.6  421.86  5314.0  423.43  5327.7  423.49
#Mann=7,-1,0
  4707.5    0.12       0  4761.5     0.1       0  4967.4    0.12       0
  4985.5    0.05       0  4989.5    0.12       0  5062.4     0.1       0
  5083.0    0.12       0
Bank Sta=4985.5,4989.5
Exp/Cntr=0.3,0.1

Type RM Length L Ch R = 1,2529,195,195,195
BEGIN DESCRIPTION:
H21365
END DESCRIPTION:
XS GIS Cut Line= 3
      2520512.44     13857745.11      2519957.35     13857897.66
      2519644.85     13858164.21
#Sta/Elev= 30
  4598.2  429.13  4647.4  427.71  4693.1  424.56  4709.6  426.44  4761.5  425.16
  4792.6  421.72  4801.6  422.71  4813.3  421.21  4834.1  420.96  4846.4  418.38
  4906.7  414.91  4948.1  413.58  4968.9  414.23  4989.2  412.37  4994.4  413.27
  4998.0  410.16  4998.3  409.66  5002.0  410.16  5020.7  416.20  5034.0  418.75
  5108.1  419.71  5301.3  418.93  5336.4  417.43  5358.4  419.30  5379.2  418.91
  5428.6  422.57  5479.2  423.99  5500.0  426.56  5520.9  425.53  5584.6  427.89
#Mann=3,-1,0
  4598.2    0.12       0  4998.0    0.05       0  5002.0    0.12       0
Bank Sta=4998,5002
Exp/Cntr=0.3,0.1

Type RM Length L Ch R = 1,2334,163,163,163
BEGIN DESCRIPTION:
StreamM050 2.0
END DESCRIPTION:
XS GIS Cut Line= 3
      2520275.03     13857624.99      2520075.00     13857675.00
      2519524.96     13857725.00
#Sta/Elev= 30
  4793.8  423.43  4811.9  423.66  4853.1  420.73  4894.3  419.99  4907.2  418.45
  4935.6  417.40  4940.7  415.52  4969.1  411.19  4974.8  408.25  4975.0  407.75
  4978.8  408.25  4997.4  412.69  5060.2  412.37  5080.3  415.84  5100.4  416.81
  5120.5  417.15  5140.6  416.11  5170.7  416.92  5210.9  414.29  5251.0  416.22
  5271.1  416.18  5301.2  418.31  5311.3  417.90  5331.3  419.56  5351.4  419.62
  5421.7  422.88  5451.8  425.42  5482.0  425.27  5502.1  426.96  5552.3  429.18
#Mann=3,-1,0
  4793.8    0.12       0  4974.8    0.05       0  4978.8    0.12       0
Bank Sta=4974.8,4978.8
Exp/Cntr=0.3,0.1

Type RM Length L Ch R = 1,2171,289,289,289
BEGIN DESCRIPTION:
H21364
END DESCRIPTION:
XS GIS Cut Line= 3
      2520387.41     13857449.19      2519966.54     13857544.76
      2519575.01     13857675.27
#Sta/Elev= 30
  4630.6  428.33  4745.9  425.76  4797.1  423.16  4848.4  421.77  4861.9  420.68
  4868.9  418.89  4889.4  417.82  4905.0  414.55  4910.1  412.41  4953.2  411.13
  4971.5  411.55  4989.2  408.13  4989.4  407.63  4993.2  408.13  4996.3  409.98
  5002.2  408.67  5012.5  409.16  5033.0  413.78  5039.4  416.28  5060.4  417.22
  5084.9  415.42  5137.2  415.61  5174.1  412.74  5190.3  410.59  5200.4  410.86
  5211.4  413.38  5237.3  416.26  5253.5  415.84  5332.2  418.71  5474.9  426.46
#Mann=3,-1,0
  4630.6    0.12       0  4989.2    0.05       0  4993.2    0.12       0
Bank Sta=4989.2,4993.2
Exp/Cntr=0.3,0.1

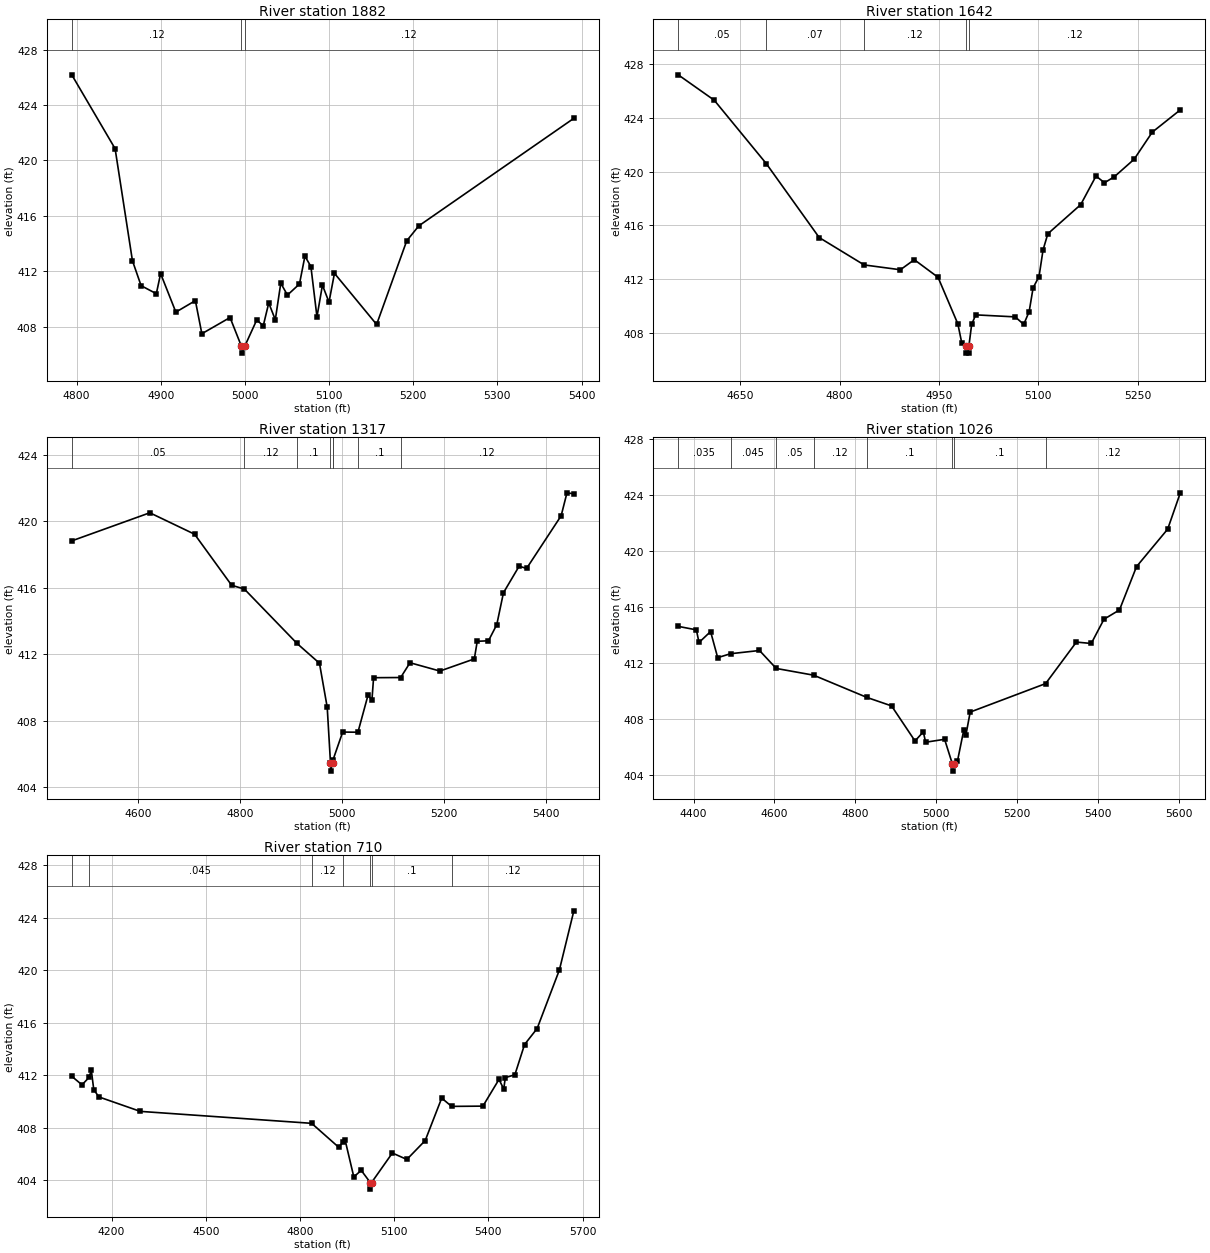
Type RM Length L Ch R = 1,1882,240,240,240
BEGIN DESCRIPTION:
StreamM050 1.0
END DESCRIPTION:
XS GIS Cut Line= 3
      2520124.99     13857325.00      2519925.00     13857375.00
      2519624.96     13857625.03
#Sta/Elev= 30
  4794.2  426.18  4845.7  420.85  4866.3  412.76  4876.6  410.96  4894.7  410.38
  4899.8  411.83  4917.9  409.05  4941.1  409.88  4948.8  407.49  4982.3  408.66
  4995.8  406.59  4996.0  406.09  4999.8  406.59  5014.0  408.48  5021.8  408.07
  5028.3  409.71  5036.1  408.50  5042.6  411.14  5050.5  410.28  5064.8  411.08
  5071.3  413.09  5078.4  412.34  5085.6  408.71  5092.1  411.00  5099.9  409.77
  5106.4  411.85  5156.5  408.16  5192.3  414.20  5206.7  415.28  5390.9  423.04
#Mann=3,-1,0
  4794.2    0.12       0  4995.8    0.05       0  4999.8    0.12       0
Bank Sta=4995.8,4999.8
Exp/Cntr=0.3,0.1

Type RM Length L Ch R = 1,1642,325,325,325
BEGIN DESCRIPTION:
H21363
END DESCRIPTION:
XS GIS Cut Line= 2
      2520075.03     13857059.49      2519450.09     13857487.76
#Sta/Elev= 30
  4556.5  427.22  4610.8  425.33  4689.3  420.61  4769.2  415.10  4837.0  413.06
  4891.7  412.70  4912.7  413.45  4948.5  412.14  4978.4  408.67  4984.4  407.23
  4991.0  406.99  4991.2  406.49  4994.7  406.49  4995.0  406.99  4999.3  408.64
  5005.4  409.34  5065.0  409.19  5077.8  408.63  5086.0  409.58  5092.0  411.36
  5100.9  412.19  5107.0  414.18  5114.2  415.38  5163.8  417.55  5186.9  419.68
  5199.7  419.18  5214.6  419.63  5244.4  420.93  5271.8  422.95  5314.1  424.61
#Mann=5,-1,0
  4556.5    0.05       0  4689.3    0.07       0  4837.0    0.12       0
  4991.0    0.05       0  4995.0    0.12       0
Bank Sta=4991,4995
Exp/Cntr=0.3,0.1

Type RM Length L Ch R = 1,1317,291,291,291
BEGIN DESCRIPTION:
H21362
END DESCRIPTION:
XS GIS Cut Line= 3
      2520122.79     13856739.70      2519624.67     13857061.36
      2519440.89     13857406.88
#Sta/Elev= 30
  4469.8  418.82  4622.8  420.51  4710.6  419.22  4783.2  416.15  4808.2  415.92
  4911.4  412.65  4955.4  411.46  4970.6  408.81  4977.0  405.47  4977.3  404.97
  4981.0  405.47  4982.0  405.65  5000.9  407.32  5030.8  407.31  5050.5  409.53
  5058.3  409.26  5061.5  410.59  5114.6  410.60  5132.9  411.49  5191.5  410.99
  5259.0  411.72  5264.7  412.78  5286.7  412.81  5303.0  413.78  5316.1  415.70
  5346.9  417.30  5361.4  417.16  5429.2  420.33  5440.6  421.71  5454.1  421.65
#Mann=8,-1,0
  4469.8    0.05       0  4808.2    0.12       0  4911.4     0.1       0
  4977.0    0.05       0  4981.0     0.1       0  4982.0    0.12       0
  5030.8     0.1       0  5114.6    0.12       0
Bank Sta=4977,4981
Exp/Cntr=0.3,0.1

Type RM Length L Ch R = 1,1026,316,316,316
BEGIN DESCRIPTION:
H21361
END DESCRIPTION:
XS GIS Cut Line= 3
      2520065.78     13856528.34      2519541.96     13856765.44
      2519329.38     13857397.68
#Sta/Elev= 30
  4362.2  414.63  4407.0  414.38  4413.6  413.48  4442.2  414.26  4459.8  412.40
  4491.6  412.68  4563.2  412.91  4604.6  411.63  4697.1  411.15  4829.3  409.56
  4889.9  408.96  4947.9  406.46  4968.4  407.11  4974.2  406.37  5021.1  406.58
  5040.5  404.81  5040.7  404.31  5044.5  404.81  5052.8  405.01  5068.7  407.26
  5074.0  406.91  5084.4  408.52  5271.0  410.55  5347.1  413.51  5383.9  413.41
  5415.4  415.14  5453.7  415.80  5495.9  418.89  5572.9  421.56  5604.2  424.15
#Mann=8,-1,0
  4362.2   0.035       0  4491.6   0.045       0  4604.6    0.05       0
  4697.1    0.12       0  4829.3     0.1       0  5040.5    0.05       0
  5044.5     0.1       0  5271.0    0.12       0
Bank Sta=5040.5,5044.5
Exp/Cntr=0.3,0.1

Type RM Length L Ch R = 1,710,0,0,0
BEGIN DESCRIPTION:
H21360
END DESCRIPTION:
XS GIS Cut Line= 4
      2519950.02     13856307.76      2519271.77     13856579.80
      2519183.55     13856927.18      2519266.18     13857430.35
#Sta/Elev= 30
  4073.3  411.92  4105.9  411.27  4128.5  411.84  4135.5  412.39  4143.4  410.90
  4159.7  410.35  4291.5  409.25  4837.3  408.34  4922.9  406.53  4938.0  406.92
  4943.6  407.09  4971.6  404.26  4995.2  404.76  5024.1  403.83  5024.4  403.33
  5028.1  403.83  5094.4  406.08  5140.5  405.59  5199.0  407.03  5251.5  410.26
  5283.1  409.63  5382.8  409.65  5433.9  411.68  5449.1  410.96  5454.2  411.82
  5484.6  412.04  5515.4  414.34  5555.5  415.56  5626.4  420.02  5672.4  424.52
#Mann=7,-1,0
  4073.3   0.035       0  4128.5   0.045       0  4837.3    0.12       0
  4938.0     0.1       0  5024.1    0.05       0  5028.1     0.1       0
  5283.1    0.12       0
Bank Sta=5024.1,5028.1
Exp/Cntr=0.3,0.1

Chan Stop Cuts=-1