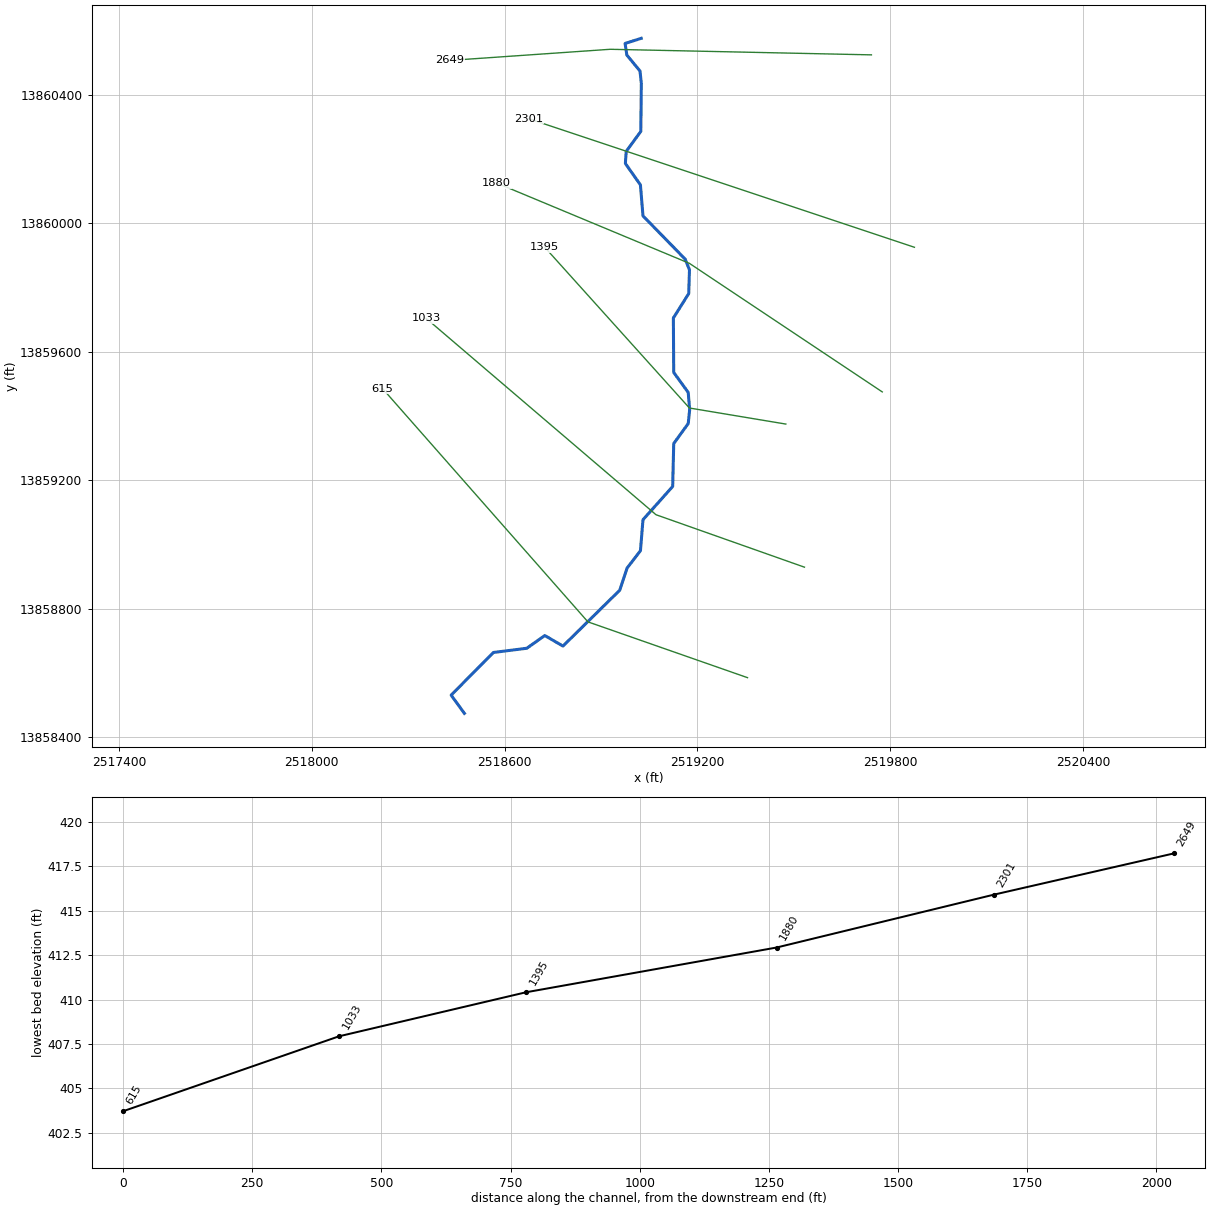
--- StreamM051.prj (project) ---

Proj Title=StreamM051 Base Level Engineering
Current Plan=p01
Default Exp/Contr=0.3,0.1
English Units
Geom File=g01
Flow File=f01
Plan File=p01
BEGIN DESCRIPTION:
StreamM051
END DESCRIPTION:

--- StreamM051.p01 (plan) ---

Plan Title=Multiple Run
Short Identifier=Multiple
Geom File=g01
Flow File=f01
Subcritical Flow
K Sum by GR= 0
Std Step Tol= 0.01
Critical Tol= 0.01
Num of Std Step Trials= 20
Max Error Tol= 0.3
Flow Tol Ratio= 0.001
Split Flow NTrial= 30
Split Flow Tol= 0.02
Split Flow Ratio= 0.02
Log Output Level= 0
Friction Slope Method= 1
Unsteady Friction Slope Method= 2
Unsteady Bridges Friction Slope Method= 1
Parabolic Critical Depth
Global Vel Dist=  1 , 1 , 1
Global Log Level= 0
CheckData=True
Encroach Param= -1, 0, 0, 0
BEGIN DESCRIPTION:
Multiple Run
END DESCRIPTION:

--- StreamM051.f01 (steady flow) ---

Flow Title=Multiple
Number of Profiles=7
Profile Names=10-year,25-year,50-year,1pct_min,100-year,1pct_plu,500-year
River Rch & RM= StreamM051,Reach-1,2649
     323     495     642     406     809    1614    1267
Boundary for River Rch & Prof#=StreamM051,Reach-1,1
Up Type=0
Dn Type=3
Dn Slope=0.005
Boundary for River Rch & Prof#=StreamM051,Reach-1,2
Up Type=0
Dn Type=3
Dn Slope=0.005
Boundary for River Rch & Prof#=StreamM051,Reach-1,3
Up Type=0
Dn Type=3
Dn Slope=0.005
Boundary for River Rch & Prof#=StreamM051,Reach-1,4
Up Type=0
Dn Type=3
Dn Slope=0.005
Boundary for River Rch & Prof#=StreamM051,Reach-1,5
Up Type=0
Dn Type=3
Dn Slope=0.005
Boundary for River Rch & Prof#=StreamM051,Reach-1,6
Up Type=0
Dn Type=3
Dn Slope=0.005
Boundary for River Rch & Prof#=StreamM051,Reach-1,7
Up Type=0
Dn Type=3
Dn Slope=0.005

--- StreamM051.g01 (geometry) ---

Geom Title=Existing Conditions

River Reach=StreamM051,Reach-1
Reach XY= 30
      2519025.00     13860575.00      2518974.90     13860559.09
      2518980.31     13860523.00      2519021.22     13860473.48
      2519025.45     13860435.19      2519023.76     13860285.50
      2518978.37     13860223.26      2518975.77     13860185.69
      2519022.62     13860119.03      2519030.52     13860022.57
      2519161.66     13859888.30      2519175.21     13859854.95
      2519172.84     13859780.98      2519125.07     13859704.97
      2519126.22     13859535.50      2519171.30     13859473.40
      2519175.81     13859419.97      2519171.30     13859376.60
      2519126.23     13859314.49      2519122.92     13859180.86
      2519030.54     13859077.42      2519022.67     13858980.97
      2518981.14     13858927.17      2518958.36     13858858.32
      2518781.67     13858684.30      2518725.10     13858717.20
      2518669.11     13858677.55      2518565.21     13858664.48
      2518433.77     13858531.67      2518475.00     13858475.00

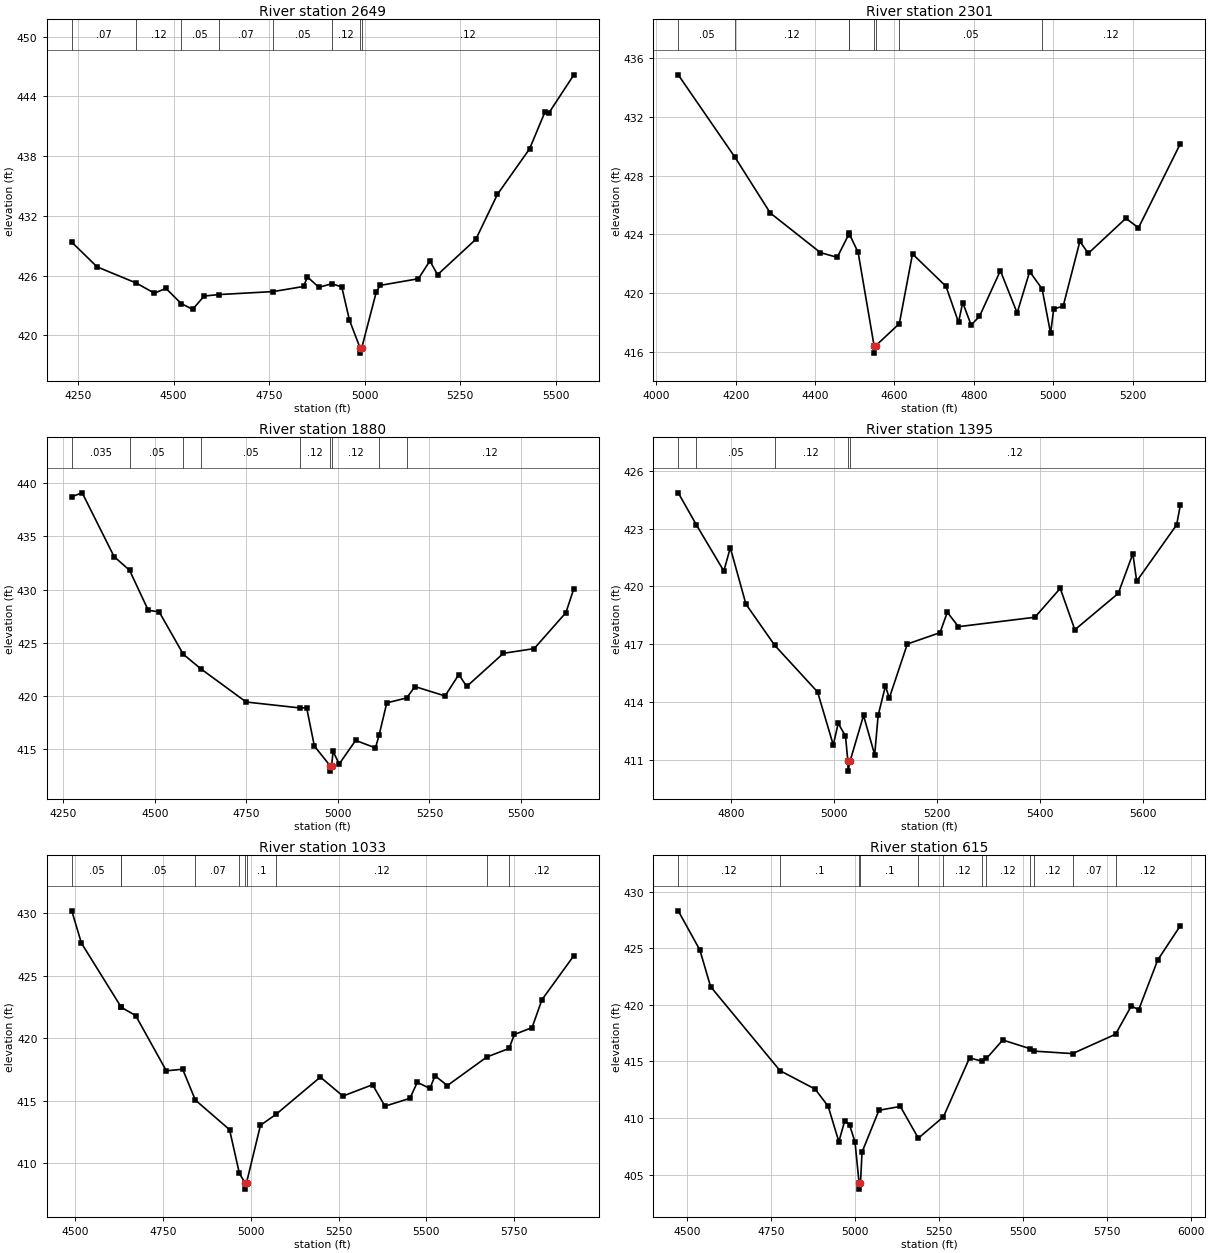
Type RM Length L Ch R = 1,2649,348,348,348
BEGIN DESCRIPTION:
H21374
END DESCRIPTION:
XS GIS Cut Line= 3
      2519741.18     13860523.58      2518928.70     13860540.94
      2518429.36     13860506.26
#Sta/Elev= 30
  4233.6  429.37  4299.8  426.89  4402.0  425.27  4449.8  424.25  4479.8  424.73
  4520.1  423.20  4549.8  422.63  4579.9  423.96  4618.7  424.11  4760.4  424.41
  4839.9  424.92  4849.9  425.88  4879.9  424.84  4914.5  425.20  4939.9  424.86
  4959.9  421.54  4987.9  418.73  4988.2  418.23  4991.9  418.73  5030.0  424.36
  5040.0  425.03  5140.2  425.70  5170.3  427.49  5190.3  426.10  5290.5  429.66
  5347.1  434.18  5430.9  438.73  5471.0  442.42  5481.0  442.31  5546.8  446.17
#Mann=8,-1,0
  4233.6    0.07       0  4402.0    0.12       0  4520.1    0.05       0
  4618.7    0.07       0  4760.4    0.05       0  4914.5    0.12       0
  4987.9    0.05       0  4991.9    0.12       0
Bank Sta=4987.9,4991.9
Exp/Cntr=0.3,0.1

Type RM Length L Ch R = 1,2301,421,421,421
BEGIN DESCRIPTION:
StreamM051 4.0
END DESCRIPTION:
XS GIS Cut Line= 3
      2519874.96     13859925.01      2518975.00     13860225.00
      2518674.97     13860325.01
#Sta/Elev= 30
  4055.2  434.88  4198.4  429.25  4287.1  425.46  4413.5  422.76  4455.7  422.44
  4484.2  423.97  4485.3  424.08  4508.4  422.78  4548.6  416.41  4548.8  415.91
  4552.6  416.41  4612.2  417.92  4645.4  422.67  4729.8  420.46  4761.4  418.01
  4771.9  419.36  4793.0  417.83  4814.1  418.41  4866.8  421.53  4909.0  418.65
  4940.6  421.47  4971.9  420.29  4993.3  417.26  5001.2  418.93  5024.9  419.10
  5067.1  423.53  5088.2  422.71  5183.0  425.10  5214.7  424.45  5320.1  430.18
#Mann=8,-1,0
  4055.2    0.05       0  4198.4    0.12       0  4484.2    0.05       0
  4485.3    0.07       0  4548.6    0.05       0  4552.6    0.07       0
  4612.2    0.05       0  4971.9    0.12       0
Bank Sta=4548.6,4552.6
Exp/Cntr=0.3,0.1

Type RM Length L Ch R = 1,1880,485,485,485
BEGIN DESCRIPTION:
StreamM051 3.0
END DESCRIPTION:
XS GIS Cut Line= 3
      2519774.97     13859475.02      2519175.00     13859875.00
      2518574.97     13860125.01
#Sta/Elev= 30
  4273.2  438.74  4301.7  439.10  4388.8  433.10  4431.0  431.82  4482.0  428.06
  4512.0  427.90  4577.7  423.92  4626.1  422.54  4749.4  419.43  4896.6  418.87
  4914.6  418.89  4935.7  415.29  4978.8  413.43  4979.0  412.93  4982.8  413.43
  4986.8  414.78  5003.5  413.60  5048.4  415.82  5102.6  415.11  5112.6  416.34
  5133.5  419.35  5187.7  419.81  5210.4  420.88  5292.7  420.00  5330.1  422.01
  5351.8  420.89  5452.0  424.01  5535.9  424.45  5622.6  427.83  5644.3  430.09
#Mann=9,-1,0
  4273.2   0.035       0  4431.0    0.05       0  4577.7   0.035       0
  4626.1    0.05       0  4896.6    0.12       0  4978.8    0.05       0
  4982.8    0.12       0  5112.6    0.05       0  5187.7    0.12       0
Bank Sta=4978.8,4982.8
Exp/Cntr=0.3,0.1

Type RM Length L Ch R = 1,1395,362,362,362
BEGIN DESCRIPTION:
StreamM051 2.0
END DESCRIPTION:
XS GIS Cut Line= 3
      2519474.96     13859375.01      2519175.00     13859425.00
      2518724.98     13859925.02
#Sta/Elev= 30
  4696.7  424.86  4731.7  423.21  4785.4  420.80  4798.0  422.01  4828.4  419.08
  4884.5  416.94  4967.8  414.52  4998.3  411.77  5007.9  412.89  5022.1  412.23
  5026.8  410.91  5027.1  410.41  5030.8  410.91  5057.2  413.30  5078.9  411.26
  5085.6  413.30  5099.8  414.83  5107.3  414.20  5142.4  417.01  5206.0  417.60
  5220.2  418.66  5241.8  417.91  5390.6  418.40  5439.9  419.90  5468.3  417.75
  5552.8  419.64  5581.2  421.70  5588.6  420.27  5666.4  423.20  5673.5  424.22
#Mann=5,-1,0
  4696.7   0.035       0  4731.7    0.05       0  4884.5    0.12       0
  5026.8    0.05       0  5030.8    0.12       0
Bank Sta=5026.8,5030.8
Exp/Cntr=0.3,0.1

Type RM Length L Ch R = 1,1033,418,418,418
BEGIN DESCRIPTION:
StreamM051 1.0
END DESCRIPTION:
XS GIS Cut Line= 3
      2519532.91     13858929.81      2519071.06     13859093.02
      2518355.80     13859704.12
#Sta/Elev= 30
  4489.9  430.21  4517.3  427.63  4630.9  422.49  4631.1  422.48  4671.9  421.83
  4759.4  417.40  4805.9  417.53  4842.0  415.06  4939.5  412.69  4967.5  409.19
  4983.8  408.43  4984.1  407.93  4987.8  408.43  5027.5  413.04  5072.0  413.92
  5198.2  416.90  5262.5  415.38  5347.0  416.29  5382.3  414.57  5453.5  415.20
  5474.4  416.48  5510.6  415.99  5524.8  417.01  5560.0  416.22  5672.7  418.51
  5735.9  419.19  5751.0  420.31  5801.5  420.86  5829.5  423.09  5920.5  426.62
#Mann=10,-1,0
  4489.9    0.05       0  4630.9    0.12       0  4631.1    0.05       0
  4842.0    0.07       0  4967.5     0.1       0  4983.8    0.05       0
  4987.8     0.1       0  5072.0    0.12       0  5672.7    0.07       0
  5735.9    0.12       0
Bank Sta=4983.8,4987.8
Exp/Cntr=0.3,0.1

Type RM Length L Ch R = 1,615,0,0,0
BEGIN DESCRIPTION:
H21373
END DESCRIPTION:
XS GIS Cut Line= 3
      2519355.79     13858586.08      2518859.26     13858759.69
      2518220.35     13859485.41
#Sta/Elev= 30
  4474.4  428.31  4538.8  424.84  4570.6  421.61  4777.1  414.18  4881.6  412.55
  4920.2  411.03  4952.0  407.90  4969.4  409.74  4983.7  409.40  5000.0  407.88
  5012.3  404.21  5012.5  403.71  5016.3  404.21  5020.9  406.98  5071.2  410.68
  5134.8  411.02  5188.3  408.21  5263.1  410.11  5340.6  415.31  5377.8  415.02
  5391.0  415.26  5439.3  416.89  5518.9  416.14  5531.8  415.91  5646.8  415.69
  5774.7  417.40  5821.7  419.91  5843.5  419.56  5900.1  423.96  5967.3  426.99
#Mann=12,-1,0
  4474.4    0.12       0  4777.1     0.1       0  5012.3    0.05       0
  5016.3     0.1       0  5188.3    0.05       0  5263.1    0.12       0
  5377.8    0.05       0  5391.0    0.12       0  5518.9    0.07       0
  5531.8    0.12       0  5646.8    0.07       0  5774.7    0.12       0
Bank Sta=5012.3,5016.3
Exp/Cntr=0.3,0.1

Chan Stop Cuts=-1