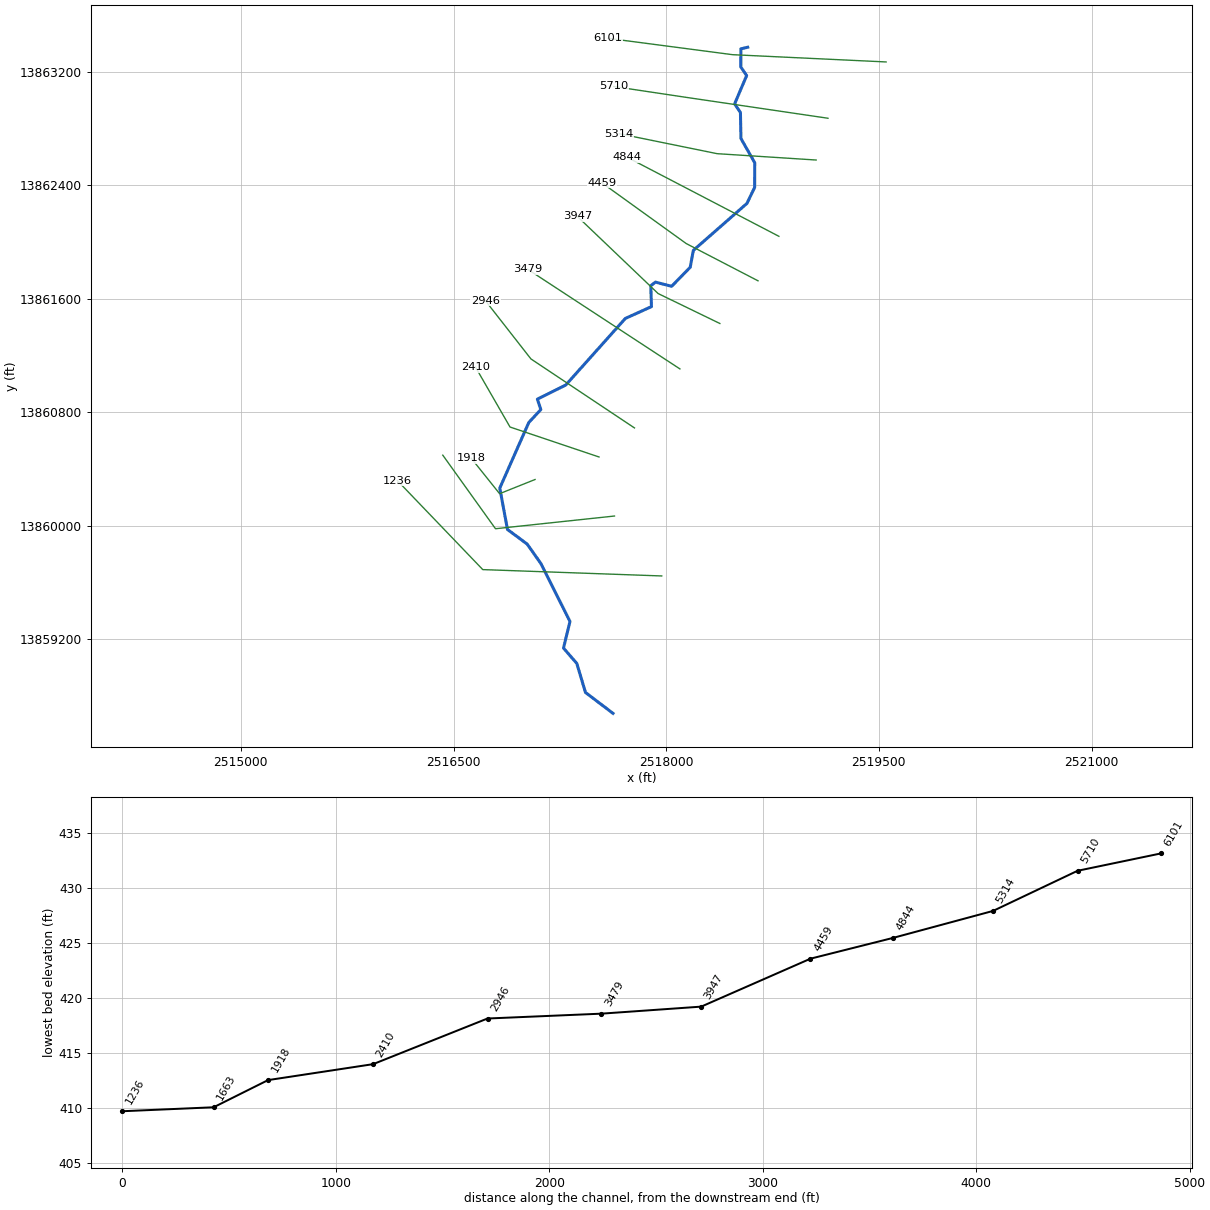
--- StreamM052.prj (project) ---

Proj Title=StreamM052 Base Level Engineering
Current Plan=p01
Default Exp/Contr=0.3,0.1
English Units
Geom File=g01
Flow File=f01
Plan File=p01
BEGIN DESCRIPTION:
StreamM052
END DESCRIPTION:

--- StreamM052.p01 (plan) ---

Plan Title=Multiple Run
Short Identifier=Multiple
Geom File=g01
Flow File=f01
Subcritical Flow
K Sum by GR= 0
Std Step Tol= 0.01
Critical Tol= 0.01
Num of Std Step Trials= 20
Max Error Tol= 0.3
Flow Tol Ratio= 0.001
Split Flow NTrial= 30
Split Flow Tol= 0.02
Split Flow Ratio= 0.02
Log Output Level= 0
Friction Slope Method= 1
Unsteady Friction Slope Method= 2
Unsteady Bridges Friction Slope Method= 1
Parabolic Critical Depth
Global Vel Dist=  1 , 1 , 1
Global Log Level= 0
CheckData=True
Encroach Param= -1, 0, 0, 0
BEGIN DESCRIPTION:
Multiple Run
END DESCRIPTION:

--- StreamM052.f01 (steady flow) ---

Flow Title=Multiple
Number of Profiles=7
Profile Names=10-year,25-year,50-year,1pct_min,100-year,1pct_plu,500-year
River Rch & RM= StreamM052,Reach-1,6101
     584     927    1232     794    1584    3160    2588
Boundary for River Rch & Prof#=StreamM052,Reach-1,1
Up Type=0
Dn Type=3
Dn Slope=0.005
Boundary for River Rch & Prof#=StreamM052,Reach-1,2
Up Type=0
Dn Type=3
Dn Slope=0.005
Boundary for River Rch & Prof#=StreamM052,Reach-1,3
Up Type=0
Dn Type=3
Dn Slope=0.005
Boundary for River Rch & Prof#=StreamM052,Reach-1,4
Up Type=0
Dn Type=3
Dn Slope=0.005
Boundary for River Rch & Prof#=StreamM052,Reach-1,5
Up Type=0
Dn Type=3
Dn Slope=0.005
Boundary for River Rch & Prof#=StreamM052,Reach-1,6
Up Type=0
Dn Type=3
Dn Slope=0.005
Boundary for River Rch & Prof#=StreamM052,Reach-1,7
Up Type=0
Dn Type=3
Dn Slope=0.005

--- StreamM052.g01 (geometry) ---

Geom Title=Existing Conditions

River Reach=StreamM052,Reach-1
Reach XY= 30
      2518575.00     13863375.00      2518526.41     13863363.56
      2518526.36     13863235.45      2518567.44     13863175.00
      2518482.56     13862975.00      2518523.62     13862914.56
      2518527.24     13862730.93      2518624.49     13862559.79
      2518623.80     13862385.50      2518569.17     13862272.70
      2518191.46     13861941.75      2518169.48     13861822.57
      2518038.21     13861688.14      2517924.64     13861717.74
      2517891.21     13861692.56      2517896.03     13861544.77
      2517711.76     13861461.39      2517291.68     13860991.64
      2517091.24     13860892.04      2517115.68     13860818.35
      2517030.86     13860727.30      2516826.19     13860264.50
      2516880.52     13859972.56      2517019.38     13859869.38
      2517116.84     13859731.05      2517321.33     13859323.42
      2517275.61     13859135.62      2517369.46     13859027.42
      2517430.73     13858822.45      2517625.00     13858675.00

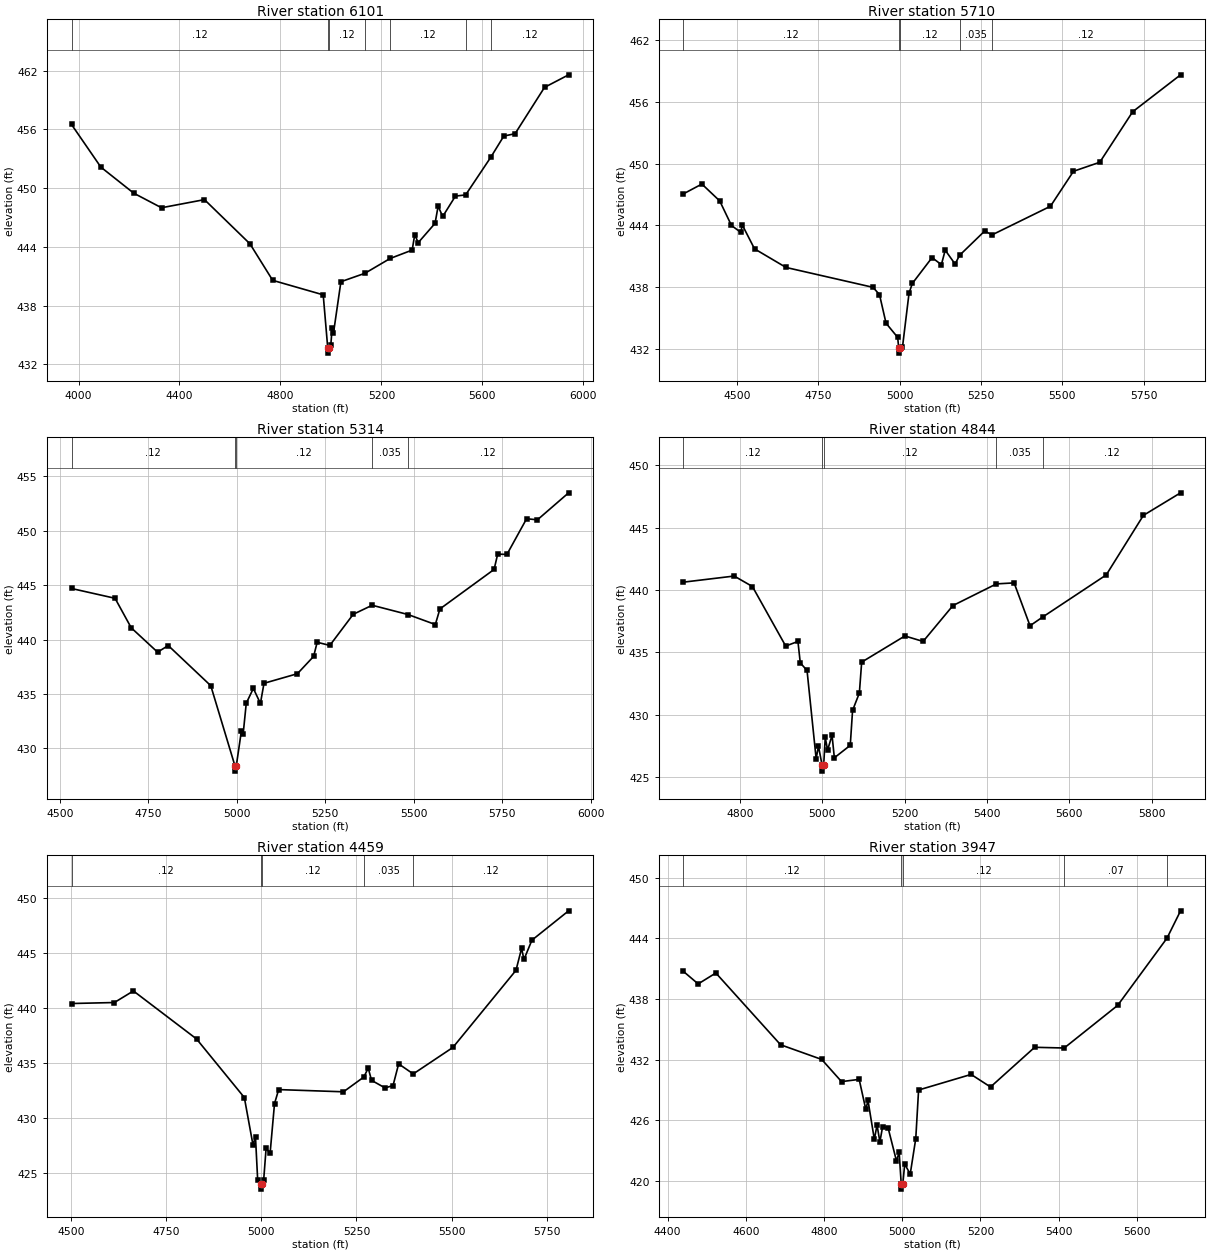
Type RM Length L Ch R = 1,6101,391,391,391
BEGIN DESCRIPTION:
H21385
END DESCRIPTION:
XS GIS Cut Line= 3
      2519551.09     13863271.15      2518468.24     13863322.41
      2517590.45     13863437.74
#Sta/Elev= 30
  3972.3  456.49  4088.5  452.14  4218.7  449.48  4328.8  447.99  4499.0  448.82
  4679.2  444.31  4769.3  440.58  4969.5  439.10  4987.5  433.65  4987.8  433.15
  4991.5  433.65  4999.5  433.95  5005.0  435.74  5010.0  435.17  5039.6  440.44
  5134.7  441.30  5234.5  442.81  5321.9  443.67  5332.0  445.23  5346.0  444.43
  5412.6  446.40  5424.7  448.15  5442.9  447.10  5493.3  449.18  5533.7  449.30
  5633.5  453.15  5685.0  455.31  5729.6  455.55  5846.3  460.28  5941.7  461.56
#Mann=7,-1,0
  3972.3    0.12       0  4987.5    0.05       0  4991.5    0.12       0
  5134.7   0.035       0  5234.5    0.12       0  5533.7    0.07       0
  5633.5    0.12       0
Bank Sta=4987.5,4991.5
Exp/Cntr=0.3,0.1

Type RM Length L Ch R = 1,5710,396,396,396
BEGIN DESCRIPTION:
H21384
END DESCRIPTION:
XS GIS Cut Line= 3
      2519141.03     13862873.89      2518141.46     13863021.26
      2517629.46     13863098.06
#Sta/Elev= 30
  4335.3  447.06  4391.9  448.01  4446.7  446.37  4482.9  443.98  4511.3  443.32
  4516.3  444.02  4553.7  441.71  4650.6  439.90  4917.6  437.97  4937.8  437.27
  4958.0  434.48  4993.8  433.10  4996.9  432.07  4997.1  431.57  5000.9  432.07
  5008.5  432.14  5028.7  437.40  5038.9  438.35  5099.5  440.86  5128.1  440.17
  5139.9  441.58  5170.3  440.23  5184.0  441.08  5261.2  443.44  5284.0  443.07
  5463.4  445.85  5534.2  449.25  5615.1  450.13  5716.2  455.04  5863.4  458.63
#Mann=5,-1,0
  4335.3    0.12       0  4996.9    0.05       0  5000.9    0.12       0
  5184.0   0.035       0  5284.0    0.12       0
Bank Sta=4996.9,5000.9
Exp/Cntr=0.3,0.1

Type RM Length L Ch R = 1,5314,470,470,470
BEGIN DESCRIPTION:
H21383
END DESCRIPTION:
XS GIS Cut Line= 3
      2519057.74     13862579.15      2518359.31     13862624.00
      2517668.66     13862764.69
#Sta/Elev= 30
  4532.9  444.70  4655.9  443.80  4701.6  441.09  4776.1  438.85  4806.2  439.46
  4926.4  435.77  4994.6  428.42  4994.8  427.92  4998.6  428.42  5013.0  431.62
  5018.0  431.36  5026.7  434.16  5046.7  435.52  5066.7  434.14  5076.8  435.99
  5171.2  436.87  5217.0  438.46  5227.1  439.76  5262.8  439.47  5329.0  442.33
  5382.5  443.16  5483.6  442.31  5561.0  441.39  5573.9  442.82  5727.0  446.45
  5737.2  447.86  5763.3  447.83  5818.9  451.11  5849.5  451.01  5937.6  453.49
#Mann=5,-1,0
  4532.9    0.12       0  4994.6    0.05       0  4998.6    0.12       0
  5382.5   0.035       0  5483.6    0.12       0
Bank Sta=4994.6,4998.6
Exp/Cntr=0.3,0.1

Type RM Length L Ch R = 1,4844,385,385,385
BEGIN DESCRIPTION:
H21382
END DESCRIPTION:
XS GIS Cut Line= 2
      2518795.02     13862040.92      2517725.01     13862598.35
#Sta/Elev= 30
  4663.5  440.63  4786.6  441.12  4830.8  440.28  4911.6  435.50  4941.3  435.87
  4947.0  434.15  4963.4  433.54  4985.5  426.46  4991.2  427.46  4999.8  425.96
  5000.0  425.46  5003.8  425.96  5007.6  428.16  5013.3  427.15  5024.1  428.34
  5029.7  426.53  5068.3  427.53  5073.9  430.33  5090.4  431.73  5096.0  434.21
  5200.9  436.31  5245.1  435.87  5317.5  438.75  5423.0  440.49  5466.0  440.57
  5504.6  437.13  5535.8  437.84  5689.6  441.21  5779.8  445.99  5870.0  447.80
#Mann=5,-1,0
  4663.5    0.12       0  4999.8    0.05       0  5003.8    0.12       0
  5423.0   0.035       0  5535.8    0.12       0
Bank Sta=4999.8,5003.8
Exp/Cntr=0.3,0.1

Type RM Length L Ch R = 1,4459,512,512,512
BEGIN DESCRIPTION:
H21381
END DESCRIPTION:
XS GIS Cut Line= 3
      2518647.60     13861726.98      2518141.46     13861989.67
      2517545.55     13862418.98
#Sta/Elev= 30
  4502.1  440.40  4614.6  440.49  4664.5  441.54  4830.2  437.19  4955.7  431.88
  4978.2  427.62  4985.0  428.27  4990.7  424.41  4998.8  424.08  4999.0  423.58
  5002.8  424.08  5006.4  424.39  5012.8  427.27  5023.3  426.83  5034.9  431.33
  5045.8  432.60  5215.9  432.40  5269.4  433.74  5280.9  434.55  5289.5  433.44
  5325.1  432.75  5346.0  432.97  5360.7  434.93  5399.0  434.02  5503.1  436.42
  5668.7  443.41  5683.4  445.40  5689.6  444.39  5710.5  446.14  5806.8  448.80
#Mann=5,-1,0
  4502.1    0.12       0  4998.8    0.05       0  5002.8    0.12       0
  5269.4   0.035       0  5399.0    0.12       0
Bank Sta=4998.8,5002.8
Exp/Cntr=0.3,0.1

Type RM Length L Ch R = 1,3947,468,468,468
BEGIN DESCRIPTION:
H21380
END DESCRIPTION:
XS GIS Cut Line= 3
      2518378.51     13861425.83      2517942.83     13861637.26
      2517373.53     13862180.97
#Sta/Elev= 30
  4440.4  440.72  4478.0  439.49  4523.2  440.57  4688.8  433.48  4794.0  432.03
  4844.7  429.84  4889.8  430.06  4906.8  427.09  4912.4  427.98  4928.6  424.13
  4935.5  425.55  4942.8  423.89  4949.7  425.37  4963.8  425.27  4985.2  422.01
  4992.1  422.85  4997.4  419.72  4997.6  419.22  5001.4  419.72  5006.3  421.69
  5020.4  420.71  5034.6  424.22  5041.8  429.01  5176.1  430.55  5225.8  429.31
  5338.7  433.23  5414.3  433.16  5551.0  437.37  5677.2  444.01  5711.9  446.71
#Mann=5,-1,0
  4440.4    0.12       0  4997.4    0.05       0  5001.4    0.12       0
  5414.3    0.07       0  5677.2    0.12       0
Bank Sta=4997.4,5001.4
Exp/Cntr=0.3,0.1

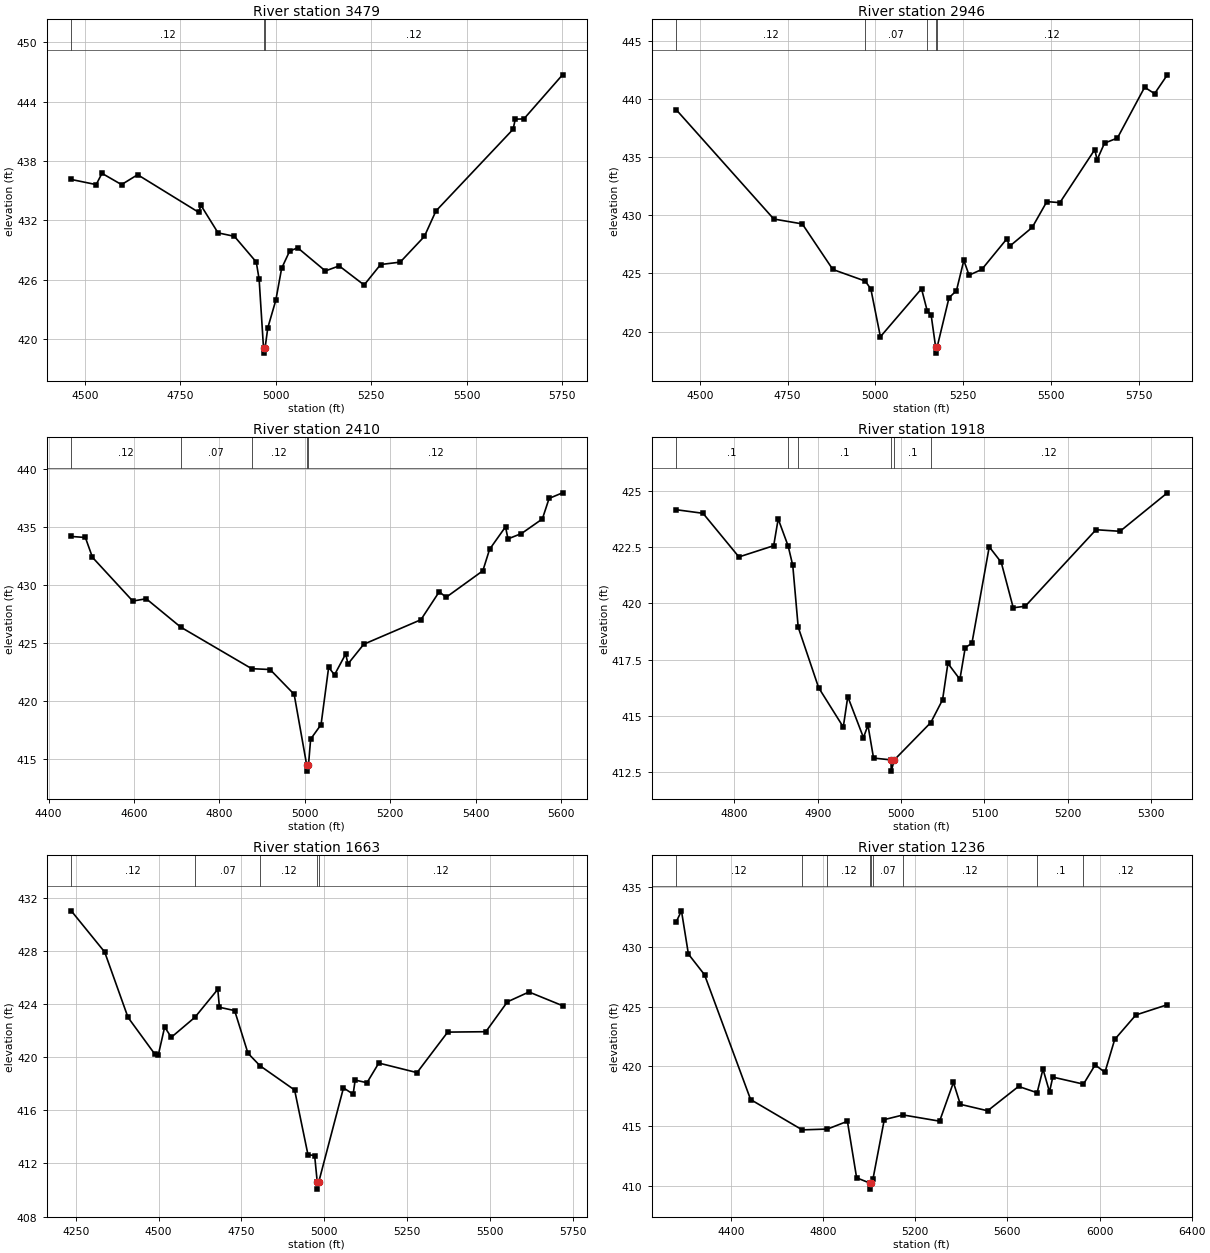
Type RM Length L Ch R = 1,3479,533,533,533
BEGIN DESCRIPTION:
H21379
END DESCRIPTION:
XS GIS Cut Line= 2
      2518096.59     13861105.46      2517020.36     13861810.13
#Sta/Elev= 30
  4464.3  436.14  4529.6  435.62  4544.8  436.76  4596.0  435.62  4638.2  436.62
  4798.0  432.82  4804.0  433.52  4848.7  430.74  4891.5  430.39  4948.8  427.79
  4956.3  426.05  4967.8  419.08  4968.1  418.58  4971.8  419.08  4979.0  421.14
  5000.0  423.93  5015.2  427.15  5036.2  428.90  5057.3  429.23  5129.7  426.89
  5165.9  427.40  5231.2  425.47  5274.4  427.54  5325.7  427.78  5389.0  430.38
  5419.2  432.95  5621.2  441.21  5627.1  442.24  5649.5  442.26  5750.7  446.72
#Mann=3,-1,0
  4464.3    0.12       0  4967.8    0.05       0  4971.8    0.12       0
Bank Sta=4967.8,4971.8
Exp/Cntr=0.3,0.1

Type RM Length L Ch R = 1,2946,536,536,536
BEGIN DESCRIPTION:
H21378
END DESCRIPTION:
XS GIS Cut Line= 3
      2517776.22     13860688.98      2517045.79     13861175.93
      2516725.45     13861585.97
#Sta/Elev= 30
  4432.7  439.10  4710.8  429.68  4791.9  429.26  4878.8  425.34  4971.0  424.34
  4987.0  423.66  5014.2  419.55  5131.2  423.68  5147.5  421.77  5158.5  421.44
  5171.5  418.64  5171.7  418.14  5175.5  418.64  5209.5  422.91  5230.6  423.51
  5251.6  426.12  5266.6  424.85  5302.7  425.34  5373.9  427.97  5382.1  427.34
  5446.3  428.96  5487.9  431.18  5525.0  431.09  5624.4  435.66  5630.8  434.77
  5652.0  436.21  5688.7  436.65  5766.2  441.02  5794.5  440.47  5830.9  442.09
#Mann=5,-1,0
  4432.7    0.12       0  4971.0    0.07       0  5147.5    0.12       0
  5171.5    0.05       0  5175.5    0.12       0
Bank Sta=5171.5,5175.5
Exp/Cntr=0.3,0.1

Type RM Length L Ch R = 1,2410,492,492,492
BEGIN DESCRIPTION:
H21377
END DESCRIPTION:
XS GIS Cut Line= 3
      2517526.37     13860483.92      2516898.42     13860695.37
      2516654.92     13861118.29
#Sta/Elev= 30
  4453.0  434.22  4486.1  434.13  4502.7  432.42  4597.1  428.65  4628.6  428.85
  4709.2  426.41  4875.7  422.82  4918.7  422.75  4975.1  420.61  5004.6  414.49
  5004.8  413.99  5008.6  414.49  5013.7  416.75  5038.1  418.00  5055.9  422.94
  5069.6  422.29  5095.8  424.09  5101.1  423.23  5138.2  424.93  5271.9  427.04
  5315.0  429.46  5330.8  428.97  5417.0  431.26  5432.8  433.11  5470.1  435.05
  5475.9  434.01  5507.5  434.47  5556.4  435.73  5572.2  437.50  5603.6  437.98
#Mann=5,-1,0
  4453.0    0.12       0  4709.2    0.07       0  4875.7    0.12       0
  5004.6    0.05       0  5008.6    0.12       0
Bank Sta=5004.6,5008.6
Exp/Cntr=0.3,0.1

Type RM Length L Ch R = 1,1918,255,255,255
BEGIN DESCRIPTION:
StreamM052 1.0
END DESCRIPTION:
XS GIS Cut Line= 3
      2517074.98     13860324.99      2516825.00     13860225.00
      2516625.00     13860475.01
#Sta/Elev= 30
  4730.0  424.16  4762.3  424.00  4805.4  422.06  4847.1  422.56  4852.5  423.75
  4864.5  422.54  4870.0  421.68  4876.5  418.94  4901.0  416.25  4930.6  414.50
  4936.0  415.85  4954.8  414.03  4960.2  414.58  4966.9  413.12  4987.8  413.04
  4988.1  412.54  4991.8  413.04  5035.6  414.70  5049.7  415.71  5056.1  417.33
  5070.5  416.62  5076.9  418.03  5084.9  418.22  5105.7  422.51  5120.1  421.82
  5134.5  419.80  5148.9  419.87  5233.8  423.27  5262.6  423.20  5319.4  424.91
#Mann=6,-1,0
  4730.0     0.1       0  4864.5    0.12       0  4876.5     0.1       0
  4987.8    0.05       0  4991.8     0.1       0  5035.6    0.12       0
Bank Sta=4987.8,4991.8
Exp/Cntr=0.3,0.1

Type RM Length L Ch R = 1,1663,427,427,427
BEGIN DESCRIPTION:
H21376
END DESCRIPTION:
XS GIS Cut Line= 3
      2517635.32     13860067.45      2516795.90     13859977.74
      2516424.29     13860496.72
#Sta/Elev= 30
  4236.4  431.02  4337.3  427.92  4407.7  423.00  4488.1  420.25  4499.0  420.15
  4518.3  422.27  4538.4  421.50  4609.8  423.01  4678.6  425.11  4683.6  423.76
  4729.5  423.51  4769.7  420.30  4805.9  419.36  4910.5  417.53  4950.8  412.66
  4970.9  412.60  4978.9  410.57  4979.2  410.07  4982.9  410.57  5057.9  417.69
  5087.1  417.22  5093.2  418.28  5128.8  418.08  5164.5  419.56  5279.9  418.84
  5372.4  421.89  5487.5  421.92  5552.6  424.17  5617.7  424.91  5718.9  423.88
#Mann=5,-1,0
  4236.4    0.12       0  4609.8    0.07       0  4805.9    0.12       0
  4978.9    0.05       0  4982.9    0.12       0
Bank Sta=4978.9,4982.9
Exp/Cntr=0.3,0.1

Type RM Length L Ch R = 1,1236,0,0,0
BEGIN DESCRIPTION:
H21375
END DESCRIPTION:
XS GIS Cut Line= 3
      2517968.43     13859644.56      2516706.20     13859689.41
      2516103.91     13860317.32
#Sta/Elev= 30
  4161.4  432.06  4184.8  433.01  4214.9  429.39  4284.9  427.66  4485.0  417.21
  4709.2  414.67  4818.8  414.74  4905.3  415.39  4945.3  410.66  5003.4  410.21
  5003.6  409.71  5007.4  410.21  5016.2  410.55  5065.4  415.53  5147.0  415.92
  5305.6  415.40  5365.6  418.64  5395.6  416.81  5514.2  416.27  5648.5  418.31
  5729.0  417.78  5754.5  419.76  5782.8  417.85  5797.0  419.09  5930.2  418.50
  5980.9  420.11  6023.4  419.49  6065.8  422.24  6157.7  424.29  6294.5  425.15
#Mann=9,-1,0
  4161.4    0.12       0  4709.2    0.07       0  4818.8    0.12       0
  5003.4    0.05       0  5007.4    0.12       0  5016.2    0.07       0
  5147.0    0.12       0  5729.0     0.1       0  5930.2    0.12       0
Bank Sta=5003.4,5007.4
Exp/Cntr=0.3,0.1

Chan Stop Cuts=-1