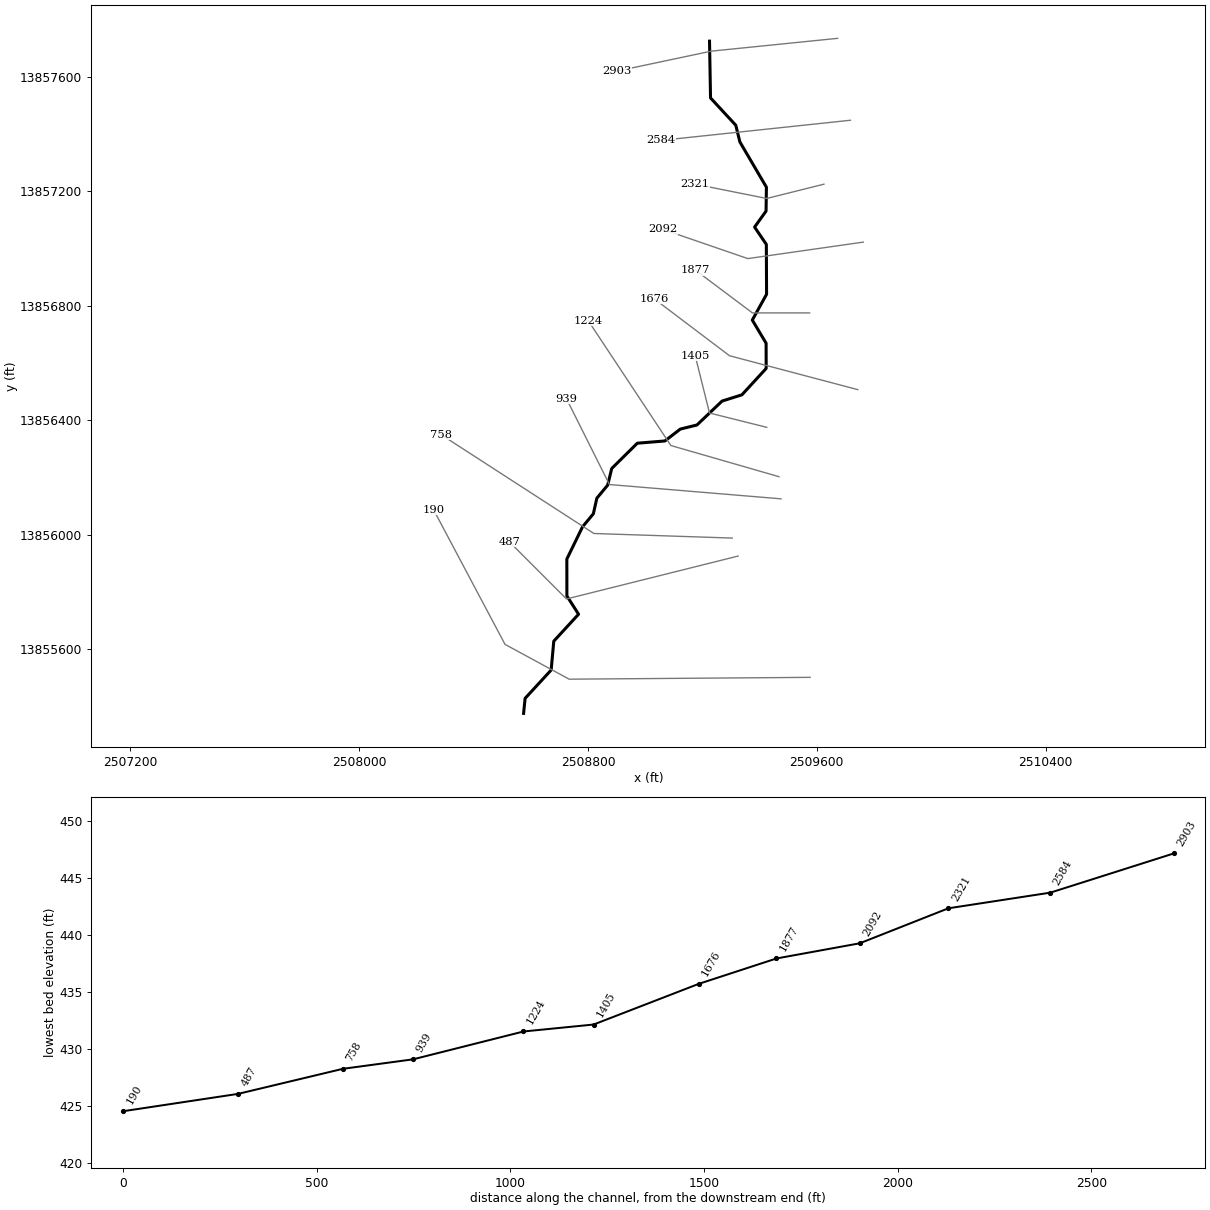
--- StreamM053.prj (project) ---

Proj Title=StreamM053 Base Level Engineering
Current Plan=p01
Default Exp/Contr=0.3,0.1
English Units
Geom File=g01
Flow File=f01
Plan File=p01
BEGIN DESCRIPTION:
StreamM053
END DESCRIPTION:

--- StreamM053.p01 (plan) ---

Plan Title=Multiple Run
Short Identifier=Multiple
Geom File=g01
Flow File=f01
Subcritical Flow
K Sum by GR= 0
Std Step Tol= 0.01
Critical Tol= 0.01
Num of Std Step Trials= 20
Max Error Tol= 0.3
Flow Tol Ratio= 0.001
Split Flow NTrial= 30
Split Flow Tol= 0.02
Split Flow Ratio= 0.02
Log Output Level= 0
Friction Slope Method= 1
Unsteady Friction Slope Method= 2
Unsteady Bridges Friction Slope Method= 1
Parabolic Critical Depth
Global Vel Dist=  1 , 1 , 1
Global Log Level= 0
CheckData=True
Encroach Param= -1, 0, 0, 0
BEGIN DESCRIPTION:
Multiple Run
END DESCRIPTION:

--- StreamM053.f01 (steady flow) ---

Flow Title=Multiple
Number of Profiles=7
Profile Names=10-year,25-year,50-year,1pct_min,100-year,1pct_plu,500-year
River Rch & RM= StreamM053,Reach-1,2903
     374     580     760     483     965    1924    1536
Boundary for River Rch & Prof#=StreamM053,Reach-1,1
Up Type=0
Dn Type=3
Dn Slope=0.005
Boundary for River Rch & Prof#=StreamM053,Reach-1,2
Up Type=0
Dn Type=3
Dn Slope=0.005
Boundary for River Rch & Prof#=StreamM053,Reach-1,3
Up Type=0
Dn Type=3
Dn Slope=0.005
Boundary for River Rch & Prof#=StreamM053,Reach-1,4
Up Type=0
Dn Type=3
Dn Slope=0.005
Boundary for River Rch & Prof#=StreamM053,Reach-1,5
Up Type=0
Dn Type=3
Dn Slope=0.005
Boundary for River Rch & Prof#=StreamM053,Reach-1,6
Up Type=0
Dn Type=3
Dn Slope=0.005
Boundary for River Rch & Prof#=StreamM053,Reach-1,7
Up Type=0
Dn Type=3
Dn Slope=0.005

--- StreamM053.g01 (geometry) ---

Geom Title=Existing Conditions

River Reach=StreamM053,Reach-1
Reach XY= 30
      2509225.00     13857725.00      2509228.54     13857526.47
      2509316.84     13857431.05      2509331.10     13857372.81
      2509423.91     13857214.45      2509422.64     13857130.89
      2509382.56     13857075.00      2509423.62     13857014.56
      2509424.46     13856840.21      2509374.60     13856750.00
      2509422.81     13856669.03      2509423.04     13856580.88
      2509338.24     13856488.62      2509268.96     13856466.82
      2509181.05     13856383.16      2509122.83     13856368.86
      2509069.03     13856327.33      2508972.56     13856319.48
      2508883.13     13856231.07      2508868.90     13856172.82
      2508831.08     13856127.20      2508818.92     13856072.80
      2508781.08     13856027.20      2508726.19     13855914.50
      2508726.38     13855785.44      2508767.19     13855721.59
      2508680.55     13855627.43      2508671.39     13855526.50
      2508580.33     13855427.51      2508575.00     13855375.00

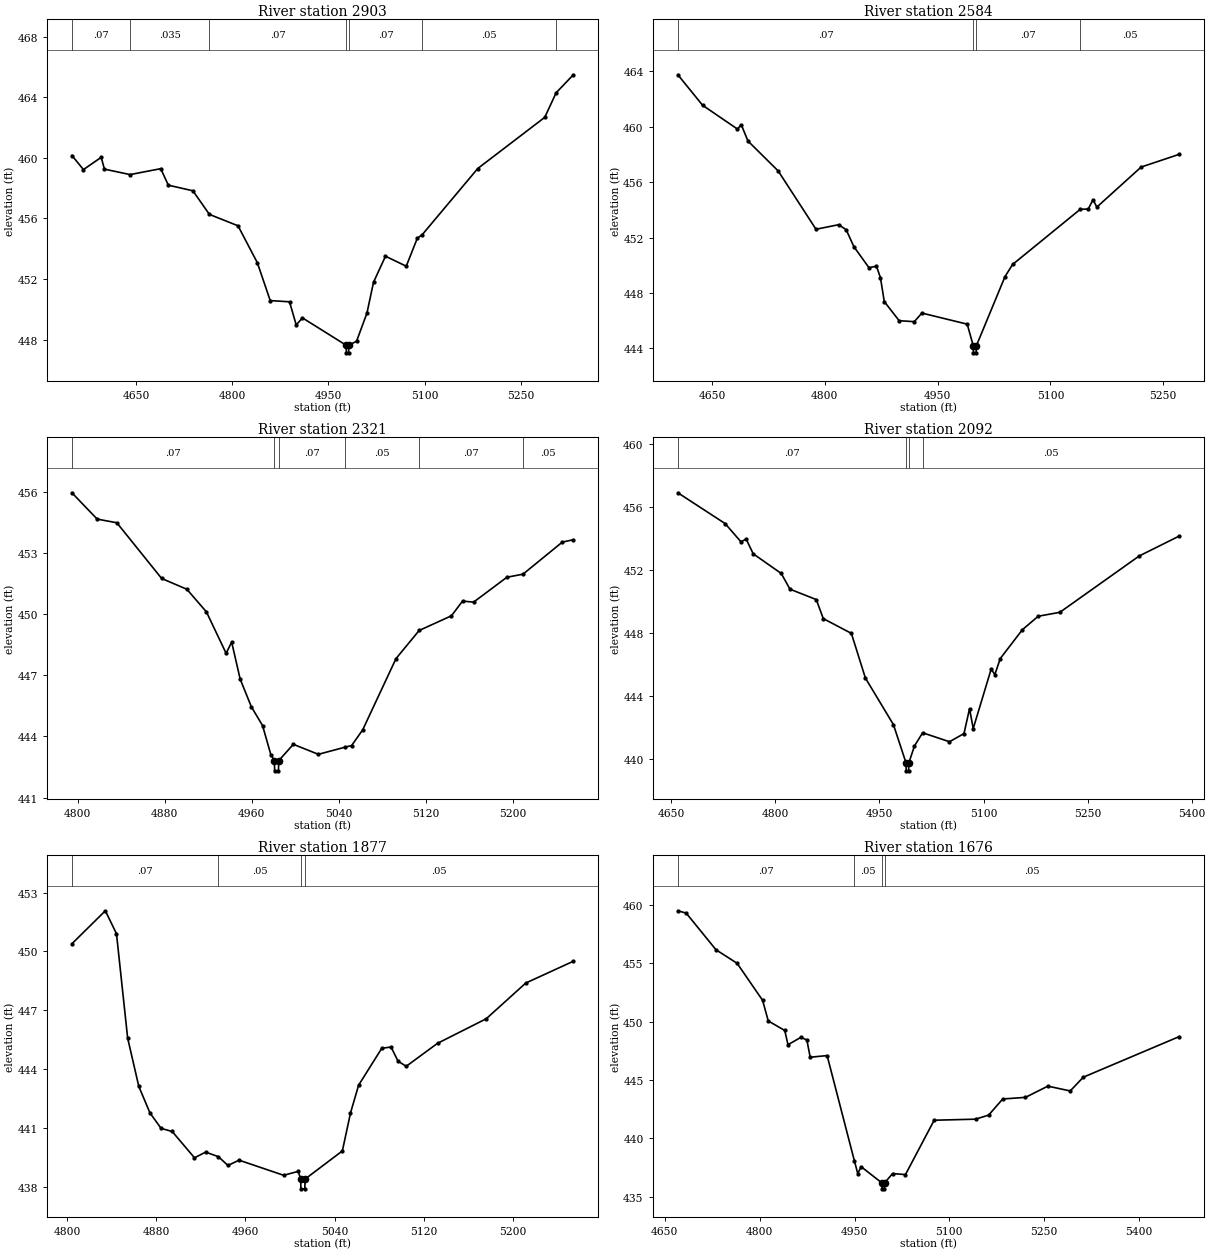
Type RM Length L Ch R = 1,2903,319,319,319
BEGIN DESCRIPTION:
StreamM053 6.0
END DESCRIPTION:
XS GIS Cut Line= 3
      2509672.88     13857734.87      2509230.81     13857690.03
      2508899.87     13857620.02
#Sta/Elev= 30
  4549.7  460.15  4567.7  459.22  4595.4  460.03  4600.4  459.25  4640.5  458.89
  4688.3  459.28  4700.2  458.19  4738.5  457.82  4764.3  456.26  4808.9  455.51
  4839.1  453.07  4859.2  450.57  4889.3  450.49  4899.8  448.96  4909.4  449.43
  4977.8  447.62  4978.0  447.12  4981.5  447.12  4981.8  447.62  4994.0  447.89
  5010.2  449.75  5020.4  451.78  5039.1  453.50  5071.5  452.84  5088.8  454.69
  5096.4  454.92  5183.1  459.29  5287.7  462.67  5305.4  464.29  5332.3  465.48
#Mann=7,-1,0
  4549.7    0.07       0  4640.5   0.035       0  4764.3    0.07       0
  4977.8    0.05       0  4981.8    0.07       0  5096.4    0.05       0
  5305.4    0.07       0
Bank Sta=4977.8,4981.8
Exp/Cntr=0.3,0.1

Type RM Length L Ch R = 1,2584,263,263,263
BEGIN DESCRIPTION:
H21391
END DESCRIPTION:
XS GIS Cut Line= 2
      2509717.67     13857448.50      2509054.60     13857378.03
#Sta/Elev= 30
  4604.6  463.75  4637.5  461.55  4683.9  459.83  4688.9  460.15  4697.8  458.97
  4738.0  456.81  4788.3  452.60  4818.5  452.93  4828.5  452.56  4838.6  451.35
  4858.7  449.83  4868.7  449.93  4874.0  449.11  4879.1  447.38  4898.9  446.00
  4919.0  445.93  4929.1  446.55  4989.4  445.75  4997.5  444.18  4997.7  443.68
  5001.2  443.68  5001.5  444.18  5039.7  449.19  5049.8  450.06  5139.7  454.04
  5150.3  454.06  5156.7  454.73  5161.8  454.20  5220.7  457.09  5271.4  458.01
#Mann=4,-1,0
  4604.6    0.07       0  4997.5    0.05       0  5001.5    0.07       0
  5139.7    0.05       0
Bank Sta=4997.5,5001.5
Exp/Cntr=0.3,0.1

Type RM Length L Ch R = 1,2321,229,229,229
BEGIN DESCRIPTION:
StreamM053 5.0
END DESCRIPTION:
XS GIS Cut Line= 3
      2509625.03     13857225.01      2509425.00     13857175.00
      2509175.04     13857224.99
#Sta/Elev= 30
  4794.6  455.94  4817.8  454.65  4835.9  454.47  4877.1  451.74  4900.3  451.21
  4918.3  450.10  4936.4  448.07  4941.5  448.62  4949.3  446.81  4959.6  445.45
  4969.9  444.53  4977.6  443.09  4980.8  442.81  4981.0  442.31  4984.5  442.31
  4984.8  442.81  4998.2  443.61  5021.2  443.12  5045.8  443.47  5051.8  443.55
  5062.0  444.32  5092.6  447.81  5113.9  449.19  5143.6  449.91  5153.8  450.63
  5164.0  450.58  5194.6  451.80  5209.4  451.95  5245.5  453.52  5255.7  453.64
#Mann=6,-1,0
  4794.6    0.07       0  4980.8    0.05       0  4984.8    0.07       0
  5045.8    0.05       0  5113.9    0.07       0  5209.4    0.05       0
Bank Sta=4980.8,4984.8
Exp/Cntr=0.3,0.1

Type RM Length L Ch R = 1,2092,215,215,215
BEGIN DESCRIPTION:
H21390
END DESCRIPTION:
XS GIS Cut Line= 3
      2509762.54     13857022.47      2509358.94     13856964.82
      2509061.07     13857067.31
#Sta/Elev= 30
  4659.4  456.92  4727.6  454.96  4750.2  453.81  4757.9  453.97  4768.0  453.04
  4808.4  451.79  4821.0  450.79  4858.9  450.13  4869.0  448.92  4909.5  447.98
  4929.7  445.14  4970.1  442.18  4988.3  439.74  4988.5  439.24  4992.0  439.24
  4992.3  439.74  5000.4  440.82  5012.2  441.66  5050.9  441.09  5071.8  441.61
  5079.8  443.19  5085.1  441.93  5111.0  445.71  5116.3  445.36  5124.1  446.38
  5155.9  448.21  5178.8  449.07  5210.0  449.32  5324.3  452.90  5382.1  454.17
#Mann=4,-1,0
  4659.4    0.07       0  4988.3    0.05       0  4992.3    0.07       0
  5012.2    0.05       0
Bank Sta=4988.3,4992.3
Exp/Cntr=0.3,0.1

Type RM Length L Ch R = 1,1877,201,201,201
BEGIN DESCRIPTION:
StreamM053 4.0
END DESCRIPTION:
XS GIS Cut Line= 3
      2509574.96     13856775.00      2509375.00     13856775.00
      2509174.97     13856925.02
#Sta/Elev= 30
  4804.3  450.39  4834.3  452.07  4844.3  450.90  4854.3  445.59  4864.3  443.13
  4874.3  441.78  4884.3  440.99  4894.3  440.83  4914.3  439.49  4924.3  439.78
  4935.7  439.55  4944.3  439.10  4954.3  439.37  4994.3  438.60  5007.4  438.80
  5009.6  438.41  5009.8  437.91  5013.3  437.91  5013.6  438.41  5047.0  439.84
  5054.3  441.77  5061.6  443.19  5082.4  445.07  5090.7  445.13  5097.0  444.41
  5104.3  444.15  5132.4  445.32  5176.1  446.57  5211.6  448.39  5254.3  449.50
#Mann=4,-1,0
  4804.3    0.07       0  4935.7    0.05       0  5009.6    0.05       0
  5013.6    0.05       0
Bank Sta=5009.6,5013.6
Exp/Cntr=0.3,0.1

Type RM Length L Ch R = 1,1676,271,271,271
BEGIN DESCRIPTION:
H21389
END DESCRIPTION:
XS GIS Cut Line= 3
      2509743.29     13856506.76      2509294.87     13856625.28
      2509032.22     13856823.87
#Sta/Elev= 30
  4670.6  459.51  4683.8  459.31  4730.9  456.17  4764.3  455.01  4804.6  451.84
  4813.6  450.07  4839.7  449.25  4844.8  448.03  4865.4  448.67  4874.7  448.43
  4879.9  446.96  4906.7  447.10  4949.8  438.08  4955.2  436.98  4960.4  437.58
  4993.5  436.18  4993.8  435.68  4997.3  435.68  4997.5  436.18  5010.2  436.99
  5030.6  436.90  5076.0  441.56  5141.4  441.65  5162.2  442.00  5184.4  443.38
  5220.4  443.52  5255.8  444.48  5291.2  444.07  5312.0  445.25  5463.7  448.73
#Mann=4,-1,0
  4670.6    0.07       0  4949.8    0.05       0  4993.5    0.05       0
  4997.5    0.05       0
Bank Sta=4993.5,4997.5
Exp/Cntr=0.3,0.1

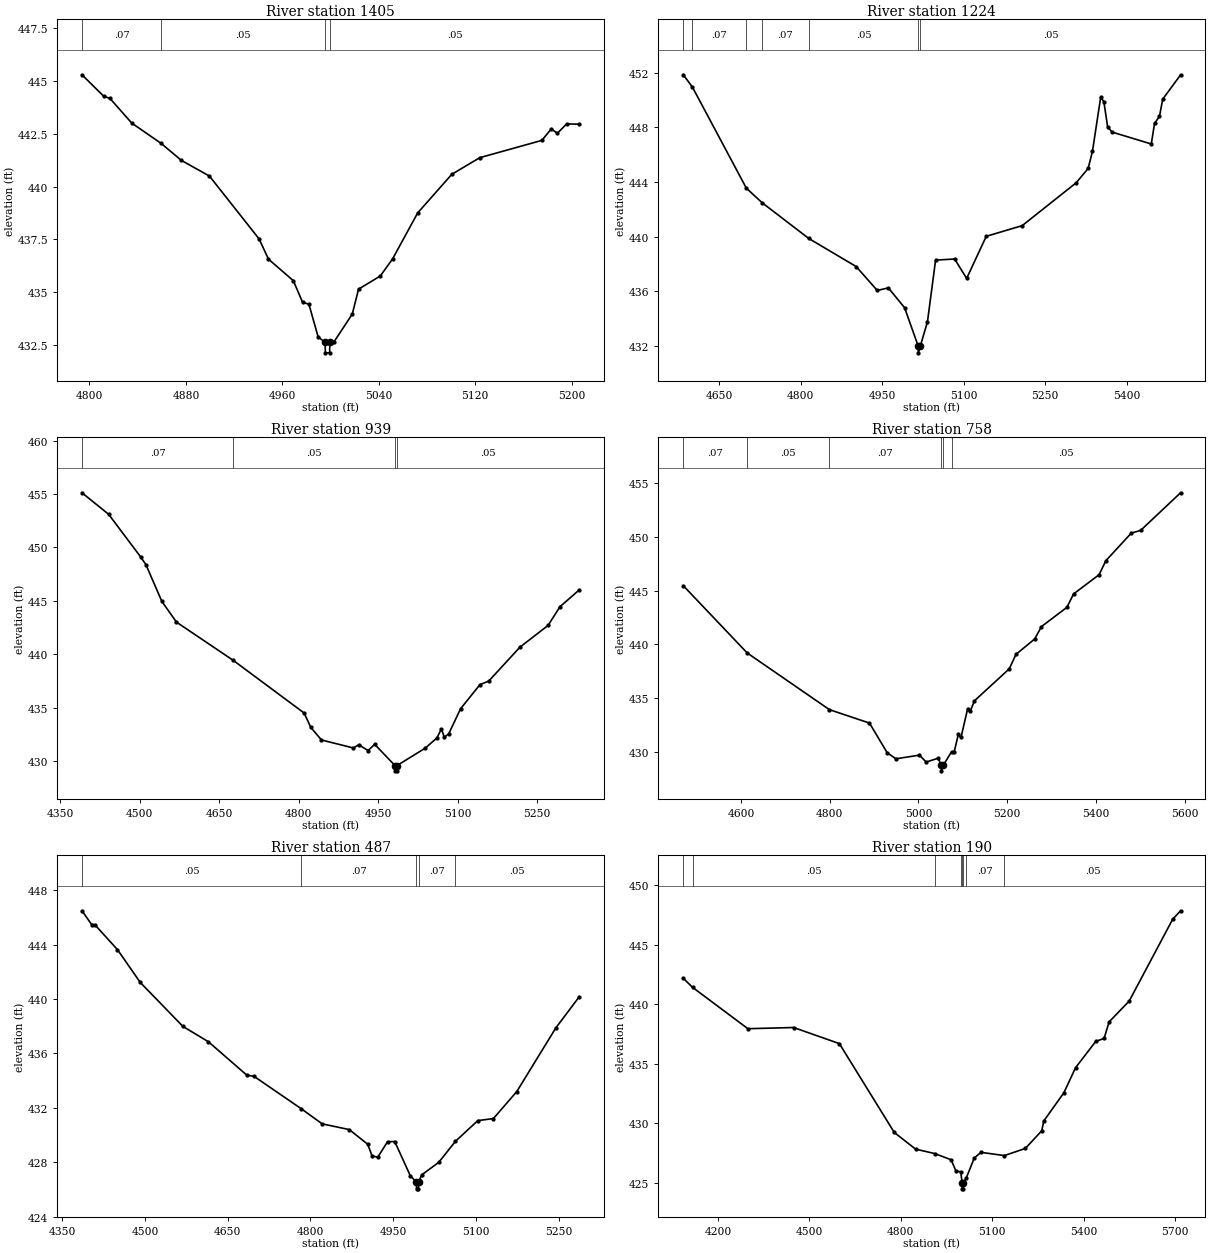
Type RM Length L Ch R = 1,1405,181,181,181
BEGIN DESCRIPTION:
StreamM053 3.0
END DESCRIPTION:
XS GIS Cut Line= 3
      2509425.05     13856374.99      2509225.00     13856425.00
      2509174.99     13856625.04
#Sta/Elev= 30
  4793.8  445.30  4811.9  444.28  4817.0  444.18  4835.1  443.01  4859.4  442.05
  4876.3  441.24  4899.5  440.50  4940.7  437.52  4948.5  436.56  4969.1  435.54
  4976.8  434.51  4982.0  434.43  4989.7  432.87  4995.4  432.62  4995.7  432.12
  4999.2  432.12  4999.4  432.62  5002.6  432.62  5018.0  433.96  5023.2  435.14
  5041.2  435.76  5051.5  436.58  5072.2  438.75  5100.5  440.58  5123.7  441.37
  5175.2  442.19  5183.0  442.73  5188.1  442.53  5195.8  442.97  5206.2  442.96
#Mann=4,-1,0
  4793.8    0.07       0  4859.4    0.05       0  4995.4    0.05       0
  4999.4    0.05       0
Bank Sta=4995.4,4999.4
Exp/Cntr=0.3,0.1

Type RM Length L Ch R = 1,1224,285,285,285
BEGIN DESCRIPTION:
H21388
END DESCRIPTION:
XS GIS Cut Line= 3
      2509467.85     13856202.45      2509089.87     13856311.36
      2508801.60     13856746.96
#Sta/Elev= 30
  4583.5  451.84  4600.4  450.93  4699.6  443.55  4728.2  442.50  4814.6  439.87
  4901.8  437.82  4940.7  436.07  4961.1  436.26  4991.0  434.81  5016.0  432.01
  5016.3  431.51  5020.0  432.01  5033.1  433.78  5048.1  438.29  5083.2  438.37
  5105.3  436.95  5141.4  440.03  5207.6  440.81  5306.9  443.94  5329.0  444.99
  5337.0  446.25  5352.1  450.20  5358.0  449.87  5364.9  448.03  5373.1  447.65
  5445.3  446.78  5451.3  448.28  5460.4  448.81  5466.4  450.06  5499.2  451.83
#Mann=7,-1,0
  4583.5    0.05       0  4600.4    0.07       0  4699.6    0.05       0
  4728.2    0.07       0  4814.6    0.05       0  5016.0    0.05       0
  5020.0    0.05       0
Bank Sta=5016,5020
Exp/Cntr=0.3,0.1

Type RM Length L Ch R = 1,939,181,181,181
BEGIN DESCRIPTION:
StreamM053 2.0
END DESCRIPTION:
XS GIS Cut Line= 3
      2509475.03     13856125.00      2508875.00     13856175.00
      2508725.01     13856474.98
#Sta/Elev= 30
  4391.5  455.11  4441.7  453.10  4501.9  449.12  4512.0  448.39  4542.1  444.94
  4569.6  443.00  4676.9  439.41  4810.5  434.48  4823.0  433.13  4843.1  431.96
  4903.3  431.21  4913.3  431.51  4930.9  430.97  4943.4  431.55  4981.6  429.57
  4981.8  429.07  4985.3  429.07  4985.6  429.57  5038.3  431.18  5060.7  432.15
  5069.1  433.00  5074.7  432.21  5083.1  432.55  5105.4  434.89  5141.8  437.14
  5158.5  437.48  5217.2  440.65  5270.3  442.69  5292.7  444.44  5329.0  446.01
#Mann=4,-1,0
  4391.5    0.07       0  4676.9    0.05       0  4981.6    0.05       0
  4985.6    0.05       0
Bank Sta=4981.6,4985.6
Exp/Cntr=0.3,0.1

Type RM Length L Ch R = 1,758,271,271,271
BEGIN DESCRIPTION:
H21387
END DESCRIPTION:
XS GIS Cut Line= 3
      2509304.47     13855987.83      2508820.79     13856003.85
      2508285.86     13856349.80
#Sta/Elev= 30
  4470.0  445.45  4614.0  439.20  4799.3  433.93  4889.7  432.68  4929.7  429.92
  4949.3  429.36  5002.3  429.70  5017.5  429.06  5044.5  429.41  5051.8  428.74
  5052.0  428.24  5055.8  428.74  5074.7  430.01  5080.8  430.02  5090.0  431.63
  5096.0  431.34  5111.1  434.03  5117.1  433.80  5126.3  434.75  5204.8  437.72
  5220.0  439.07  5262.2  440.50  5277.4  441.65  5334.8  443.44  5349.9  444.69
  5407.3  446.47  5422.5  447.77  5479.9  450.34  5501.0  450.59  5591.0  454.09
#Mann=6,-1,0
  4470.0    0.07       0  4614.0    0.05       0  4799.3    0.07       0
  5051.8    0.05       0  5055.8    0.07       0  5074.7    0.05       0
Bank Sta=5051.8,5055.8
Exp/Cntr=0.3,0.1

Type RM Length L Ch R = 1,487,297,297,297
BEGIN DESCRIPTION:
StreamM053 1.0
END DESCRIPTION:
XS GIS Cut Line= 3
      2509324.99     13855925.00      2508725.00     13855775.00
      2508525.00     13855975.00
#Sta/Elev= 30
  4385.9  446.50  4403.9  445.46  4409.1  445.48  4450.3  443.64  4491.5  441.23
  4568.9  437.99  4615.2  436.86  4684.8  434.40  4697.7  434.32  4782.8  431.95
  4821.4  430.82  4870.4  430.40  4903.9  429.32  4911.6  428.48  4921.9  428.36
  4939.9  429.51  4952.8  429.52  4981.2  426.99  4992.1  426.54  4992.3  426.04
  4995.8  426.04  4996.1  426.54  5001.8  427.07  5032.6  427.99  5062.9  429.54
  5103.4  431.06  5131.6  431.21  5174.1  433.20  5244.8  437.88  5287.2  440.17
#Mann=5,-1,0
  4385.9    0.05       0  4782.8    0.07       0  4992.1    0.05       0
  4996.1    0.07       0  5062.9    0.05       0
Bank Sta=4992.1,4996.1
Exp/Cntr=0.3,0.1

Type RM Length L Ch R = 1,190,0,0,0
BEGIN DESCRIPTION:
H21386
END DESCRIPTION:
XS GIS Cut Line= 4
      2509576.79     13855500.95      2508734.31     13855494.54
      2508510.08     13855616.26      2508260.23     13856087.14
#Sta/Elev= 30
  4086.6  442.18  4116.8  441.42  4298.4  437.95  4448.4  438.05  4598.4  436.70
  4778.4  429.25  4848.4  427.85  4910.9  427.48  4964.8  426.96  4981.0  426.00
  4996.5  425.95  5000.9  425.02  5001.1  424.52  5004.6  424.52  5004.9  425.02
  5014.7  425.44  5040.9  427.11  5062.7  427.58  5139.7  427.31  5208.4  427.91
  5262.1  429.39  5268.7  430.21  5334.7  432.58  5373.0  434.68  5439.0  436.88
  5466.6  437.14  5483.0  438.52  5548.9  440.27  5691.5  447.13  5717.3  447.84
#Mann=8,-1,0
  4086.6   0.035       0  4116.8    0.05       0  4910.9    0.07       0
  4996.5    0.05       0  5000.9    0.05       0  5004.9    0.05       0
  5014.7    0.07       0  5139.7    0.05       0
Bank Sta=5000.9,5004.9
Exp/Cntr=0.3,0.1

Chan Stop Cuts=-1