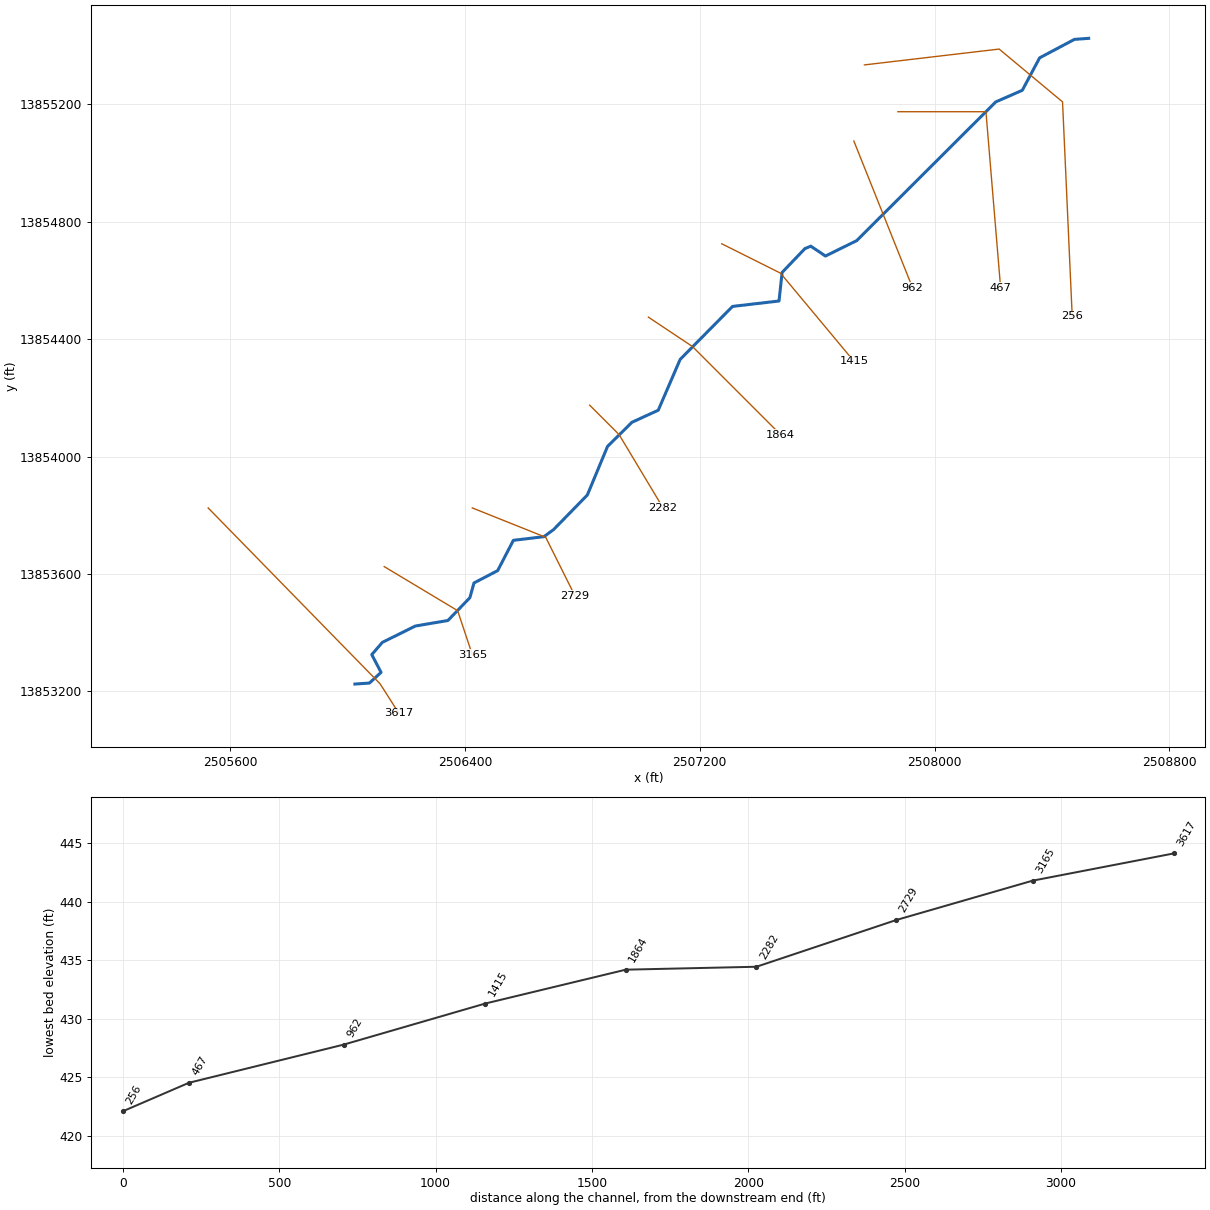
--- StreamM054.prj (project) ---

Proj Title=StreamM054 Base Level Engineering
Current Plan=p01
Default Exp/Contr=0.3,0.1
English Units
Geom File=g01
Flow File=f01
Plan File=p01
BEGIN DESCRIPTION:
StreamM054
END DESCRIPTION:

--- StreamM054.p01 (plan) ---

Plan Title=Multiple Run
Short Identifier=Multiple
Geom File=g01
Flow File=f01
Subcritical Flow
K Sum by GR= 0
Std Step Tol= 0.01
Critical Tol= 0.01
Num of Std Step Trials= 20
Max Error Tol= 0.3
Flow Tol Ratio= 0.001
Split Flow NTrial= 30
Split Flow Tol= 0.02
Split Flow Ratio= 0.02
Log Output Level= 0
Friction Slope Method= 1
Unsteady Friction Slope Method= 2
Unsteady Bridges Friction Slope Method= 1
Parabolic Critical Depth
Global Vel Dist=  1 , 1 , 1
Global Log Level= 0
CheckData=True
Encroach Param= -1, 0, 0, 0
BEGIN DESCRIPTION:
Multiple Run
END DESCRIPTION:

--- StreamM054.f01 (steady flow) ---

Flow Title=Multiple
Number of Profiles=7
Profile Names=10-year,25-year,50-year,1pct_min,100-year,1pct_plu,500-year
River Rch & RM= StreamM054,Reach-1,3617
     417     652     857     547    1092    2179    1752
Boundary for River Rch & Prof#=StreamM054,Reach-1,1
Up Type=0
Dn Type=3
Dn Slope=0.005
Boundary for River Rch & Prof#=StreamM054,Reach-1,2
Up Type=0
Dn Type=3
Dn Slope=0.005
Boundary for River Rch & Prof#=StreamM054,Reach-1,3
Up Type=0
Dn Type=3
Dn Slope=0.005
Boundary for River Rch & Prof#=StreamM054,Reach-1,4
Up Type=0
Dn Type=3
Dn Slope=0.005
Boundary for River Rch & Prof#=StreamM054,Reach-1,5
Up Type=0
Dn Type=3
Dn Slope=0.005
Boundary for River Rch & Prof#=StreamM054,Reach-1,6
Up Type=0
Dn Type=3
Dn Slope=0.005
Boundary for River Rch & Prof#=StreamM054,Reach-1,7
Up Type=0
Dn Type=3
Dn Slope=0.005

--- StreamM054.g01 (geometry) ---

Geom Title=Existing Conditions

River Reach=StreamM054,Reach-1
Reach XY= 30
      2506025.00     13853225.00      2506074.36     13853228.27
      2506114.13     13853264.76      2506082.45     13853325.21
      2506118.32     13853366.86      2506230.97     13853422.67
      2506341.79     13853441.45      2506416.73     13853519.23
      2506430.65     13853569.36      2506511.44     13853611.48
      2506564.90     13853714.61      2506669.10     13853727.15
      2506701.87     13853751.18      2506816.86     13853868.94
      2506885.76     13854034.70      2506968.95     13854116.84
      2507058.51     13854157.95      2507133.14     13854331.06
      2507311.69     13854511.63      2507469.92     13854530.04
      2507480.55     13854627.39      2507558.30     13854708.63
      2507578.32     13854716.86      2507628.23     13854683.25
      2507734.68     13854735.75      2508208.34     13855208.34
      2508298.83     13855247.87      2508357.94     13855358.52
      2508476.49     13855421.40      2508525.00     13855425.00

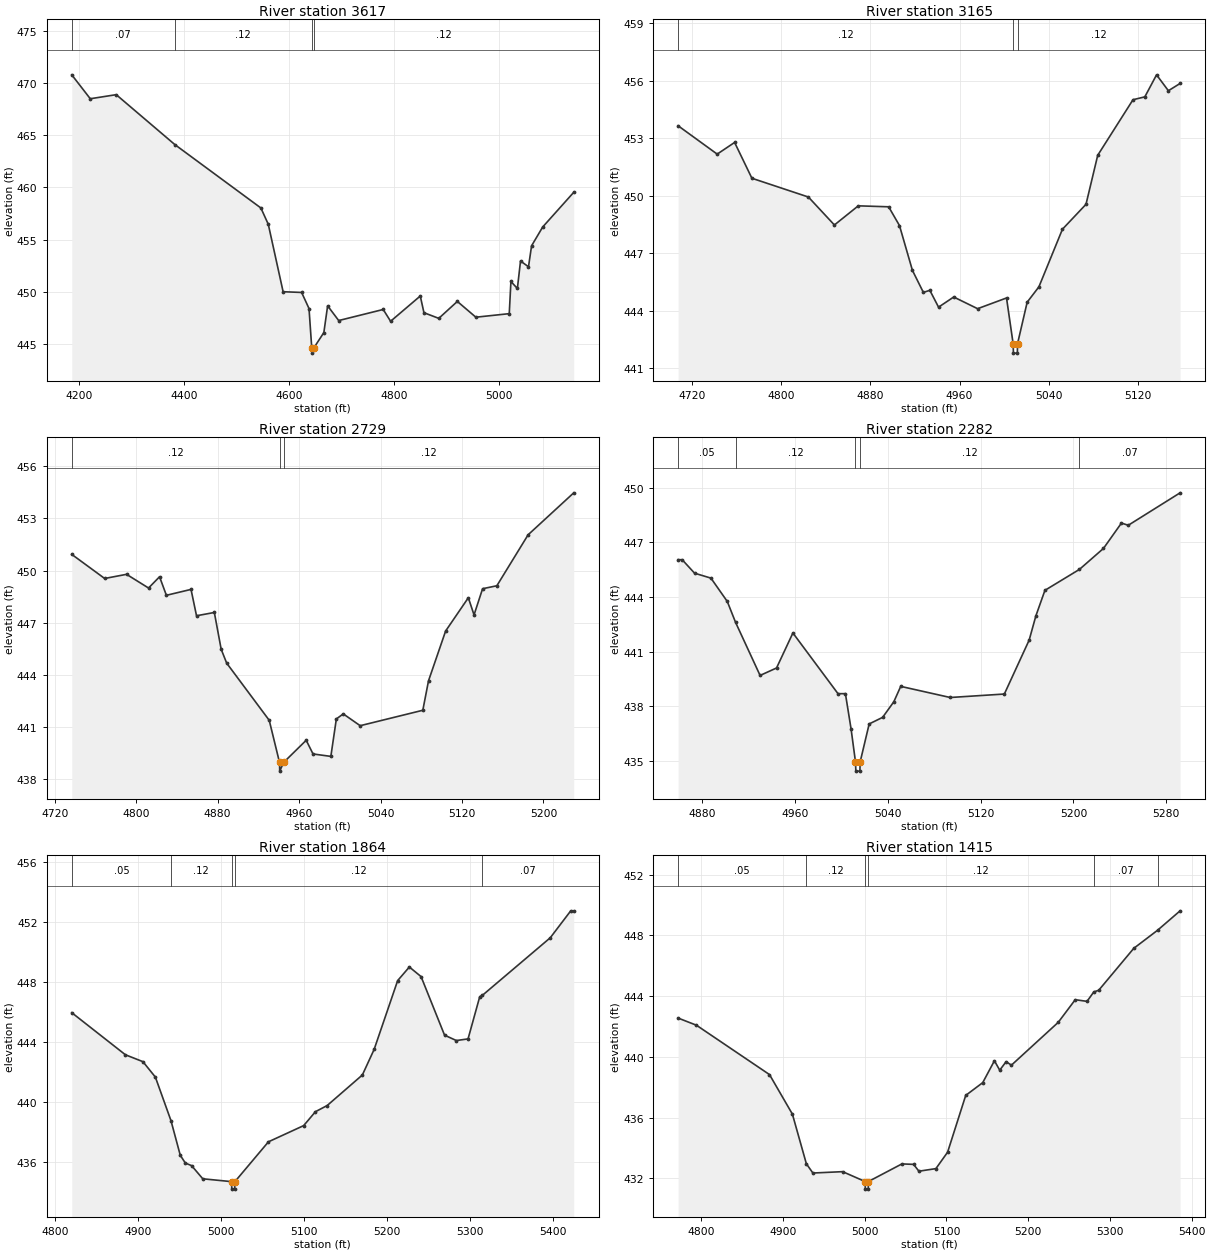
Type RM Length L Ch R = 1,3617,452,452,452
BEGIN DESCRIPTION:
StreamM054 8.0
END DESCRIPTION:
XS GIS Cut Line= 3
      2505525.02     13853824.98      2506111.00     13853225.46
      2506174.97     13853125.04
#Sta/Elev= 30
  4185.8  470.77  4221.1  468.48  4270.6  468.87  4382.4  464.09  4546.5  458.02
  4560.6  456.46  4588.9  450.00  4624.2  449.93  4638.3  448.39  4643.5  444.62
  4643.7  444.12  4647.5  444.62  4666.6  446.09  4673.8  448.65  4694.9  447.24
  4779.8  448.30  4793.9  447.17  4850.5  449.59  4857.5  447.99  4885.8  447.45
  4921.2  449.07  4956.5  447.56  5020.2  447.90  5023.4  450.98  5035.7  450.31
  5041.7  452.94  5056.9  452.39  5062.8  454.40  5084.0  456.20  5143.2  459.52
#Mann=4,-1,0
  4185.8    0.07       0  4382.4    0.12       0  4643.5    0.05       0
  4647.5    0.12       0
Bank Sta=4643.5,4647.5
Exp/Cntr=0.3,0.1

Type RM Length L Ch R = 1,3165,436,436,436
BEGIN DESCRIPTION:
StreamM054 7.0
END DESCRIPTION:
XS GIS Cut Line= 3
      2506124.97     13853625.02      2506375.00     13853475.00
      2506425.00     13853324.99
#Sta/Elev= 30
  4707.9  453.66  4742.9  452.18  4758.5  452.79  4774.0  450.92  4824.6  449.94
  4847.9  448.48  4869.3  449.48  4896.5  449.43  4906.2  448.45  4917.8  446.11
  4927.6  444.96  4933.4  445.07  4941.2  444.19  4954.8  444.72  4976.2  444.11
  5002.1  444.67  5008.0  442.29  5008.3  441.79  5011.8  441.79  5012.0  442.29
  5020.6  444.45  5031.1  445.25  5052.2  448.26  5073.3  449.56  5083.8  452.12
  5115.4  455.02  5126.0  455.17  5136.5  456.32  5147.1  455.49  5157.6  455.87
#Mann=3,-1,0
  4707.9    0.12       0  5008.0    0.05       0  5012.0    0.12       0
Bank Sta=5008,5012
Exp/Cntr=0.3,0.1

Type RM Length L Ch R = 1,2729,447,447,447
BEGIN DESCRIPTION:
StreamM054 6.0
END DESCRIPTION:
XS GIS Cut Line= 3
      2506425.01     13853825.00      2506675.00     13853725.00
      2506775.02     13853524.96
#Sta/Elev= 30
  4736.8  450.93  4769.1  449.54  4790.6  449.78  4812.2  448.99  4823.0  449.64
  4829.7  448.57  4853.9  448.91  4859.3  447.39  4876.8  447.58  4883.5  445.46
  4888.9  444.66  4930.7  441.36  4940.8  438.93  4941.0  438.43  4944.8  438.93
  4967.0  440.21  4973.7  439.42  4991.2  439.28  4996.6  441.44  5003.4  441.73
  5020.0  441.05  5081.5  441.94  5087.1  443.64  5103.9  446.51  5126.2  448.43
  5131.8  447.44  5140.2  448.95  5154.2  449.12  5184.9  452.06  5229.7  454.48
#Mann=3,-1,0
  4736.8    0.12       0  4940.8    0.05       0  4944.8    0.12       0
Bank Sta=4940.8,4944.8
Exp/Cntr=0.3,0.1

Type RM Length L Ch R = 1,2282,418,418,418
BEGIN DESCRIPTION:
StreamM054 5.0
END DESCRIPTION:
XS GIS Cut Line= 3
      2506824.99     13854175.01      2506925.00     13854075.00
      2507075.01     13853824.98
#Sta/Elev= 30
  4859.0  446.04  4862.5  446.04  4873.2  445.30  4887.3  445.03  4901.4  443.75
  4908.5  442.61  4929.7  439.69  4943.9  440.10  4958.0  442.02  4996.9  438.69
  5003.3  438.69  5008.2  436.75  5012.0  434.94  5012.3  434.44  5015.8  434.44
  5016.0  434.94  5023.8  437.03  5035.4  437.39  5045.1  438.25  5051.0  439.09
  5093.7  438.48  5140.4  438.67  5161.8  441.63  5167.6  442.96  5175.4  444.36
  5205.2  445.51  5225.9  446.66  5241.4  448.05  5247.3  447.93  5292.0  449.71
#Mann=5,-1,0
  4859.0    0.05       0  4908.5    0.12       0  5012.0    0.05       0
  5016.0    0.12       0  5205.2    0.07       0
Bank Sta=5012,5016
Exp/Cntr=0.3,0.1

Type RM Length L Ch R = 1,1864,449,449,449
BEGIN DESCRIPTION:
StreamM054 4.0
END DESCRIPTION:
XS GIS Cut Line= 3
      2507024.97     13854475.02      2507175.00     13854375.00
      2507475.01     13854074.99
#Sta/Elev= 30
  4819.9  445.97  4884.5  443.16  4905.6  442.70  4920.6  441.67  4939.4  438.76
  4950.6  436.45  4956.7  435.93  4964.2  435.76  4977.7  434.88  5012.4  434.69
  5012.6  434.19  5016.1  434.19  5016.4  434.69  5056.8  437.35  5099.2  438.43
  5113.4  439.36  5127.5  439.77  5169.9  441.81  5184.1  443.52  5212.4  448.11
  5226.5  449.02  5240.6  448.38  5268.9  444.47  5283.1  444.11  5297.2  444.22
  5311.3  447.04  5314.3  447.12  5396.2  450.97  5420.9  452.77  5424.5  452.77
#Mann=5,-1,0
  4819.9    0.05       0  4939.4    0.12       0  5012.4    0.05       0
  5016.4    0.12       0  5314.3    0.07       0
Bank Sta=5012.4,5016.4
Exp/Cntr=0.3,0.1

Type RM Length L Ch R = 1,1415,453,453,453
BEGIN DESCRIPTION:
StreamM054 3.0
END DESCRIPTION:
XS GIS Cut Line= 3
      2507274.97     13854725.02      2507475.00     13854625.00
      2507725.03     13854324.97
#Sta/Elev= 30
  4771.7  442.56  4794.1  442.09  4883.5  438.84  4911.5  436.24  4928.6  432.97
  4936.6  432.36  4973.0  432.45  5000.5  431.80  5000.8  431.30  5004.3  431.30
  5004.5  431.80  5045.5  432.96  5059.8  432.93  5066.3  432.48  5087.1  432.65
  5101.4  433.73  5123.6  437.47  5144.4  438.31  5158.7  439.75  5165.2  439.13
  5173.0  439.69  5179.5  439.46  5236.8  442.28  5257.6  443.77  5272.0  443.66
  5280.3  444.28  5286.3  444.39  5329.2  447.15  5358.3  448.34  5385.9  449.62
#Mann=6,-1,0
  4771.7    0.05       0  4928.6    0.12       0  5000.5    0.05       0
  5004.5    0.12       0  5280.3    0.07       0  5358.3    0.05       0
Bank Sta=5000.5,5004.5
Exp/Cntr=0.3,0.1

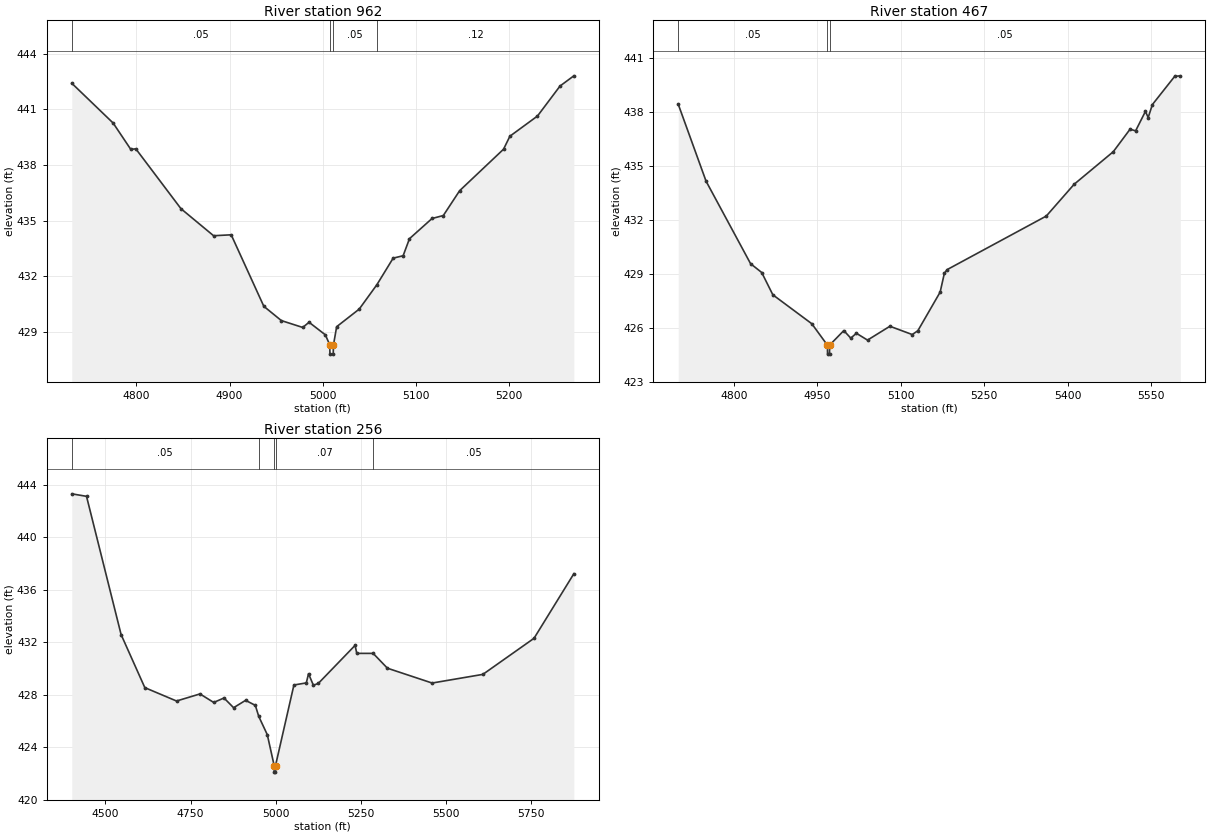
Type RM Length L Ch R = 1,962,495,495,495
BEGIN DESCRIPTION:
StreamM054 2.0
END DESCRIPTION:
XS GIS Cut Line= 3
      2507724.99     13855075.01      2507825.00     13854825.00
      2507924.99     13854575.03
#Sta/Elev= 30
  4730.7  442.41  4775.1  440.26  4794.0  438.84  4799.4  438.87  4847.8  435.64
  4882.8  434.18  4901.7  434.23  4936.7  430.37  4955.5  429.60  4978.4  429.23
  4985.2  429.51  5002.7  428.83  5007.4  428.29  5007.6  427.79  5011.1  427.79
  5011.4  428.29  5014.8  429.27  5039.0  430.22  5058.0  431.54  5075.4  432.97
  5086.1  433.10  5092.9  434.02  5117.1  435.11  5129.2  435.27  5146.7  436.61
  5193.8  438.85  5200.6  439.55  5230.2  440.64  5254.4  442.26  5269.2  442.81
#Mann=4,-1,0
  4730.7    0.05       0  5007.4    0.05       0  5011.4    0.05       0
  5058.0    0.12       0
Bank Sta=5007.4,5011.4
Exp/Cntr=0.3,0.1

Type RM Length L Ch R = 1,467,211,211,211
BEGIN DESCRIPTION:
StreamM054 1.0
END DESCRIPTION:
XS GIS Cut Line= 3
      2507875.00     13855175.00      2508175.00     13855175.00
      2508225.00     13854574.98
#Sta/Elev= 30
  4700.3  438.43  4750.3  434.15  4830.3  429.56  4850.3  429.07  4870.3  427.83
  4940.3  426.22  4968.3  425.03  4968.6  424.53  4972.1  424.53  4972.3  425.03
  4997.8  425.84  5010.3  425.42  5020.4  425.69  5040.4  425.31  5080.6  426.08
  5120.7  425.62  5130.8  425.83  5170.9  427.98  5178.4  429.02  5183.4  429.23
  5361.6  432.21  5411.7  433.98  5482.0  435.79  5512.1  437.04  5522.1  436.95
  5539.7  438.03  5544.7  437.69  5552.2  438.41  5592.3  439.98  5602.4  440.01
#Mann=3,-1,0
  4700.3    0.05       0  4968.3    0.05       0  4972.3    0.05       0
Bank Sta=4968.3,4972.3
Exp/Cntr=0.3,0.1

Type RM Length L Ch R = 1,256,0,0,0
BEGIN DESCRIPTION:
H21392
END DESCRIPTION:
XS GIS Cut Line= 4
      2507761.05     13855334.47      2508220.00     13855388.46
      2508436.00     13855208.46      2508468.93     13854478.20
#Sta/Elev= 30
  4401.1  443.31  4444.4  443.12  4546.0  432.58  4615.6  428.54  4708.7  427.52
  4777.6  428.06  4817.9  427.41  4848.1  427.75  4876.3  427.01  4911.5  427.57
  4940.1  427.19  4950.1  426.35  4975.3  424.95  4995.4  422.60  4995.6  422.10
  4999.1  422.10  4999.4  422.60  5053.4  428.74  5089.8  428.90  5096.3  429.60
  5110.6  428.72  5125.0  428.86  5233.0  431.76  5238.0  431.15  5286.1  431.15
  5328.0  430.02  5459.2  428.89  5608.3  429.55  5758.5  432.30  5875.4  437.22
#Mann=5,-1,0
  4401.1    0.05       0  4950.1    0.07       0  4995.4    0.05       0
  4999.4    0.07       0  5286.1    0.05       0
Bank Sta=4995.4,4999.4
Exp/Cntr=0.3,0.1

Chan Stop Cuts=-1