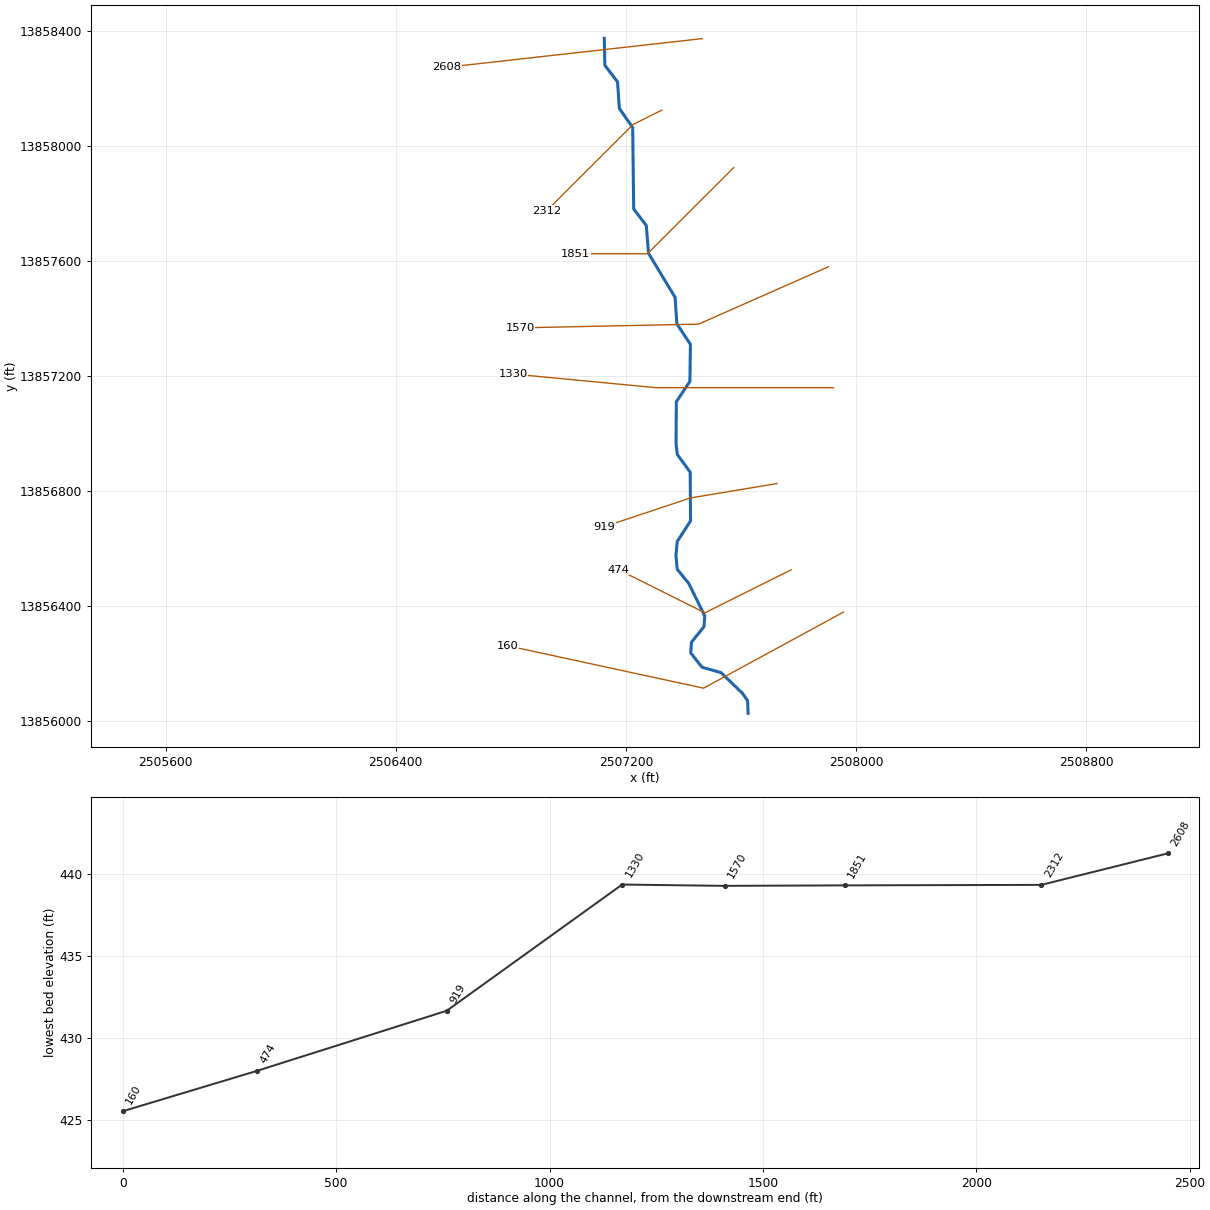
--- StreamM055.prj (project) ---

Proj Title=StreamM055 Base Level Engineering
Current Plan=p01
Default Exp/Contr=0.3,0.1
English Units
Geom File=g01
Flow File=f01
Plan File=p01
BEGIN DESCRIPTION:
StreamM055
END DESCRIPTION:

--- StreamM055.p01 (plan) ---

Plan Title=Multiple Run
Short Identifier=Multiple
Geom File=g01
Flow File=f01
Subcritical Flow
K Sum by GR= 0
Std Step Tol= 0.01
Critical Tol= 0.01
Num of Std Step Trials= 20
Max Error Tol= 0.3
Flow Tol Ratio= 0.001
Split Flow NTrial= 30
Split Flow Tol= 0.02
Split Flow Ratio= 0.02
Log Output Level= 0
Friction Slope Method= 1
Unsteady Friction Slope Method= 2
Unsteady Bridges Friction Slope Method= 1
Parabolic Critical Depth
Global Vel Dist=  1 , 1 , 1
Global Log Level= 0
CheckData=True
Encroach Param= -1, 0, 0, 0
BEGIN DESCRIPTION:
Multiple Run
END DESCRIPTION:

--- StreamM055.f01 (steady flow) ---

Flow Title=Multiple
Number of Profiles=7
Profile Names=10-year,25-year,50-year,1pct_min,100-year,1pct_plu,500-year
River Rch & RM= StreamM055,Reach-1,2608
     660    1065    1432     933    1862    3716    3117
Boundary for River Rch & Prof#=StreamM055,Reach-1,1
Up Type=0
Dn Type=3
Dn Slope=0.005
Boundary for River Rch & Prof#=StreamM055,Reach-1,2
Up Type=0
Dn Type=3
Dn Slope=0.005
Boundary for River Rch & Prof#=StreamM055,Reach-1,3
Up Type=0
Dn Type=3
Dn Slope=0.005
Boundary for River Rch & Prof#=StreamM055,Reach-1,4
Up Type=0
Dn Type=3
Dn Slope=0.005
Boundary for River Rch & Prof#=StreamM055,Reach-1,5
Up Type=0
Dn Type=3
Dn Slope=0.005
Boundary for River Rch & Prof#=StreamM055,Reach-1,6
Up Type=0
Dn Type=3
Dn Slope=0.005
Boundary for River Rch & Prof#=StreamM055,Reach-1,7
Up Type=0
Dn Type=3
Dn Slope=0.005

--- StreamM055.g01 (geometry) ---

Geom Title=Existing Conditions

River Reach=StreamM055,Reach-1
Reach XY= 30
      2507125.00     13858375.00      2507127.10     13858280.87
      2507171.17     13858223.42      2507177.35     13858130.98
      2507223.78     13858064.50      2507227.26     13857780.94
      2507271.14     13857723.40      2507278.83     13857626.58
      2507371.17     13857473.42      2507377.36     13857380.98
      2507424.50     13857309.78      2507422.75     13857180.94
      2507375.52     13857109.78      2507374.54     13856964.82
      2507378.78     13856926.57      2507423.78     13856864.49
      2507424.93     13856695.03      2507378.70     13856623.40
      2507374.18     13856575.00      2507378.67     13856526.58
      2507418.88     13856477.18      2507474.25     13856364.31
      2507471.60     13856326.72      2507428.36     13856273.24
      2507425.54     13856235.47      2507464.89     13856185.65
      2507531.04     13856166.85      2507605.24     13856095.14
      2507623.33     13856068.87      2507625.00     13856025.00

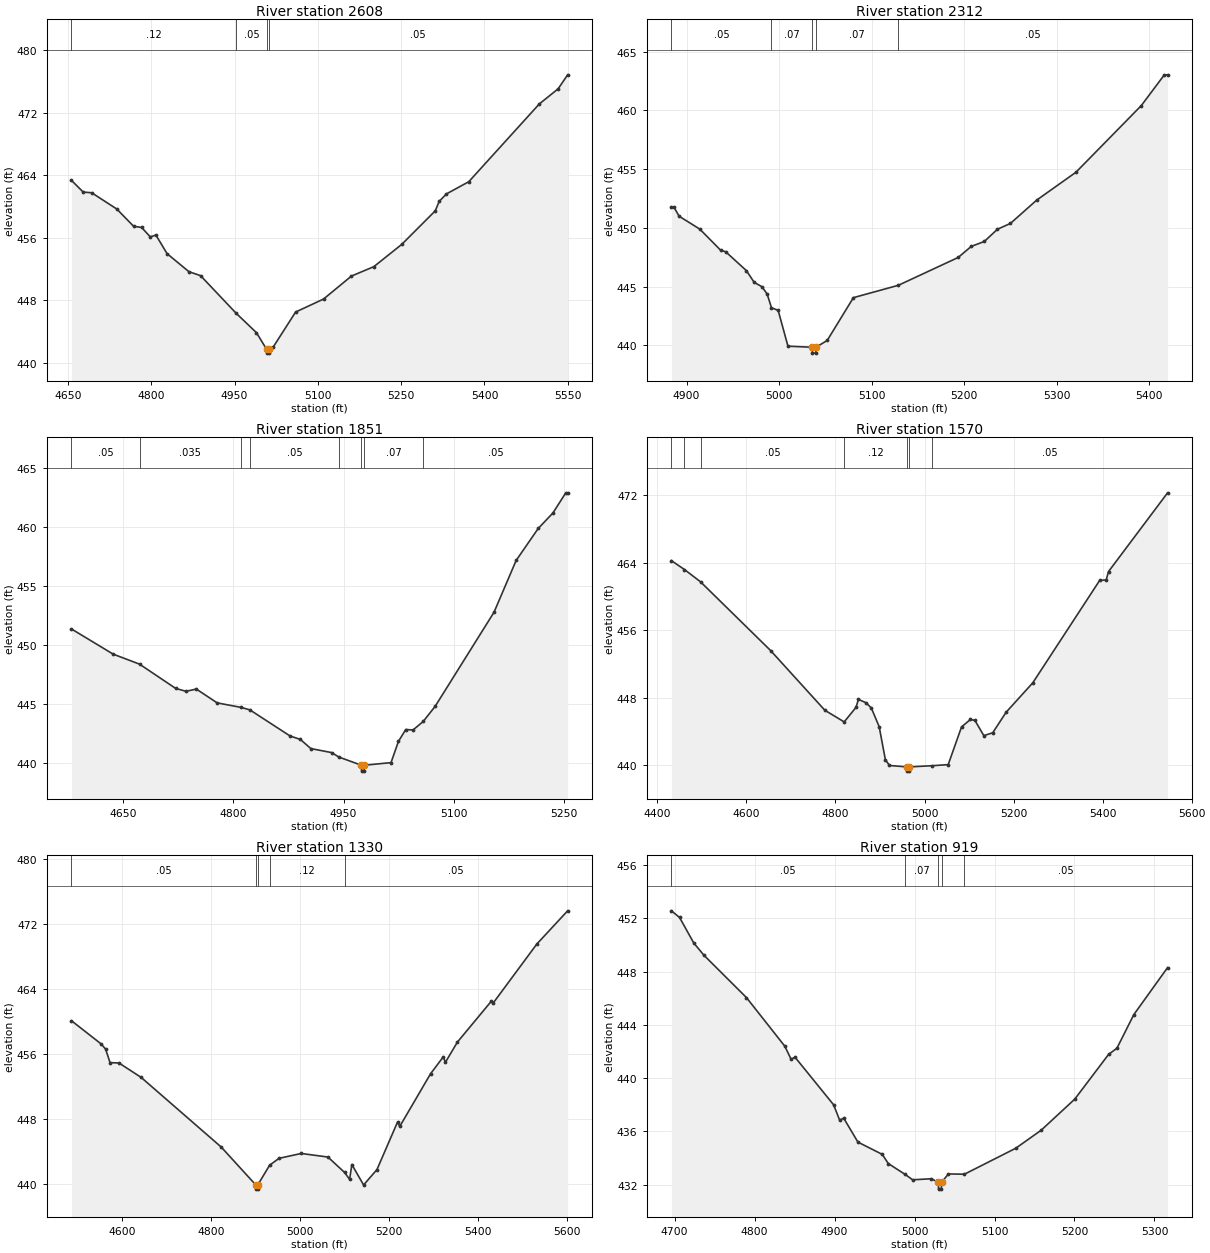
Type RM Length L Ch R = 1,2608,296,296,296
BEGIN DESCRIPTION:
H21395
END DESCRIPTION:
XS GIS Cut Line= 2
      2507466.08     13858374.05      2506578.15     13858274.43
#Sta/Elev= 30
  4656.3  463.35  4677.5  461.85  4692.6  461.77  4737.9  459.69  4768.1  457.49
  4782.7  457.33  4798.3  456.12  4808.3  456.37  4828.5  453.98  4867.8  451.68
  4888.8  451.17  4952.8  446.37  4989.5  443.88  5007.6  441.77  5007.8  441.27
  5011.3  441.27  5011.6  441.77  5019.6  442.05  5059.9  446.52  5110.2  448.18
  5160.5  451.12  5200.8  452.32  5251.1  455.17  5311.5  459.46  5318.5  460.67
  5331.6  461.62  5371.8  463.18  5498.7  473.11  5532.8  475.06  5549.8  476.84
#Mann=4,-1,0
  4656.3    0.12       0  4952.8    0.05       0  5007.6    0.05       0
  5011.6    0.05       0
Bank Sta=5007.6,5011.6
Exp/Cntr=0.3,0.1

Type RM Length L Ch R = 1,2312,461,461,461
BEGIN DESCRIPTION:
StreamM055 5.0
END DESCRIPTION:
XS GIS Cut Line= 3
      2507324.96     13858124.98      2507225.00     13858075.00
      2506925.02     13857775.02
#Sta/Elev= 30
  4883.7  451.76  4886.5  451.76  4892.0  451.00  4914.4  449.90  4936.8  448.11
  4942.4  447.97  4964.7  446.37  4973.1  445.37  4981.5  445.00  4987.1  444.38
  4991.8  443.21  4999.0  442.99  5009.6  439.94  5035.9  439.85  5036.1  439.35
  5039.6  439.35  5039.9  439.85  5052.0  440.43  5080.3  444.07  5128.8  445.12
  5193.5  447.49  5207.6  448.43  5221.7  448.85  5235.9  449.89  5250.0  450.39
  5278.3  452.37  5320.7  454.74  5391.4  460.42  5416.2  463.03  5419.7  463.03
#Mann=5,-1,0
  4883.7    0.05       0  4991.8    0.07       0  5035.9    0.05       0
  5039.9    0.07       0  5128.8    0.05       0
Bank Sta=5035.9,5039.9
Exp/Cntr=0.3,0.1

Type RM Length L Ch R = 1,1851,281,281,281
BEGIN DESCRIPTION:
StreamM055 4.0
END DESCRIPTION:
XS GIS Cut Line= 3
      2507575.03     13857925.03      2507275.00     13857625.00
      2507025.00     13857625.00
#Sta/Elev= 30
  4580.3  451.36  4636.9  449.23  4672.8  448.38  4721.8  446.33  4735.9  446.08
  4750.0  446.27  4778.3  445.10  4810.6  444.72  4822.7  444.51  4877.3  442.30
  4891.5  442.00  4905.6  441.23  4933.9  440.89  4943.8  440.51  4974.3  439.82
  4974.6  439.32  4978.1  439.32  4978.3  439.82  5014.6  440.04  5024.6  441.83
  5034.6  442.84  5044.6  442.81  5058.4  443.53  5074.6  444.81  5154.6  452.78
  5184.6  457.16  5214.6  459.87  5234.6  461.18  5252.1  462.89  5254.6  462.89
#Mann=8,-1,0
  4580.3    0.05       0  4672.8   0.035       0  4810.6    0.07       0
  4822.7    0.05       0  4943.8    0.07       0  4974.3    0.05       0
  4978.3    0.07       0  5058.4    0.05       0
Bank Sta=4974.3,4978.3
Exp/Cntr=0.3,0.1

Type RM Length L Ch R = 1,1570,240,240,240
BEGIN DESCRIPTION:
StreamM055 3.0
END DESCRIPTION:
XS GIS Cut Line= 3
      2507904.39     13857579.77      2507453.02     13857380.12
      2506832.41     13857367.10
#Sta/Elev= 30
  4431.6  464.26  4460.9  463.21  4497.0  461.75  4654.3  453.60  4776.2  446.51
  4819.6  445.13  4846.1  446.85  4851.6  447.80  4868.3  447.41  4880.4  446.80
  4898.2  444.56  4912.1  440.65  4921.3  439.96  4961.2  439.79  4961.4  439.29
  4964.9  439.29  4965.2  439.79  5016.5  439.93  5053.2  440.06  5083.2  444.54
  5103.2  445.42  5113.2  445.31  5133.2  443.50  5153.2  443.84  5183.2  446.27
  5243.2  449.77  5393.3  461.91  5408.0  461.98  5413.3  462.97  5545.9  472.31
#Mann=7,-1,0
  4431.6    0.05       0  4460.9    0.07       0  4497.0    0.05       0
  4819.6    0.12       0  4961.2    0.05       0  4965.2    0.12       0
  5016.5    0.05       0
Bank Sta=4961.2,4965.2
Exp/Cntr=0.3,0.1

Type RM Length L Ch R = 1,1330,411,411,411
BEGIN DESCRIPTION:
H21394
END DESCRIPTION:
XS GIS Cut Line= 3
      2507921.82     13857158.77      2507305.45     13857158.77
      2506808.19     13857206.33
#Sta/Elev= 30
  4486.6  460.10  4553.4  457.24  4563.4  456.60  4573.4  454.94  4593.4  454.90
  4643.4  453.12  4823.4  444.55  4901.4  439.87  4901.7  439.37  4905.2  439.37
  4905.4  439.87  4932.2  442.31  4953.4  443.16  5003.4  443.76  5063.4  443.32
  5100.9  441.42  5112.2  440.57  5117.2  442.40  5143.6  439.88  5173.7  441.78
  5219.9  447.62  5225.0  447.09  5294.3  453.58  5322.7  455.64  5327.7  454.99
  5354.6  457.47  5430.4  462.47  5435.5  462.31  5533.2  469.54  5602.5  473.63
#Mann=5,-1,0
  4486.6    0.05       0  4901.4    0.05       0  4905.4    0.05       0
  4932.2    0.12       0  5100.9    0.05       0
Bank Sta=4901.4,4905.4
Exp/Cntr=0.3,0.1

Type RM Length L Ch R = 1,919,445,445,445
BEGIN DESCRIPTION:
StreamM055 2.0
END DESCRIPTION:
XS GIS Cut Line= 3
      2507725.02     13856825.00      2507425.00     13856775.00
      2507124.98     13856674.99
#Sta/Elev= 30
  4696.0  452.56  4706.2  452.06  4723.9  450.15  4736.6  449.23  4789.8  446.05
  4837.9  442.39  4845.6  441.42  4850.6  441.57  4898.8  438.00  4906.4  436.84
  4911.4  437.00  4929.2  435.20  4959.6  434.28  4967.2  433.59  4988.1  432.78
  4997.6  432.37  5021.2  432.45  5029.8  432.17  5030.0  431.67  5033.5  431.67
  5033.8  432.17  5042.3  432.81  5062.4  432.79  5126.6  434.74  5158.3  436.09
  5200.4  438.43  5242.6  441.78  5253.1  442.25  5274.2  444.77  5316.4  448.30
#Mann=5,-1,0
  4696.0    0.05       0  4988.1    0.07       0  5029.8    0.05       0
  5033.8    0.07       0  5062.4    0.05       0
Bank Sta=5029.8,5033.8
Exp/Cntr=0.3,0.1

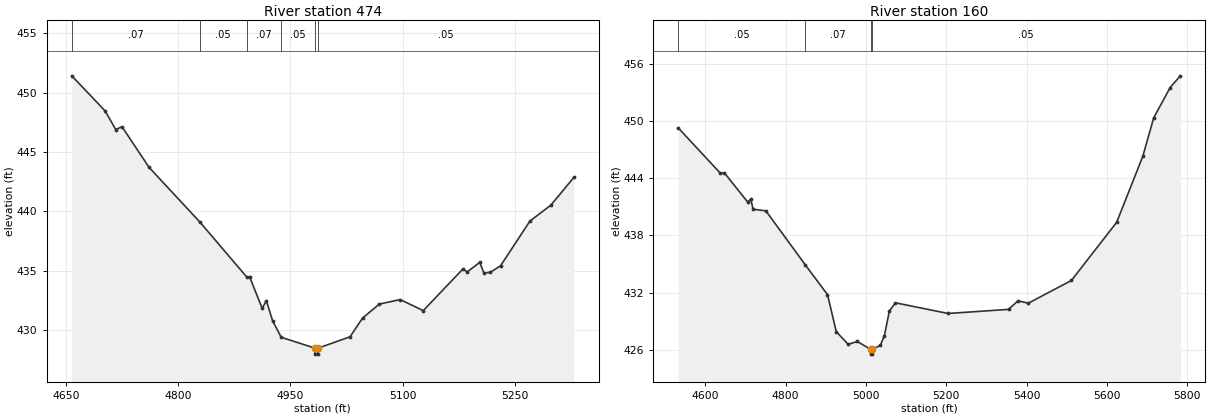
Type RM Length L Ch R = 1,474,314,314,314
BEGIN DESCRIPTION:
StreamM055 1.0
END DESCRIPTION:
XS GIS Cut Line= 3
      2507775.01     13856525.00      2507475.00     13856375.00
      2507175.03     13856524.99
#Sta/Elev= 30
  4658.1  451.41  4702.8  448.45  4716.8  446.89  4725.2  447.13  4761.5  443.70
  4829.0  439.13  4892.1  434.47  4895.7  434.51  4912.5  431.85  4918.1  432.50
  4926.4  430.81  4937.9  429.42  4983.1  428.50  4983.4  428.00  4986.9  428.00
  4987.1  428.50  5029.9  429.46  5046.6  431.03  5069.0  432.21  5096.9  432.59
  5127.7  431.66  5180.8  435.17  5186.4  434.91  5203.2  435.72  5208.7  434.83
  5217.1  434.87  5231.1  435.44  5270.2  439.19  5298.2  440.53  5328.9  442.86
#Mann=6,-1,0
  4658.1    0.07       0  4829.0    0.05       0  4892.1    0.07       0
  4937.9    0.05       0  4983.1    0.05       0  4987.1    0.05       0
Bank Sta=4983.1,4987.1
Exp/Cntr=0.3,0.1

Type RM Length L Ch R = 1,160,0,0,0
BEGIN DESCRIPTION:
H21393
END DESCRIPTION:
XS GIS Cut Line= 3
      2507956.48     13856377.51      2507470.38     13856112.76
      2506790.27     13856260.05
#Sta/Elev= 30
  4532.9  449.30  4637.5  444.55  4647.9  444.57  4705.4  441.53  4713.5  441.81
  4719.2  440.76  4750.9  440.59  4848.7  434.94  4904.3  431.79  4926.2  427.90
  4955.9  426.57  4978.7  426.87  5011.5  426.04  5011.8  425.54  5015.3  425.54
  5015.5  426.04  5035.6  426.45  5045.8  427.46  5058.4  430.08  5073.4  430.93
  5204.5  429.81  5354.8  430.24  5378.4  431.14  5404.1  430.89  5511.4  433.28
  5624.0  439.39  5689.0  446.32  5716.1  450.36  5757.0  453.54  5782.3  454.77
#Mann=4,-1,0
  4532.9    0.05       0  4848.7    0.07       0  5011.5    0.05       0
  5015.5    0.05       0
Bank Sta=5011.5,5015.5
Exp/Cntr=0.3,0.1

Chan Stop Cuts=-1