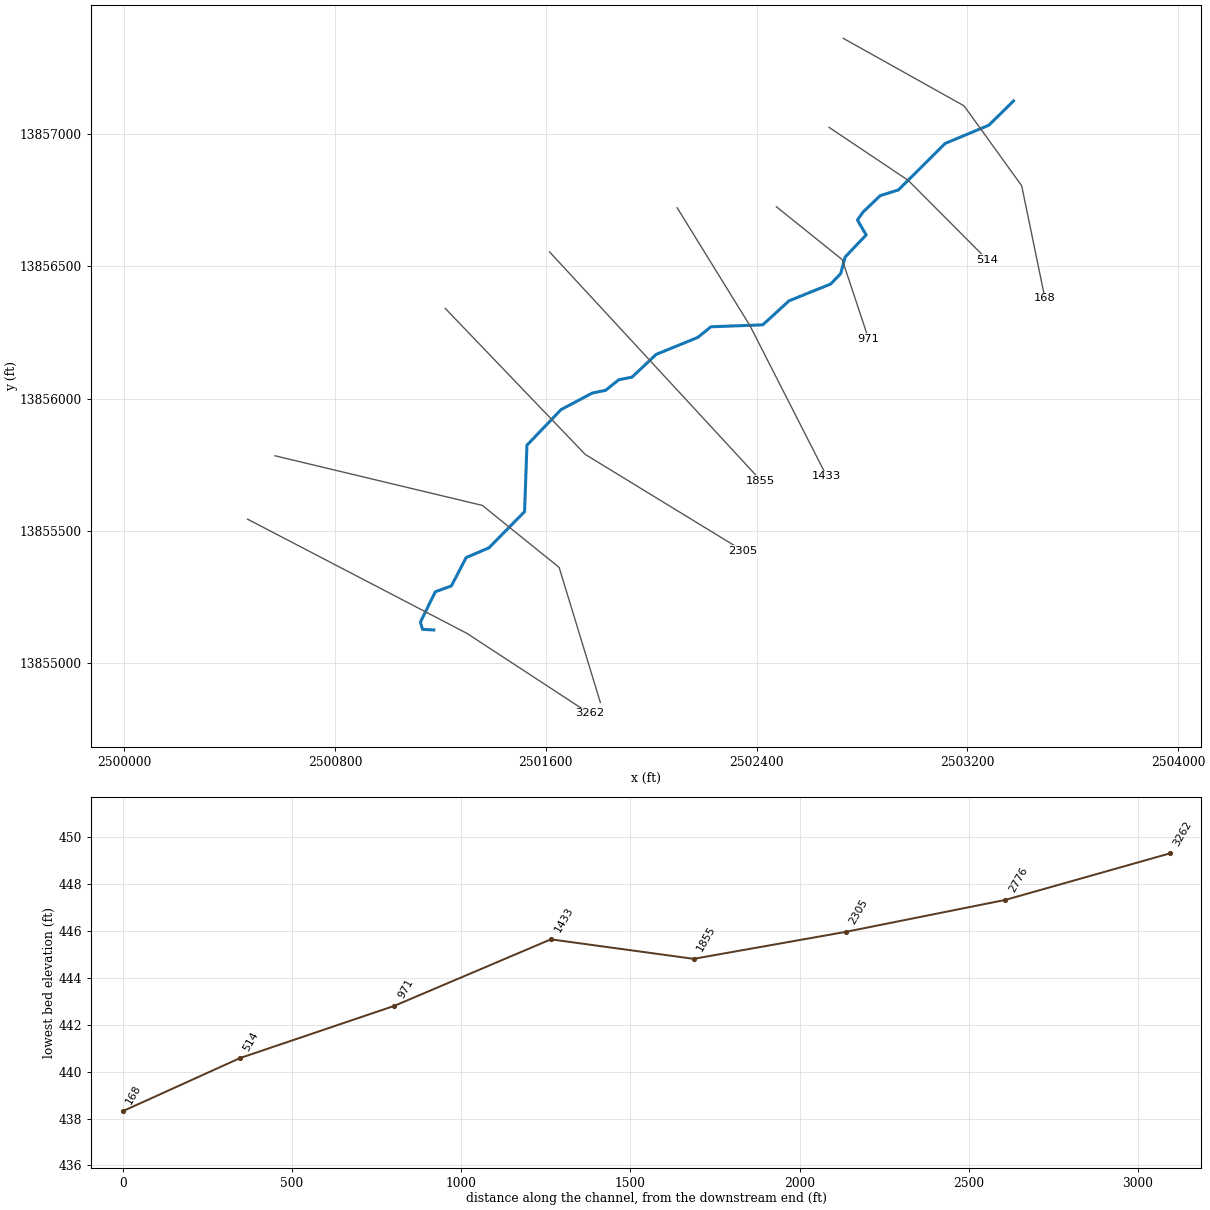
--- StreamM056.prj (project) ---

Proj Title=StreamM056 Base Level Engineering
Current Plan=p01
Default Exp/Contr=0.3,0.1
English Units
Geom File=g01
Flow File=f01
Plan File=p01
BEGIN DESCRIPTION:
StreamM056
END DESCRIPTION:

--- StreamM056.p01 (plan) ---

Plan Title=Multiple Run
Short Identifier=Multiple
Geom File=g01
Flow File=f01
Subcritical Flow
K Sum by GR= 0
Std Step Tol= 0.01
Critical Tol= 0.01
Num of Std Step Trials= 20
Max Error Tol= 0.3
Flow Tol Ratio= 0.001
Split Flow NTrial= 30
Split Flow Tol= 0.02
Split Flow Ratio= 0.02
Log Output Level= 0
Friction Slope Method= 1
Unsteady Friction Slope Method= 2
Unsteady Bridges Friction Slope Method= 1
Parabolic Critical Depth
Global Vel Dist=  1 , 1 , 1
Global Log Level= 0
CheckData=True
Encroach Param= -1, 0, 0, 0
BEGIN DESCRIPTION:
Multiple Run
END DESCRIPTION:

--- StreamM056.f01 (steady flow) ---

Flow Title=Multiple
Number of Profiles=7
Profile Names=10-year,25-year,50-year,1pct_min,100-year,1pct_plu,500-year
River Rch & RM= StreamM056,Reach-1,3262
     605     974    1307     852    1699    3391    2840
River Rch & RM= StreamM056,Reach-1,1855
     799    1309    1778    1172    2337    4664    3995
Boundary for River Rch & Prof#=StreamM056,Reach-1,1
Up Type=0
Dn Type=3
Dn Slope=0.005
Boundary for River Rch & Prof#=StreamM056,Reach-1,2
Up Type=0
Dn Type=3
Dn Slope=0.005
Boundary for River Rch & Prof#=StreamM056,Reach-1,3
Up Type=0
Dn Type=3
Dn Slope=0.005
Boundary for River Rch & Prof#=StreamM056,Reach-1,4
Up Type=0
Dn Type=3
Dn Slope=0.005
Boundary for River Rch & Prof#=StreamM056,Reach-1,5
Up Type=0
Dn Type=3
Dn Slope=0.005
Boundary for River Rch & Prof#=StreamM056,Reach-1,6
Up Type=0
Dn Type=3
Dn Slope=0.005
Boundary for River Rch & Prof#=StreamM056,Reach-1,7
Up Type=0
Dn Type=3
Dn Slope=0.005

--- StreamM056.g01 (geometry) ---

Geom Title=Existing Conditions

River Reach=StreamM056,Reach-1
Reach XY= 30
      2501175.00     13855125.00      2501132.23     13855127.61
      2501124.44     13855154.74      2501180.61     13855269.38
      2501241.85     13855291.58      2501297.86     13855398.83
      2501384.66     13855435.79      2501519.54     13855572.55
      2501528.54     13855823.54      2501658.32     13855958.36
      2501776.72     13856020.84      2501827.20     13856031.08
      2501876.74     13856070.81      2501927.29     13856080.85
      2502018.95     13856166.84      2502177.18     13856231.12
      2502226.55     13856271.25      2502423.53     13856278.55
      2502522.71     13856369.15      2502681.34     13856433.02
      2502719.25     13856472.46      2502735.83     13856534.66
      2502815.68     13856618.34      2502782.56     13856675.01
      2502804.07     13856705.07      2502868.92     13856766.84
      2502938.21     13856788.63      2503115.32     13856964.24
      2503281.08     13857033.09      2503375.00     13857125.00

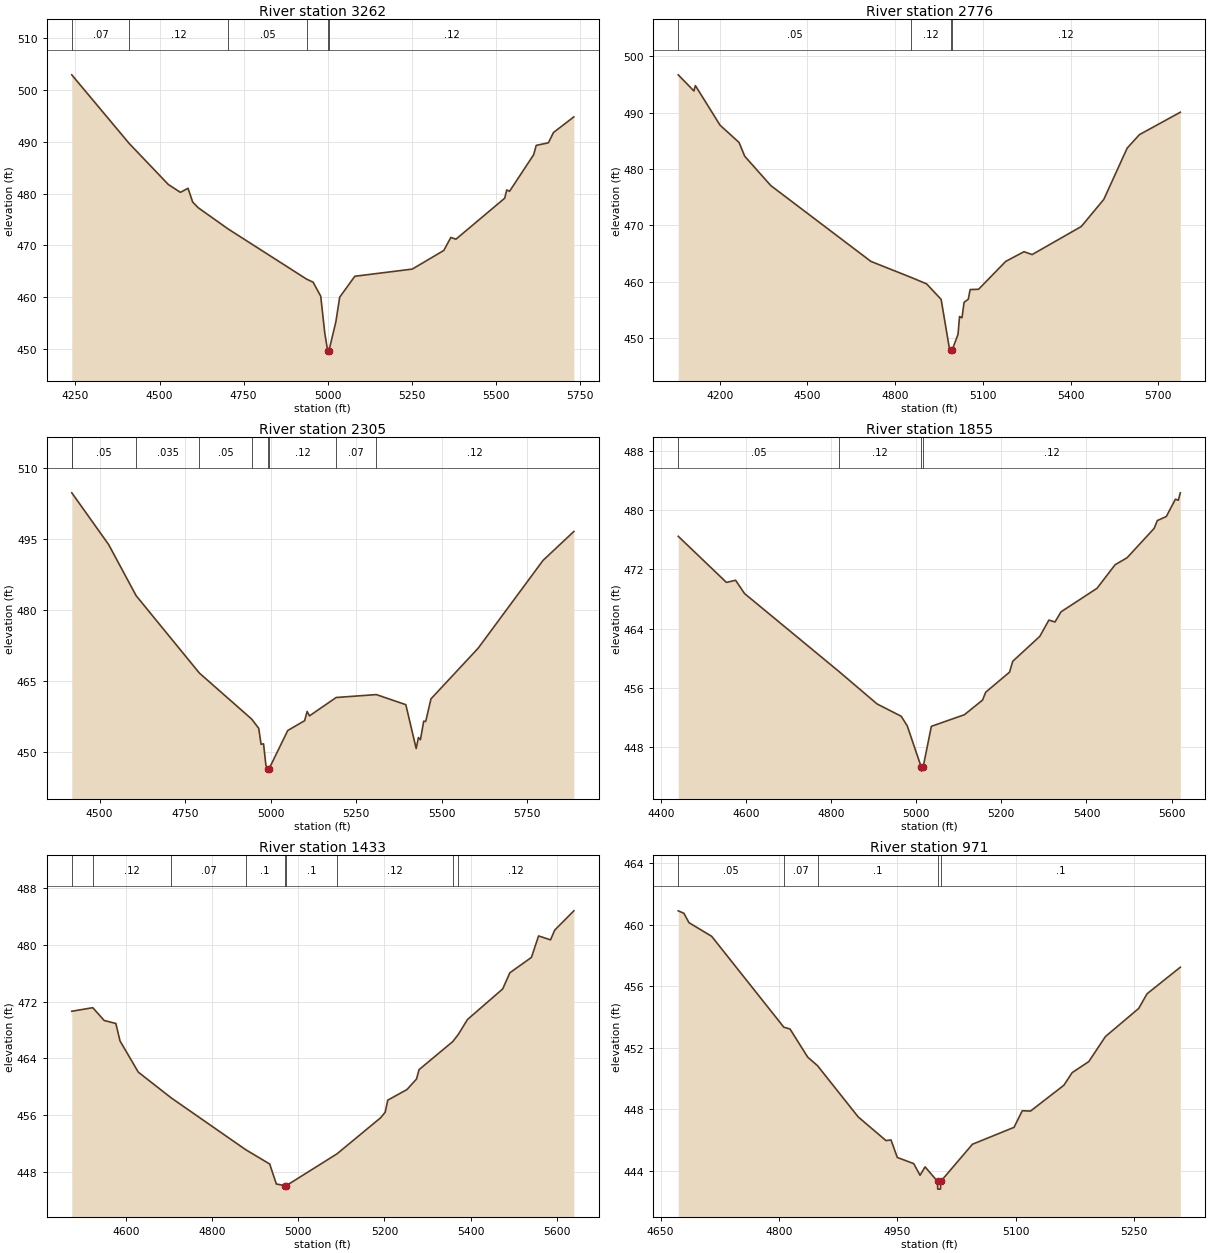
Type RM Length L Ch R = 1,3262,486,486,486
BEGIN DESCRIPTION:
H21400
END DESCRIPTION:
XS GIS Cut Line= 3
      2500468.43     13855543.95      2501301.74     13855111.67
      2501764.99     13854809.78
#Sta/Elev= 30
  4239.3  502.84  4409.8  489.64  4526.5  481.72  4562.1  480.23  4584.7  481.01
  4598.5  478.37  4614.9  477.27  4704.4  473.16  4937.0  463.53  4956.4  462.94
  4979.0  460.24  4991.0  453.15  4999.5  449.79  4999.7  449.29  5003.5  449.79
  5024.0  455.33  5035.3  460.05  5080.3  464.08  5251.0  465.46  5344.5  469.04
  5365.6  471.55  5380.7  471.21  5525.6  479.10  5531.6  480.69  5540.0  480.43
  5611.7  487.48  5619.2  489.26  5655.4  489.76  5670.5  491.74  5731.0  494.75
#Mann=6,-1,0
  4239.3    0.07       0  4409.8    0.12       0  4704.4    0.05       0
  4937.0    0.12       0  4999.5    0.05       0  5003.5    0.12       0
Bank Sta=4999.5,5003.5
Exp/Cntr=0.3,0.1

Type RM Length L Ch R = 1,2776,471,471,471
BEGIN DESCRIPTION:
H21399
END DESCRIPTION:
XS GIS Cut Line= 4
      2500572.56     13855783.55      2501359.03     13855596.04
      2501650.70     13855361.67      2501806.96     13854851.23
#Sta/Elev= 30
  4058.3  496.70  4111.9  493.84  4117.0  494.79  4201.3  487.76  4266.4  484.69
  4285.5  482.26  4374.9  477.04  4717.0  463.59  4854.4  460.75  4907.5  459.60
  4957.1  456.85  4985.9  447.98  4990.3  447.81  4990.5  447.31  4994.3  447.81
  5014.7  450.62  5020.1  453.81  5028.4  453.58  5035.5  456.32  5049.9  456.88
  5056.3  458.59  5085.1  458.64  5177.9  463.59  5240.5  465.31  5268.2  464.80
  5436.2  469.78  5513.3  474.60  5593.1  483.69  5634.9  486.08  5774.8  490.06
#Mann=4,-1,0
  4058.3    0.05       0  4854.4    0.12       0  4990.3    0.05       0
  4994.3    0.12       0
Bank Sta=4990.3,4994.3
Exp/Cntr=0.3,0.1

Type RM Length L Ch R = 1,2305,450,450,450
BEGIN DESCRIPTION:
H21398
END DESCRIPTION:
XS GIS Cut Line= 3
      2501218.41     13856340.83      2501749.66     13855788.75
      2502348.65     13855424.15
#Sta/Elev= 30
  4418.6  504.70  4418.9  504.67  4420.3  504.54  4526.3  493.79  4606.7  482.99
  4791.6  466.65  4944.1  456.96  4965.0  454.99  4971.9  451.61  4979.1  451.72
  4986.0  447.21  4991.3  446.45  4991.5  445.95  4995.3  446.45  5049.9  454.53
  5099.2  456.60  5106.5  458.55  5113.4  457.62  5191.2  461.49  5308.6  462.11
  5394.9  459.98  5425.2  450.72  5431.7  453.04  5437.6  452.57  5447.2  456.49
  5453.0  456.44  5468.5  461.21  5606.0  471.87  5795.9  490.43  5886.0  496.54
#Mann=10,-1,0
  4418.6    0.05       0  4418.9   0.035       0  4420.3    0.05       0
  4606.7   0.035       0  4791.6    0.05       0  4944.1    0.12       0
  4991.3    0.05       0  4995.3    0.12       0  5191.2    0.07       0
  5308.6    0.12       0
Bank Sta=4991.3,4995.3
Exp/Cntr=0.3,0.1

Type RM Length L Ch R = 1,1855,422,422,422
BEGIN DESCRIPTION:
H21397
END DESCRIPTION:
XS GIS Cut Line= 2
      2501614.25     13856554.36      2502416.24     13855689.88
#Sta/Elev= 30
  4441.2  476.47  4554.4  470.25  4575.9  470.54  4596.9  468.75  4818.2  458.26
  4908.2  453.86  4964.9  452.20  4979.1  450.90  5012.2  445.30  5012.5  444.80
  5016.2  445.30  5035.7  450.84  5113.4  452.41  5155.9  454.38  5163.3  455.44
  5219.4  458.15  5226.8  459.61  5290.3  462.97  5311.8  465.17  5326.0  464.91
  5340.2  466.28  5424.7  469.45  5467.2  472.63  5495.5  473.58  5559.0  477.54
  5566.4  478.59  5587.4  479.13  5608.9  481.47  5615.7  481.33  5620.4  482.33
#Mann=4,-1,0
  4441.2    0.05       0  4818.2    0.12       0  5012.2    0.05       0
  5016.2    0.12       0
Bank Sta=5012.2,5016.2
Exp/Cntr=0.3,0.1

Type RM Length L Ch R = 1,1433,462,462,462
BEGIN DESCRIPTION:
StreamM056 3.0
END DESCRIPTION:
XS GIS Cut Line= 3
      2502098.62     13856721.03      2502375.00     13856275.00
      2502666.33     13855705.40
#Sta/Elev= 30
  4474.8  470.64  4523.6  471.14  4550.0  469.34  4577.1  468.92  4586.6  466.48
  4629.1  462.08  4705.2  458.47  4878.4  451.17  4933.9  449.16  4949.3  446.35
  4968.6  446.13  4968.8  445.63  4972.6  446.13  5089.9  450.59  5191.1  455.66
  5201.7  456.44  5207.7  458.14  5252.2  459.63  5274.4  461.11  5280.3  462.43
  5358.7  466.39  5371.3  467.38  5392.6  469.48  5474.3  473.78  5490.9  476.05
  5540.9  478.21  5557.5  481.23  5585.3  480.68  5594.8  482.04  5639.3  484.76
#Mann=9,-1,0
  4474.8    0.05       0  4523.6    0.12       0  4705.2    0.07       0
  4878.4     0.1       0  4968.6    0.05       0  4972.6     0.1       0
  5089.9    0.12       0  5358.7     0.1       0  5371.3    0.12       0
Bank Sta=4968.6,4972.6
Exp/Cntr=0.3,0.1

Type RM Length L Ch R = 1,971,457,457,457
BEGIN DESCRIPTION:
StreamM056 2.0
END DESCRIPTION:
XS GIS Cut Line= 3
      2502475.01     13856724.99      2502725.00     13856525.00
      2502825.01     13856224.98
#Sta/Elev= 30
  4672.4  460.91  4679.6  460.75  4686.0  460.14  4714.8  459.25  4806.2  453.34
  4814.1  453.22  4836.5  451.39  4849.0  450.83  4900.5  447.50  4935.7  445.96
  4942.1  446.00  4950.1  444.86  4970.9  444.46  4978.9  443.70  4985.3  444.25
  5001.1  443.30  5001.3  442.80  5004.8  442.80  5005.1  443.30  5045.3  445.72
  5098.0  446.82  5108.5  447.90  5119.0  447.88  5161.2  449.56  5171.7  450.38
  5192.8  451.10  5213.9  452.73  5256.1  454.56  5266.6  455.51  5308.8  457.24
#Mann=5,-1,0
  4672.4    0.05       0  4806.2    0.07       0  4849.0     0.1       0
  5001.1    0.05       0  5005.1     0.1       0
Bank Sta=5001.1,5005.1
Exp/Cntr=0.3,0.1

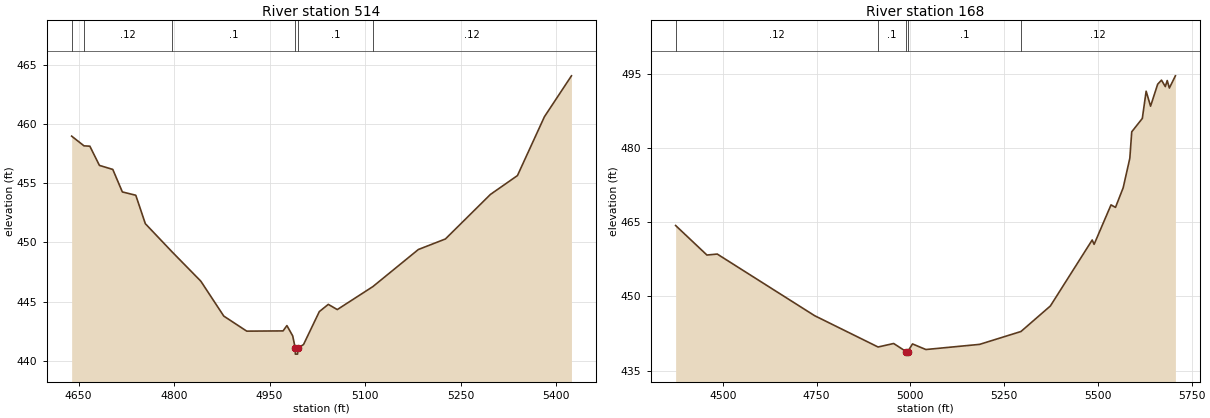
Type RM Length L Ch R = 1,514,346,346,346
BEGIN DESCRIPTION:
StreamM056 1.0
END DESCRIPTION:
XS GIS Cut Line= 3
      2502674.98     13857025.01      2502975.00     13856825.00
      2503274.97     13856525.03
#Sta/Elev= 30
  4639.2  458.97  4658.6  458.15  4667.8  458.12  4682.8  456.50  4703.8  456.16
  4718.8  454.26  4739.9  453.98  4754.9  451.58  4797.1  449.19  4842.0  446.73
  4878.1  443.78  4914.1  442.51  4971.2  442.53  4977.2  442.98  4986.3  442.11
  4990.3  441.07  4990.5  440.57  4994.0  440.57  4994.3  441.07  5003.3  441.38
  5028.1  444.16  5042.2  444.77  5056.3  444.33  5112.2  446.27  5183.6  449.40
  5226.1  450.29  5296.8  454.05  5339.2  455.64  5381.6  460.61  5424.0  464.06
#Mann=6,-1,0
  4639.2    0.07       0  4658.6    0.12       0  4797.1     0.1       0
  4990.3    0.05       0  4994.3     0.1       0  5112.2    0.12       0
Bank Sta=4990.3,4994.3
Exp/Cntr=0.3,0.1

Type RM Length L Ch R = 1,168,0,0,0
BEGIN DESCRIPTION:
H21396
END DESCRIPTION:
XS GIS Cut Line= 4
      2502728.85     13857361.65      2503187.16     13857106.46
      2503405.91     13856804.38      2503494.17     13856378.66
#Sta/Elev= 30
  4374.4  464.30  4457.9  458.33  4485.4  458.53  4744.9  446.08  4914.1  439.75
  4955.6  440.46  4989.2  438.81  4989.5  438.31  4993.2  438.81  5005.9  440.37
  5041.5  439.24  5184.7  440.28  5295.0  442.88  5373.4  448.04  5484.9  461.37
  5490.0  460.49  5535.1  468.47  5547.0  467.96  5567.5  471.93  5585.2  477.89
  5590.3  483.23  5618.5  485.93  5628.7  491.43  5640.5  488.41  5659.4  492.84
  5669.6  493.67  5679.8  492.37  5684.9  493.59  5690.6  492.07  5706.7  494.54
#Mann=5,-1,0
  4374.4    0.12       0  4914.1     0.1       0  4989.2    0.05       0
  4993.2     0.1       0  5295.0    0.12       0
Bank Sta=4989.2,4993.2
Exp/Cntr=0.3,0.1

Chan Stop Cuts=-1