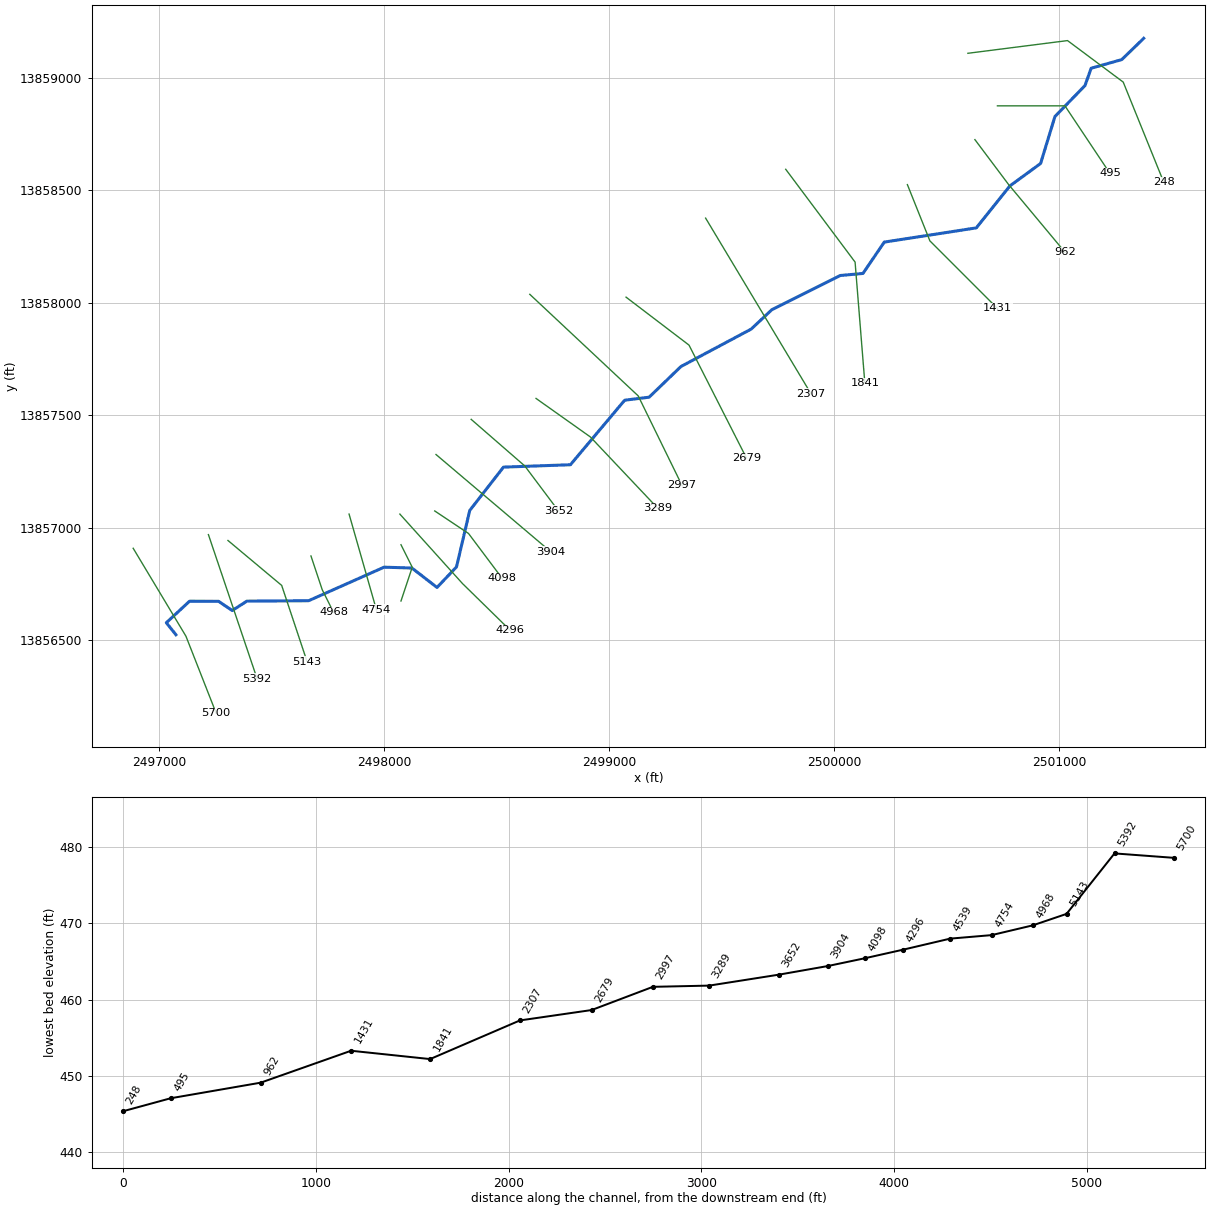
--- StreamM057.prj (project) ---

Proj Title=StreamM057 Base Level Engineering
Current Plan=p01
Default Exp/Contr=0.3,0.1
English Units
Geom File=g01
Flow File=f01
Plan File=p01
BEGIN DESCRIPTION:
StreamM057
END DESCRIPTION:

--- StreamM057.p01 (plan) ---

Plan Title=Multiple Run
Short Identifier=Multiple
Geom File=g01
Flow File=f01
Subcritical Flow
K Sum by GR= 0
Std Step Tol= 0.01
Critical Tol= 0.01
Num of Std Step Trials= 20
Max Error Tol= 0.3
Flow Tol Ratio= 0.001
Split Flow NTrial= 30
Split Flow Tol= 0.02
Split Flow Ratio= 0.02
Log Output Level= 0
Friction Slope Method= 1
Unsteady Friction Slope Method= 2
Unsteady Bridges Friction Slope Method= 1
Parabolic Critical Depth
Global Vel Dist=  1 , 1 , 1
Global Log Level= 0
CheckData=True
Encroach Param= -1, 0, 0, 0
BEGIN DESCRIPTION:
Multiple Run
END DESCRIPTION:

--- StreamM057.f01 (steady flow) ---

Flow Title=Multiple
Number of Profiles=7
Profile Names=10-year,25-year,50-year,1pct_min,100-year,1pct_plu,500-year
River Rch & RM= StreamM057,Reach-1,5700
     217     324     414     258     514    1025     780
River Rch & RM= StreamM057,Reach-1,4296
     451     708     935     599    1196    2386    1933
River Rch & RM= StreamM057,Reach-1,2307
     519     820    1086     697    1392    2777    2260
Boundary for River Rch & Prof#=StreamM057,Reach-1,1
Up Type=0
Dn Type=3
Dn Slope=0.005
Boundary for River Rch & Prof#=StreamM057,Reach-1,2
Up Type=0
Dn Type=3
Dn Slope=0.005
Boundary for River Rch & Prof#=StreamM057,Reach-1,3
Up Type=0
Dn Type=3
Dn Slope=0.005
Boundary for River Rch & Prof#=StreamM057,Reach-1,4
Up Type=0
Dn Type=3
Dn Slope=0.005
Boundary for River Rch & Prof#=StreamM057,Reach-1,5
Up Type=0
Dn Type=3
Dn Slope=0.005
Boundary for River Rch & Prof#=StreamM057,Reach-1,6
Up Type=0
Dn Type=3
Dn Slope=0.005
Boundary for River Rch & Prof#=StreamM057,Reach-1,7
Up Type=0
Dn Type=3
Dn Slope=0.005

--- StreamM057.g01 (geometry) ---

Geom Title=Existing Conditions

River Reach=StreamM057,Reach-1
Reach XY= 30
      2497075.00     13856525.00      2497032.24     13856578.35
      2497135.43     13856673.97      2497264.56     13856673.63
      2497325.00     13856632.56      2497390.16     13856674.34
      2497664.50     13856676.20      2497999.93     13856825.23
      2498123.53     13856821.46      2498235.00     13856735.11
      2498321.61     13856826.40      2498380.52     13857077.43
      2498530.44     13857269.82      2498827.70     13857280.36
      2499068.83     13857567.14      2499177.43     13857580.52
      2499318.95     13857716.84      2499631.05     13857883.16
      2499722.71     13857969.15      2500026.59     13858121.17
      2500127.67     13858130.42      2500222.30     13858269.64
      2500631.19     13858332.82      2500780.62     13858519.38
      2500916.87     13858618.93      2500980.52     13858827.43
      2501114.21     13858965.34      2501141.46     13859042.13
      2501277.45     13859080.46      2501375.00     13859175.00

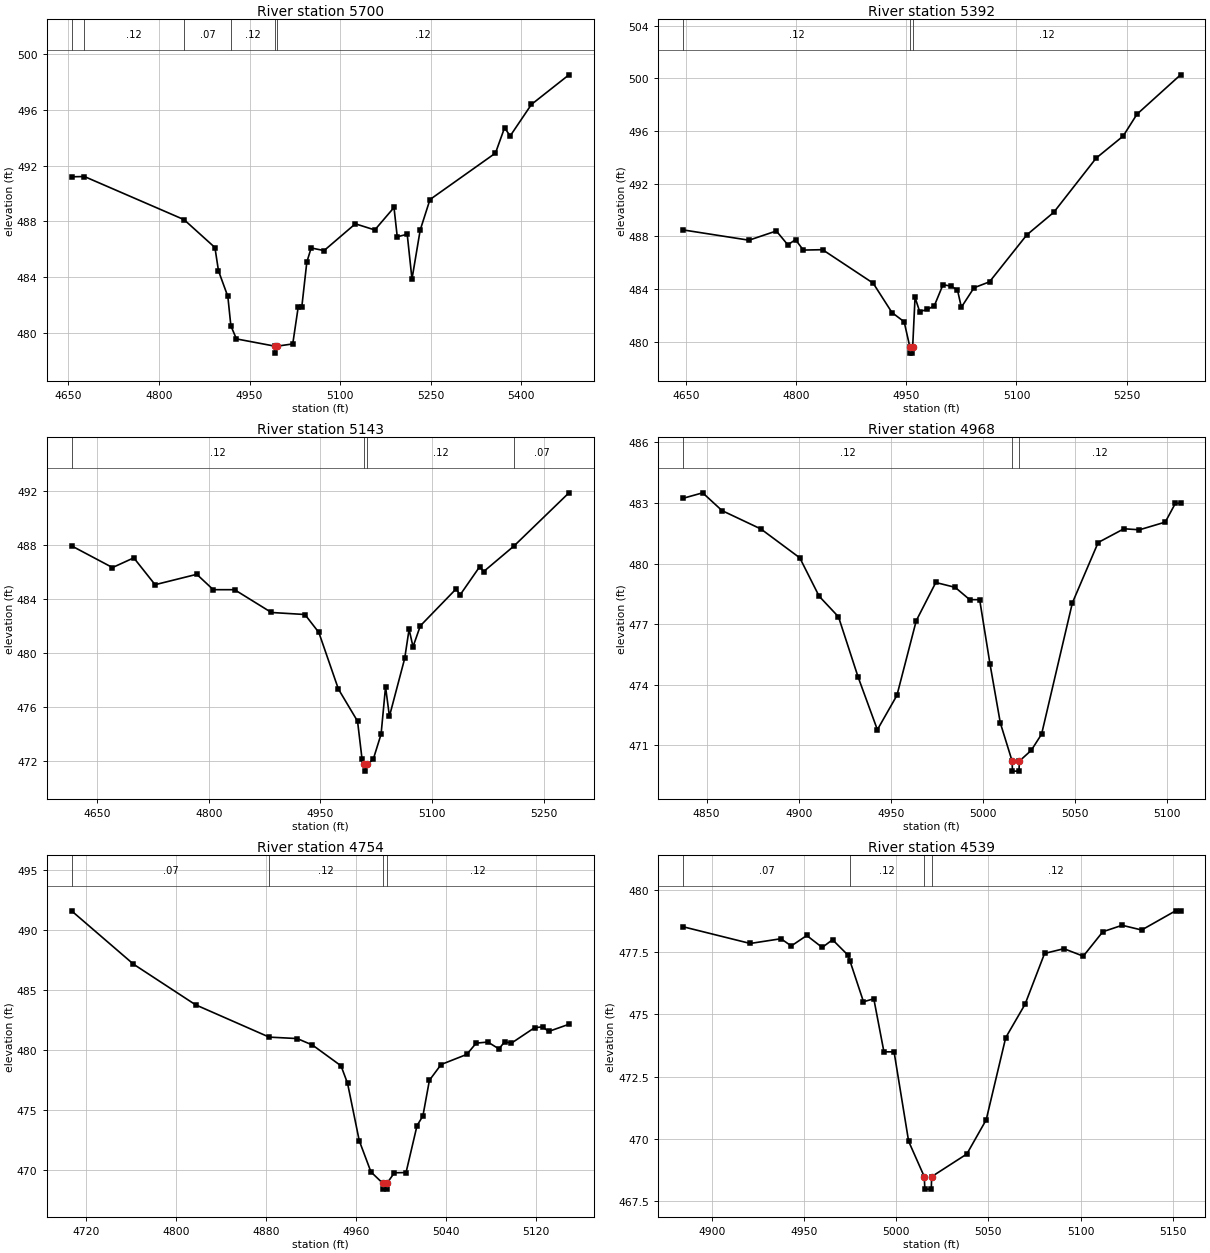
Type RM Length L Ch R = 1,5700,308,308,308
BEGIN DESCRIPTION:
H21408
END DESCRIPTION:
XS GIS Cut Line= 3
      2496885.10     13856909.18      2497119.50     13856518.51
      2497254.04     13856175.65
#Sta/Elev= 30
  4655.1  491.20  4676.4  491.22  4841.4  488.13  4892.6  486.13  4898.5  484.46
  4914.0  482.62  4919.0  480.52  4928.2  479.58  4991.7  479.06  4991.9  478.56
  4995.7  479.06  5021.5  479.22  5030.6  481.88  5036.5  481.87  5044.8  485.08
  5052.0  486.10  5073.4  485.91  5125.2  487.83  5157.4  487.39  5189.2  489.00
  5194.6  486.90  5211.1  487.08  5219.0  483.87  5232.6  487.38  5248.8  489.57
  5357.3  492.90  5372.3  494.71  5381.7  494.13  5416.9  496.39  5479.0  498.51
#Mann=6,-1,0
  4655.1    0.07       0  4676.4    0.12       0  4841.4    0.07       0
  4919.0    0.12       0  4991.7    0.05       0  4995.7    0.12       0
Bank Sta=4991.7,4995.7
Exp/Cntr=0.3,0.1

Type RM Length L Ch R = 1,5392,249,249,249
BEGIN DESCRIPTION:
H21407
END DESCRIPTION:
XS GIS Cut Line= 2
      2497219.33     13856969.89      2497435.92     13856328.79
#Sta/Elev= 30
  4646.5  488.49  4736.1  487.71  4773.3  488.41  4788.9  487.36  4799.4  487.75
  4810.0  486.96  4836.2  486.99  4905.0  484.45  4930.6  482.22  4947.2  481.52
  4954.8  479.64  4955.0  479.14  4958.5  479.14  4958.8  479.64  4962.0  483.37
  4968.3  482.29  4978.9  482.46  4988.2  482.73  5000.0  484.33  5010.5  484.23
  5019.7  483.94  5025.0  482.62  5042.2  484.10  5063.3  484.55  5114.0  488.11
  5150.8  489.83  5208.4  493.94  5245.1  495.61  5263.9  497.27  5323.2  500.26
#Mann=3,-1,0
  4646.5    0.12       0  4954.8    0.05       0  4958.8    0.12       0
Bank Sta=4954.8,4958.8
Exp/Cntr=0.3,0.1

Type RM Length L Ch R = 1,5143,175,175,175
BEGIN DESCRIPTION:
H21406
END DESCRIPTION:
XS GIS Cut Line= 3
      2497306.15     13856943.84      2497544.85     13856744.20
      2497657.68     13856405.69
#Sta/Elev= 30
  4615.8  487.92  4670.8  486.31  4699.4  487.03  4728.0  485.04  4784.0  485.81
  4806.1  484.67  4834.7  484.67  4884.2  482.98  4929.2  482.83  4947.9  481.50
  4974.2  477.30  4999.9  474.92  5005.9  472.13  5009.1  471.72  5009.4  471.22
  5013.1  471.72  5021.0  472.10  5031.5  473.96  5037.5  477.47  5042.7  475.28
  5063.2  479.57  5069.1  481.73  5074.4  480.44  5084.2  481.99  5132.3  484.73
  5137.6  484.28  5164.0  486.38  5169.2  486.01  5210.0  487.91  5283.8  491.85
#Mann=4,-1,0
  4615.8    0.12       0  5009.1    0.05       0  5013.1    0.12       0
  5210.0    0.07       0
Bank Sta=5009.1,5013.1
Exp/Cntr=0.3,0.1

Type RM Length L Ch R = 1,4968,214,214,214
BEGIN DESCRIPTION:
StreamM057 11.0
END DESCRIPTION:
XS GIS Cut Line= 3
      2497674.99     13856875.02      2497725.00     13856725.00
      2497774.98     13856625.03
#Sta/Elev= 30
  4837.3  483.23  4847.9  483.50  4858.4  482.62  4879.5  481.71  4900.6  480.28
  4911.1  478.38  4921.6  477.36  4932.2  474.39  4942.7  471.77  4953.3  473.47
  4963.8  477.17  4974.4  479.06  4984.9  478.82  4992.8  478.21  4998.2  478.21
  5003.8  475.03  5009.4  472.11  5015.8  470.22  5016.0  469.72  5019.5  469.72
  5019.8  470.22  5026.2  470.75  5031.8  471.55  5048.5  478.05  5062.5  481.04
  5076.5  481.72  5084.9  481.67  5098.9  482.05  5104.4  482.98  5107.2  482.98
#Mann=3,-1,0
  4837.3    0.12       0  5015.8    0.05       0  5019.8    0.12       0
Bank Sta=5015.8,5019.8
Exp/Cntr=0.3,0.1

Type RM Length L Ch R = 1,4754,215,215,215
BEGIN DESCRIPTION:
H21405
END DESCRIPTION:
XS GIS Cut Line= 2
      2497844.32     13857061.07      2497965.86     13856635.69
#Sta/Elev= 30
  4707.2  491.60  4762.3  487.16  4817.5  483.78  4883.0  481.09  4907.9  480.97
  4921.5  480.43  4946.9  478.70  4952.7  477.24  4963.1  472.47  4973.5  469.87
  4983.9  468.94  4984.1  468.44  4987.6  468.44  4987.9  468.94  4994.3  469.80
  5004.7  469.82  5014.5  473.73  5019.7  474.53  5025.5  477.50  5035.9  478.81
  5058.7  479.65  5067.1  480.59  5077.5  480.68  5087.3  480.11  5092.5  480.71
  5098.3  480.58  5119.1  481.88  5126.3  481.94  5131.5  481.56  5149.6  482.16
#Mann=4,-1,0
  4707.2    0.07       0  4883.0    0.12       0  4983.9    0.05       0
  4987.9    0.12       0
Bank Sta=4983.9,4987.9
Exp/Cntr=0.3,0.1

Type RM Length L Ch R = 1,4539,243,243,243
BEGIN DESCRIPTION:
StreamM057 10.0
END DESCRIPTION:
XS GIS Cut Line= 3
      2498074.99     13856925.03      2498125.00     13856825.00
      2498074.98     13856674.95
#Sta/Elev= 30
  4884.3  478.51  4920.7  477.84  4937.4  478.03  4943.0  477.74  4951.4  478.16
  4959.8  477.68  4965.4  477.99  4973.8  477.37  4974.9  477.13  4982.2  475.50
  4987.8  475.62  4993.3  473.49  4998.8  473.49  5006.7  469.90  5015.2  468.48
  5015.5  467.98  5019.0  467.98  5019.2  468.48  5038.3  469.39  5048.8  470.76
  5059.4  474.06  5069.9  475.40  5080.5  477.44  5091.0  477.63  5101.5  477.33
  5112.1  478.31  5122.6  478.57  5133.2  478.38  5151.6  479.15  5154.3  479.15
#Mann=4,-1,0
  4884.3    0.07       0  4974.9    0.12       0  5015.2    0.05       0
  5019.2    0.12       0
Bank Sta=5015.2,5019.2
Exp/Cntr=0.3,0.1

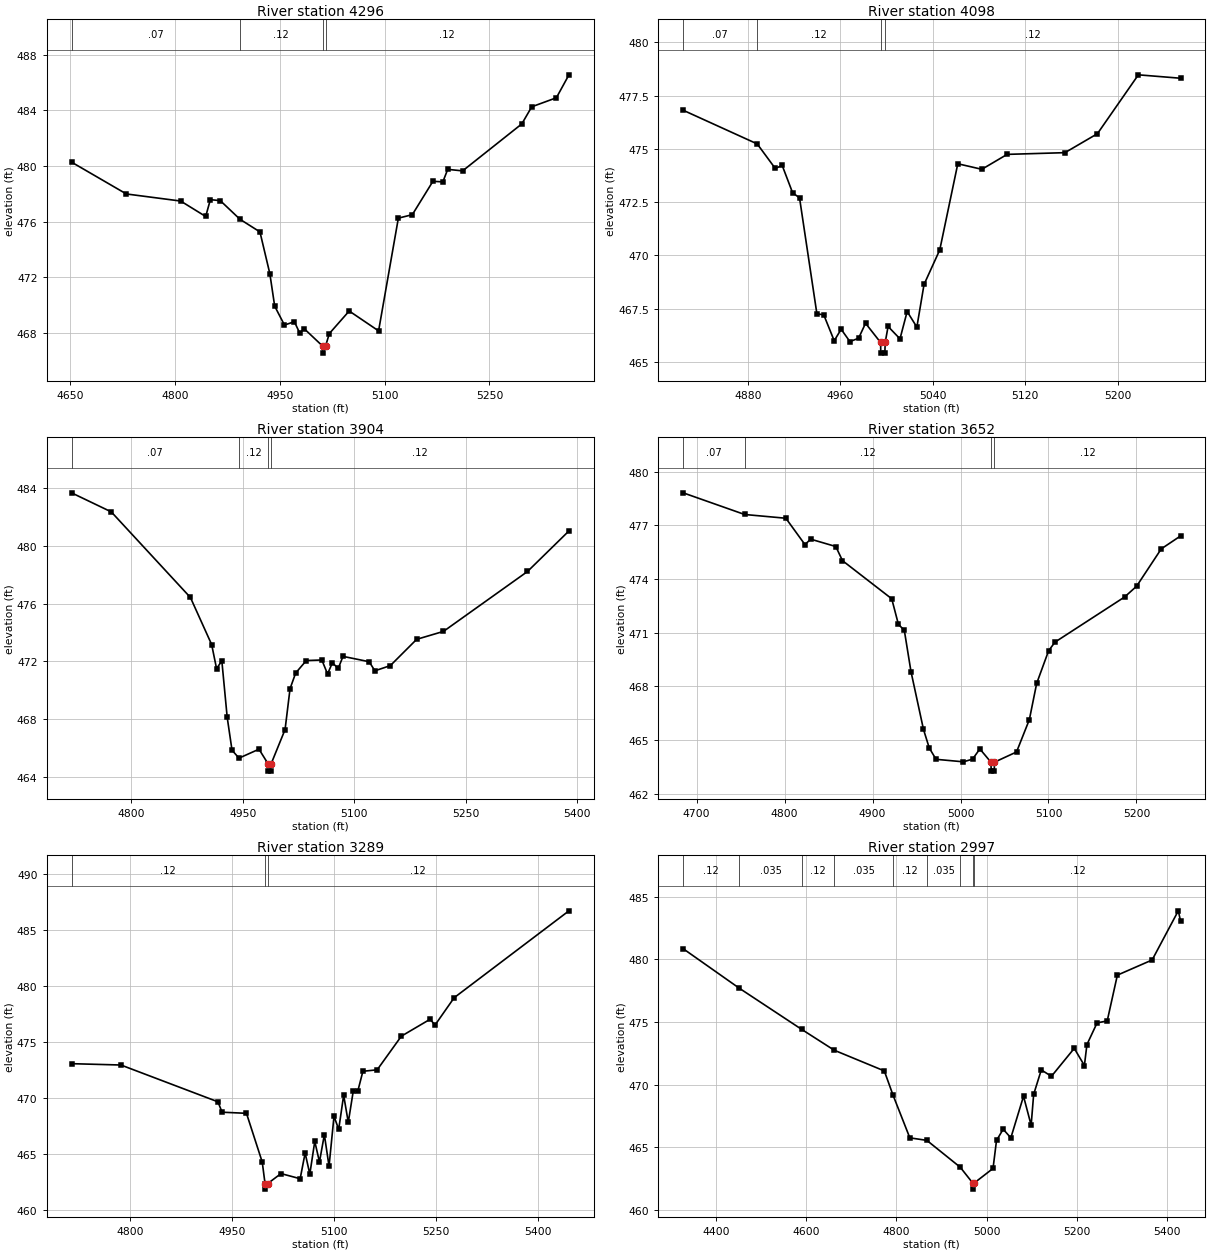
Type RM Length L Ch R = 1,4296,198,198,198
BEGIN DESCRIPTION:
H21404
END DESCRIPTION:
XS GIS Cut Line= 3
      2498069.99     13857061.08      2498347.80     13856752.88
      2498560.23     13856544.79
#Sta/Elev= 30
  4651.5  480.28  4730.0  477.99  4807.8  477.48  4843.6  476.37  4850.3  477.58
  4864.5  477.51  4892.7  476.17  4921.3  475.26  4935.5  472.25  4942.4  469.92
  4956.4  468.56  4970.6  468.80  4978.1  468.00  4984.8  468.29  5011.2  467.04
  5011.5  466.54  5015.2  467.04  5020.7  467.95  5049.1  469.57  5091.2  468.14
  5119.5  476.25  5139.5  476.50  5169.0  478.90  5183.2  478.86  5190.2  479.76
  5211.5  479.65  5296.3  483.03  5310.5  484.26  5345.8  484.91  5363.8  486.56
#Mann=4,-1,0
  4651.5    0.07       0  4892.7    0.12       0  5011.2    0.05       0
  5015.2    0.12       0
Bank Sta=5011.2,5015.2
Exp/Cntr=0.3,0.1

Type RM Length L Ch R = 1,4098,194,194,194
BEGIN DESCRIPTION:
StreamM057 9.0
END DESCRIPTION:
XS GIS Cut Line= 3
      2498224.98     13857075.02      2498375.00     13856975.00
      2498525.00     13856775.01
#Sta/Elev= 30
  4824.0  476.81  4888.1  475.23  4903.7  474.08  4909.7  474.22  4918.7  472.94
  4924.7  472.70  4939.7  467.27  4945.7  467.21  4954.7  466.00  4960.7  466.54
  4968.3  465.96  4975.8  466.12  4981.8  466.82  4994.8  465.92  4995.0  465.42
  4998.5  465.42  4998.8  465.92  5001.3  466.67  5011.6  466.09  5017.8  467.37
  5026.2  466.64  5032.4  468.64  5046.0  470.26  5061.6  474.30  5082.4  474.04
  5104.3  474.74  5154.3  474.82  5182.4  475.71  5217.8  478.47  5254.3  478.31
#Mann=4,-1,0
  4824.0    0.07       0  4888.1    0.12       0  4994.8    0.05       0
  4998.8    0.12       0
Bank Sta=4994.8,4998.8
Exp/Cntr=0.3,0.1

Type RM Length L Ch R = 1,3904,252,252,252
BEGIN DESCRIPTION:
H21409
END DESCRIPTION:
XS GIS Cut Line= 2
      2498230.64     13857325.78      2498741.40     13856892.93
#Sta/Elev= 30
  4719.7  483.67  4773.2  482.35  4879.7  476.42  4908.3  473.16  4914.9  471.49
  4922.0  472.03  4929.2  468.12  4935.7  465.84  4945.1  465.29  4972.0  465.91
  4984.3  464.89  4984.6  464.39  4988.1  464.39  4988.3  464.89  5007.1  467.27
  5013.8  470.10  5021.4  471.19  5035.7  472.05  5056.6  472.09  5064.3  471.12
  5070.8  471.90  5078.6  471.50  5085.1  472.34  5120.3  471.97  5128.0  471.34
  5148.8  471.70  5184.2  473.52  5220.3  474.07  5333.4  478.22  5389.2  481.03
#Mann=4,-1,0
  4719.7    0.07       0  4945.1    0.12       0  4984.3    0.05       0
  4988.3    0.12       0
Bank Sta=4984.3,4988.3
Exp/Cntr=0.3,0.1

Type RM Length L Ch R = 1,3652,363,363,363
BEGIN DESCRIPTION:
StreamM057 8.0
END DESCRIPTION:
XS GIS Cut Line= 3
      2498386.86     13857482.05      2498625.00     13857275.00
      2498775.02     13857074.97
#Sta/Elev= 30
  4684.6  478.82  4754.5  477.61  4801.4  477.40  4823.1  475.93  4829.7  476.23
  4858.2  475.82  4865.8  475.03  4921.8  472.90  4929.4  471.47  4936.1  471.14
  4943.7  468.83  4957.9  465.60  4964.5  464.56  4972.2  463.93  5003.3  463.79
  5013.7  463.94  5022.0  464.51  5034.6  463.77  5034.9  463.27  5038.4  463.27
  5038.6  463.77  5063.7  464.34  5078.3  466.15  5086.6  468.17  5100.2  470.00
  5107.5  470.48  5186.6  473.00  5200.2  473.60  5228.3  475.69  5250.2  476.41
#Mann=4,-1,0
  4684.6    0.07       0  4754.5    0.12       0  5034.6    0.05       0
  5038.6    0.12       0
Bank Sta=5034.6,5038.6
Exp/Cntr=0.3,0.1

Type RM Length L Ch R = 1,3289,292,292,292
BEGIN DESCRIPTION:
StreamM057 7.0
END DESCRIPTION:
XS GIS Cut Line= 3
      2498674.96     13857575.03      2498916.37     13857403.92
      2499215.87     13857087.07
#Sta/Elev= 30
  4713.4  473.05  4786.1  472.93  4928.8  469.64  4934.9  468.71  4970.8  468.61
  4994.0  464.25  4998.1  462.33  4998.4  461.83  5002.1  462.33  5021.6  463.22
  5049.8  462.76  5057.1  465.06  5064.0  463.17  5071.3  466.10  5078.2  464.26
  5085.4  466.70  5092.3  463.88  5099.6  468.35  5106.5  467.17  5113.8  470.23
  5120.6  467.80  5127.9  470.59  5134.8  470.64  5142.1  472.37  5163.1  472.50
  5198.7  475.51  5241.2  477.03  5248.1  476.49  5276.4  478.95  5445.3  486.72
#Mann=3,-1,0
  4713.4    0.12       0  4998.1    0.05       0  5002.1    0.12       0
Bank Sta=4998.1,5002.1
Exp/Cntr=0.3,0.1

Type RM Length L Ch R = 1,2997,318,318,318
BEGIN DESCRIPTION:
H21410
END DESCRIPTION:
XS GIS Cut Line= 3
      2498647.29     13858037.60      2499129.05     13857586.22
      2499323.62     13857188.43
#Sta/Elev= 30
  4327.2  480.85  4451.6  477.70  4590.2  474.41  4662.3  472.75  4773.3  471.10
  4792.4  469.19  4829.9  465.76  4867.6  465.56  4941.6  463.42  4969.1  462.17
  4969.4  461.67  4973.1  462.17  5014.4  463.32  5022.1  465.55  5036.9  466.45
  5053.9  465.76  5082.0  469.08  5098.9  466.77  5104.5  469.23  5121.4  471.18
  5143.9  470.67  5194.5  472.90  5217.0  471.53  5222.6  473.20  5245.1  474.93
  5267.6  475.09  5290.1  478.74  5367.2  479.95  5425.2  483.87  5430.2  483.06
#Mann=9,-1,0
  4327.2    0.12       0  4451.6   0.035       0  4590.2    0.12       0
  4662.3   0.035       0  4792.4    0.12       0  4867.6   0.035       0
  4941.6    0.12       0  4969.1    0.05       0  4973.1    0.12       0
Bank Sta=4969.1,4973.1
Exp/Cntr=0.3,0.1

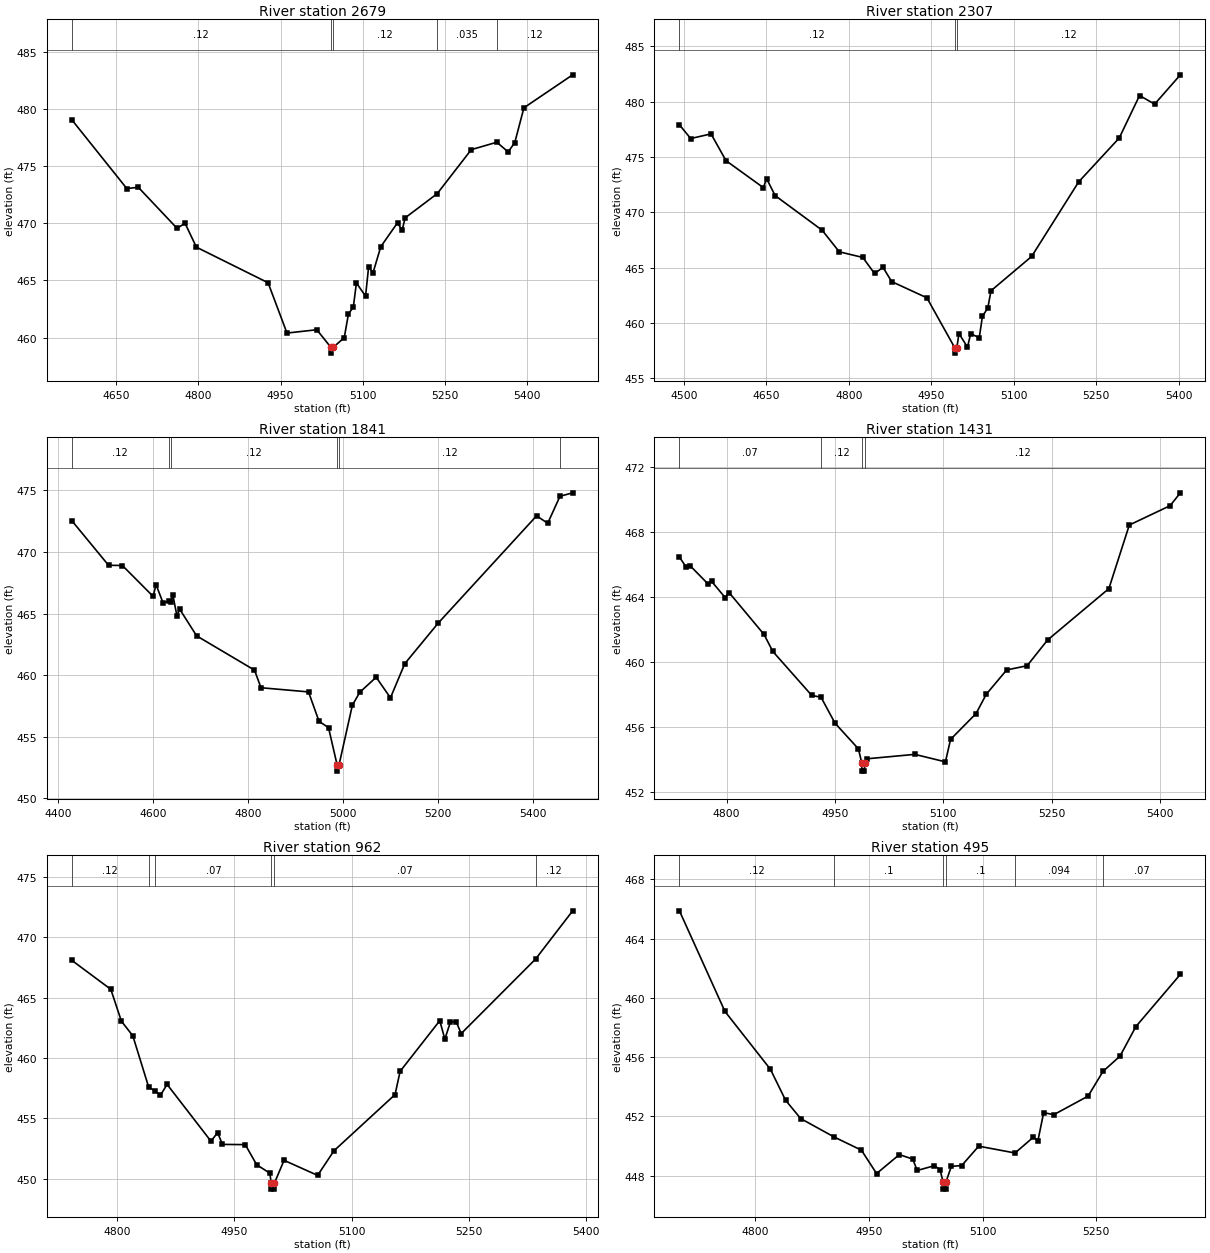
Type RM Length L Ch R = 1,2679,372,372,372
BEGIN DESCRIPTION:
StreamM057 6.0
END DESCRIPTION:
XS GIS Cut Line= 3
      2499074.97     13858025.02      2499354.74     13857811.91
      2499610.03     13857310.00
#Sta/Elev= 30
  4568.7  479.10  4669.3  473.06  4690.3  473.17  4761.1  469.57  4775.6  470.02
  4796.4  467.92  4927.3  464.80  4961.8  460.39  5016.3  460.68  5042.1  459.13
  5042.4  458.63  5046.1  459.13  5066.4  459.99  5074.0  462.05  5083.0  462.68
  5088.6  464.78  5105.3  463.63  5110.9  466.20  5118.9  465.67  5133.1  467.96
  5163.8  470.07  5172.0  469.39  5177.6  470.49  5236.1  472.61  5298.4  476.47
  5345.0  477.12  5365.7  476.27  5377.8  477.09  5394.5  480.14  5483.5  483.03
#Mann=5,-1,0
  4568.7    0.12       0  5042.1    0.05       0  5046.1    0.12       0
  5236.1   0.035       0  5345.0    0.12       0
Bank Sta=5042.1,5046.1
Exp/Cntr=0.3,0.1

Type RM Length L Ch R = 1,2307,466,466,466
BEGIN DESCRIPTION:
H21403
END DESCRIPTION:
XS GIS Cut Line= 2
      2499428.54     13858376.12      2499897.30     13857594.86
#Sta/Elev= 30
  4491.8  477.91  4512.3  476.67  4549.3  477.09  4576.5  474.67  4644.5  472.23
  4650.3  473.05  4665.9  471.51  4751.4  468.38  4782.5  466.43  4825.3  465.92
  4846.6  464.47  4862.2  465.02  4877.7  463.74  4941.9  462.27  4992.4  457.77
  4992.6  457.27  4996.4  457.77  5000.2  459.04  5015.7  457.81  5021.6  459.03
  5037.1  458.66  5042.9  460.59  5052.7  461.36  5058.5  462.91  5132.4  466.01
  5217.9  472.75  5291.7  476.72  5328.7  480.56  5356.1  479.78  5402.9  482.43
#Mann=3,-1,0
  4491.8    0.12       0  4992.4    0.05       0  4996.4    0.12       0
Bank Sta=4992.4,4996.4
Exp/Cntr=0.3,0.1

Type RM Length L Ch R = 1,1841,410,410,410
BEGIN DESCRIPTION:
H21402
END DESCRIPTION:
XS GIS Cut Line= 3
      2499784.41     13858593.19      2500092.59     13858180.83
      2500135.99     13857642.68
#Sta/Elev= 30
  4429.0  472.55  4506.5  468.92  4535.7  468.90  4600.3  466.40  4606.6  467.34
  4621.2  465.88  4633.6  466.00  4637.1  465.90  4642.0  466.49  4650.4  464.84
  4656.6  465.34  4692.0  463.19  4813.8  460.41  4827.5  458.98  4927.6  458.64
  4949.7  456.25  4969.7  455.74  4987.8  452.71  4988.0  452.21  4991.8  452.71
  5019.9  457.56  5035.5  458.61  5070.0  459.83  5100.1  458.16  5130.2  460.93
  5200.5  464.22  5407.7  472.93  5431.2  472.33  5457.0  474.52  5483.7  474.80
#Mann=6,-1,0
  4429.0    0.12       0  4633.6    0.07       0  4637.1    0.12       0
  4987.8    0.05       0  4991.8    0.12       0  5457.0    0.07       0
Bank Sta=4987.8,4991.8
Exp/Cntr=0.3,0.1

Type RM Length L Ch R = 1,1431,469,469,469
BEGIN DESCRIPTION:
StreamM057 3.0
END DESCRIPTION:
XS GIS Cut Line= 3
      2500324.99     13858525.04      2500425.00     13858275.00
      2500725.03     13857974.97
#Sta/Elev= 30
  4734.8  466.46  4744.3  465.83  4749.6  465.93  4773.9  464.83  4779.3  464.97
  4798.1  463.97  4803.5  464.28  4852.0  461.70  4864.1  460.66  4917.9  457.96
  4930.9  457.84  4950.2  456.25  4982.6  454.67  4987.3  453.80  4987.5  453.30
  4991.0  453.30  4991.3  453.80  4994.7  454.06  5060.7  454.33  5103.1  453.87
  5110.2  455.25  5145.5  456.84  5159.7  458.03  5187.9  459.52  5216.2  459.78
  5244.5  461.36  5329.4  464.52  5357.7  468.43  5414.2  469.62  5428.4  470.41
#Mann=4,-1,0
  4734.8    0.07       0  4930.9    0.12       0  4987.3    0.05       0
  4991.3    0.12       0
Bank Sta=4987.3,4991.3
Exp/Cntr=0.3,0.1

Type RM Length L Ch R = 1,962,467,467,467
BEGIN DESCRIPTION:
StreamM057 2.0
END DESCRIPTION:
XS GIS Cut Line= 3
      2500625.00     13858725.00      2500775.00     13858525.00
      2501024.99     13858225.01
#Sta/Elev= 30
  4741.9  468.10  4791.9  465.69  4805.4  463.05  4820.0  461.84  4840.4  457.56
  4848.8  457.26  4855.4  456.90  4863.8  457.81  4920.0  453.09  4928.4  453.81
  4934.6  452.83  4963.8  452.81  4978.4  451.14  4995.1  450.45  4997.1  449.62
  4997.3  449.12  5000.8  449.12  5001.1  449.62  5013.4  451.51  5056.3  450.26
  5077.2  452.30  5155.3  456.96  5161.8  458.89  5212.5  463.09  5219.0  461.56
  5226.2  463.00  5233.4  463.01  5239.9  462.02  5335.0  468.20  5382.4  472.20
#Mann=6,-1,0
  4741.9    0.12       0  4840.4   0.094       0  4848.8    0.07       0
  4997.1    0.05       0  5001.1    0.07       0  5335.0    0.12       0
Bank Sta=4997.1,5001.1
Exp/Cntr=0.3,0.1

Type RM Length L Ch R = 1,495,247,247,247
BEGIN DESCRIPTION:
StreamM057 1.0
END DESCRIPTION:
XS GIS Cut Line= 3
      2500724.95     13858875.00      2501025.00     13858875.00
      2501225.00     13858575.00
#Sta/Elev= 30
  4700.3  465.87  4760.3  459.08  4820.3  455.17  4840.3  453.08  4860.3  451.84
  4904.7  450.59  4940.3  449.71  4960.3  448.13  4990.3  449.41  5007.9  449.11
  5013.9  448.34  5036.4  448.66  5043.9  448.40  5047.9  447.58  5048.2  447.08
  5051.7  447.08  5051.9  447.58  5058.9  448.62  5072.5  448.67  5095.0  449.98
  5142.9  449.52  5167.1  450.59  5173.1  450.36  5180.6  452.24  5194.1  452.11
  5239.2  453.36  5258.9  455.03  5281.3  456.06  5302.3  458.06  5360.9  461.58
#Mann=6,-1,0
  4700.3    0.12       0  4904.7     0.1       0  5047.9    0.05       0
  5051.9     0.1       0  5142.9   0.094       0  5258.9    0.07       0
Bank Sta=5047.9,5051.9
Exp/Cntr=0.3,0.1

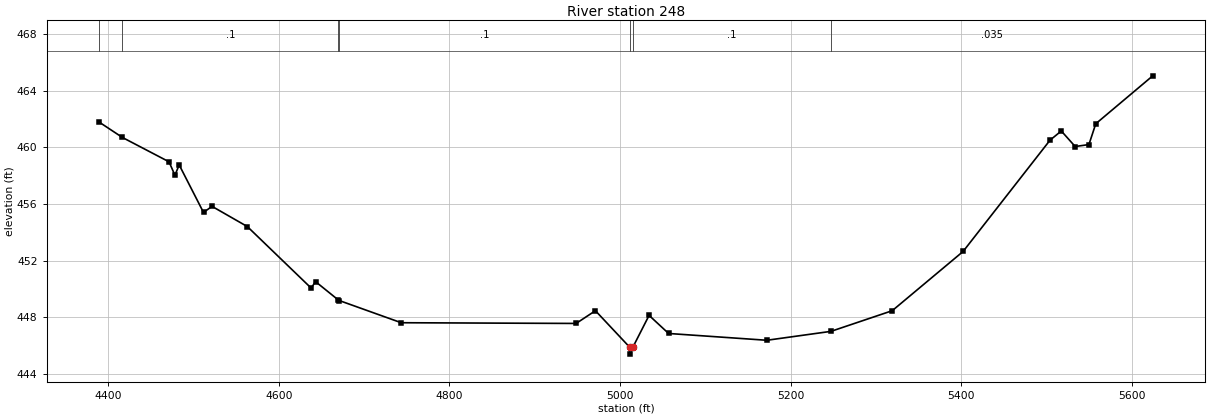
Type RM Length L Ch R = 1,248,0,0,0
BEGIN DESCRIPTION:
H21401
END DESCRIPTION:
XS GIS Cut Line= 4
      2500593.92     13859108.57      2501036.60     13859164.99
      2501284.00     13858980.53      2501464.11     13858535.67
#Sta/Elev= 30
  4389.7  461.78  4416.8  460.70  4471.4  458.98  4478.3  458.03  4483.3  458.76
  4511.8  455.40  4521.8  455.83  4563.2  454.40  4638.0  450.05  4643.1  450.51
  4670.0  449.20  4670.9  449.17  4743.6  447.60  4948.6  447.55  4971.2  448.45
  5011.2  445.88  5011.5  445.38  5015.2  445.88  5034.1  448.12  5057.0  446.84
  5172.1  446.36  5247.3  446.99  5319.1  448.45  5402.2  452.64  5504.1  460.51
  5517.3  461.16  5533.6  460.06  5549.7  460.20  5557.7  461.67  5624.5  465.06
#Mann=7,-1,0
  4389.7    0.12       0  4416.8     0.1       0  4670.0    0.12       0
  4670.9     0.1       0  5011.2    0.05       0  5015.2     0.1       0
  5247.3   0.035       0
Bank Sta=5011.2,5015.2
Exp/Cntr=0.3,0.1

Chan Stop Cuts=-1