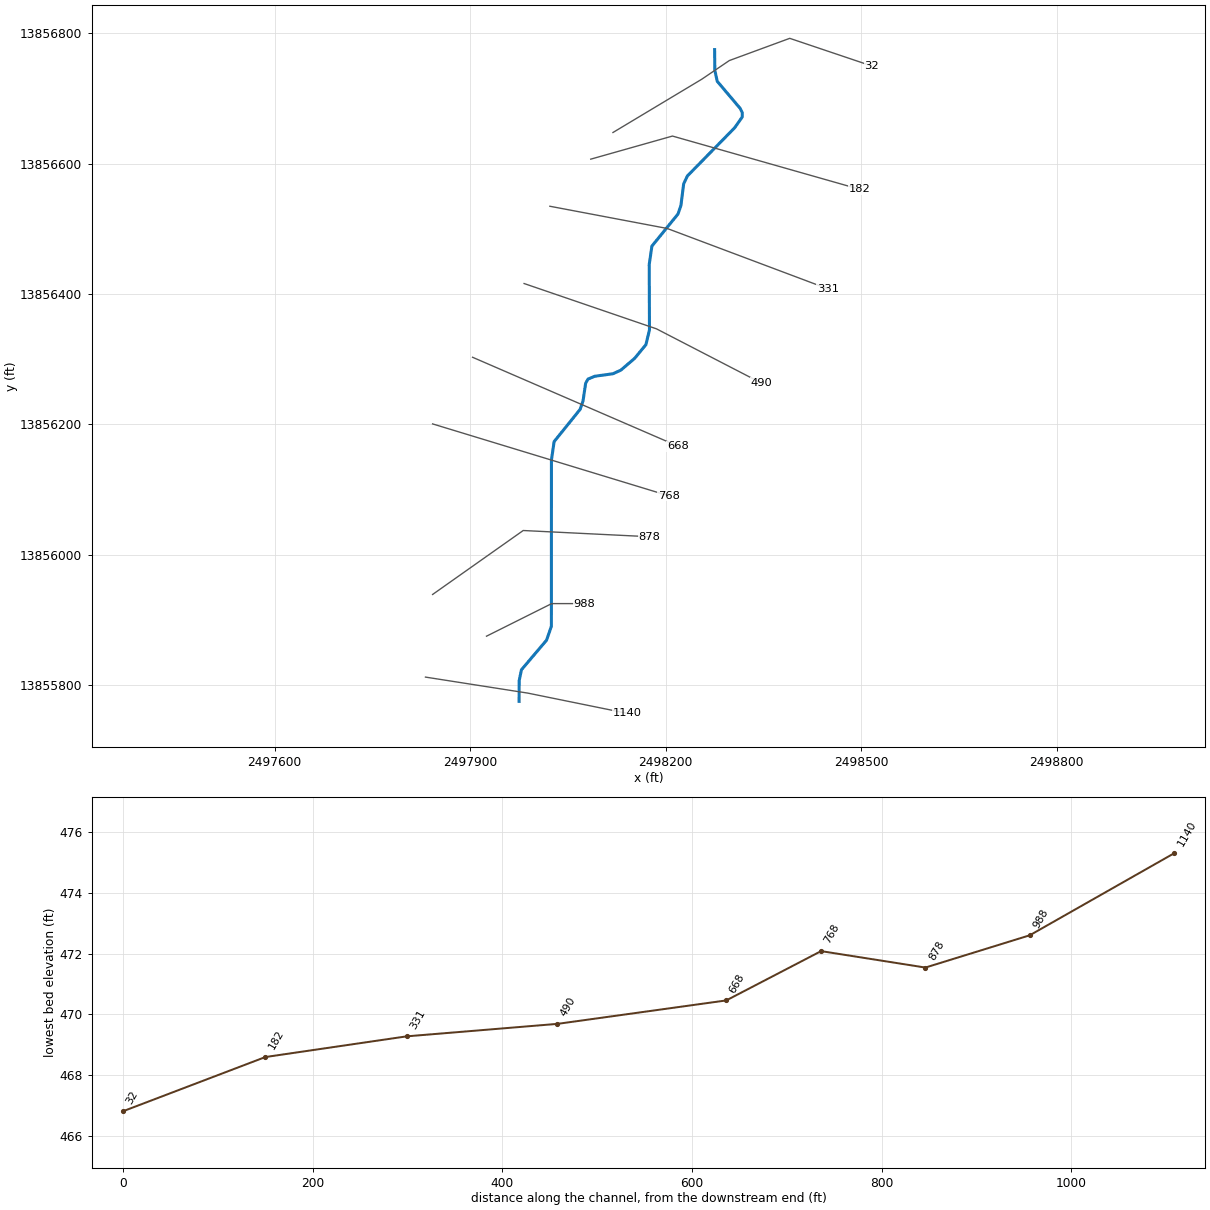
--- StreamM058.prj (project) ---

Proj Title=StreamM058 Base Level Engineering
Current Plan=p01
Default Exp/Contr=0.3,0.1
English Units
Geom File=g01
Flow File=f01
Plan File=p01
BEGIN DESCRIPTION:
StreamM058
END DESCRIPTION:

--- StreamM058.p01 (plan) ---

Plan Title=Multiple Run
Short Identifier=Multiple
Geom File=g01
Flow File=f01
Subcritical Flow
K Sum by GR= 0
Std Step Tol= 0.01
Critical Tol= 0.01
Num of Std Step Trials= 20
Max Error Tol= 0.3
Flow Tol Ratio= 0.001
Split Flow NTrial= 30
Split Flow Tol= 0.02
Split Flow Ratio= 0.02
Log Output Level= 0
Friction Slope Method= 1
Unsteady Friction Slope Method= 2
Unsteady Bridges Friction Slope Method= 1
Parabolic Critical Depth
Global Vel Dist=  1 , 1 , 1
Global Log Level= 0
CheckData=True
Encroach Param= -1, 0, 0, 0
BEGIN DESCRIPTION:
Multiple Run
END DESCRIPTION:

--- StreamM058.f01 (steady flow) ---

Flow Title=Multiple
Number of Profiles=7
Profile Names=10-year,25-year,50-year,1pct_min,100-year,1pct_plu,500-year
River Rch & RM= StreamM058,Reach-1,1140
     219     328     420     262     522    1042     796
Boundary for River Rch & Prof#=StreamM058,Reach-1,1
Up Type=0
Dn Type=3
Dn Slope=0.005
Boundary for River Rch & Prof#=StreamM058,Reach-1,2
Up Type=0
Dn Type=3
Dn Slope=0.005
Boundary for River Rch & Prof#=StreamM058,Reach-1,3
Up Type=0
Dn Type=3
Dn Slope=0.005
Boundary for River Rch & Prof#=StreamM058,Reach-1,4
Up Type=0
Dn Type=3
Dn Slope=0.005
Boundary for River Rch & Prof#=StreamM058,Reach-1,5
Up Type=0
Dn Type=3
Dn Slope=0.005
Boundary for River Rch & Prof#=StreamM058,Reach-1,6
Up Type=0
Dn Type=3
Dn Slope=0.005
Boundary for River Rch & Prof#=StreamM058,Reach-1,7
Up Type=0
Dn Type=3
Dn Slope=0.005

--- StreamM058.g01 (geometry) ---

Geom Title=Existing Conditions

River Reach=StreamM058,Reach-1
Reach XY= 30
      2497975.00     13855775.00      2497975.12     13855806.80
      2497978.65     13855823.49      2498017.11     13855868.84
      2498024.55     13855890.19      2498024.63     13856145.16
      2498028.74     13856173.48      2498068.72     13856223.16
      2498073.13     13856236.09      2498077.09     13856262.98
      2498080.62     13856269.38      2498091.08     13856273.83
      2498118.77     13856277.61      2498131.08     13856283.15
      2498152.18     13856301.15      2498169.60     13856322.32
      2498175.05     13856344.89      2498174.67     13856445.14
      2498178.76     13856473.44      2498218.86     13856522.83
      2498223.28     13856535.71      2498227.51     13856568.97
      2498233.18     13856581.06      2498305.69     13856654.99
      2498317.40     13856671.62      2498317.45     13856678.26
      2498314.11     13856684.90      2498279.02     13856726.36
      2498275.32     13856743.12      2498275.00     13856775.00

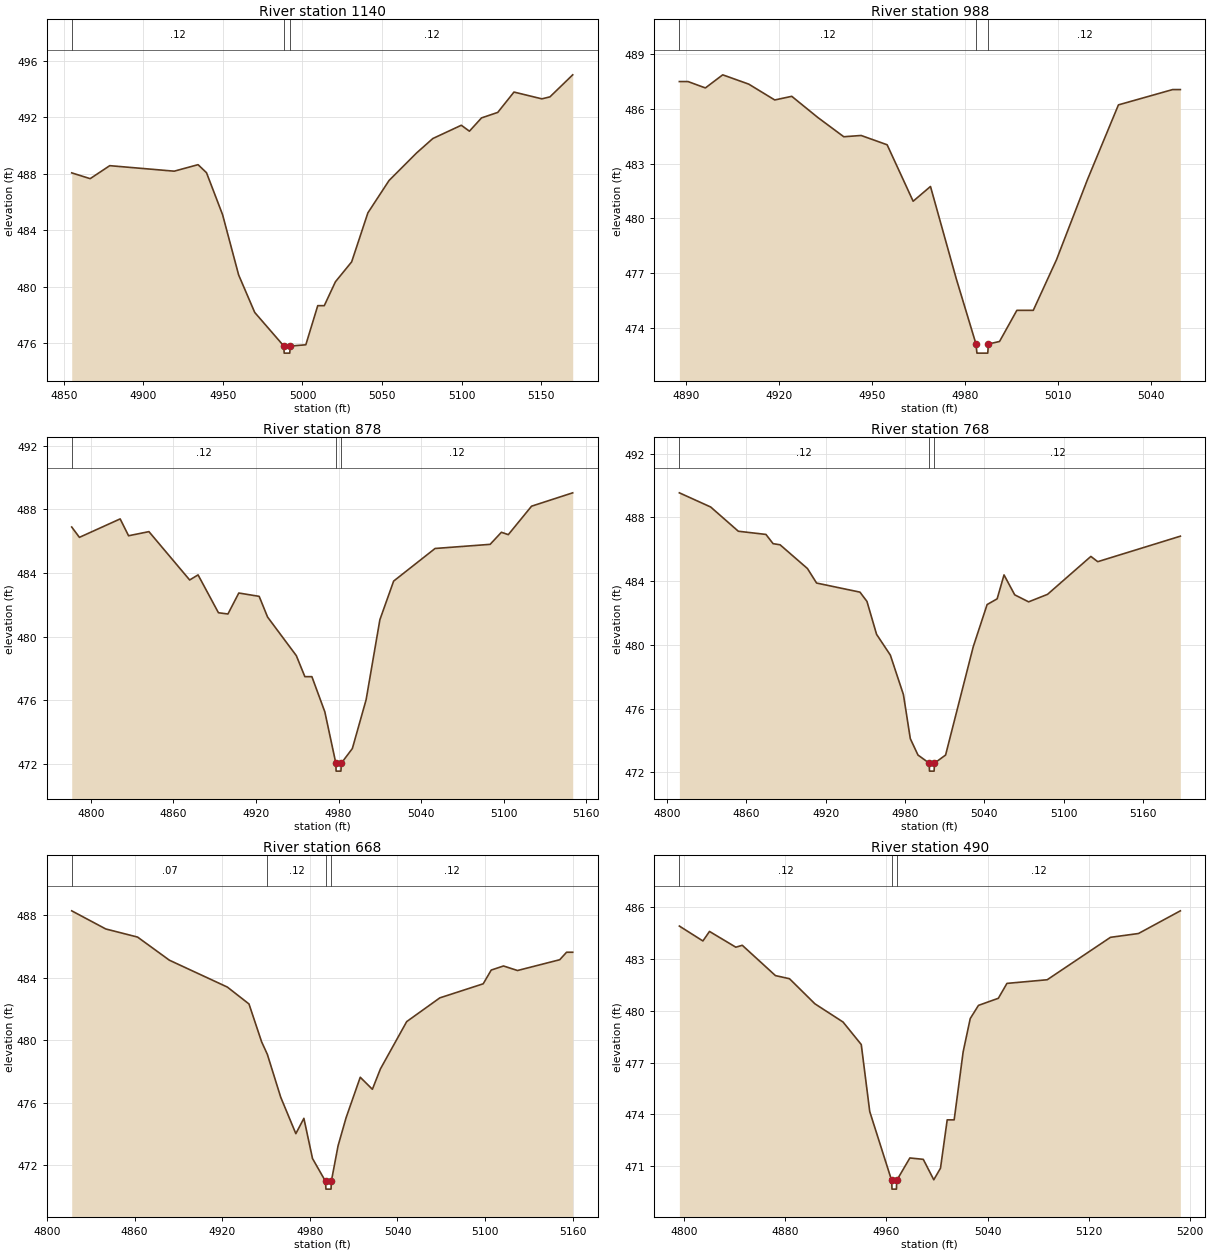
Type RM Length L Ch R = 1,1140,152,152,152
BEGIN DESCRIPTION:
H21417
END DESCRIPTION:
XS GIS Cut Line= 3
      2497831.36     13855812.24      2497988.15     13855787.70
      2498141.11     13855756.57
#Sta/Elev= 30
  4855.0  488.05  4866.6  487.64  4878.9  488.56  4919.4  488.17  4934.4  488.63
  4939.7  488.06  4949.8  485.09  4959.9  480.82  4970.0  478.17  4988.3  475.79
  4988.5  475.29  4992.0  475.29  4992.3  475.79  5002.1  475.88  5009.6  478.65
  5013.7  478.65  5020.7  480.34  5030.9  481.75  5041.1  485.22  5054.4  487.51
  5071.7  489.46  5081.9  490.48  5099.8  491.42  5104.9  491.00  5112.5  491.94
  5122.7  492.33  5132.9  493.77  5150.4  493.29  5155.5  493.43  5169.8  494.99
#Mann=3,-1,0
  4855.0    0.12       0  4988.3    0.05       0  4992.3    0.12       0
Bank Sta=4988.3,4992.3
Exp/Cntr=0.3,0.1

Type RM Length L Ch R = 1,988,110,110,110
BEGIN DESCRIPTION:
StreamM058 2.0
END DESCRIPTION:
XS GIS Cut Line= 3
      2497924.99     13855875.00      2498025.00     13855925.00
      2498074.99     13855925.00
#Sta/Elev= 27
  4887.8  487.51  4890.6  487.51  4896.2  487.16  4901.8  487.88  4910.2  487.37
  4918.6  486.50  4924.1  486.70  4932.5  485.54  4940.9  484.48  4946.5  484.55
  4954.9  484.04  4963.3  480.94  4968.9  481.75  4977.2  476.70  4983.6  473.10
  4983.9  472.60  4987.4  472.60  4987.6  473.10  4991.2  473.24  4996.8  474.95
  4999.6  474.95  5002.1  474.95  5009.6  477.73  5019.6  482.13  5029.6  486.23
  5047.1  487.07  5049.6  487.07
#Mann=3,-1,0
  4887.8    0.12       0  4983.6    0.05       0  4987.6    0.12       0
Bank Sta=4983.6,4987.6
Exp/Cntr=0.3,0.1

Type RM Length L Ch R = 1,878,110,110,110
BEGIN DESCRIPTION:
H21416
END DESCRIPTION:
XS GIS Cut Line= 3
      2497842.29     13855939.00      2497981.33     13856037.14
      2498174.91     13856027.60
#Sta/Elev= 30
  4786.1  486.89  4791.7  486.24  4821.3  487.40  4827.4  486.34  4842.2  486.60
  4871.8  483.56  4877.9  483.88  4892.7  481.50  4899.6  481.42  4907.5  482.74
  4922.3  482.53  4928.4  481.23  4949.3  478.80  4955.5  477.48  4960.6  477.48
  4970.0  475.27  4978.0  472.04  4978.2  471.54  4981.7  471.54  4982.0  472.04
  4990.0  472.96  5000.0  476.03  5010.0  481.06  5020.0  483.49  5050.1  485.54
  5090.1  485.80  5098.3  486.56  5103.3  486.41  5120.2  488.20  5150.1  489.04
#Mann=3,-1,0
  4786.1    0.12       0  4978.0    0.05       0  4982.0    0.12       0
Bank Sta=4978,4982
Exp/Cntr=0.3,0.1

Type RM Length L Ch R = 1,768,100,100,100
BEGIN DESCRIPTION:
H21415
END DESCRIPTION:
XS GIS Cut Line= 2
      2497842.30     13856200.71      2498204.86     13856090.31
#Sta/Elev= 30
  4809.4  489.54  4833.1  488.65  4854.0  487.13  4874.9  486.93  4880.3  486.35
  4885.6  486.28  4906.3  484.79  4913.2  483.88  4946.0  483.31  4951.3  482.73
  4958.6  480.66  4969.0  479.36  4978.9  476.88  4984.1  474.12  4989.9  473.09
  4998.4  472.58  4998.6  472.08  5002.1  472.08  5002.4  472.58  5010.8  473.09
  5031.7  479.88  5042.2  482.53  5049.8  482.89  5055.0  484.39  5063.1  483.14
  5073.6  482.70  5087.9  483.17  5120.7  485.55  5125.9  485.22  5188.4  486.82
#Mann=3,-1,0
  4809.4    0.12       0  4998.4    0.05       0  5002.4    0.12       0
Bank Sta=4998.4,5002.4
Exp/Cntr=0.3,0.1

Type RM Length L Ch R = 1,668,178,178,178
BEGIN DESCRIPTION:
H21414
END DESCRIPTION:
XS GIS Cut Line= 2
      2497903.64     13856302.94      2498218.50     13856166.64
#Sta/Elev= 30
  4816.9  488.27  4840.2  487.11  4862.0  486.59  4883.8  485.11  4923.5  483.39
  4938.3  482.31  4946.9  479.90  4950.9  479.08  4960.0  476.35  4970.4  474.01
  4975.9  474.99  4981.8  472.42  4990.7  470.96  4991.0  470.46  4994.5  470.46
  4994.7  470.96  4999.3  473.23  5004.8  475.03  5014.5  477.62  5022.8  476.85
  5028.3  478.15  5046.3  481.18  5069.0  482.70  5098.7  483.60  5104.2  484.48
  5112.6  484.74  5122.2  484.45  5151.1  485.14  5155.8  485.62  5160.0  485.62
#Mann=4,-1,0
  4816.9    0.07       0  4950.9    0.12       0  4990.7    0.05       0
  4994.7    0.12       0
Bank Sta=4990.7,4994.7
Exp/Cntr=0.3,0.1

Type RM Length L Ch R = 1,490,159,159,159
BEGIN DESCRIPTION:
StreamM058 1.0
END DESCRIPTION:
XS GIS Cut Line= 3
      2497982.68     13856416.09      2498185.80     13856346.56
      2498346.68     13856263.39
#Sta/Elev= 30
  4796.4  484.88  4815.0  484.02  4820.2  484.57  4841.0  483.66  4846.1  483.77
  4872.3  482.02  4883.4  481.84  4903.5  480.39  4925.7  479.34  4940.1  478.04
  4946.8  474.17  4964.1  470.19  4964.4  469.69  4967.9  469.69  4968.1  470.19
  4978.5  471.49  4989.1  471.41  4997.4  470.23  5002.7  470.90  5008.0  473.69
  5013.5  473.69  5020.6  477.62  5026.2  479.54  5032.7  480.30  5048.4  480.71
  5055.2  481.57  5087.0  481.78  5137.0  484.23  5159.1  484.45  5192.2  485.76
#Mann=3,-1,0
  4796.4    0.12       0  4964.1    0.05       0  4968.1    0.12       0
Bank Sta=4964.1,4968.1
Exp/Cntr=0.3,0.1

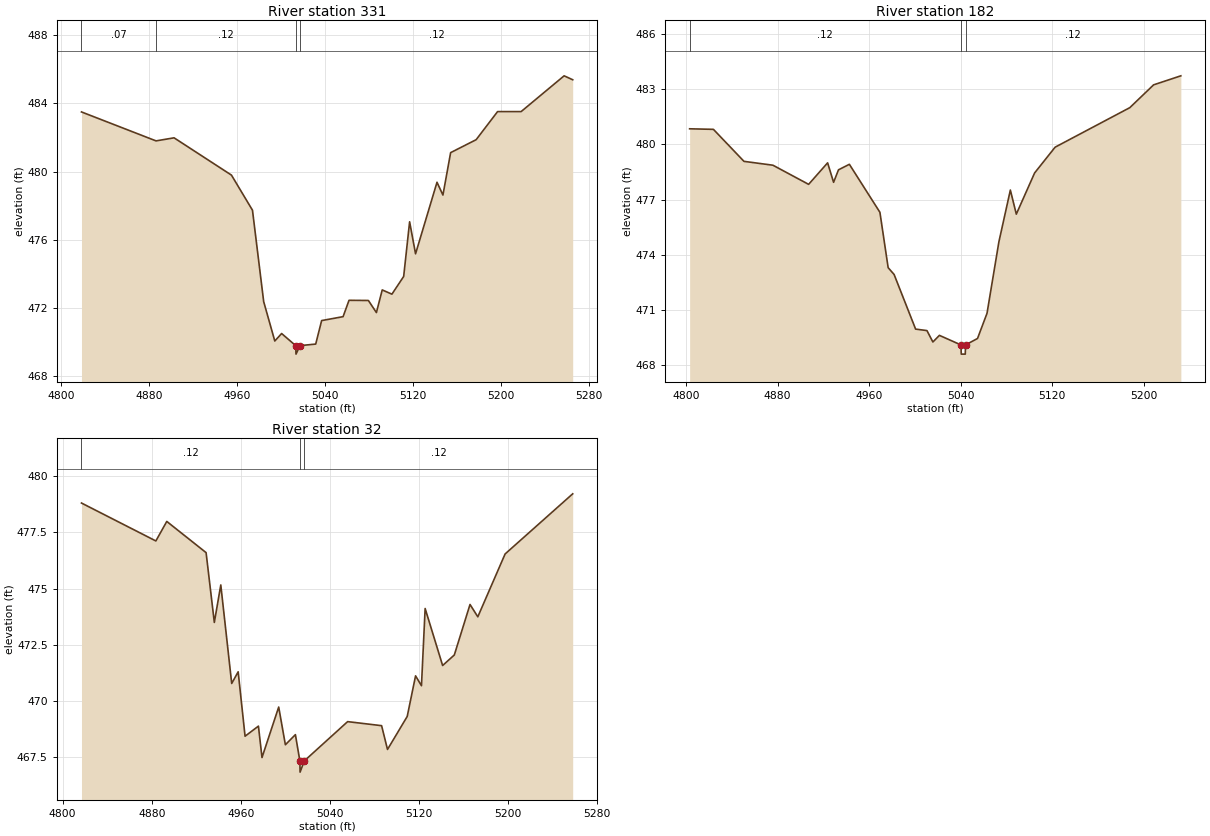
Type RM Length L Ch R = 1,331,149,149,149
BEGIN DESCRIPTION:
H21413
END DESCRIPTION:
XS GIS Cut Line= 3
      2498022.23     13856534.66      2498202.15     13856500.59
      2498448.89     13856407.89
#Sta/Elev= 30
  4818.4  483.50  4886.2  481.80  4902.6  481.98  4954.8  479.79  4973.9  477.73
  4984.1  472.36  4994.2  470.05  5000.4  470.49  5013.2  469.78  5013.5  469.28
  5017.2  469.78  5031.4  469.87  5036.8  471.25  5056.3  471.48  5061.7  472.44
  5079.3  472.43  5086.6  471.72  5091.9  473.05  5100.7  472.80  5111.4  473.84
  5116.8  477.05  5122.2  475.17  5141.7  479.37  5147.1  478.62  5154.1  481.11
  5177.3  481.87  5196.8  483.52  5218.2  483.52  5257.3  485.62  5265.1  485.39
#Mann=4,-1,0
  4818.4    0.07       0  4886.2    0.12       0  5013.2    0.05       0
  5017.2    0.12       0
Bank Sta=5013.2,5017.2
Exp/Cntr=0.3,0.1

Type RM Length L Ch R = 1,182,150,150,150
BEGIN DESCRIPTION:
H21412
END DESCRIPTION:
XS GIS Cut Line= 3
      2498084.95     13856606.91      2498210.33     13856642.35
      2498497.94     13856560.56
#Sta/Elev= 30
  4803.2  480.85  4824.0  480.82  4850.7  479.08  4876.0  478.87  4907.2  477.83
  4923.8  479.00  4929.0  477.94  4933.3  478.62  4942.8  478.92  4969.5  476.31
  4976.7  473.30  4981.9  472.93  5000.7  469.96  5010.6  469.88  5015.8  469.26
  5021.5  469.62  5040.3  469.10  5040.6  468.60  5044.1  468.60  5044.3  469.10
  5054.8  469.45  5063.1  470.82  5073.5  474.71  5083.5  477.52  5088.7  476.21
  5104.7  478.45  5122.6  479.85  5187.9  482.00  5208.7  483.24  5232.5  483.73
#Mann=3,-1,0
  4803.2    0.12       0  5040.3    0.05       0  5044.3    0.12       0
Bank Sta=5040.3,5044.3
Exp/Cntr=0.3,0.1

Type RM Length L Ch R = 1,32,0,0,0
BEGIN DESCRIPTION:
H21411
END DESCRIPTION:
XS GIS Cut Line= 5
      2498119.02     13856647.81      2498255.31     13856729.58
      2498297.57     13856758.21      2498390.26     13856792.29
      2498515.69     13856750.02
#Sta/Elev= 30
  4816.9  478.81  4883.7  477.12  4893.5  477.99  4928.8  476.60  4936.2  473.49
  4942.0  475.16  4951.8  470.77  4957.6  471.29  4963.8  468.42  4975.8  468.87
  4979.0  467.47  4994.0  469.72  5000.0  468.04  5009.0  468.49  5013.0  467.32
  5013.2  466.82  5017.0  467.32  5055.9  469.07  5086.4  468.89  5091.7  467.83
  5109.4  469.30  5116.9  471.11  5122.2  470.67  5125.5  474.11  5141.2  471.57
  5151.7  472.04  5165.8  474.29  5172.8  473.74  5197.3  476.54  5258.0  479.22
#Mann=3,-1,0
  4816.9    0.12       0  5013.0    0.05       0  5017.0    0.12       0
Bank Sta=5013,5017
Exp/Cntr=0.3,0.1

Chan Stop Cuts=-1