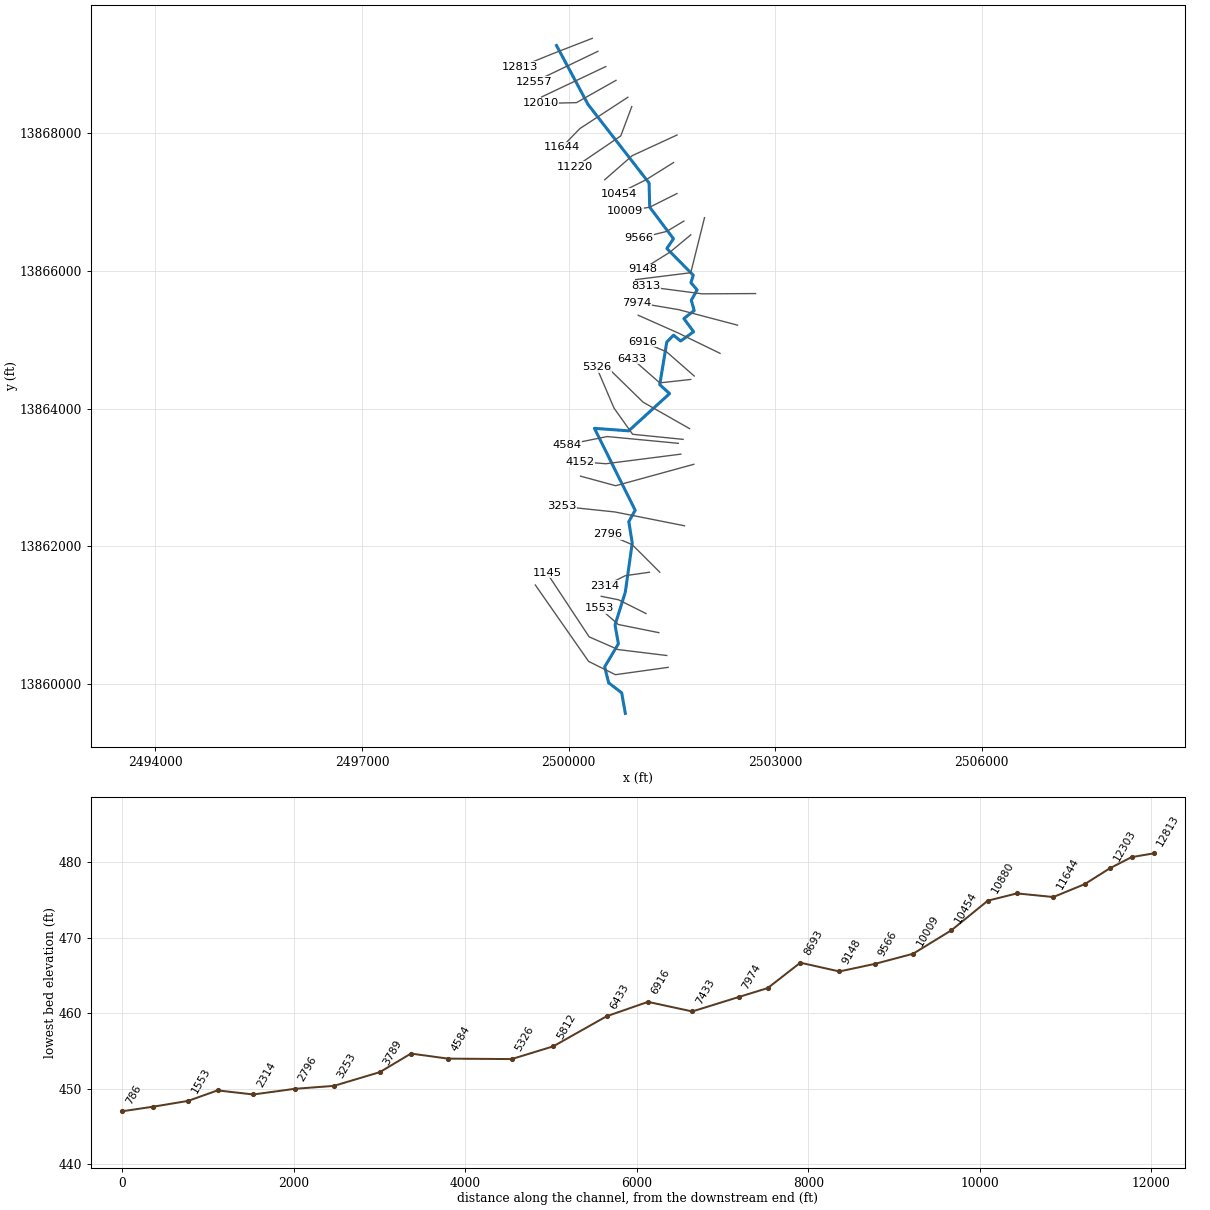
--- StreamM059.prj (project) ---

Proj Title=StreamM059 Base Level Engineering
Current Plan=p01
Default Exp/Contr=0.3,0.1
English Units
Geom File=g01
Flow File=f01
Plan File=p01
Y Axis Title=Elevation
X Axis Title(PF)=Main Channel Distance
X Axis Title(XS)=Station
BEGIN DESCRIPTION:
StreamM059
END DESCRIPTION:
DSS Export Rating Curves= 0
DSS Export Rating Curve Sorted= 0
DSS Export Volume Flow Curves= 0
DXF OffsetX= 0
DXF OffsetY= 0
DXF ScaleX= 1
DXF ScaleY= 10

--- StreamM059.p01 (plan) ---

Plan Title=Multiple Run
Short Identifier=Multiple
Geom File=g01
Flow File=f01
Subcritical Flow
K Sum by GR= 0
Std Step Tol= 0.01
Critical Tol= 0.01
Num of Std Step Trials= 20
Max Error Tol= 0.3
Flow Tol Ratio= 0.001
Split Flow NTrial= 30
Split Flow Tol= 0.02
Split Flow Ratio= 0.02
Log Output Level= 0
Friction Slope Method= 1
Unsteady Friction Slope Method= 2
Unsteady Bridges Friction Slope Method= 1
Parabolic Critical Depth
Global Vel Dist=  1 , 1 , 1
Global Log Level= 0
CheckData=True
Encroach Param= -1, 0, 0, 0
BEGIN DESCRIPTION:
Multiple Run
END DESCRIPTION:

--- StreamM059.f01 (steady flow) ---

Flow Title=Multiple
Number of Profiles=7
Profile Names=10-year,25-year,50-year,1pct_min,100-year,1pct_plu,500-year
River Rch & RM= StreamM059,Reach-1,12813
     695    1119    1501     975    1946    3884    3239
River Rch & RM= StreamM059,Reach-1,10880
     937    1530    2073    1359    2712    5411    4594
River Rch & RM= StreamM059,Reach-1,8313
    1224    2025    2767    1827    3646    7275    6272
River Rch & RM= StreamM059,Reach-1,5812
    1272    2106    2878    1901    3794    7569    6527
River Rch & RM= StreamM059,Reach-1,4584
    1356    2238    3052    2010    4010    8000    6855
Boundary for River Rch & Prof#=StreamM059,Reach-1,1
Up Type=0
Dn Type=3
Dn Slope=0.005
Boundary for River Rch & Prof#=StreamM059,Reach-1,2
Up Type=0
Dn Type=3
Dn Slope=0.005
Boundary for River Rch & Prof#=StreamM059,Reach-1,3
Up Type=0
Dn Type=3
Dn Slope=0.005
Boundary for River Rch & Prof#=StreamM059,Reach-1,4
Up Type=0
Dn Type=3
Dn Slope=0.005
Boundary for River Rch & Prof#=StreamM059,Reach-1,5
Up Type=0
Dn Type=3
Dn Slope=0.005
Boundary for River Rch & Prof#=StreamM059,Reach-1,6
Up Type=0
Dn Type=3
Dn Slope=0.005
Boundary for River Rch & Prof#=StreamM059,Reach-1,7
Up Type=0
Dn Type=3
Dn Slope=0.005

--- StreamM059.g01 (geometry) ---

Geom Title=Existing Conditions
Program Version=4.10

River Reach=StreamM059      ,Reach-1
Reach XY= 30
        2499825.       13869275.      2500283.15     13868418.94
      2501169.55     13867277.45      2501178.82     13866926.59
      2501523.58     13866468.57      2501428.03     13866326.47
       2501811.6     13865938.73      2501776.68     13865831.05
       2501867.7     13865725.08      2501782.48     13865575.01
        2501825.       13865425.      2501674.83     13865309.76
      2501816.16     13865118.05      2501628.33     13864982.62
      2501524.99     13865067.91      2501427.07     13864969.16
      2501324.59     13864349.61      2501467.55     13864218.97
      2500873.52     13863678.45      2500375.93     13863714.85
      2500967.47     13862524.99      2500875.08     13862359.61
       2500925.2     13862049.92      2500824.35     13861335.64
      2500675.38     13860859.73      2500723.81      13860585.5
      2500524.51     13860250.04      2500582.79     13860018.56
      2500771.52     13859873.74        2500825.       13859575.

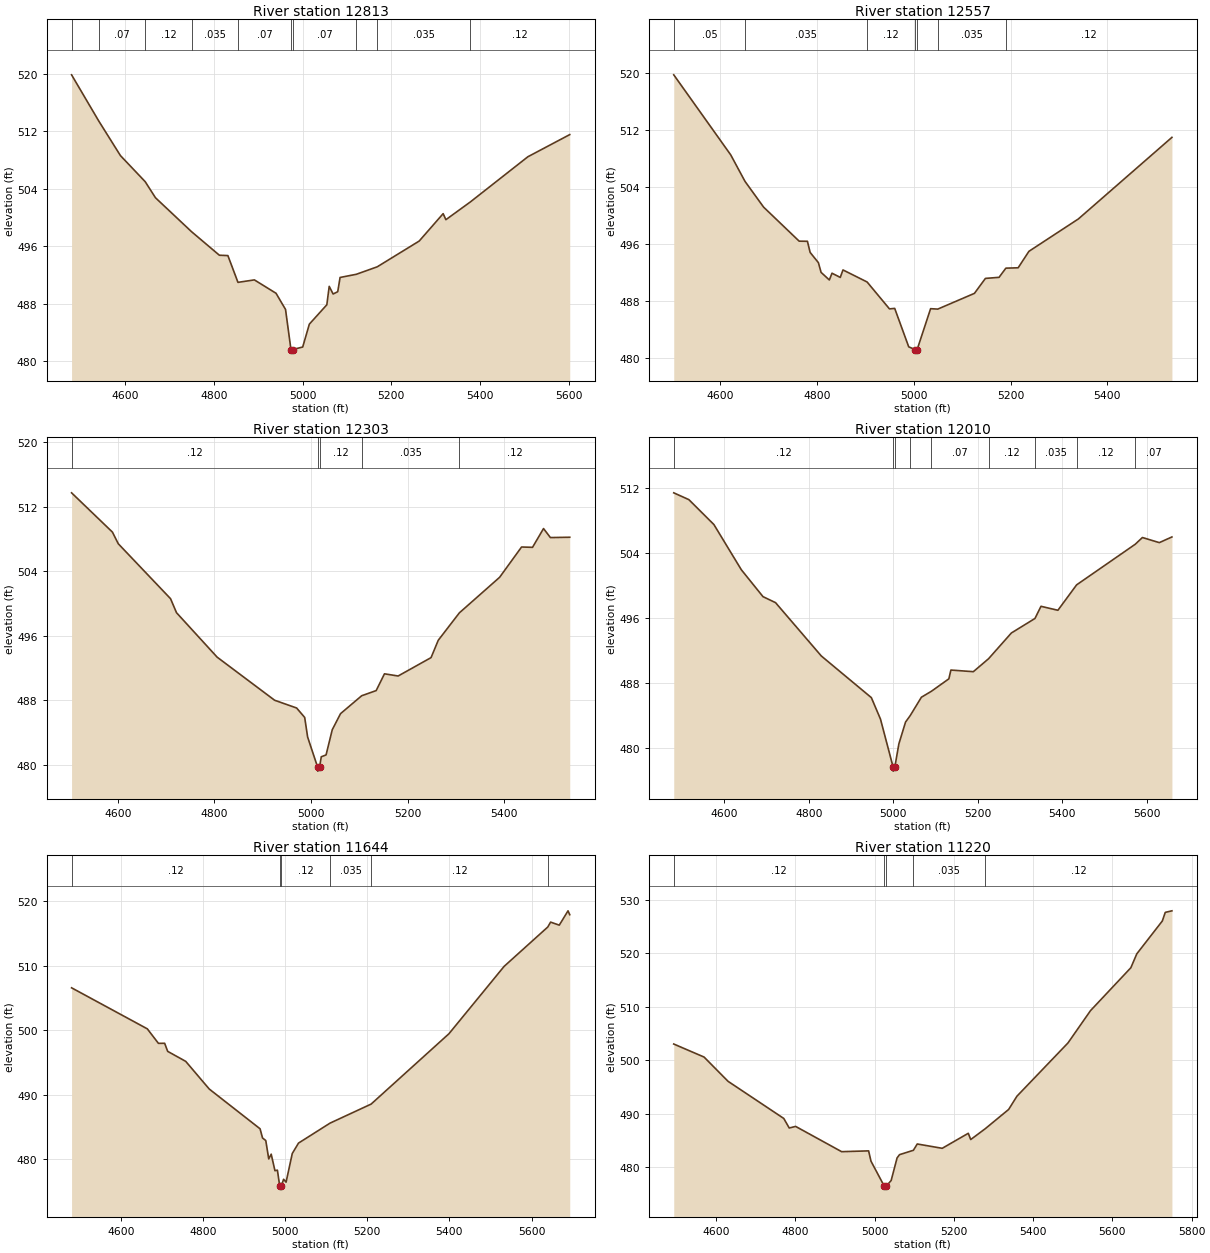
Type RM Length L Ch R = 1 ,12813   ,256,256,256
BEGIN DESCRIPTION:
H21434
END DESCRIPTION:
XS GIS Cut Line= 3
      2500344.79     13869379.13      2499775.47     13869157.96
      2499300.36     13868965.46
#Sta/Elev= 30
  4479.1  519.85  4540.6  513.41  4589.3  508.62  4645.2  504.99  4668.3  502.76
  4749.7  498.04  4812.4  494.77  4831.6  494.72  4854.3     491  4891.4  491.34
  4940.2  489.48  4961.6  487.23  4973.8  481.66    4974  481.16  4977.8  481.66
  5000.3  482.01  5015.3  485.19  5054.7  487.88  5060.1  490.44  5068.9  489.38
  5079.3   489.7  5084.6  491.68  5121.2  492.12  5168.4  493.16    5263  496.74
    5317  500.55  5323.2  499.71  5378.6  502.19  5508.1  508.46  5602.5  511.54
#Mann= 10 ,-1 , 0
  4479.1     .05       0  4540.6     .07       0  4645.2     .12       0
  4749.7    .035       0  4854.3     .07       0  4973.8     .05       0
  4977.8     .07       0  5121.2     .12       0  5168.4    .035       0
  5378.6     .12       0
Bank Sta=4973.8,4977.8
XS Rating Curve= 0 ,0
Exp/Cntr=0.3,0.1

Type RM Length L Ch R = 1 ,12557   ,254,254,254
BEGIN DESCRIPTION:
H21433
END DESCRIPTION:
XS GIS Cut Line= 2
      2500426.74     13869190.73       2499498.5     13868745.01
#Sta/Elev= 30
  4503.9  519.74  4621.7   508.5  4651.2  504.78  4689.6  501.17  4763.1  496.39
  4780.2  496.37  4785.8  494.81  4802.9  493.37  4808.4  492.01  4825.5  490.94
    4831  491.89  4848.1   491.3  4853.7  492.35  4903.5  490.66  4949.8  486.88
  4960.6  486.95  4989.6  481.55    5003  481.17  5003.3  480.67    5007  481.17
  5034.8  486.91  5049.6  486.85  5125.4  489.06  5148.1  491.16  5176.3  491.31
  5190.4   492.6  5215.8  492.65    5238  494.96  5340.3  499.51  5533.6  510.96
#Mann= 7 ,-1 , 0
  4503.9     .05       0  4651.2    .035       0  4903.5     .12       0
    5003     .05       0    5007     .12       0  5049.6    .035       0
  5190.4     .12       0
Bank Sta=5003,5007
XS Rating Curve= 0 ,0
Exp/Cntr=0.3,0.1

Type RM Length L Ch R = 1 ,12303   ,293,293,293
BEGIN DESCRIPTION:
H21432
END DESCRIPTION:
XS GIS Cut Line= 2
      2500541.44     13868969.55      2499608.78     13868527.77
#Sta/Elev= 30
    4504  513.71  4588.6  508.84  4600.8  507.39    4709  500.58  4721.4  498.84
  4805.5  493.33  4924.7  487.98  4970.2  487.02  4986.9  485.85    4993  483.42
  5013.7  479.69    5014  479.19  5017.7  479.69  5021.3  480.97  5031.2   481.2
    5044  484.32  5061.2  486.32    5105  488.54    5135  489.18  5152.2  491.26
  5180.5  490.99  5248.7  493.27  5263.6  495.42  5307.3  498.82  5390.7  503.23
  5436.2  506.99  5458.9  506.95  5481.7  509.28  5495.9  508.16    5536   508.2
#Mann= 5 ,-1 , 0
    4504     .12       0  5013.7     .05       0  5017.7     .12       0
    5105    .035       0  5307.3     .12       0
Bank Sta=5013.7,5017.7
XS Rating Curve= 0 ,0
Exp/Cntr=0.3,0.1

Type RM Length L Ch R = 1 ,12010   ,366,366,366
BEGIN DESCRIPTION:
H21431
END DESCRIPTION:
XS GIS Cut Line= 3
       2500688.9     13868768.85      2500115.44     13868445.26
      2499595.24     13868432.97
#Sta/Elev= 30
  4480.7   511.4  4516.5  510.56  4575.7  507.49  4640.7  501.91  4691.9   498.6
  4721.6  497.86  4829.8  491.29  4948.3  486.15  4969.9   483.5  4999.8  477.59
    5000  477.09  5003.8  477.59  5013.4  480.45  5029.2  483.14  5040.4  483.95
  5066.7   486.2  5090.5  486.94  5131.7  488.47  5136.5  489.55  5189.6  489.35
  5225.7  490.95  5279.6  494.12  5335.4  495.91  5349.7  497.41  5389.7  496.92
  5433.9  500.05  5572.7  505.06  5589.7  505.89  5629.7  505.26  5659.5  505.96
#Mann= 9 ,-1 , 0
  4480.7     .12       0  4999.8     .05       0  5003.8     .12       0
  5040.4    .035       0  5090.5     .07       0  5225.7     .12       0
  5335.4    .035       0  5433.9     .12       0  5572.7     .07       0
Bank Sta=4999.8,5003.8
XS Rating Curve= 0 ,0
Exp/Cntr=0.3,0.1

Type RM Length L Ch R = 1 ,11644   ,424,424,424
BEGIN DESCRIPTION:
H21430
END DESCRIPTION:
XS GIS Cut Line= 3
      2500860.92     13868523.09      2500164.59     13868068.43
      2499899.17     13867794.84
#Sta/Elev= 30
  4480.3  506.58  4664.7  500.22  4691.8  497.97  4706.9  497.98  4714.3  496.73
  4758.2  495.18  4815.5  490.89  4939.2  484.73  4945.2  483.31  4953.1  482.91
  4960.3  480.06  4966.3   480.8  4975.4  478.24  4981.4  478.32    4987  475.88
  4987.2  475.38    4991  475.88  4996.5  476.91  5002.5  476.46  5017.6   480.9
  5032.7  482.51  5109.6  485.61  5209.6  488.56    5399  499.46  5533.3   509.9
  5639.6     516  5646.5  516.76  5667.6  516.29  5688.9  518.51  5693.1  517.91
#Mann= 6 ,-1 , 0
  4480.3     .12       0    4987     .05       0    4991     .12       0
  5109.6    .035       0  5209.6     .12       0  5639.6     .07       0
Bank Sta=4987,4991
XS Rating Curve= 0 ,0
Exp/Cntr=0.3,0.1

Type RM Length L Ch R = 1 ,11220   ,340,340,340
BEGIN DESCRIPTION:
H21429
END DESCRIPTION:
XS GIS Cut Line= 3
      2500918.24     13868387.89      2500758.51     13867961.93
      2500094.94     13867511.36
#Sta/Elev= 30
  4493.2  503.02  4569.7  500.58  4630.2  496.04  4770.8  489.09  4784.6   487.3
  4800.7   487.6  4916.8  482.87  4984.9  483.02  4990.9  481.09  5024.8  476.36
  5025.1  475.86  5028.8  476.36  5041.8  477.48  5056.7   481.7  5062.8  482.31
  5097.9  483.13  5107.6  484.31  5170.6   483.5  5236.4  486.31  5242.5  485.14
  5278.9  487.15  5338.2  490.77  5359.1  493.25  5487.9  503.22  5544.8  509.27
  5646.6   517.3  5661.5  519.89    5726  526.05  5733.4  527.66  5750.2  527.95
#Mann= 5 ,-1 , 0
  4493.2     .12       0  5024.8     .05       0  5028.8     .12       0
  5097.9    .035       0  5278.9     .12       0
Bank Sta=5024.8,5028.8
XS Rating Curve= 0 ,0
Exp/Cntr=0.3,0.1

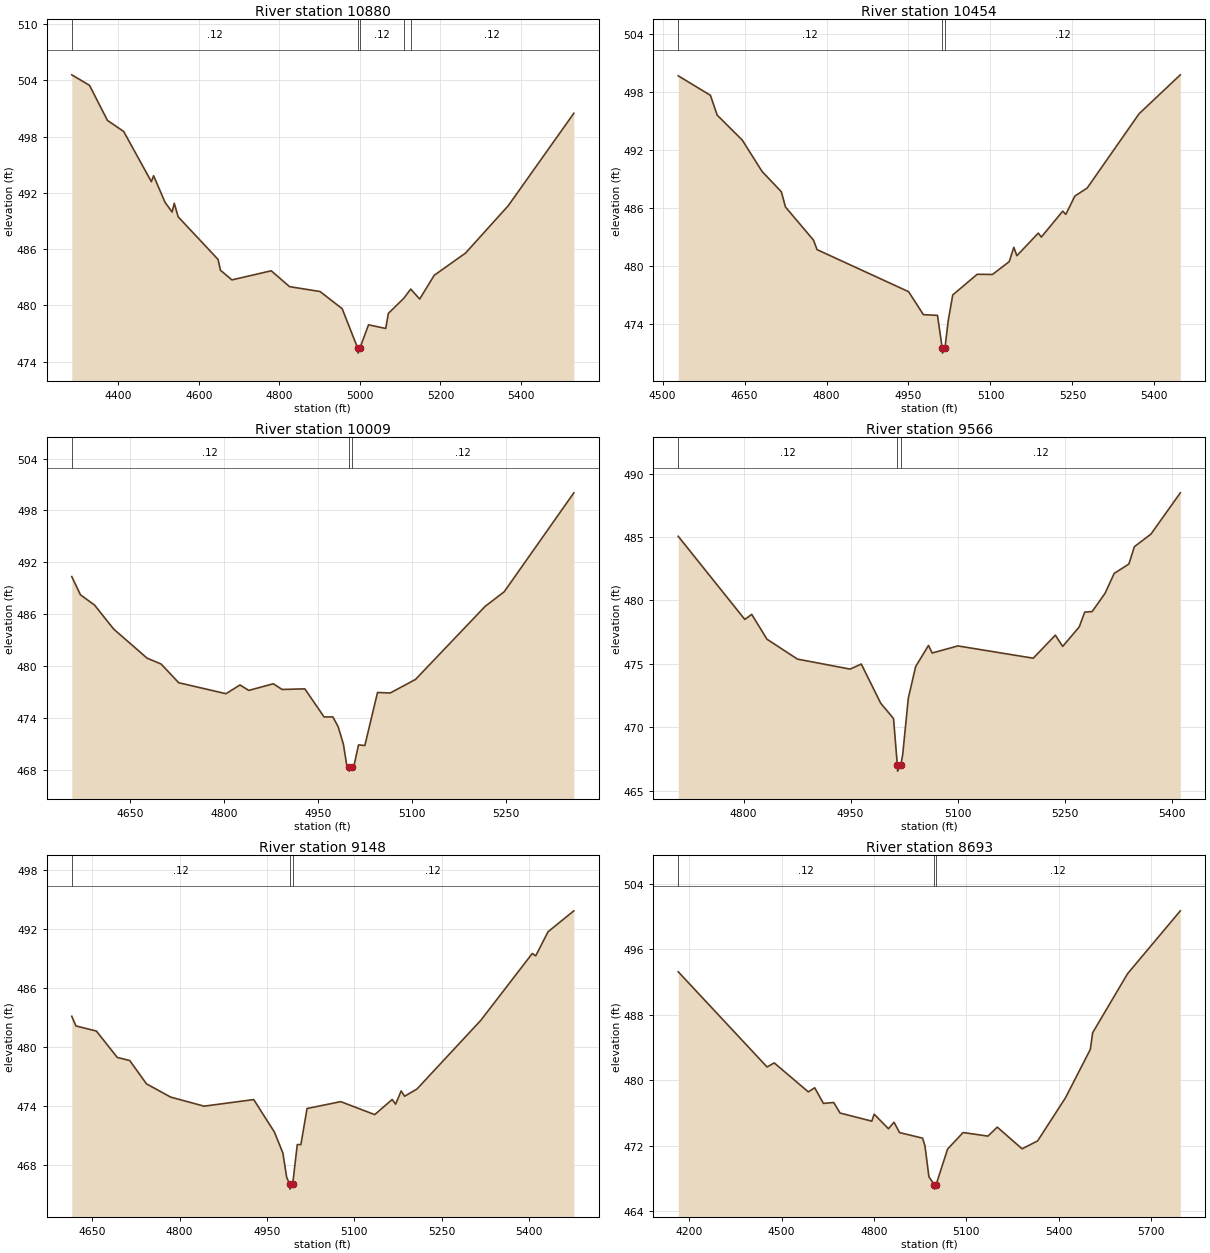
Type RM Length L Ch R = 1 ,10880   ,426,426,426
BEGIN DESCRIPTION:
StreamM059 21.0
END DESCRIPTION:
XS GIS Cut Line= 3
      2501575.01       13867975.        2500925.       13867675.
      2500525.01       13867325.
#Sta/Elev= 30
  4284.1  504.58  4328.2  503.46  4372.7  499.72  4413.1  498.54  4481.9  493.18
  4487.4  493.82  4515.9  490.98  4533.3  489.95  4538.8  490.88  4548.4  489.44
  4647.6  484.89  4653.5  483.74    4682  482.71  4779.7  483.68  4825.2  481.99
  4900.9  481.47  4955.9  479.64  4994.8   475.4  4995.2   474.9  4999.6   475.4
  5021.4  477.92  5064.1  477.53  5070.7  479.14  5109.1  480.75  5126.2  481.73
  5148.5  480.67  5184.6   483.2  5262.4  485.57  5368.7  490.63  5531.5  500.48
#Mann= 5 ,-1 , 0
  4284.1     .12       0  4994.8     .05       0  4999.6     .12       0
  5109.1    .035       0  5126.2     .12       0
Bank Sta=4994.8,4999.6
XS Rating Curve= 0 ,0
Exp/Cntr=0.3,0.1

Type RM Length L Ch R = 1 ,10454   ,445,445,445
BEGIN DESCRIPTION:
StreamM059 20.0
END DESCRIPTION:
XS GIS Cut Line= 3
      2501524.99     13867574.99        2501125.       13867325.
        2500725.       13867125.
#Sta/Elev= 30
  4528.6  499.67  4587.5  497.65  4599.9   495.6  4645.9  493.01  4681.9  489.78
  4717.3  487.67  4724.9  486.09  4776.2  482.66  4782.7  481.68  4950.2  477.33
  4977.3  474.95  5003.1  474.88  5011.8  471.47  5012.2  470.97  5016.7  471.47
  5022.6  474.28    5031  476.99  5075.8  479.13  5103.7  479.11  5134.4  480.44
  5142.8  481.92  5148.4  481.05  5187.6  483.39  5193.1  482.98  5232.3  485.66
  5237.9  485.33  5254.6  487.23    5277  488.05    5372  495.74  5447.5  499.77
#Mann= 3 ,-1 , 0
  4528.6     .12       0  5011.8     .05       0  5016.7     .12       0
Bank Sta=5011.8,5016.7
XS Rating Curve= 0 ,0
Exp/Cntr=0.3,0.1

Type RM Length L Ch R = 1 ,10009   ,443,443,443
BEGIN DESCRIPTION:
StreamM059 19.0
END DESCRIPTION:
XS GIS Cut Line= 3
      2501574.96     13867124.98        2501175.       13866925.
      2500825.02       13866875.
#Sta/Elev= 30
    4557  490.36  4570.9  488.25  4593.3  487.07    4624  484.28  4677.1  480.93
  4699.5  480.25  4727.5  478.09  4802.9  476.82  4825.3  477.83  4839.3   477.2
  4878.4  477.97  4892.4  477.31  4928.7  477.38  4959.4  474.13  4973.4  474.14
  4981.8  473.01  4990.2  470.99  4995.8  468.42  4998.9  468.37  4999.3  467.87
  5003.8  468.37  5006.7  468.37  5014.3   470.9  5024.4  470.83  5044.6  476.96
  5064.8   476.9  5105.2  478.47  5216.3  486.92  5246.6   488.6  5357.7  500.04
#Mann= 3 ,-1 , 0
    4557     .12       0  4998.9     .05       0  5003.8     .12       0
Bank Sta=4998.9,5003.8
XS Rating Curve= 0 ,0
Exp/Cntr=0.3,0.1

Type RM Length L Ch R = 1 ,9566    ,418,418,418
BEGIN DESCRIPTION:
StreamM059 18.0
END DESCRIPTION:
XS GIS Cut Line= 3
      2501674.99     13866724.99        2501425.       13866575.
      2501025.05     13866475.01
#Sta/Elev= 30
  4708.5  485.06  4801.8   478.5  4811.5   478.9  4832.9  476.94  4875.6  475.37
  4949.5  474.58  4965.1  474.98  4992.3  471.89  5010.3  470.68  5015.6  467.03
    5016  466.53  5020.6  467.03  5023.2  467.86    5031  472.28  5041.3  474.78
  5059.3  476.45  5064.5  475.85  5100.5  476.41  5206.2  475.44  5237.1  477.26
  5247.4  476.37  5270.6  477.91  5278.3  479.08  5288.7  479.12  5306.7  480.55
  5319.6  482.13  5340.2  482.87  5347.9  484.24  5371.1  485.23  5412.3  488.49
#Mann= 3 ,-1 , 0
  4708.5     .12       0  5015.6     .05       0  5020.6     .12       0
Bank Sta=5015.6,5020.6
XS Rating Curve= 0 ,0
Exp/Cntr=0.3,0.1

Type RM Length L Ch R = 1 ,9148    ,455,455,455
BEGIN DESCRIPTION:
StreamM059 17.0
END DESCRIPTION:
XS GIS Cut Line= 3
      2501775.03     13866525.03        2501475.       13866275.
      2501074.96     13866024.98
#Sta/Elev= 30
  4614.7   483.1  4621.9  482.12    4657   481.6  4692.8  478.92  4714.3   478.6
    4743  476.23  4784.6  474.88  4841.9  473.96  4927.2  474.63  4962.9  471.31
  4977.3  469.19  4983.8  466.71  4989.1  466.02  4989.4  465.52  4994.1  466.02
    5002  470.05  5008.2  470.05  5018.8  473.72  5076.6  474.42    5135   473.1
    5165  474.64  5170.9  474.16  5180.4  475.51  5186.3  474.97  5207.5   475.7
  5317.2  482.69  5405.6  489.49  5411.5  489.25  5432.7   491.7    5477  493.83
#Mann= 3 ,-1 , 0
  4614.7     .12       0  4989.1     .05       0  4994.1     .12       0
Bank Sta=4989.1,4994.1
XS Rating Curve= 0 ,0
Exp/Cntr=0.3,0.1

Type RM Length L Ch R = 1 ,8693    ,380,380,380
BEGIN DESCRIPTION:
StreamM059 16.0
END DESCRIPTION:
XS GIS Cut Line= 3
        2501975.     13866775.02        2501775.       13865975.
      2500974.97       13865875.
#Sta/Elev= 30
    4164  493.25  4452.6  481.61  4475.8  482.11  4586.6  478.57  4607.3  479.07
  4635.6  477.16  4669.1  477.27  4689.7  475.98  4792.8  474.99  4800.5  475.84
  4846.9  474.06  4864.9  474.86    4883  473.59  4957.7  472.91  4965.4  471.98
  4978.3   468.2  4996.2  467.18  4996.6  466.68  5001.2  467.18    5039  471.58
  5089.4   473.6    5170  473.16  5200.3  474.26  5280.9  471.61  5331.3  472.57
    5422  477.85  5502.6  483.76  5510.2   485.8  5623.5  493.01  5794.9   500.7
#Mann= 3 ,-1 , 0
    4164     .12       0  4996.2     .05       0  5001.2     .12       0
Bank Sta=4996.2,5001.2
XS Rating Curve= 0 ,0
Exp/Cntr=0.3,0.1

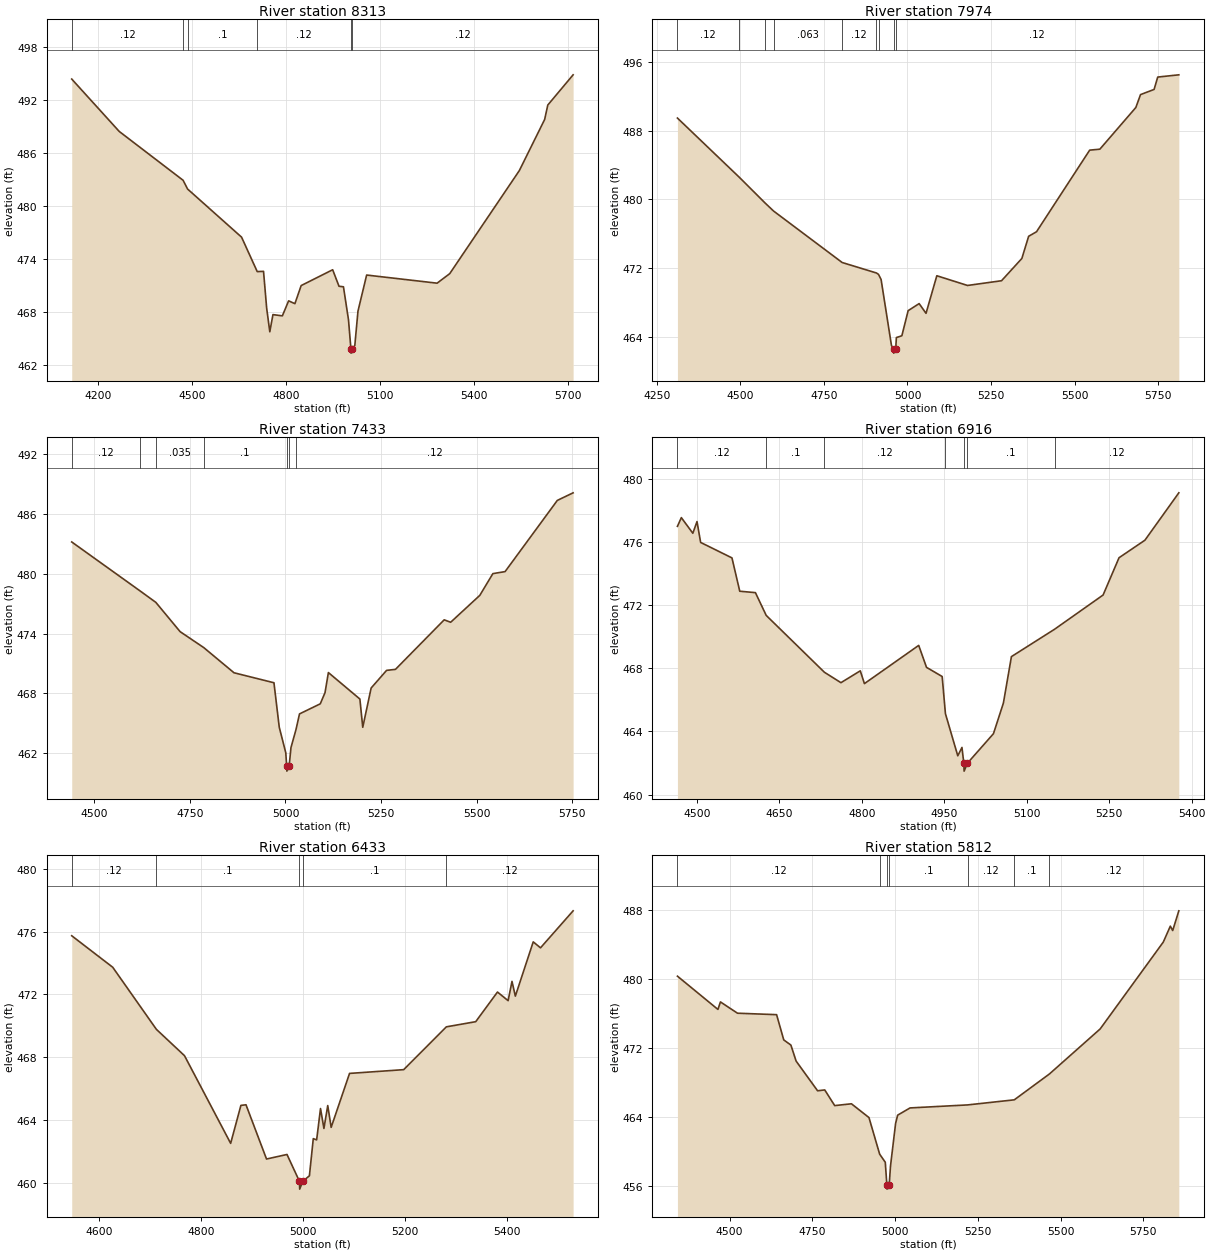
Type RM Length L Ch R = 1 ,8313    ,339,339,339
BEGIN DESCRIPTION:
StreamM059 15.0
END DESCRIPTION:
XS GIS Cut Line= 3
      2502716.35     13865672.28      2501942.24     13865668.19
      2501125.01       13865775.
#Sta/Elev= 30
  4117.4  494.35  4268.8  488.42  4472.4  482.89  4486.7   481.9  4658.8  476.45
  4708.7  472.55  4728.8  472.58  4738.8  468.41  4748.8  465.74  4758.8  467.68
  4788.8  467.54  4808.8  469.24  4828.8  468.92  4848.8  470.97  4949.2  472.76
  4969.4  470.89  4983.6  470.83  4999.7  467.08  5007.3  463.82  5007.6  463.32
  5012.3  463.82  5019.8  464.19  5029.9  468.08  5057.5  472.16  5282.1  471.24
  5322.4  472.32  5544.3  483.99  5624.9  489.77    5635  491.41  5715.7  494.83
#Mann= 6 ,-1 , 0
  4117.4     .12       0  4472.4    .035       0  4486.7      .1       0
  4708.7     .12       0  5007.3     .05       0  5012.3     .12       0
Bank Sta=5007.3,5012.3
XS Rating Curve= 0 ,0
Exp/Cntr=0.3,0.1

Type RM Length L Ch R = 1 ,7974    ,541,541,541
BEGIN DESCRIPTION:
H21428
END DESCRIPTION:
XS GIS Cut Line= 3
      2502454.26     13865213.53      2501598.18     13865438.81
        2500992.     13865541.21
#Sta/Elev= 30
  4311.8  489.47  4496.7  482.59  4574.6  479.57  4599.3  478.66  4804.6  472.67
  4907.3  471.45  4913.3  471.29  4921.1  470.69  4952.1  463.02  4958.4  462.63
  4958.9  462.13  4964.8  462.63  4966.8  463.94  4983.2  464.15    5002  467.07
  5034.9  467.89  5055.5  466.76  5087.8  471.13  5179.6     470  5281.4  470.55
  5342.2  473.14  5362.5  475.72  5386.1  476.25  5545.1  485.74  5575.5  485.85
  5683.2   490.7  5697.2   492.2  5737.8   492.8  5748.7  494.24  5811.8   494.5
#Mann= 9 ,-1 , 0
  4311.8     .12       0  4496.7    .063       0  4574.6    .035       0
  4599.3    .063       0  4804.6     .12       0  4907.3      .1       0
  4913.3     .12       0  4958.4     .05       0  4964.8     .12       0
Bank Sta=4958.4,4964.8
XS Rating Curve= 0 ,0
Exp/Cntr=0.3,0.1

Type RM Length L Ch R = 1 ,7433    ,517,517,517
BEGIN DESCRIPTION:
H21427
END DESCRIPTION:
XS GIS Cut Line= 3
      2502200.27     13864803.94      2501594.08     13865098.85
      2501012.47     13865356.88
#Sta/Elev= 30
  4441.4  483.17  4620.6  478.25  4661.2  477.12  4724.6  474.19  4786.5  472.59
  4865.5  470.07  4969.9  469.07  4983.8  464.61  5000.8  462.06  5003.2  460.72
  5003.7  460.22  5009.6  460.72  5014.4  462.58  5027.5  464.38  5036.7  465.95
    5091  466.96  5103.4  468.08  5112.2  470.09  5194.5  467.44    5202  464.61
  5223.9  468.54  5264.3  470.31  5287.5  470.41  5414.8  475.37  5431.8  475.13
  5507.9  477.82  5542.1     480    5574   480.2  5710.5  487.33  5751.8  488.09
#Mann= 7 ,-1 , 0
  4441.4     .12       0  4620.6      .1       0  4661.2    .035       0
  4786.5      .1       0  5003.2     .05       0  5009.6      .1       0
  5027.5     .12       0
Bank Sta=5003.2,5009.6
XS Rating Curve= 0 ,0
Exp/Cntr=0.3,0.1

Type RM Length L Ch R = 1 ,6916    ,483,483,483
BEGIN DESCRIPTION:
StreamM059 12.0
END DESCRIPTION:
XS GIS Cut Line= 3
      2501824.99     13864475.01        2501425.       13864825.
      2501074.99     13864975.01
#Sta/Elev= 30
  4464.4  476.99  4471.5  477.54  4492.4  476.55    4500  477.29  4506.6  475.97
  4563.6  474.99  4577.8  472.88  4606.3  472.79  4625.9  471.35  4731.8  467.75
  4761.9  467.09  4797.1  467.84  4804.6  467.03  4903.4  469.45  4917.6  468.06
  4946.1  467.48    4952  465.13  4974.5  462.46  4982.1  462.99  4985.5  461.99
    4986  461.49    4992  461.99  5039.4  463.86  5057.5   465.8  5072.1  468.74
  5150.5  470.47  5238.9  472.64  5267.9     475    5315  476.11  5376.7  479.11
#Mann= 7 ,-1 , 0
  4464.4     .12       0  4625.9      .1       0  4731.8     .12       0
    4952      .1       0  4985.5     .05       0    4992      .1       0
  5150.5     .12       0
Bank Sta=4985.5,4992
XS Rating Curve= 0 ,0
Exp/Cntr=0.3,0.1

Type RM Length L Ch R = 1 ,6433    ,621,621,621
BEGIN DESCRIPTION:
StreamM059 11.0
END DESCRIPTION:
XS GIS Cut Line= 3
      2501775.05     13864425.01        2501325.       13864375.
      2500925.02     13864724.98
#Sta/Elev= 30
  4546.4  475.74  4626.9  473.73  4712.6  469.77  4767.8  468.09  4858.4   462.5
  4878.5  464.92  4888.5  464.96  4928.8   461.5    4969  461.79  4993.4  460.08
  4993.9  459.58    5000  460.08    5013  460.43  5020.6   462.8  5027.2  462.72
  5034.8  464.72  5041.5  463.45    5049  464.91  5055.7  463.52  5091.8  466.96
  5198.1   467.2  5281.8  469.93  5339.5  470.26  5382.2  472.15  5403.1   471.6
  5410.7  472.83  5417.3  471.89  5452.4  475.35  5466.7  474.97  5530.7  477.33
#Mann= 5 ,-1 , 0
  4546.4     .12       0  4712.6      .1       0  4993.4     .05       0
    5000      .1       0  5281.8     .12       0
Bank Sta=4993.4,5000
XS Rating Curve= 0 ,0
Exp/Cntr=0.3,0.1

Type RM Length L Ch R = 1 ,5812    ,486,486,486
BEGIN DESCRIPTION:
H21426
END DESCRIPTION:
XS GIS Cut Line= 3
      2501757.96     13863710.29      2501082.09     13864095.33
      2500554.47     13864610.68
#Sta/Elev= 30
  4342.1  480.33  4464.5  476.47  4472.1  477.34  4523.6  476.03  4641.8  475.86
  4663.4  472.93    4685  472.33  4700.8  470.47  4765.7  467.02  4787.3  467.12
  4817.4   465.3    4868  465.51    4921  463.91  4953.3  459.66  4970.3  458.72
    4975   456.1  4975.5   455.6  4982.1   456.1  4986.1   458.3  5001.5  463.24
  5007.7  464.19  5045.2  465.03  5219.2  465.38  5360.2  465.97  5466.6  468.98
  5619.7   474.2  5810.7   484.3  5831.8  486.14    5839  485.63  5857.5  487.92
#Mann= 7 ,-1 , 0
  4342.1     .12       0  4953.3      .1       0    4975     .05       0
  4982.1      .1       0  5219.2     .12       0  5360.2      .1       0
  5466.6     .12       0
Bank Sta=4975,4982.1
XS Rating Curve= 0 ,0
Exp/Cntr=0.3,0.1

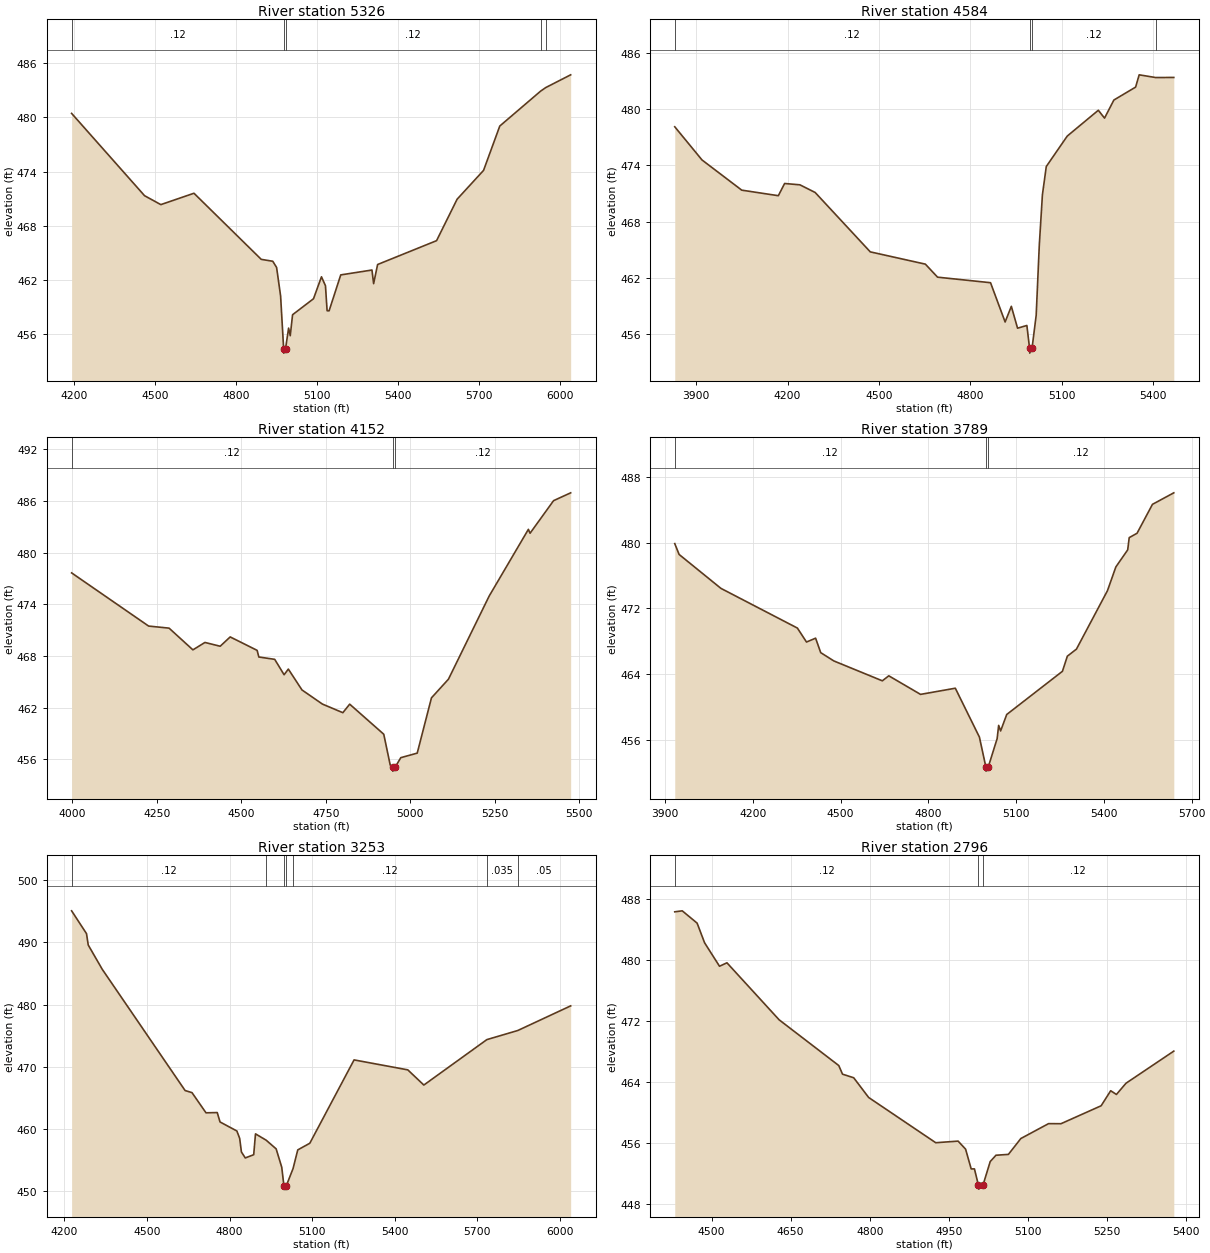
Type RM Length L Ch R = 1 ,5326    ,742,742,742
BEGIN DESCRIPTION:
H21425
END DESCRIPTION:
XS GIS Cut Line= 4
      2501663.73     13863554.66      2500930.54     13863628.39
       2500660.2     13864009.32      2500406.93     13864601.65
#Sta/Elev= 30
  4189.8  480.45  4459.9  471.34  4520.2  470.35  4642.9  471.61  4892.1  464.29
  4934.8  464.08    4949  463.39  4963.8  460.23    4975  454.41  4975.5  453.91
  4982.1  454.41  4993.4  456.68  4999.5  455.84  5008.1  458.16  5085.6  459.93
  5115.1  462.36  5129.9  461.37    5136   458.6  5143.3  458.59  5186.5  462.57
  5302.1  463.11  5308.3   461.6    5323  463.72  5541.4  466.36  5617.5  470.95
  5715.4  474.14  5775.5  479.05  5926.9  482.92  5945.8  483.31    6038  484.72
#Mann= 5 ,-1 , 0
  4189.8     .12       0    4975     .05       0  4982.1     .12       0
  5926.9     .07       0  5945.8     .12       0
Bank Sta=4975,4982.1
XS Rating Curve= 0 ,0
Exp/Cntr=0.3,0.1

Type RM Length L Ch R = 1 ,4584    ,432,432,432
BEGIN DESCRIPTION:
H21424
END DESCRIPTION:
XS GIS Cut Line= 3
      2501594.05     13863497.32       2500561.9     13863595.62
      2499972.07     13863476.84
#Sta/Elev= 30
  3829.5  478.11    3919  474.57  4049.5  471.35  4169.6  470.76  4190.2  472.06
  4240.4  471.92  4290.6   471.1  4471.4  464.77  4652.3  463.46  4692.4  462.07
  4866.3  461.48  4914.2  457.29  4934.6  458.96    4955  456.63  4985.6  456.92
  4994.5  454.47    4995  453.97  5002.5  454.47  5016.2  458.02  5026.4  465.49
  5036.6  470.85  5049.3  473.87  5118.2  477.12  5220.2  479.87  5240.6  479.03
  5271.2  480.96  5342.6  482.34  5354.3  483.65  5408.7  483.36    5468  483.37
#Mann= 4 ,-1 , 0
  3829.5     .12       0  4994.5     .05       0  5002.5     .12       0
  5408.7      .1       0
Bank Sta=4994.5,5002.5
XS Rating Curve= 0 ,0
Exp/Cntr=0.3,0.1

Type RM Length L Ch R = 1 ,4152    ,363,363,363
BEGIN DESCRIPTION:
H21423
END DESCRIPTION:
XS GIS Cut Line= 3
      2501630.93     13863340.03      2500541.42     13863200.77
      2500164.59     13863229.44
#Sta/Elev= 30
  3998.3  477.64  4226.1  471.47  4286.6  471.23  4357.1  468.71  4392.7  469.57
  4437.8  469.13  4467.4  470.21  4547.1  468.65  4552.2  467.88  4599.1  467.61
  4626.9  465.82  4639.4  466.48  4679.7  464.06  4740.2  462.42  4800.7  461.42
  4820.9  462.41  4921.7  458.92  4940.9  455.33  4947.9  455.14  4948.4  454.64
    4956  455.14  4972.1   456.2  5020.7  456.73  5062.8  463.14  5113.1  465.31
  5233.5  474.95  5349.5  482.69  5354.5  482.24    5424  486.02  5474.6  486.93
#Mann= 3 ,-1 , 0
  3998.3     .12       0  4947.9     .05       0    4956     .12       0
Bank Sta=4947.9,4956
XS Rating Curve= 0 ,0
Exp/Cntr=0.3,0.1

Type RM Length L Ch R = 1 ,3789    ,536,536,536
BEGIN DESCRIPTION:
H21422
END DESCRIPTION:
XS GIS Cut Line= 3
      2501819.33     13863192.57      2500684.78     13862881.28
      2500173.82     13863020.26
#Sta/Elev= 30
    3933  479.87  3947.9  478.55  4090.9  474.42  4352.3  469.59  4383.4  467.89
  4414.5  468.36    4432   466.6  4476.9  465.59  4642.6  463.17  4664.7  463.78
  4773.2  461.52  4892.1  462.27  4974.4  456.33  4996.6  452.68  4997.1  452.18
  5004.7  452.68  5035.1  456.14  5040.3  457.75    5047  457.07  5067.8  459.07
  5258.3  464.33  5275.1  466.17  5306.2  467.03  5412.2  474.14  5440.9  477.03
  5481.4  479.11  5486.6   480.6  5513.4  481.13  5566.1  484.65    5639  486.05
#Mann= 3 ,-1 , 0
    3933     .12       0  4996.6     .05       0  5004.7     .12       0
Bank Sta=4996.6,5004.7
XS Rating Curve= 0 ,0
Exp/Cntr=0.3,0.1

Type RM Length L Ch R = 1 ,3253    ,457,457,457
BEGIN DESCRIPTION:
H21421
END DESCRIPTION:
XS GIS Cut Line= 3
      2501684.21     13862299.65      2500672.49     13862500.36
      2499894.22     13862582.28
#Sta/Elev= 30
  4226.1  495.07  4280.3   491.4  4286.5  489.58  4337.4  485.68  4638.6   466.2
  4663.7  465.86  4714.6  462.62  4755.4  462.66  4765.6  461.15  4826.8   459.7
    4837  458.51  4843.3  456.33  4857.4  455.37    4888  455.89  4894.5  459.24
  4933.3  458.22  4969.5  456.83  4989.9  453.88  4997.9  450.86  4998.4  450.36
  5006.1  450.86    5031  453.66  5048.1  456.66  5091.9  457.73  5252.8  471.12
  5448.1  469.52  5506.4  467.08  5735.5  474.38  5847.7  475.84  6040.1   479.8
#Mann= 7 ,-1 , 0
  4226.1     .12       0  4933.3      .1       0  4997.9     .05       0
  5006.1      .1       0    5031     .12       0  5735.5    .035       0
  5847.7     .05       0
Bank Sta=4997.9,5006.1
XS Rating Curve= 0 ,0
Exp/Cntr=0.3,0.1

Type RM Length L Ch R = 1 ,2796    ,482,482,482
BEGIN DESCRIPTION:
StreamM059 3.0
END DESCRIPTION:
XS GIS Cut Line= 3
      2501325.01     13861624.99        2500925.       13862025.
      2500574.99       13862175.
#Sta/Elev= 30
  4430.2   486.3  4444.4  486.43  4472.6  484.82  4486.8  482.24  4515.1  479.17
  4529.2  479.62  4628.2  472.15  4741.3  466.16  4748.4  465.03  4769.6  464.56
  4797.9  461.98  4925.2  456.05  4967.6  456.26  4981.8  455.21  4992.4  452.62
  4998.6  452.62  5006.2  450.47  5006.7  449.97  5014.7  450.47  5028.5  453.58
  5039.4  454.41    5063  454.52  5086.6   456.6  5139.2  458.55  5162.7  458.54
  5238.9  460.89    5257  462.86  5267.9  462.37    5286  463.84  5376.7  468.05
#Mann= 3 ,-1 , 0
  4430.2     .12       0  5006.2     .05       0  5014.7     .12       0
Bank Sta=5006.2,5014.7
XS Rating Curve= 0 ,0
Exp/Cntr=0.3,0.1

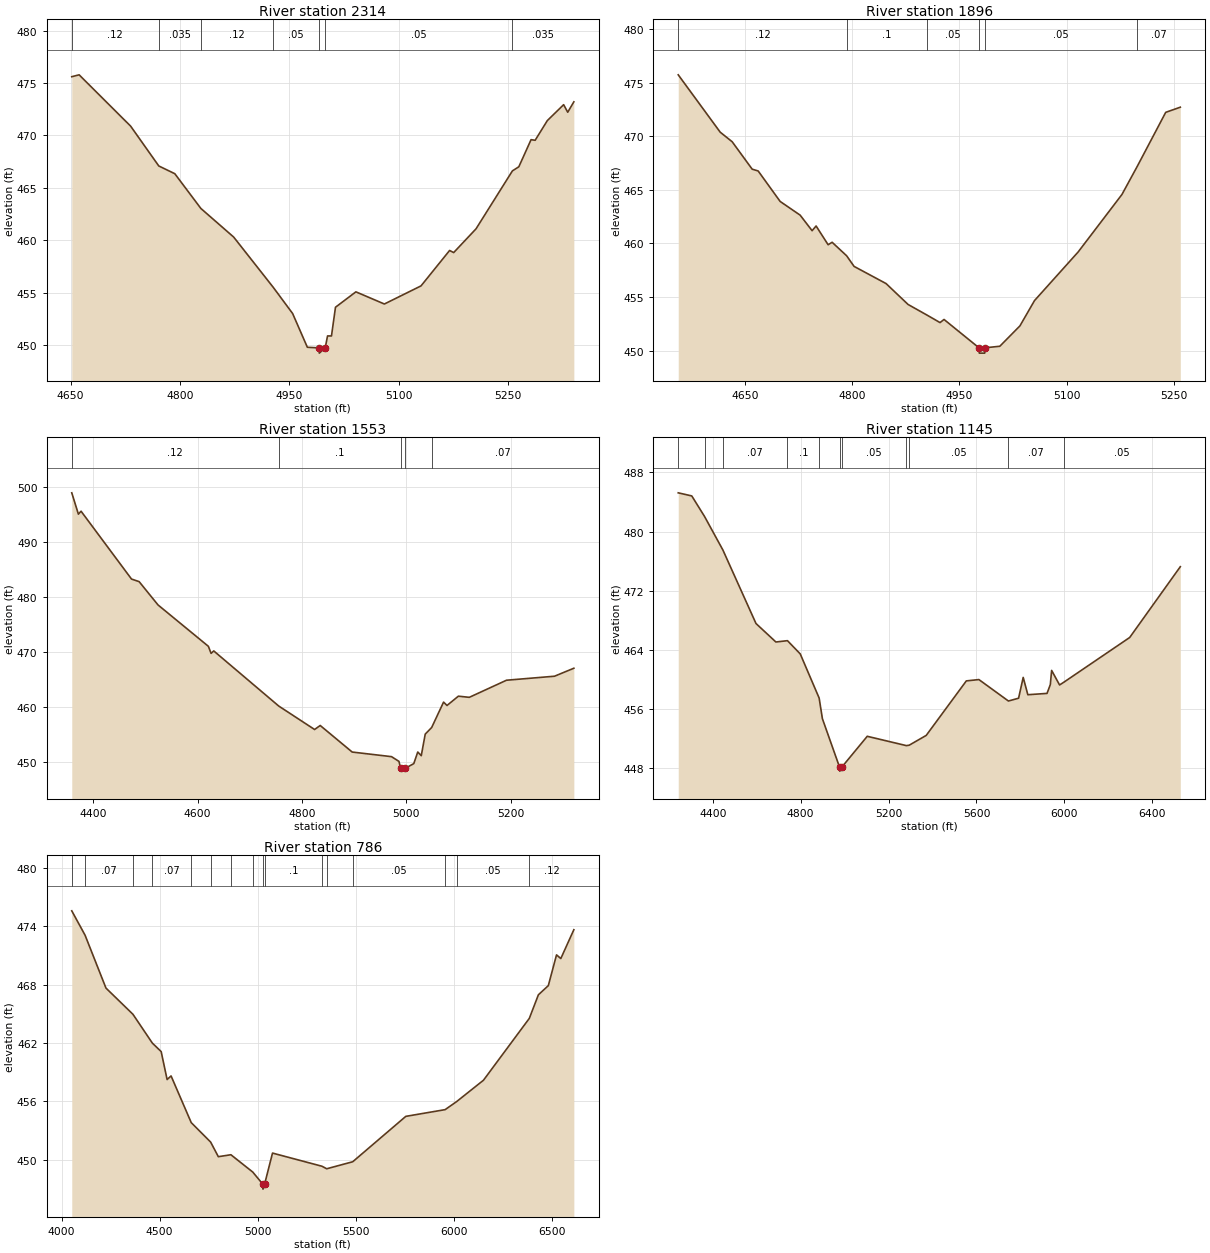
Type RM Length L Ch R = 1 ,2314    ,418,418,418
BEGIN DESCRIPTION:
StreamM059 2.0
END DESCRIPTION:
XS GIS Cut Line= 3
      2501175.01       13861625.        2500825.       13861575.
      2500524.98     13861424.99
#Sta/Elev= 30
  4651.5  475.61  4661.6  475.79  4732.3  470.89  4770.9  467.09  4792.9  466.35
  4828.7  463.03  4873.7   460.3  4927.9  455.51  4954.6     453  4974.8  449.78
  4990.7  449.72  4991.2  449.22  4999.3  449.72  5002.5  450.86  5007.9  450.86
  5013.4   453.6  5041.4  455.07  5080.5  453.91  5130.8  455.64    5170  459.02
  5175.6  458.82  5206.3  461.09  5256.2  466.62    5265  467.01  5281.8   469.6
  5287.4  469.54  5304.1  471.42  5326.5  472.94  5332.1  472.22  5340.5  473.21
#Mann= 7 ,-1 , 0
  4651.5     .12       0  4770.9    .035       0  4828.7     .12       0
  4927.9     .05       0  4990.7     .05       0  4999.3     .05       0
  5256.2    .035       0
Bank Sta=4990.7,4999.3
XS Rating Curve= 0 ,0
Exp/Cntr=0.3,0.1

Type RM Length L Ch R = 1 ,1896    ,343,343,343
BEGIN DESCRIPTION:
StreamM059 1.0
END DESCRIPTION:
XS GIS Cut Line= 3
      2501124.96     13861025.02        2500725.       13861225.
      2500475.02       13861275.
#Sta/Elev= 30
  4556.7  475.72  4615.4  470.37  4632.1  469.48  4660.1  466.92  4668.5  466.75
  4699.2  463.91  4727.2  462.63  4743.9  461.18  4749.5  461.62  4766.3  459.87
  4771.9   460.1  4792.2  458.84  4802.6  457.85  4847.3  456.25  4878.1   454.3
    4904  453.33  4922.8  452.61  4928.4   452.9  4977.2  450.26  4977.7  449.76
  4985.3  449.76  4985.8  450.26  5006.4   450.4  5034.5   452.3  5054.9  454.66
    5116   459.2  5177.2  464.56  5198.5  467.17  5238.4  472.22  5258.8   472.7
#Mann= 6 ,-1 , 0
  4556.7     .12       0  4792.2      .1       0    4904     .05       0
  4977.2     .05       0  4985.8     .05       0  5198.5     .07       0
Bank Sta=4977.2,4985.8
XS Rating Curve= 0 ,0
Exp/Cntr=0.3,0.1

Type RM Length L Ch R = 1 ,1553    ,408,408,408
BEGIN DESCRIPTION:
H21420
END DESCRIPTION:
XS GIS Cut Line= 3
      2501311.43     13860747.29      2500721.64     13860866.06
      2500451.32     13861103.62
#Sta/Elev= 30
  4359.2  498.98  4371.9   495.1    4377  495.64  4473.6   483.3  4488.2  482.83
  4524.4  478.59  4620.8  471.07    4626  469.78  4631.1  470.23  4755.5  460.21
  4824.2  455.94    4835  456.67  4896.2  451.84  4971.6     451  4985.8  450.14
    4989  448.87  4989.5  448.37  4997.7  448.87  5014.2  449.74  5021.8  451.85
  5028.5  451.18  5036.1   455.1  5048.5  456.31  5071.2  460.92  5077.8  460.31
  5099.6     462  5120.5  461.79  5191.7   464.9  5283.7  465.63  5320.7  467.08
#Mann= 5 ,-1 , 0
  4359.2     .12       0  4755.5      .1       0    4989     .05       0
  4997.7      .1       0  5048.5     .07       0
Bank Sta=4989,4997.7
XS Rating Curve= 0 ,0
Exp/Cntr=0.3,0.1

Type RM Length L Ch R = 1 ,1145    ,359,359,359
BEGIN DESCRIPTION:
H21419
END DESCRIPTION:
XS GIS Cut Line= 4
      2501426.16     13860415.51      2500721.64     13860501.52
      2500299.76     13860685.84      2499685.35     13861615.64
#Sta/Elev= 30
  4242.9  485.23  4304.5  484.81  4362.5  482.04  4446.1   477.5  4596.7  467.56
  4687.3  465.06  4739.9  465.24  4798.1  463.45  4884.1  457.48  4898.9  454.69
  4977.4   448.1  4977.9   447.6  4986.1   448.1    5103  452.31  5280.9  451.05
  5294.1  451.11  5371.3  452.43  5553.8   459.8    5611  459.98  5745.4  457.08
  5791.6  457.46  5812.6  460.27  5833.7  457.93    5921  458.11    5936   459.3
    5942  461.22  5978.1  459.25  5998.4  459.64  6297.2  465.67  6527.5  475.24
#Mann= 11 ,-1 , 0
  4242.9     .07       0  4362.5     .12       0  4446.1     .07       0
  4739.9      .1       0  4884.1     .05       0  4977.4     .05       0
  4986.1     .05       0  5280.9      .1       0  5294.1     .05       0
  5745.4     .07       0  5998.4     .05       0
Bank Sta=4977.4,4986.1
XS Rating Curve= 0 ,0
Exp/Cntr=0.3,0.1

Type RM Length L Ch R = 1 ,786     ,0,0,0
BEGIN DESCRIPTION:
H21418
END DESCRIPTION:
XS GIS Cut Line= 4
      2501446.67     13860243.48      2500680.68     13860136.98
      2500291.56     13860329.49      2499517.42     13861439.51
#Sta/Elev= 30
  4052.1  475.57  4119.9  473.07  4226.5  467.64  4364.1  464.95  4463.2  461.99
  4508.1  461.12  4538.4  458.25  4558.6  458.62  4661.4  453.83  4760.4  451.83
  4799.7  450.33  4863.8  450.53  4975.3  448.75  5026.8   447.5  5027.3     447
  5035.5   447.5    5076   450.7  5328.1  449.35  5352.4  449.09  5485.1  449.81
  5755.9  454.47  5956.4  455.16  6015.3  455.99    6152  458.18  6385.8  464.53
  6432.1  466.95  6482.7  467.89  6524.6  471.05  6546.4  470.67  6612.9  473.63
#Mann= 16 ,-1 , 0
  4052.1     .05       0  4119.9     .07       0  4364.1    .035       0
  4463.2     .07       0  4661.4     .05       0  4760.4      .1       0
  4863.8     .05       0  4975.3      .1       0  5026.8     .05       0
  5035.5      .1       0  5328.1     .05       0  5352.4      .1       0
  5485.1     .05       0  5956.4     .07       0  6015.3     .05       0
  6385.8     .12       0
Bank Sta=5026.8,5035.5
XS Rating Curve= 0 ,0
Exp/Cntr=0.3,0.1

Chan Stop Cuts=-1
Use User Specified Reach Order=0
Composite Channel Slope=5