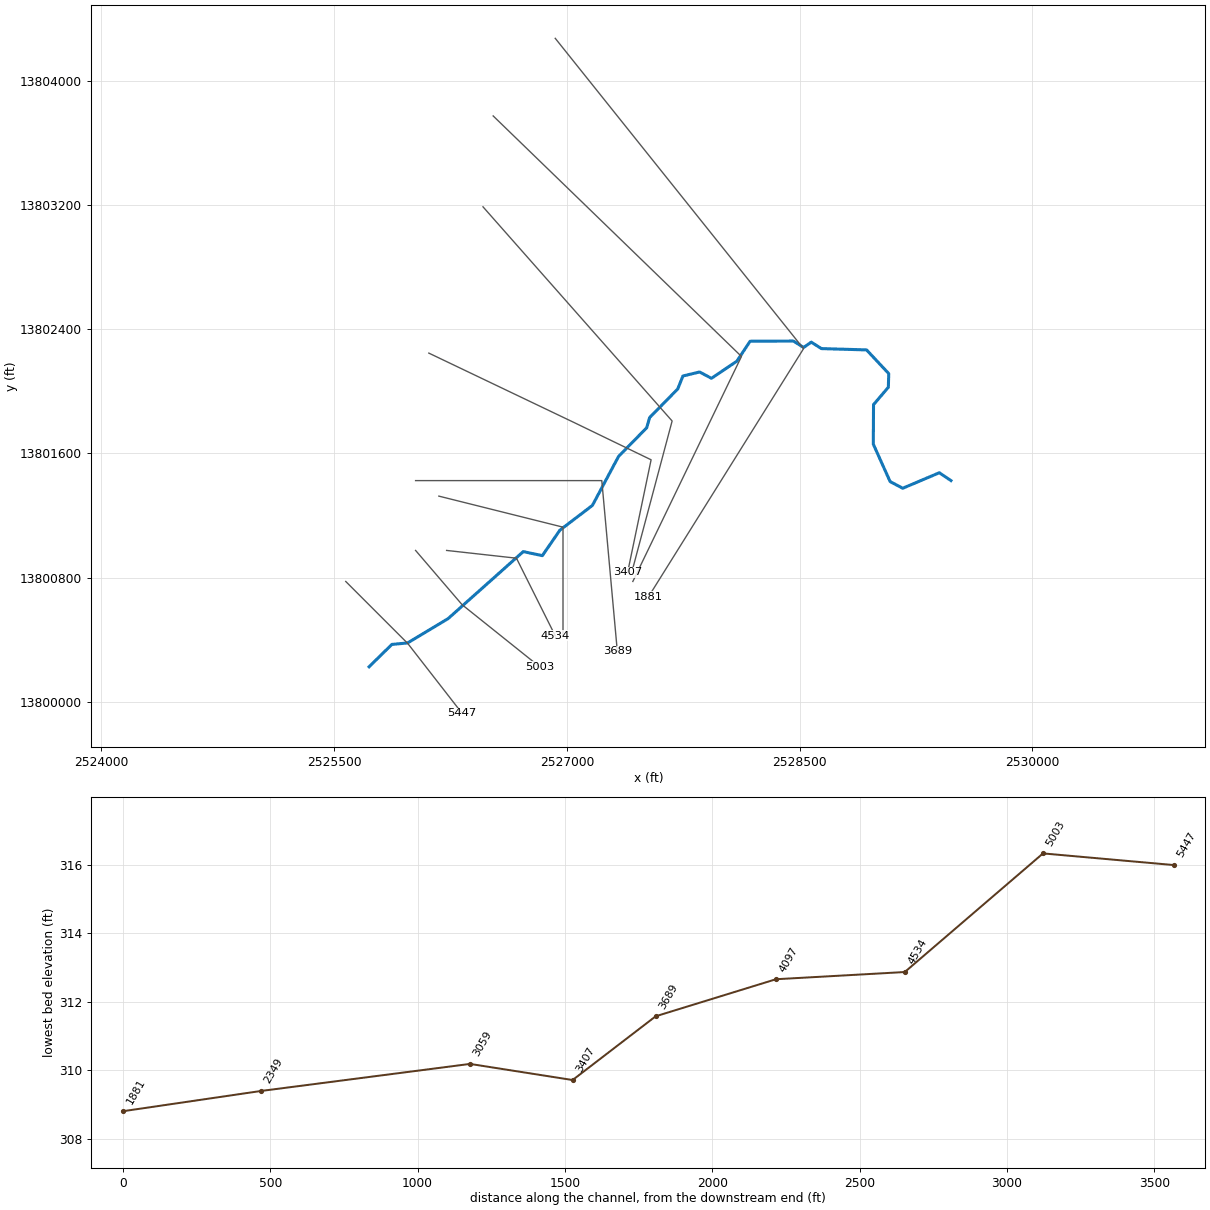
--- StreamM06.prj (project) ---

Proj Title=StreamM06 Base Level Engineering
Current Plan=p01
Default Exp/Contr=0.3,0.1
English Units
Geom File=g01
Flow File=f01
Plan File=p01
BEGIN DESCRIPTION:
StreamM06
END DESCRIPTION:

--- StreamM06.p01 (plan) ---

Plan Title=Multiple Run
Short Identifier=Multiple
Geom File=g01
Flow File=f01
Subcritical Flow
K Sum by GR= 0
Std Step Tol= 0.01
Critical Tol= 0.01
Num of Std Step Trials= 20
Max Error Tol= 0.3
Flow Tol Ratio= 0.001
Split Flow NTrial= 30
Split Flow Tol= 0.02
Split Flow Ratio= 0.02
Log Output Level= 0
Friction Slope Method= 1
Unsteady Friction Slope Method= 2
Unsteady Bridges Friction Slope Method= 1
Parabolic Critical Depth
Global Vel Dist=  1 , 1 , 1
Global Log Level= 0
CheckData=True
Encroach Param= -1, 0, 0, 0
BEGIN DESCRIPTION:
Multiple Run
END DESCRIPTION:

--- StreamM06.f01 (steady flow) ---

Flow Title=Multiple
Number of Profiles=7
Profile Names=10-year,25-year,50-year,1pct_min,100-year,1pct_plu,500-year
River Rch & RM= StreamM06,Reach-1,5447
     796    1283    1724    1120    2235    4460    3721
Boundary for River Rch & Prof#=StreamM06,Reach-1,1
Up Type=0
Dn Type=3
Dn Slope=0.005
Boundary for River Rch & Prof#=StreamM06,Reach-1,2
Up Type=0
Dn Type=3
Dn Slope=0.005
Boundary for River Rch & Prof#=StreamM06,Reach-1,3
Up Type=0
Dn Type=3
Dn Slope=0.005
Boundary for River Rch & Prof#=StreamM06,Reach-1,4
Up Type=0
Dn Type=3
Dn Slope=0.005
Boundary for River Rch & Prof#=StreamM06,Reach-1,5
Up Type=0
Dn Type=3
Dn Slope=0.005
Boundary for River Rch & Prof#=StreamM06,Reach-1,6
Up Type=0
Dn Type=3
Dn Slope=0.005
Boundary for River Rch & Prof#=StreamM06,Reach-1,7
Up Type=0
Dn Type=3
Dn Slope=0.005

--- StreamM06.g01 (geometry) ---

Geom Title=Existing Conditions

River Reach=StreamM06,Reach-1
Reach XY= 30
      2525725.00     13800225.00      2525872.57     13800369.48
      2525973.41     13800378.83      2526234.68     13800535.78
      2526718.95     13800967.50      2526841.74     13800941.29
      2526954.61     13801105.16      2527164.37     13801265.00
      2527333.16     13801581.05      2527514.22     13801765.32
      2527533.16     13801831.05      2527714.21     13802015.34
      2527747.81     13802098.98      2527854.94     13802124.99
      2527931.73     13802084.15      2528095.47     13802194.64
      2528180.67     13802323.02      2528459.84     13802324.35
      2528525.10     13802282.79      2528574.90     13802317.21
      2528640.16     13802275.65      2528931.19     13802267.19
      2529074.07     13802114.52      2529071.53     13802026.50
      2528976.06     13801914.56      2528974.56     13801659.82
      2529083.02     13801418.57      2529164.24     13801375.70
      2529399.95     13801475.61      2529475.00     13801425.00

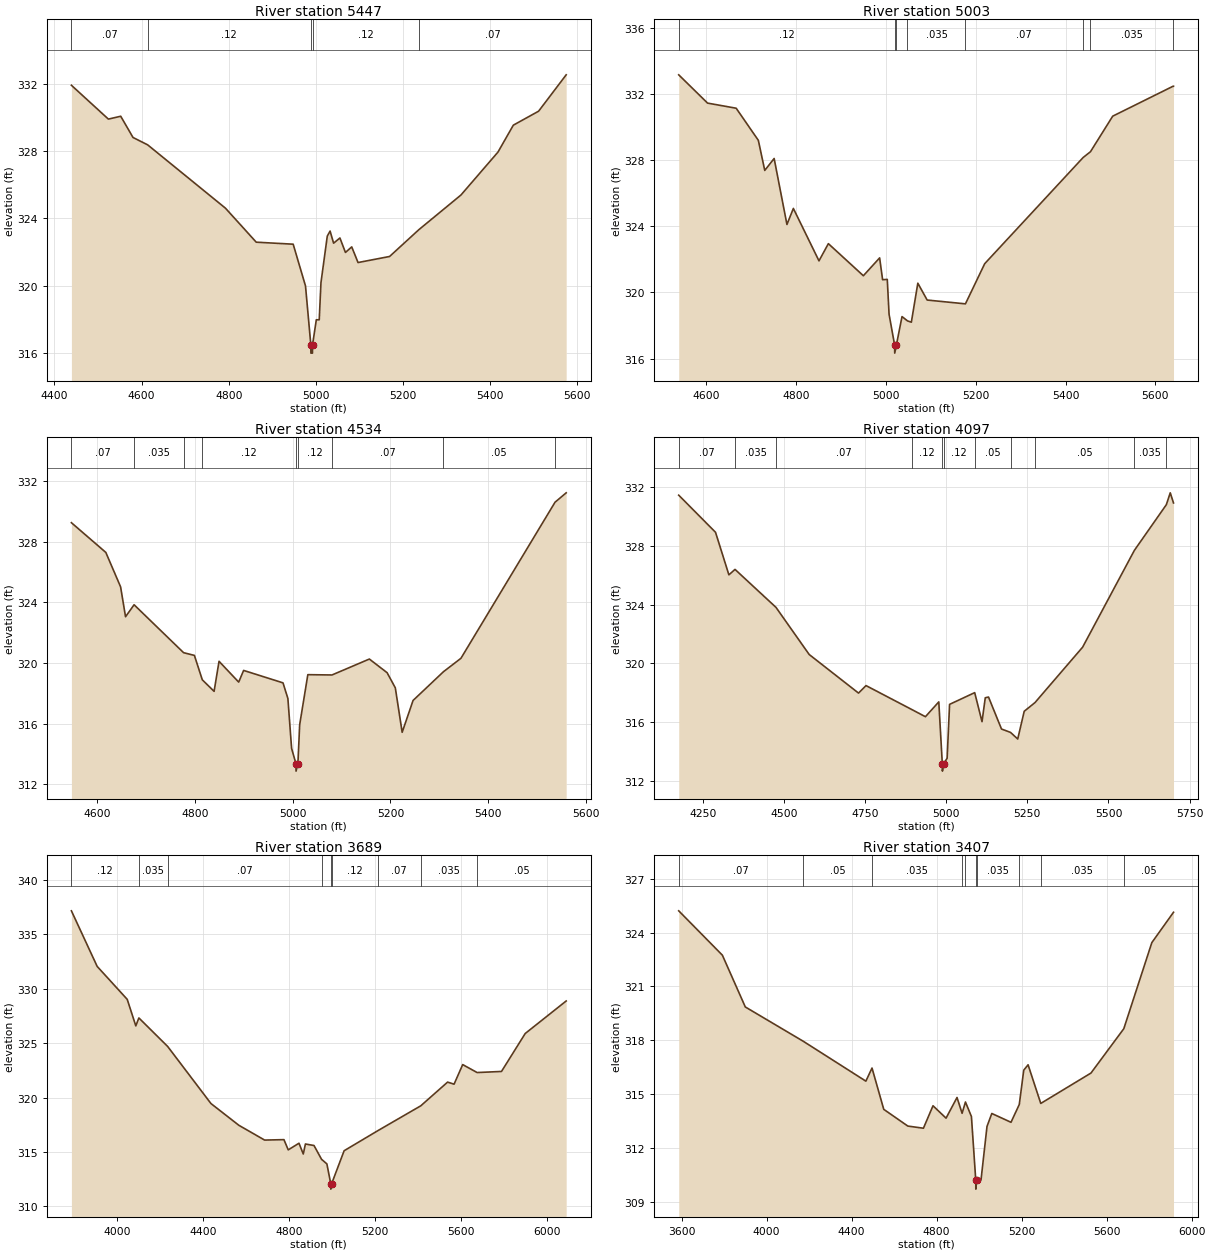
Type RM Length L Ch R = 1,5447,444,444,444
BEGIN DESCRIPTION:
StreamM06 7.0
END DESCRIPTION:
XS GIS Cut Line= 3
      2525574.98     13800775.02      2525975.00     13800375.00
      2526325.00     13799925.00
#Sta/Elev= 30
  4438.9  331.90  4523.8  329.89  4552.1  330.06  4580.3  328.80  4614.0  328.36
  4792.5  324.60  4863.2  322.58  4948.0  322.46  4976.3  319.98  4988.5  316.49
  4988.7  315.99  4992.2  315.99  4992.5  316.49  5001.1  317.97  5007.8  317.97
  5011.8  320.18  5026.3  322.94  5032.7  323.24  5040.8  322.52  5055.3  322.83
  5068.0  321.97  5082.4  322.30  5096.9  321.37  5169.3  321.73  5236.4  323.32
  5333.1  325.38  5418.1  327.93  5453.4  329.53  5511.4  330.36  5574.7  332.52
#Mann=5,-1,0
  4438.9    0.07       0  4614.0    0.12       0  4988.5    0.05       0
  4992.5    0.12       0  5236.4    0.07       0
Bank Sta=4988.5,4992.5
Exp/Cntr=0.3,0.1

Type RM Length L Ch R = 1,5003,469,469,469
BEGIN DESCRIPTION:
StreamM06 6.0
END DESCRIPTION:
XS GIS Cut Line= 3
      2526025.01     13800974.99      2526325.00     13800625.00
      2526825.02     13800224.98
#Sta/Elev= 30
  4539.0  333.16  4603.2  331.45  4666.9  331.14  4716.2  329.20  4730.5  327.38
  4751.4  328.10  4779.9  324.11  4794.2  325.08  4851.2  321.91  4872.1  322.95
  4950.0  321.01  4986.2  322.09  4992.8  320.77  5003.2  320.79  5007.2  318.68
  5019.5  316.83  5019.8  316.33  5023.6  316.83  5036.0  318.54  5048.2  318.28
  5056.8  318.20  5071.2  320.56  5092.0  319.54  5177.2  319.31  5220.1  321.74
  5439.2  328.16  5455.5  328.51  5505.0  330.66  5639.4  332.47  5640.3  332.47
#Mann=8,-1,0
  4539.0    0.12       0  5019.5    0.05       0  5023.6    0.12       0
  5048.2   0.035       0  5177.2    0.07       0  5439.2    0.05       0
  5455.5   0.035       0  5639.4    0.07       0
Bank Sta=5019.5,5023.6
Exp/Cntr=0.3,0.1

Type RM Length L Ch R = 1,4534,437,437,437
BEGIN DESCRIPTION:
StreamM06 5.0
END DESCRIPTION:
XS GIS Cut Line= 3
      2526224.99     13800975.00      2526675.00     13800925.00
      2526925.00     13800424.99
#Sta/Elev= 30
  4547.6  329.25  4618.0  327.29  4648.2  325.02  4658.3  323.05  4675.8  323.84
  4777.0  320.68  4799.1  320.50  4815.3  318.89  4839.4  318.13  4849.5  320.11
  4889.7  318.74  4899.8  319.51  4980.3  318.69  4990.3  317.66  4997.9  314.37
  5006.7  313.37  5007.0  312.87  5010.8  313.37  5014.4  315.93  5031.1  319.23
  5080.5  319.21  5156.9  320.26  5193.2  319.36  5210.0  318.36  5224.0  315.43
  5246.3  317.53  5308.3  319.42  5344.2  320.31  5536.6  330.60  5559.4  331.22
#Mann=9,-1,0
  4547.6    0.07       0  4675.8   0.035       0  4777.0    0.07       0
  4815.3    0.12       0  5006.7    0.05       0  5010.8    0.12       0
  5080.5    0.07       0  5308.3    0.05       0  5536.6   0.035       0
Bank Sta=5006.7,5010.8
Exp/Cntr=0.3,0.1

Type RM Length L Ch R = 1,4097,408,408,408
BEGIN DESCRIPTION:
StreamM06 4.0
END DESCRIPTION:
XS GIS Cut Line= 3
      2526175.02     13801325.00      2526975.00     13801125.00
      2526975.00     13800425.00
#Sta/Elev= 30
  4175.7  331.47  4289.1  328.94  4330.3  326.04  4349.2  326.41  4475.5  323.82
  4577.7  320.61  4729.7  317.98  4752.9  318.49  4895.5  316.84  4935.9  316.37
  4977.1  317.38  4987.9  313.16  4988.2  312.66  4992.1  313.16  5002.8  313.54
  5010.3  317.21  5087.7  318.01  5110.3  316.03  5120.3  317.66  5130.3  317.71
  5170.3  315.53  5198.1  315.30  5220.3  314.85  5240.3  316.74  5273.4  317.33
  5420.3  321.11  5579.8  327.71  5678.2  330.82  5690.3  331.63  5700.3  330.94
#Mann=11,-1,0
  4175.7    0.07       0  4349.2   0.035       0  4475.5    0.07       0
  4895.5    0.12       0  4987.9    0.05       0  4992.1    0.12       0
  5087.7    0.05       0  5198.1    0.07       0  5273.4    0.05       0
  5579.8   0.035       0  5678.2    0.05       0
Bank Sta=4987.9,4992.1
Exp/Cntr=0.3,0.1

Type RM Length L Ch R = 1,3689,282,282,282
BEGIN DESCRIPTION:
StreamM06 3.0
END DESCRIPTION:
XS GIS Cut Line= 3
      2526024.98     13801425.00      2527225.00     13801425.00
      2527325.00     13800324.96
#Sta/Elev= 30
  3787.0  337.17  3907.0  332.06  4047.0  329.03  4087.0  326.59  4101.3  327.32
  4235.3  324.70  4437.0  319.45  4567.0  317.45  4687.0  316.09  4777.0  316.13
  4797.0  315.19  4847.0  315.80  4867.0  314.81  4877.0  315.73  4917.0  315.59
  4952.2  314.32  4977.0  313.90  4995.0  312.08  4995.2  311.58  4999.2  312.08
  5057.3  315.11  5213.9  316.95  5414.3  319.24  5539.3  321.42  5569.4  321.23
  5609.6  323.03  5676.8  322.30  5790.3  322.40  5900.8  325.89  6091.6  328.88
#Mann=9,-1,0
  3787.0    0.12       0  4101.3   0.035       0  4235.3    0.07       0
  4952.2    0.12       0  4995.0    0.05       0  4999.2    0.12       0
  5213.9    0.07       0  5414.3   0.035       0  5676.8    0.05       0
Bank Sta=4995,4999.2
Exp/Cntr=0.3,0.1

Type RM Length L Ch R = 1,3407,348,348,348
BEGIN DESCRIPTION:
H21436
END DESCRIPTION:
XS GIS Cut Line= 4
      2526110.43     13802246.60      2527058.33     13801793.49
      2527542.71     13801559.11      2527391.66     13800835.13
#Sta/Elev= 30
  3586.3  325.21  3791.8  322.74  3899.6  319.86  4172.3  317.95  4467.0  315.73
  4495.9  316.46  4551.2  314.16  4664.4  313.23  4737.8  313.11  4782.9  314.36
  4844.3  313.67  4895.9  314.82  4919.8  313.94  4935.6  314.57  4963.7  313.76
  4984.1  310.22  4984.4  309.72  4988.3  310.22  5008.8  310.23  5037.0  313.21
  5059.6  313.93  5149.9  313.44  5188.9  314.43  5209.9  316.34  5230.3  316.64
  5290.0  314.49  5526.2  316.18  5680.8  318.65  5812.6  323.44  5914.6  325.13
#Mann=10,-1,0
  3586.3    0.07       0  4172.3    0.05       0  4495.9   0.035       0
  4919.8   0.063       0  4935.6   0.035       0  4984.1   0.035       0
  4988.3   0.035       0  5188.9   0.063       0  5290.0   0.035       0
  5680.8    0.05       0
Bank Sta=4984.1,4988.3
Exp/Cntr=0.3,0.1

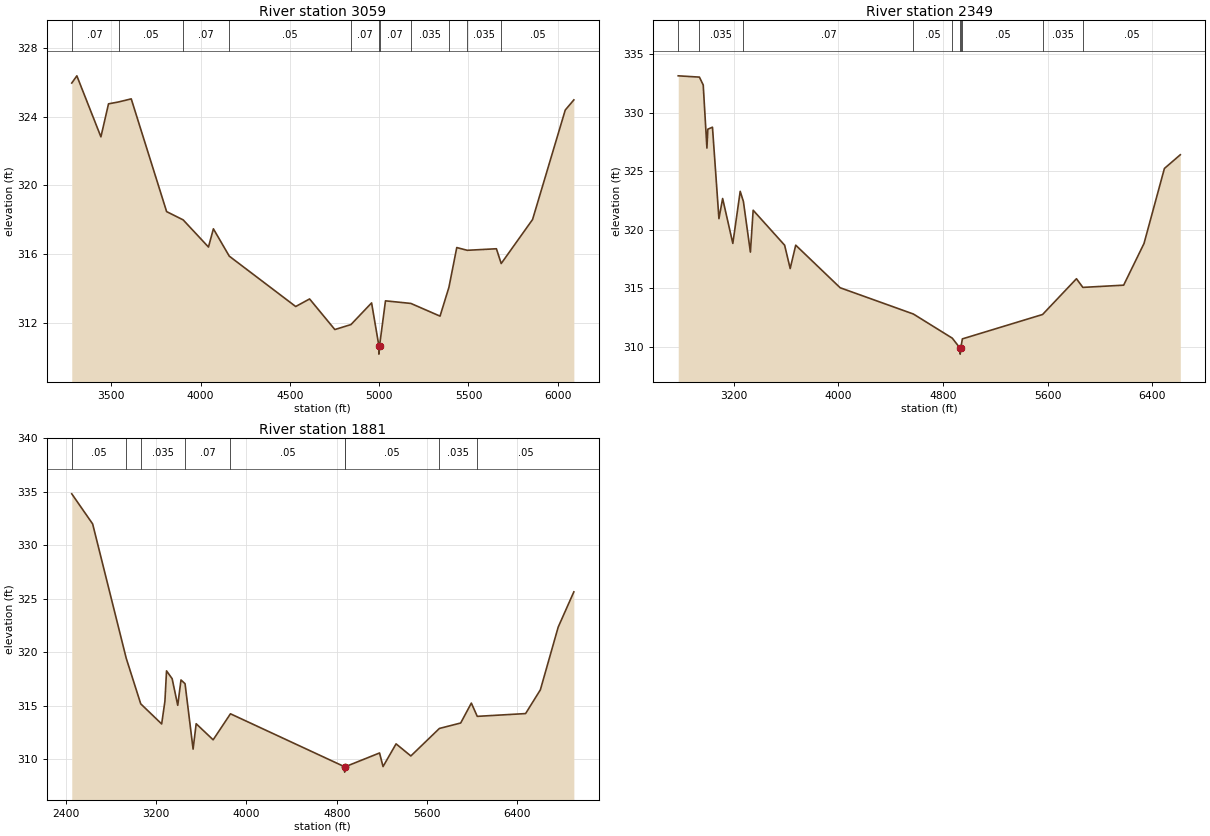
Type RM Length L Ch R = 1,3059,710,710,710
BEGIN DESCRIPTION:
H21435
END DESCRIPTION:
XS GIS Cut Line= 3
      2526459.36     13803189.33      2527678.13     13801809.11
      2527428.12     13800871.58
#Sta/Elev= 30
  3278.5  325.96  3307.0  326.38  3441.7  322.83  3484.3  324.75  3540.6  324.86
  3611.5  325.04  3809.7  318.48  3902.3  318.00  4044.0  316.42  4071.6  317.48
  4160.5  315.89  4532.5  312.96  4610.3  313.40  4751.8  311.62  4842.0  311.91
  4957.5  313.17  4998.1  310.69  4998.3  310.19  5002.3  310.69  5035.3  313.29
  5177.4  313.14  5340.8  312.40  5390.6  314.08  5434.5  316.39  5493.2  316.23
  5656.5  316.32  5683.3  315.46  5858.9  318.02  6042.0  324.39  6090.1  324.98
#Mann=11,-1,0
  3278.5    0.07       0  3540.6    0.05       0  3902.3    0.07       0
  4160.5    0.05       0  4842.0    0.07       0  4998.1    0.05       0
  5002.3    0.07       0  5177.4   0.035       0  5390.6   0.063       0
  5493.2   0.035       0  5683.3    0.05       0
Bank Sta=4998.1,5002.3
Exp/Cntr=0.3,0.1

Type RM Length L Ch R = 1,2349,468,468,468
BEGIN DESCRIPTION:
StreamM06 2.0
END DESCRIPTION:
XS GIS Cut Line= 3
      2526525.02     13803774.98      2528125.00     13802225.00
      2527424.99     13800774.97
#Sta/Elev= 30
  2777.0  333.13  2939.0  333.02  2968.0  332.35  2996.3  326.97  3003.2  328.58
  3038.7  328.75  3088.1  320.95  3116.4  322.67  3194.3  318.84  3250.7  323.28
  3275.1  322.42  3328.6  318.10  3349.7  321.67  3590.2  318.69  3632.7  316.70
  3675.1  318.69  4014.7  315.06  4574.4  312.82  4871.9  310.76  4931.8  309.90
  4932.1  309.40  4936.3  309.90  4948.9  310.70  5562.1  312.78  5821.0  315.83
  5869.8  315.09  6181.7  315.28  6337.2  318.83  6493.2  325.23  6614.8  326.40
#Mann=10,-1,0
  2777.0    0.05       0  2939.0   0.035       0  3275.1    0.07       0
  4574.4    0.05       0  4871.9    0.07       0  4931.8    0.05       0
  4936.3    0.07       0  4948.9    0.05       0  5562.1   0.035       0
  5869.8    0.05       0
Bank Sta=4931.8,4936.3
Exp/Cntr=0.3,0.1

Type RM Length L Ch R = 1,1881,0,0,0
BEGIN DESCRIPTION:
StreamM06 1.0
END DESCRIPTION:
XS GIS Cut Line= 3
      2526925.00     13804275.00      2528525.00     13802275.00
      2527524.97     13800674.96
#Sta/Elev= 30
  2452.8  334.81  2637.7  332.00  2934.9  319.46  3063.8  315.19  3249.2  313.31
  3278.0  315.43  3292.4  318.27  3342.0  317.54  3391.7  315.05  3420.5  317.42
  3456.4  317.07  3527.7  310.96  3554.9  313.33  3705.4  311.83  3858.6  314.26
  4870.1  309.31  4870.4  308.81  4874.7  309.31  5179.7  310.60  5210.4  309.33
  5326.0  311.45  5456.9  310.32  5709.7  312.89  5898.5  313.40  5992.8  315.26
  6045.3  314.02  6473.4  314.28  6604.3  316.50  6762.3  322.36  6900.9  325.65
#Mann=9,-1,0
  2452.8    0.05       0  2934.9    0.07       0  3063.8   0.035       0
  3456.4    0.07       0  3858.6    0.05       0  4870.1    0.05       0
  4874.7    0.05       0  5709.7   0.035       0  6045.3    0.05       0
Bank Sta=4870.1,4874.7
Exp/Cntr=0.3,0.1

Chan Stop Cuts=-1