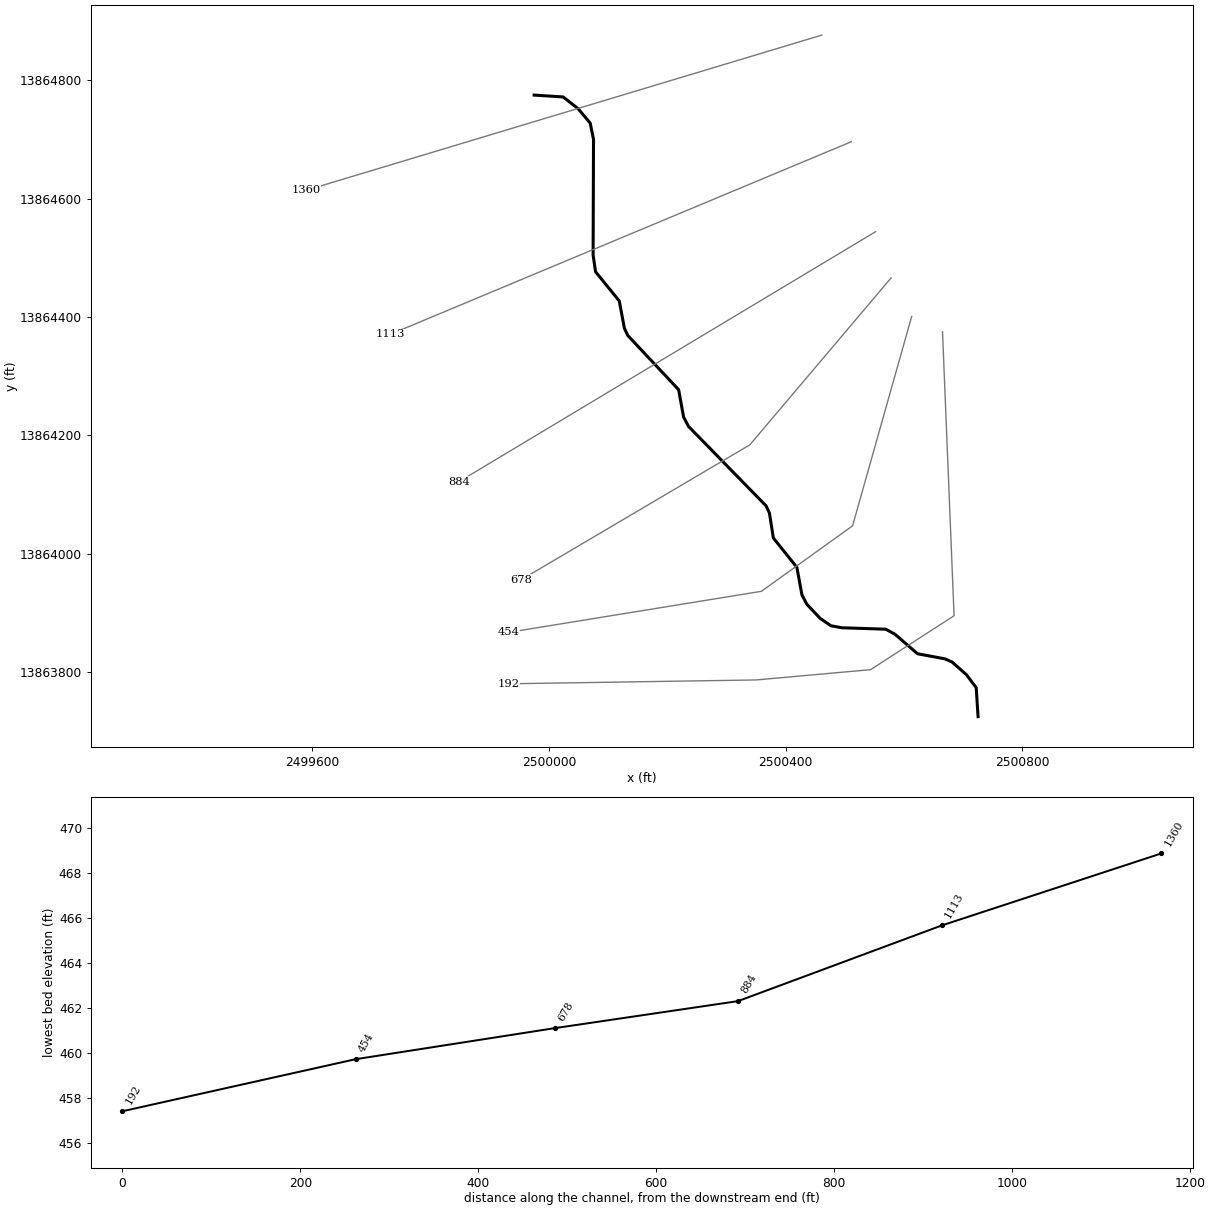
--- StreamM060.prj (project) ---

Proj Title=StreamM060 Base Level Engineering
Current Plan=p01
Default Exp/Contr=0.3,0.1
English Units
Geom File=g01
Flow File=f01
Plan File=p01
BEGIN DESCRIPTION:
StreamM060
END DESCRIPTION:

--- StreamM060.p01 (plan) ---

Plan Title=Multiple Run
Short Identifier=Multiple
Geom File=g01
Flow File=f01
Subcritical Flow
K Sum by GR= 0
Std Step Tol= 0.01
Critical Tol= 0.01
Num of Std Step Trials= 20
Max Error Tol= 0.3
Flow Tol Ratio= 0.001
Split Flow NTrial= 30
Split Flow Tol= 0.02
Split Flow Ratio= 0.02
Log Output Level= 0
Friction Slope Method= 1
Unsteady Friction Slope Method= 2
Unsteady Bridges Friction Slope Method= 1
Parabolic Critical Depth
Global Vel Dist=  1 , 1 , 1
Global Log Level= 0
CheckData=True
Encroach Param= -1, 0, 0, 0
BEGIN DESCRIPTION:
Multiple Run
END DESCRIPTION:

--- StreamM060.f01 (steady flow) ---

Flow Title=Multiple
Number of Profiles=7
Profile Names=10-year,25-year,50-year,1pct_min,100-year,1pct_plu,500-year
River Rch & RM= StreamM060,Reach-1,1360
     308     472     614     389     776    1548    1220
Boundary for River Rch & Prof#=StreamM060,Reach-1,1
Up Type=0
Dn Type=3
Dn Slope=0.005
Boundary for River Rch & Prof#=StreamM060,Reach-1,2
Up Type=0
Dn Type=3
Dn Slope=0.005
Boundary for River Rch & Prof#=StreamM060,Reach-1,3
Up Type=0
Dn Type=3
Dn Slope=0.005
Boundary for River Rch & Prof#=StreamM060,Reach-1,4
Up Type=0
Dn Type=3
Dn Slope=0.005
Boundary for River Rch & Prof#=StreamM060,Reach-1,5
Up Type=0
Dn Type=3
Dn Slope=0.005
Boundary for River Rch & Prof#=StreamM060,Reach-1,6
Up Type=0
Dn Type=3
Dn Slope=0.005
Boundary for River Rch & Prof#=StreamM060,Reach-1,7
Up Type=0
Dn Type=3
Dn Slope=0.005

--- StreamM060.g01 (geometry) ---

Geom Title=Existing Conditions

River Reach=StreamM060,Reach-1
Reach XY= 30
      2499975.00     13864775.00      2500024.02     13864771.88
      2500049.15     13864752.25      2500069.74     13864727.69
      2500075.33     13864700.19      2500074.64     13864504.85
      2500078.75     13864476.55      2500118.86     13864427.17
      2500127.50     13864381.04      2500133.16     13864368.95
      2500219.13     13864277.28      2500227.53     13864231.05
      2500235.78     13864215.32      2500366.86     13864081.06
      2500372.50     13864068.96      2500379.19     13864026.73
      2500418.89     13863977.16      2500427.41     13863930.83
      2500435.61     13863914.94      2500457.87     13863891.30
      2500476.28     13863878.52      2500494.95     13863875.08
      2500569.03     13863872.67      2500584.65     13863864.17
      2500622.84     13863831.13      2500669.11     13863822.59
      2500681.31     13863817.05      2500705.45     13863795.64
      2500721.86     13863773.97      2500725.00     13863725.00

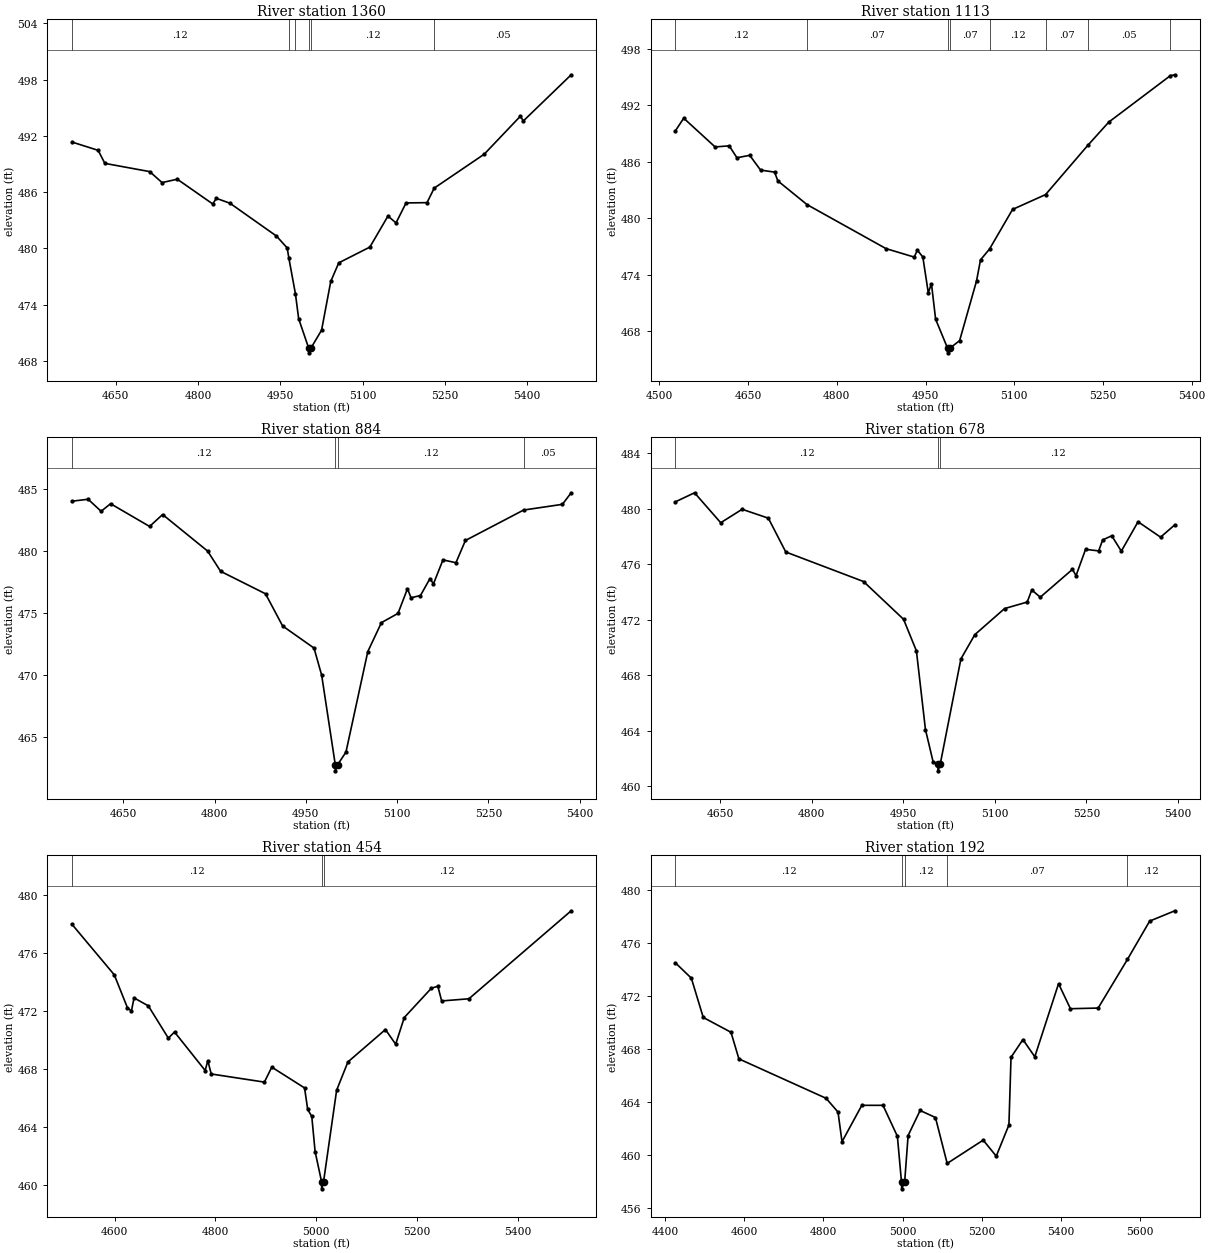
Type RM Length L Ch R = 1,1360,247,247,247
BEGIN DESCRIPTION:
H21442
END DESCRIPTION:
XS GIS Cut Line= 2
      2500460.96     13864876.36      2499589.29     13864613.99
#Sta/Elev= 30
  4569.8  491.36  4617.8  490.47  4630.0  489.08  4711.8  488.20  4734.3  487.03
  4762.1  487.39  4826.7  484.75  4833.3  485.35  4858.0  484.83  4942.8  481.33
  4962.4  480.06  4965.4  478.99  4977.5  475.14  4983.3  472.51  5001.6  469.37
  5001.8  468.87  5005.6  469.37  5025.1  471.29  5041.8  476.48  5056.4  478.47
  5113.1  480.15  5146.1  483.46  5160.8  482.73  5179.1  484.86  5217.3  484.89
  5230.4  486.44  5321.6  490.06  5387.6  494.12  5392.8  493.60  5480.1  498.53
#Mann=6,-1,0
  4569.8    0.12       0  4965.4    0.07       0  4977.5    0.12       0
  5001.6    0.05       0  5005.6    0.12       0  5230.4    0.05       0
Bank Sta=5001.6,5005.6
Exp/Cntr=0.3,0.1

Type RM Length L Ch R = 1,1113,229,229,229
BEGIN DESCRIPTION:
H21441
END DESCRIPTION:
XS GIS Cut Line= 2
      2500510.84     13864696.22      2499731.81     13864370.72
#Sta/Elev= 30
  4527.2  489.31  4541.1  490.64  4594.2  487.58  4618.0  487.70  4631.1  486.43
  4652.7  486.69  4671.0  485.12  4694.8  484.90  4700.2  483.97  4749.7  481.44
  4883.2  476.76  4930.8  475.86  4936.2  476.59  4945.4  475.87  4954.6  472.07
  4960.0  473.02  4967.0  469.25  4987.2  466.17  4987.5  465.67  4991.2  466.17
  5007.6  466.97  5036.2  473.32  5042.9  475.56  5058.2  476.72  5097.1  480.93
  5152.9  482.51  5224.2  487.74  5259.7  490.22  5364.0  495.17  5371.5  495.26
#Mann=8,-1,0
  4527.2    0.12       0  4749.7    0.07       0  4987.2    0.05       0
  4991.2    0.07       0  5058.2    0.12       0  5152.9    0.07       0
  5224.2    0.05       0  5364.0   0.035       0
Bank Sta=4987.2,4991.2
Exp/Cntr=0.3,0.1

Type RM Length L Ch R = 1,884,206,206,206
BEGIN DESCRIPTION:
H21440
END DESCRIPTION:
XS GIS Cut Line= 2
      2500552.06     13864544.31      2499848.40     13864122.11
#Sta/Elev= 30
  4565.4  484.01  4592.2  484.17  4613.5  483.20  4629.1  483.81  4693.2  481.98
  4714.6  482.94  4788.5  480.00  4809.9  478.37  4883.7  476.56  4911.8  473.97
  4963.4  472.19  4976.0  470.00  4998.3  462.81  4998.6  462.31  5002.3  462.81
  5015.9  463.82  5051.8  471.91  5074.2  474.24  5101.4  474.98  5117.0  476.97
  5122.8  476.24  5138.3  476.42  5153.9  477.78  5159.7  477.36  5175.3  479.29
  5196.6  479.06  5212.2  480.85  5307.8  483.30  5371.6  483.76  5386.0  484.69
#Mann=4,-1,0
  4565.4    0.12       0  4998.3    0.05       0  5002.3    0.12       0
  5307.8    0.05       0
Bank Sta=4998.3,5002.3
Exp/Cntr=0.3,0.1

Type RM Length L Ch R = 1,678,224,224,224
BEGIN DESCRIPTION:
H21439
END DESCRIPTION:
XS GIS Cut Line= 3
      2500578.14     13864466.21      2500339.42     13864184.08
      2499953.10     13863956.20
#Sta/Elev= 30
  4576.7  480.51  4607.9  481.16  4650.8  479.00  4685.9  479.97  4728.8  479.33
  4757.4  476.89  4884.8  474.76  4950.3  472.04  4971.4  469.76  4986.2  464.09
  4998.7  461.77  5006.5  461.61  5006.8  461.11  5010.5  461.61  5044.3  469.18
  5067.1  470.93  5115.8  472.81  5152.9  473.28  5160.4  474.15  5174.3  473.63
  5227.1  475.64  5232.9  475.18  5248.5  477.08  5270.0  476.97  5276.5  477.76
  5291.4  478.06  5307.1  476.95  5334.5  479.07  5371.4  477.96  5394.8  478.85
#Mann=3,-1,0
  4576.7    0.12       0  5006.5    0.05       0  5010.5    0.12       0
Bank Sta=5006.5,5010.5
Exp/Cntr=0.3,0.1

Type RM Length L Ch R = 1,454,262,262,262
BEGIN DESCRIPTION:
H21438
END DESCRIPTION:
XS GIS Cut Line= 4
      2500612.85     13864401.07      2500513.03     13864047.36
      2500358.95     13863936.68      2499931.38     13863867.23
#Sta/Elev= 30
  4515.2  477.96  4599.4  474.47  4625.4  472.21  4633.4  471.97  4638.6  472.88
  4667.0  472.33  4706.6  470.11  4718.9  470.53  4779.7  467.88  4784.9  468.56
  4791.7  467.64  4897.1  467.08  4911.8  468.11  4976.8  466.68  4983.0  465.20
  4991.1  464.72  4997.7  462.30  5010.5  460.23  5010.7  459.73  5014.5  460.23
  5040.4  466.52  5062.8  468.47  5137.2  470.70  5157.5  469.69  5174.6  471.53
  5228.4  473.55  5241.2  473.68  5248.7  472.67  5302.8  472.82  5505.6  478.88
#Mann=3,-1,0
  4515.2    0.12       0  5010.5    0.05       0  5014.5    0.12       0
Bank Sta=5010.5,5014.5
Exp/Cntr=0.3,0.1

Type RM Length L Ch R = 1,192,0,0,0
BEGIN DESCRIPTION:
H21437
END DESCRIPTION:
XS GIS Cut Line= 5
      2500664.94     13864375.01      2500684.47     13863895.45
      2500543.41     13863804.31      2500350.27     13863786.94
      2499931.44     13863780.43
#Sta/Elev= 30
  4426.4  474.49  4466.4  473.34  4496.5  470.37  4566.5  469.25  4586.5  467.24
  4806.7  464.26  4836.7  463.22  4846.8  460.98  4896.8  463.73  4950.3  463.73
  4986.6  461.39  4997.0  457.92  4997.5  457.42  5004.9  457.92  5013.7  461.45
  5044.0  463.34  5082.7  462.81  5112.3  459.34  5203.2  461.10  5236.2  459.89
  5268.2  462.25  5273.5  467.36  5303.5  468.70  5333.5  467.40  5393.5  472.92
  5423.5  471.03  5493.5  471.08  5567.5  474.76  5623.5  477.65  5687.1  478.43
#Mann=5,-1,0
  4426.4    0.12       0  4997.0    0.05       0  5004.9    0.12       0
  5112.3    0.07       0  5567.5    0.12       0
Bank Sta=4997,5004.9
Exp/Cntr=0.3,0.1

Chan Stop Cuts=-1