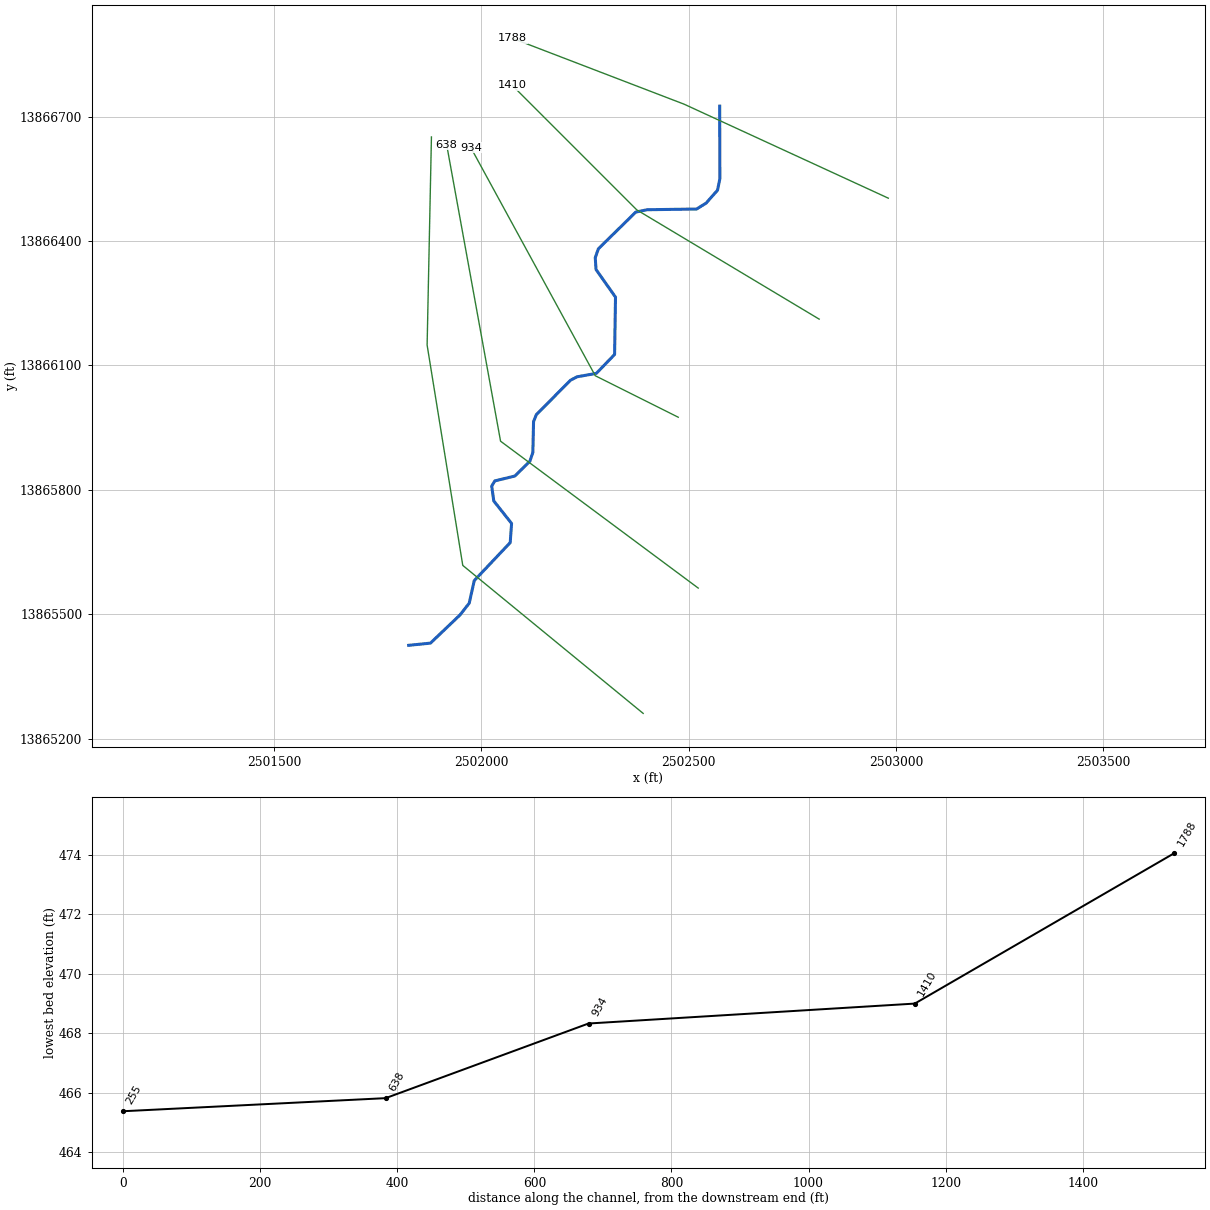
--- StreamM061.prj (project) ---

Proj Title=StreamM061 Base Level Engineering
Current Plan=p01
Default Exp/Contr=0.3,0.1
English Units
Geom File=g01
Flow File=f01
Plan File=p01
BEGIN DESCRIPTION:
StreamM061
END DESCRIPTION:

--- StreamM061.p01 (plan) ---

Plan Title=Multiple Run
Short Identifier=Multiple
Geom File=g01
Flow File=f01
Subcritical Flow
K Sum by GR= 0
Std Step Tol= 0.01
Critical Tol= 0.01
Num of Std Step Trials= 20
Max Error Tol= 0.3
Flow Tol Ratio= 0.001
Split Flow NTrial= 30
Split Flow Tol= 0.02
Split Flow Ratio= 0.02
Log Output Level= 0
Friction Slope Method= 1
Unsteady Friction Slope Method= 2
Unsteady Bridges Friction Slope Method= 1
Parabolic Critical Depth
Global Vel Dist=  1 , 1 , 1
Global Log Level= 0
CheckData=True
Encroach Param= -1, 0, 0, 0
BEGIN DESCRIPTION:
Multiple Run
END DESCRIPTION:

--- StreamM061.f01 (steady flow) ---

Flow Title=Multiple
Number of Profiles=7
Profile Names=10-year,25-year,50-year,1pct_min,100-year,1pct_plu,500-year
River Rch & RM= StreamM061,Reach-1,1788
     557     888    1184     767    1530    3053    2525
Boundary for River Rch & Prof#=StreamM061,Reach-1,1
Up Type=0
Dn Type=3
Dn Slope=0.005
Boundary for River Rch & Prof#=StreamM061,Reach-1,2
Up Type=0
Dn Type=3
Dn Slope=0.005
Boundary for River Rch & Prof#=StreamM061,Reach-1,3
Up Type=0
Dn Type=3
Dn Slope=0.005
Boundary for River Rch & Prof#=StreamM061,Reach-1,4
Up Type=0
Dn Type=3
Dn Slope=0.005
Boundary for River Rch & Prof#=StreamM061,Reach-1,5
Up Type=0
Dn Type=3
Dn Slope=0.005
Boundary for River Rch & Prof#=StreamM061,Reach-1,6
Up Type=0
Dn Type=3
Dn Slope=0.005
Boundary for River Rch & Prof#=StreamM061,Reach-1,7
Up Type=0
Dn Type=3
Dn Slope=0.005

--- StreamM061.g01 (geometry) ---

Geom Title=Existing Conditions

River Reach=StreamM061,Reach-1
Reach XY= 30
      2502575.00     13866725.00      2502575.35     13866549.78
      2502569.66     13866522.26      2502542.23     13866491.24
      2502519.35     13866476.98      2502399.89     13866475.27
      2502372.53     13866469.54      2502282.47     13866381.08
      2502274.95     13866359.67      2502276.78     13866331.14
      2502323.77     13866264.50      2502321.56     13866126.25
      2502277.57     13866080.74      2502231.08     13866072.45
      2502215.32     13866064.22      2502132.86     13865981.19
      2502126.17     13865964.52      2502124.51     13865890.10
      2502117.20     13865868.56      2502080.97     13865833.15
      2502032.78     13865821.44      2502025.25     13865808.98
      2502030.25     13865773.14      2502073.18     13865718.90
      2502069.89     13865672.71      2501983.18     13865581.04
      2501971.03     13865526.64      2501948.74     13865498.13
      2501877.54     13865430.30      2501825.00     13865425.00

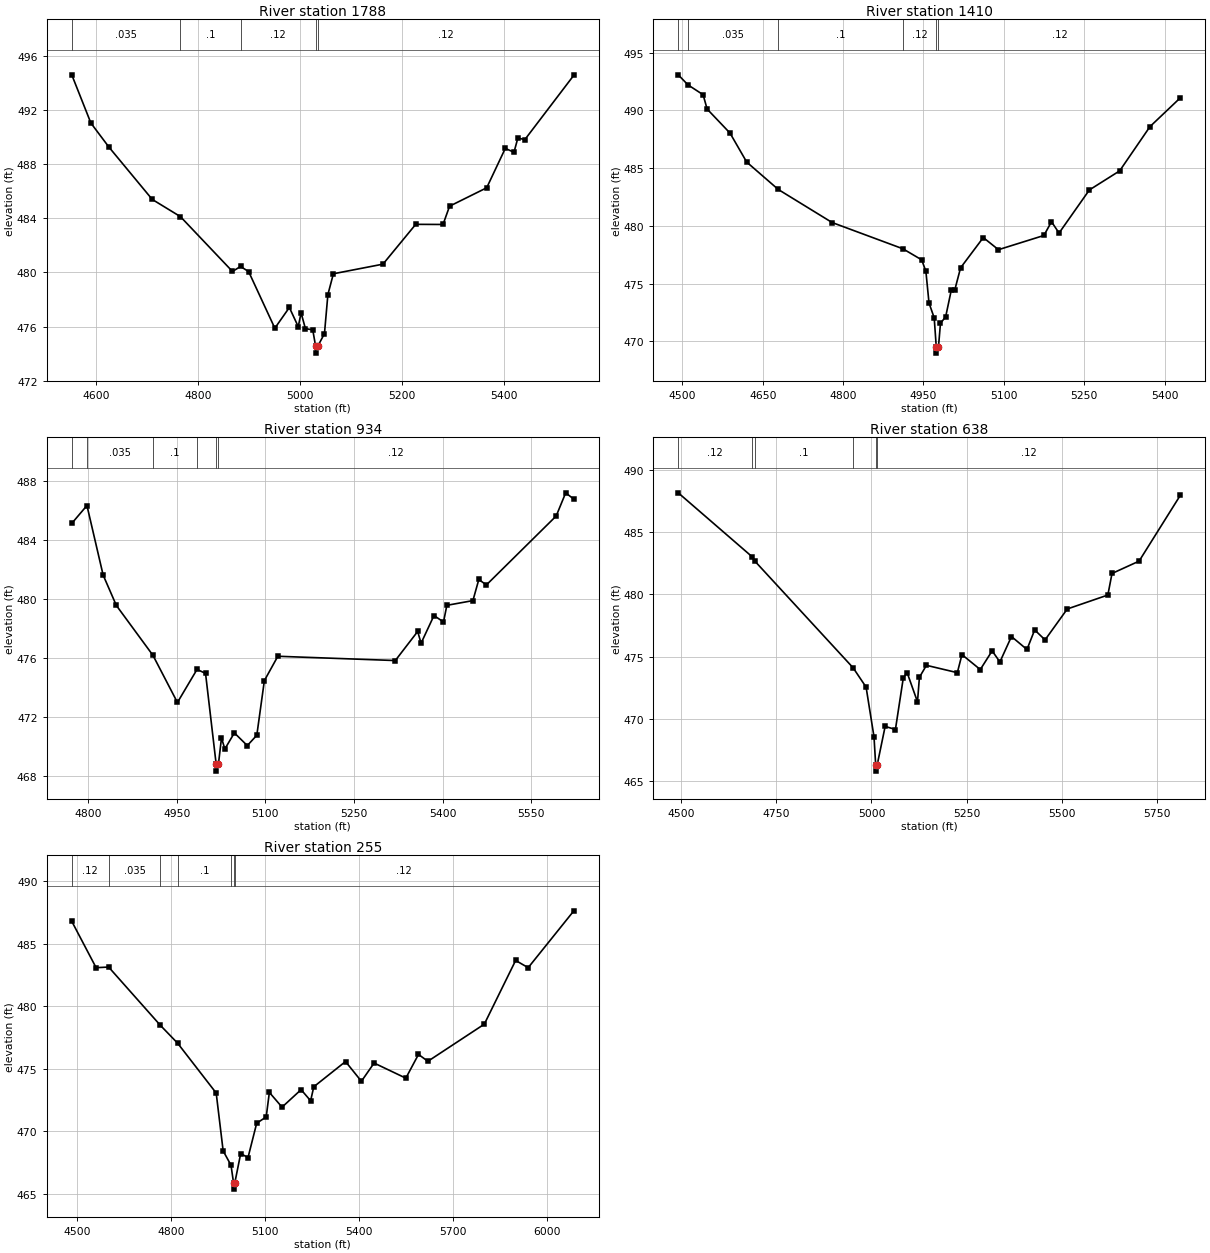
Type RM Length L Ch R = 1,1788,378,378,378
BEGIN DESCRIPTION:
H21445
END DESCRIPTION:
XS GIS Cut Line= 3
      2502981.53     13866503.13      2502489.33     13866729.70
      2502075.30     13866888.54
#Sta/Elev= 30
  4552.5  494.59  4590.0  491.03  4625.7  489.24  4710.4  485.39  4765.7  484.12
  4867.9  480.07  4883.7  480.44  4899.6  480.06  4951.0  475.88  4979.5  477.41
  4997.0  475.99  5002.5  477.02  5011.0  475.85  5025.4  475.76  5031.1  474.54
  5031.3  474.04  5035.1  474.54  5048.4  475.48  5055.1  478.36  5065.9  479.90
  5163.2  480.61  5227.5  483.55  5281.1  483.54  5293.9  484.89  5366.8  486.25
  5403.3  489.16  5420.3  488.87  5427.9  489.92  5441.7  489.81  5537.8  494.56
#Mann=5,-1,0
  4552.5   0.035       0  4765.7     0.1       0  4883.7    0.12       0
  5031.1    0.05       0  5035.1    0.12       0
Bank Sta=5031.1,5035.1
Exp/Cntr=0.3,0.1

Type RM Length L Ch R = 1,1410,476,476,476
BEGIN DESCRIPTION:
StreamM061 2.0
END DESCRIPTION:
XS GIS Cut Line= 3
      2502814.82     13866211.49      2502375.00     13866475.00
      2502074.99     13866775.01
#Sta/Elev= 30
  4492.3  493.07  4510.5  492.20  4538.7  491.35  4546.2  490.11  4588.9  488.03
  4620.1  485.52  4679.0  483.15  4779.5  480.29  4911.5  478.02  4946.7  477.06
  4954.5  476.06  4960.3  473.33  4970.0  472.04  4973.9  469.49  4974.1  468.99
  4977.9  469.49  4981.7  471.57  4991.4  472.14  5002.1  474.49  5008.6  474.49
  5019.2  476.37  5061.6  478.99  5089.9  477.94  5174.7  479.17  5188.9  480.36
  5203.0  479.38  5259.6  483.11  5316.1  484.76  5372.7  488.59  5429.3  491.08
#Mann=6,-1,0
  4492.3    0.12       0  4510.5   0.035       0  4679.0     0.1       0
  4911.5    0.12       0  4973.9    0.05       0  4977.9    0.12       0
Bank Sta=4973.9,4977.9
Exp/Cntr=0.3,0.1

Type RM Length L Ch R = 1,934,296,296,296
BEGIN DESCRIPTION:
StreamM061 1.0
END DESCRIPTION:
XS GIS Cut Line= 3
      2502475.00     13865975.00      2502275.00     13866075.00
      2501975.00     13866624.99
#Sta/Elev= 30
  4772.2  485.10  4797.9  486.31  4825.3  481.60  4847.7  479.54  4909.7  476.16
  4951.1  472.97  4984.3  475.21  4998.7  474.94  5016.6  468.82  5016.8  468.32
  5020.6  468.82  5025.7  470.57  5031.4  469.82  5047.5  470.91  5069.4  470.05
  5085.5  470.75  5098.3  474.45  5121.1  476.10  5320.0  475.81  5357.9  477.78
  5363.6  476.98  5385.5  478.86  5401.6  478.42  5407.3  479.55  5451.4  479.87
  5461.4  481.30  5474.2  480.93  5592.4  485.60  5608.5  487.17  5622.3  486.74
#Mann=6,-1,0
  4772.2    0.12       0  4797.9   0.035       0  4909.7     0.1       0
  4984.3    0.12       0  5016.6    0.05       0  5020.6    0.12       0
Bank Sta=5016.6,5020.6
Exp/Cntr=0.3,0.1

Type RM Length L Ch R = 1,638,383,383,383
BEGIN DESCRIPTION:
H21444
END DESCRIPTION:
XS GIS Cut Line= 3
      2502523.21     13865563.01      2502046.62     13865917.20
      2501916.71     13866631.70
#Sta/Elev= 30
  4491.9  488.14  4685.8  483.02  4692.7  482.68  4951.7  474.10  4985.8  472.55
  5006.6  468.56  5011.0  466.31  5011.2  465.81  5015.0  466.31  5035.9  469.40
  5062.9  469.15  5083.6  473.29  5093.6  473.72  5120.9  471.37  5126.0  473.34
  5144.4  474.30  5225.7  473.71  5237.8  475.16  5286.0  473.96  5317.2  475.46
  5337.6  474.57  5368.0  476.61  5408.7  475.57  5429.0  477.14  5456.3  476.34
  5514.7  478.82  5621.4  479.94  5632.3  481.67  5703.5  482.66  5811.9  487.94
#Mann=6,-1,0
  4491.9    0.12       0  4685.8   0.035       0  4692.7     0.1       0
  4951.7    0.12       0  5011.0    0.05       0  5015.0    0.12       0
Bank Sta=5011,5015
Exp/Cntr=0.3,0.1

Type RM Length L Ch R = 1,255,0,0,0
BEGIN DESCRIPTION:
H21443
END DESCRIPTION:
XS GIS Cut Line= 4
      2502390.39     13865260.93      2501955.48     13865617.72
      2501869.54     13866148.97      2501879.94     13866650.77
#Sta/Elev= 30
  4481.9  486.80  4559.6  483.09  4599.6  483.14  4764.6  478.48  4819.7  477.05
  4942.9  473.06  4965.1  468.43  4990.2  467.28  4998.3  465.87  4998.5  465.37
  5002.3  465.87  5021.1  468.22  5044.4  467.89  5072.1  470.64  5102.5  471.15
  5112.6  473.11  5153.1  471.93  5213.9  473.33  5244.3  472.44  5254.4  473.56
  5355.7  475.58  5406.4  474.00  5446.9  475.46  5548.2  474.25  5588.6  476.15
  5618.6  475.60  5798.7  478.57  5898.7  483.67  5938.7  483.09  6084.5  487.64
#Mann=7,-1,0
  4481.9    0.12       0  4599.6   0.035       0  4764.6   0.063       0
  4819.7     0.1       0  4990.2    0.12       0  4998.3    0.05       0
  5002.3    0.12       0
Bank Sta=4998.3,5002.3
Exp/Cntr=0.3,0.1

Chan Stop Cuts=-1