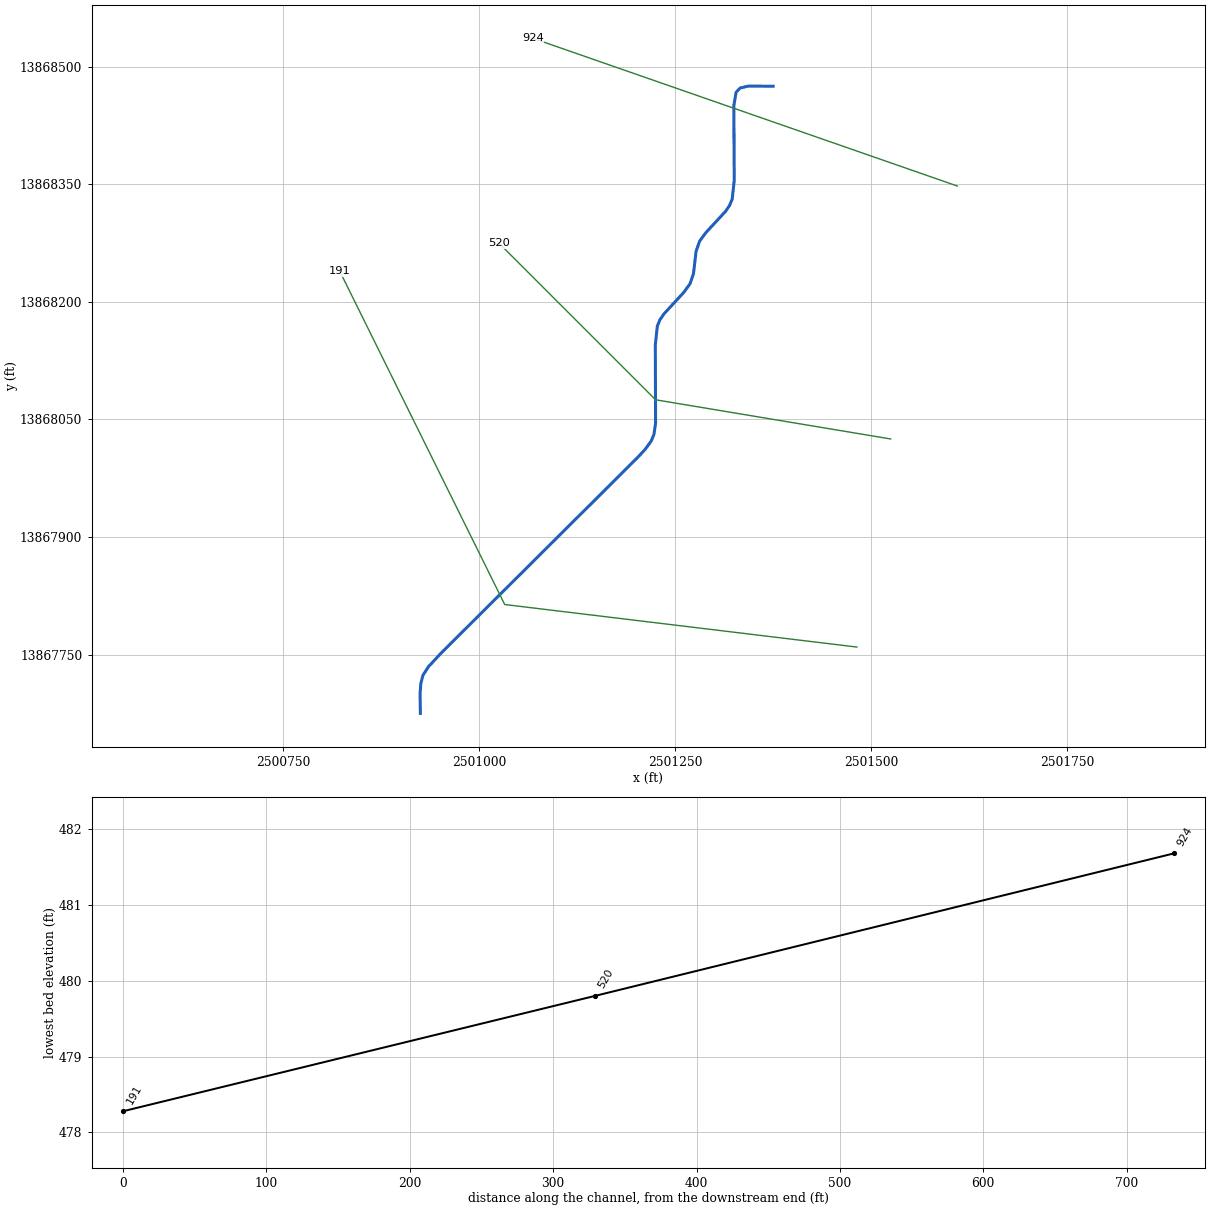
--- StreamM062.prj (project) ---

Proj Title=StreamM062 Base Level Engineering
Current Plan=p01
Default Exp/Contr=0.3,0.1
English Units
Geom File=g01
Flow File=f01
Plan File=p01
BEGIN DESCRIPTION:
StreamM062
END DESCRIPTION:

--- StreamM062.p01 (plan) ---

Plan Title=Multiple Run
Short Identifier=Multiple
Geom File=g01
Flow File=f01
Subcritical Flow
K Sum by GR= 0
Std Step Tol= 0.01
Critical Tol= 0.01
Num of Std Step Trials= 20
Max Error Tol= 0.3
Flow Tol Ratio= 0.001
Split Flow NTrial= 30
Split Flow Tol= 0.02
Split Flow Ratio= 0.02
Log Output Level= 0
Friction Slope Method= 1
Unsteady Friction Slope Method= 2
Unsteady Bridges Friction Slope Method= 1
Parabolic Critical Depth
Global Vel Dist=  1 , 1 , 1
Global Log Level= 0
CheckData=True
Encroach Param= -1, 0, 0, 0
BEGIN DESCRIPTION:
Multiple Run
END DESCRIPTION:

--- StreamM062.f01 (steady flow) ---

Flow Title=Multiple
Number of Profiles=7
Profile Names=10-year,25-year,50-year,1pct_min,100-year,1pct_plu,500-year
River Rch & RM= StreamM062,Reach-1,924
     407     634     833     532    1061    2117    1700
Boundary for River Rch & Prof#=StreamM062,Reach-1,1
Up Type=0
Dn Type=3
Dn Slope=0.005
Boundary for River Rch & Prof#=StreamM062,Reach-1,2
Up Type=0
Dn Type=3
Dn Slope=0.005
Boundary for River Rch & Prof#=StreamM062,Reach-1,3
Up Type=0
Dn Type=3
Dn Slope=0.005
Boundary for River Rch & Prof#=StreamM062,Reach-1,4
Up Type=0
Dn Type=3
Dn Slope=0.005
Boundary for River Rch & Prof#=StreamM062,Reach-1,5
Up Type=0
Dn Type=3
Dn Slope=0.005
Boundary for River Rch & Prof#=StreamM062,Reach-1,6
Up Type=0
Dn Type=3
Dn Slope=0.005
Boundary for River Rch & Prof#=StreamM062,Reach-1,7
Up Type=0
Dn Type=3
Dn Slope=0.005

--- StreamM062.g01 (geometry) ---

Geom Title=Existing Conditions

River Reach=StreamM062,Reach-1
Reach XY= 30
      2501375.00     13868475.00      2501343.05     13868475.10
      2501332.83     13868472.63      2501327.72     13868467.29
      2501324.84     13868450.18      2501325.35     13868354.88
      2501322.76     13868330.93      2501319.29     13868322.66
      2501314.20     13868315.33      2501289.04     13868288.04
      2501281.12     13868277.18      2501276.67     13868264.31
      2501273.33     13868235.69      2501268.88     13868222.82
      2501260.96     13868211.96      2501235.80     13868184.67
      2501230.72     13868177.35      2501227.25     13868169.07
      2501224.67     13868145.14      2501225.02     13868044.99
      2501222.93     13868030.86      2501219.53     13868022.55
      2501211.63     13868011.68      2501202.14     13868001.47
      2500951.35     13867751.80      2500935.51     13867734.79
      2500928.27     13867723.64      2500925.59     13867713.16
      2500924.59     13867700.37      2500925.00     13867675.00

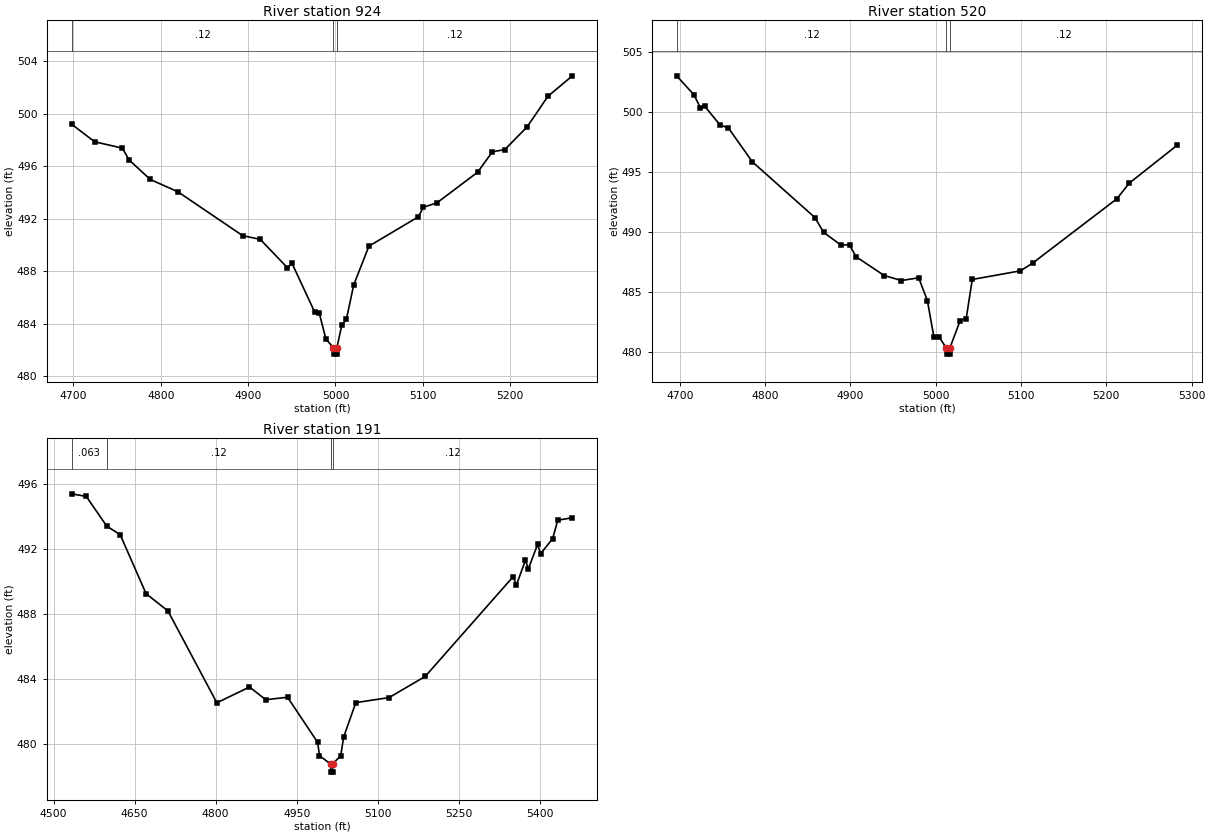
Type RM Length L Ch R = 1,924,404,404,404
BEGIN DESCRIPTION:
MXS18485
END DESCRIPTION:
XS GIS Cut Line= 2
      2501609.86     13868347.69      2501068.60     13868536.05
#Sta/Elev= 30
  4698.1  499.18  4724.4  497.85  4756.2  497.36  4763.7  496.47  4788.0  494.98
  4819.7  494.04  4893.8  490.70  4913.9  490.42  4945.0  488.26  4950.3  488.59
  4976.1  484.90  4981.4  484.82  4989.1  482.82  4997.7  482.18  4998.0  481.68
  5001.5  481.68  5001.7  482.18  5007.2  483.87  5012.5  484.33  5020.9  486.95
  5038.3  489.90  5095.0  492.14  5100.5  492.86  5116.2  493.20  5162.7  495.53
  5179.7  497.09  5193.8  497.25  5219.6  499.00  5243.2  501.31  5271.2  502.87
#Mann=3,-1,0
  4698.1    0.12       0  4997.7    0.05       0  5001.7    0.12       0
Bank Sta=4997.7,5001.7
Exp/Cntr=0.3,0.1

Type RM Length L Ch R = 1,520,329,329,329
BEGIN DESCRIPTION:
StreamM062 1.0
END DESCRIPTION:
XS GIS Cut Line= 3
      2501524.99     13868025.00      2501225.00     13868075.00
      2501024.98     13868275.02
#Sta/Elev= 30
  4696.2  503.02  4716.5  501.44  4724.1  500.35  4729.1  500.49  4746.9  498.93
  4757.0  498.66  4784.9  495.85  4858.4  491.19  4868.5  489.96  4888.8  488.90
  4898.9  488.92  4906.5  487.93  4939.5  486.36  4959.8  485.94  4980.0  486.17
  4990.2  484.26  4997.8  481.23  5003.9  481.23  5012.5  480.30  5012.7  479.80
  5016.2  479.80  5016.5  480.30  5028.6  482.60  5035.7  482.77  5042.8  486.03
  5099.3  486.75  5113.5  487.39  5212.5  492.77  5226.6  494.05  5283.2  497.24
#Mann=3,-1,0
  4696.2    0.12       0  5012.5    0.05       0  5016.5    0.12       0
Bank Sta=5012.5,5016.5
Exp/Cntr=0.3,0.1

Type RM Length L Ch R = 1,191,0,0,0
BEGIN DESCRIPTION:
MXS18484
END DESCRIPTION:
XS GIS Cut Line= 3
      2501481.81     13867759.59      2501032.56     13867813.85
      2500822.06     13868239.20
#Sta/Elev= 30
  4533.5  495.38  4560.5  495.22  4598.5  493.39  4623.1  492.88  4671.3  489.24
  4711.6  488.19  4802.3  482.54  4862.7  483.51  4892.9  482.73  4933.2  482.88
  4988.9  480.11  4992.3  479.29  5012.8  478.78  5013.0  478.28  5016.5  478.28
  5016.8  478.78  5031.6  479.29  5037.2  480.45  5059.6  482.55  5121.2  482.86
  5188.1  484.16  5351.2  490.30  5356.8  489.76  5373.6  491.29  5379.2  490.78
  5396.1  492.27  5401.7  491.70  5424.1  492.63  5433.6  493.76  5460.6  493.91
#Mann=4,-1,0
  4533.5   0.063       0  4598.5    0.12       0  5012.8    0.05       0
  5016.8    0.12       0
Bank Sta=5012.8,5016.8
Exp/Cntr=0.3,0.1

Chan Stop Cuts=-1