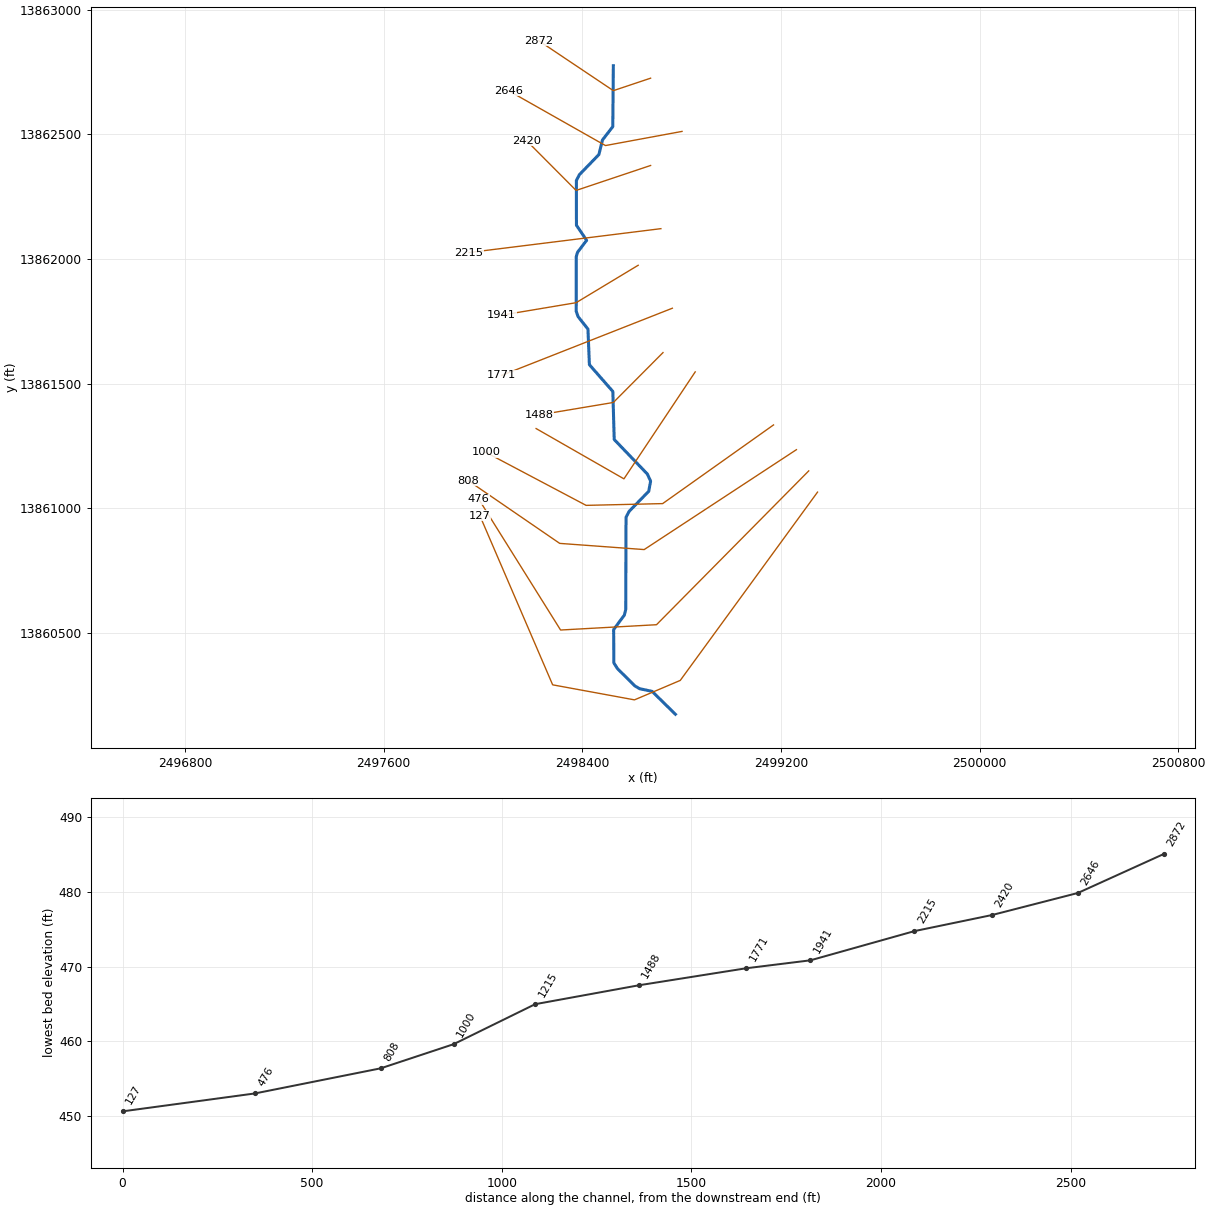
--- StreamM063.prj (project) ---

Proj Title=StreamM063 Base Level Engineering
Current Plan=p01
Default Exp/Contr=0.3,0.1
English Units
Geom File=g01
Flow File=f01
Plan File=p01
BEGIN DESCRIPTION:
StreamM063
END DESCRIPTION:

--- StreamM063.p01 (plan) ---

Plan Title=Multiple Run
Short Identifier=Multiple
Geom File=g01
Flow File=f01
Subcritical Flow
K Sum by GR= 0
Std Step Tol= 0.01
Critical Tol= 0.01
Num of Std Step Trials= 20
Max Error Tol= 0.3
Flow Tol Ratio= 0.001
Split Flow NTrial= 30
Split Flow Tol= 0.02
Split Flow Ratio= 0.02
Log Output Level= 0
Friction Slope Method= 1
Unsteady Friction Slope Method= 2
Unsteady Bridges Friction Slope Method= 1
Parabolic Critical Depth
Global Vel Dist=  1 , 1 , 1
Global Log Level= 0
CheckData=True
Encroach Param= -1, 0, 0, 0
BEGIN DESCRIPTION:
Multiple Run
END DESCRIPTION:

--- StreamM063.f01 (steady flow) ---

Flow Title=Multiple
Number of Profiles=7
Profile Names=10-year,25-year,50-year,1pct_min,100-year,1pct_plu,500-year
River Rch & RM= StreamM063,Reach-1,2872
     161     235     295     181     361     720     531
Boundary for River Rch & Prof#=StreamM063,Reach-1,1
Up Type=0
Dn Type=3
Dn Slope=0.005
Boundary for River Rch & Prof#=StreamM063,Reach-1,2
Up Type=0
Dn Type=3
Dn Slope=0.005
Boundary for River Rch & Prof#=StreamM063,Reach-1,3
Up Type=0
Dn Type=3
Dn Slope=0.005
Boundary for River Rch & Prof#=StreamM063,Reach-1,4
Up Type=0
Dn Type=3
Dn Slope=0.005
Boundary for River Rch & Prof#=StreamM063,Reach-1,5
Up Type=0
Dn Type=3
Dn Slope=0.005
Boundary for River Rch & Prof#=StreamM063,Reach-1,6
Up Type=0
Dn Type=3
Dn Slope=0.005
Boundary for River Rch & Prof#=StreamM063,Reach-1,7
Up Type=0
Dn Type=3
Dn Slope=0.005

--- StreamM063.g01 (geometry) ---

Geom Title=Existing Conditions

River Reach=StreamM063,Reach-1
Reach XY= 30
      2498525.00     13862775.00      2498522.76     13862530.93
      2498481.14     13862477.17      2498466.84     13862418.95
      2498388.40     13862338.31      2498376.05     13862314.56
      2498376.38     13862135.44      2498417.44     13862075.00
      2498381.02     13862027.45      2498375.66     13862009.84
      2498375.52     13861790.22      2498383.14     13861768.94
      2498422.73     13861719.06      2498428.56     13861576.47
      2498522.93     13861469.14      2498528.54     13861276.46
      2498661.89     13861138.21      2498675.11     13861109.64
      2498667.52     13861068.96      2498588.40     13860988.31
      2498576.06     13860964.56      2498574.93     13860595.03
      2498569.25     13860572.67      2498526.21     13860514.49
      2498527.04     13860380.85      2498541.41     13860358.20
      2498611.76     13860288.62      2498631.03     13860277.52
      2498681.07     13860266.89      2498775.00     13860175.00

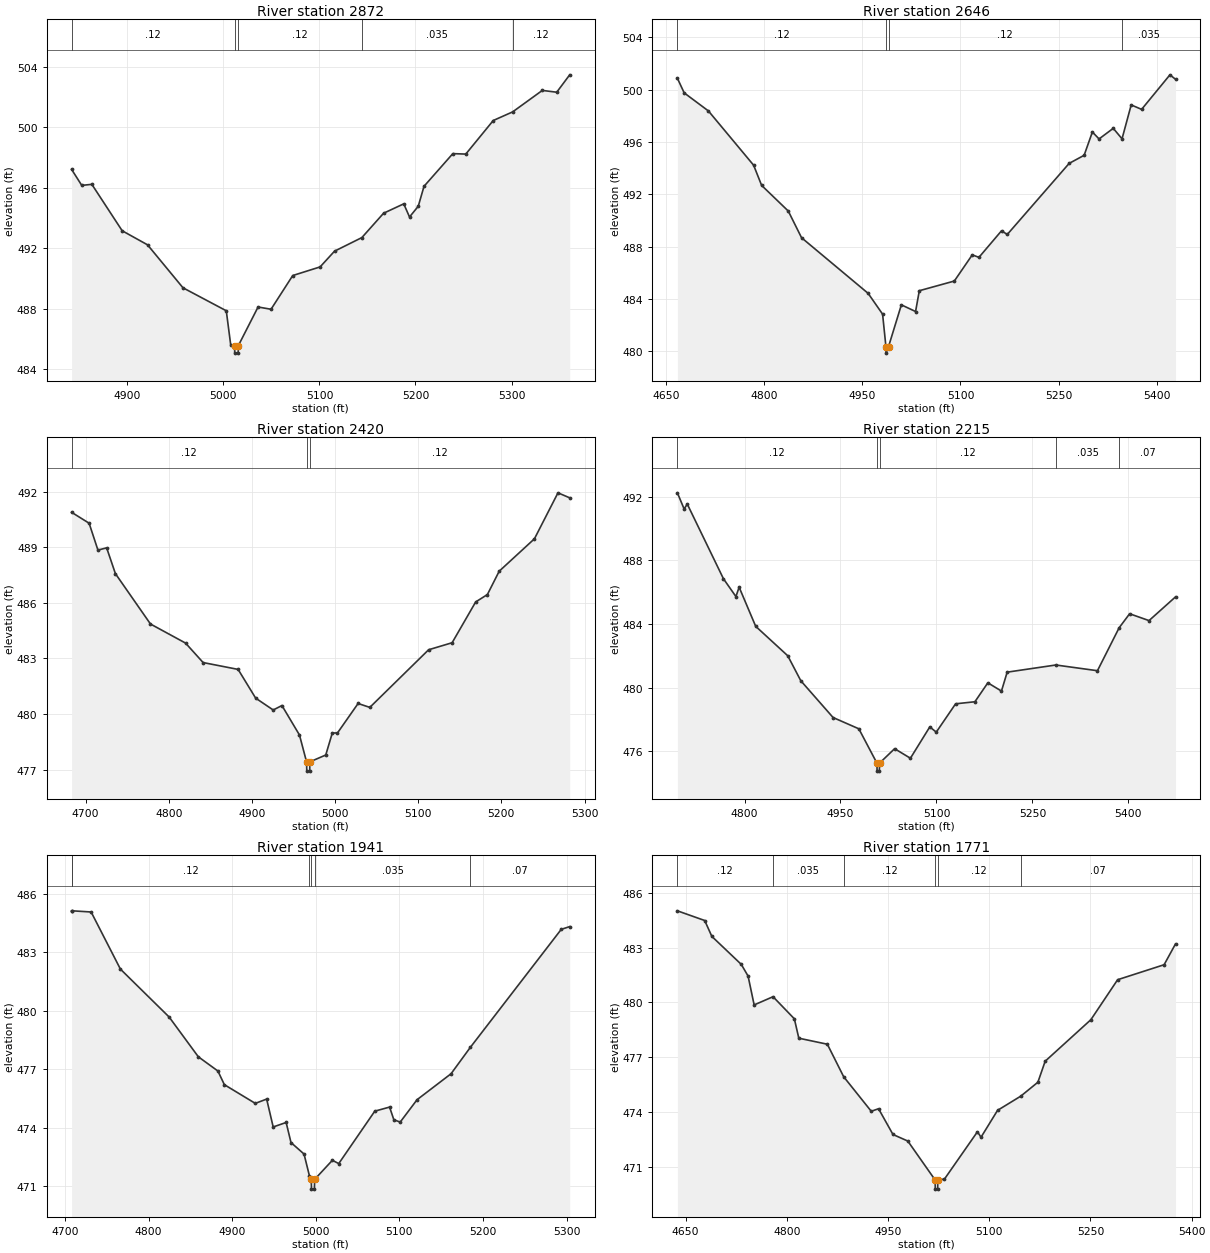
Type RM Length L Ch R = 1,2872,226,226,226
BEGIN DESCRIPTION:
StreamM063 5.0
END DESCRIPTION:
XS GIS Cut Line= 3
      2498675.02     13862725.01      2498525.00     13862675.00
      2498225.00     13862875.00
#Sta/Elev= 30
  4841.9  497.23  4852.5  496.17  4863.0  496.24  4894.6  493.17  4921.0  492.24
  4957.9  489.40  5003.0  487.88  5007.6  485.63  5011.6  485.58  5011.8  485.08
  5015.3  485.08  5015.6  485.58  5036.1  488.13  5049.6  487.98  5072.2  490.21
  5100.7  490.78  5115.7  491.82  5144.2  492.72  5166.8  494.33  5187.8  494.95
  5193.8  494.08  5202.9  494.79  5208.9  496.11  5238.9  498.27  5252.4  498.24
  5281.0  500.46  5301.2  501.03  5332.1  502.45  5347.1  502.33  5360.6  503.48
#Mann=5,-1,0
  4841.9    0.12       0  5011.6    0.05       0  5015.6    0.12       0
  5144.2   0.035       0  5301.2    0.12       0
Bank Sta=5011.6,5015.6
Exp/Cntr=0.3,0.1

Type RM Length L Ch R = 1,2646,226,226,226
BEGIN DESCRIPTION:
H21452
END DESCRIPTION:
XS GIS Cut Line= 3
      2498801.59     13862511.62      2498493.24     13862454.91
      2498103.42     13862674.63
#Sta/Elev= 30
  4667.5  500.88  4677.9  499.76  4714.9  498.38  4784.0  494.23  4796.2  492.69
  4836.9  490.73  4857.2  488.69  4958.9  484.44  4981.0  482.85  4986.1  480.37
  4986.3  479.87  4990.1  480.37  5009.7  483.56  5031.4  483.05  5037.1  484.64
  5090.6  485.38  5118.0  487.38  5128.2  487.19  5162.7  489.22  5171.5  488.94
  5266.0  494.37  5288.9  494.99  5301.5  496.77  5311.7  496.24  5333.4  497.05
  5346.8  496.25  5360.8  498.84  5376.7  498.50  5420.0  501.14  5428.5  500.80
#Mann=4,-1,0
  4667.5    0.12       0  4986.1    0.05       0  4990.1    0.12       0
  5346.8   0.035       0
Bank Sta=4986.1,4990.1
Exp/Cntr=0.3,0.1

Type RM Length L Ch R = 1,2420,205,205,205
BEGIN DESCRIPTION:
StreamM063 4.0
END DESCRIPTION:
XS GIS Cut Line= 3
      2498675.04     13862375.01      2498375.00     13862275.00
      2498175.01     13862474.99
#Sta/Elev= 30
  4683.1  490.89  4704.2  490.30  4714.8  488.85  4725.3  488.97  4735.8  487.58
  4778.0  484.86  4820.2  483.83  4841.3  482.78  4883.4  482.41  4904.5  480.86
  4925.6  480.22  4936.1  480.46  4957.2  478.87  4965.7  477.42  4966.0  476.92
  4969.5  476.92  4969.7  477.42  4988.8  477.79  4996.7  478.98  5002.9  478.98
  5027.7  480.57  5041.8  480.36  5112.5  483.47  5140.8  483.85  5169.1  486.05
  5183.2  486.45  5197.4  487.71  5239.8  489.46  5268.1  491.94  5282.2  491.67
#Mann=3,-1,0
  4683.1    0.12       0  4965.7    0.05       0  4969.7    0.12       0
Bank Sta=4965.7,4969.7
Exp/Cntr=0.3,0.1

Type RM Length L Ch R = 1,2215,274,274,274
BEGIN DESCRIPTION:
H21451
END DESCRIPTION:
XS GIS Cut Line= 2
      2498716.48     13862121.77      2497943.89     13862026.09
#Sta/Elev= 30
  4695.1  492.25  4705.6  491.24  4710.6  491.54  4767.1  486.85  4786.6  485.73
  4791.6  486.32  4817.5  483.86  4867.6  482.01  4888.0  480.44  4938.4  478.13
  4978.7  477.42  5007.0  475.26  5007.2  474.76  5010.7  474.76  5011.0  475.26
  5034.6  476.17  5059.3  475.57  5089.6  477.54  5099.7  477.21  5129.9  478.99
  5160.1  479.12  5180.3  480.31  5201.6  479.79  5210.5  480.98  5286.6  481.43
  5351.6  481.07  5385.5  483.77  5401.9  484.65  5432.2  484.22  5473.6  485.71
#Mann=5,-1,0
  4695.1    0.12       0  5007.0    0.05       0  5011.0    0.12       0
  5286.6   0.035       0  5385.5    0.07       0
Bank Sta=5007,5011
Exp/Cntr=0.3,0.1

Type RM Length L Ch R = 1,1941,170,170,170
BEGIN DESCRIPTION:
StreamM063 3.0
END DESCRIPTION:
XS GIS Cut Line= 3
      2498625.04     13861975.02      2498375.00     13861825.00
      2498075.03     13861775.00
#Sta/Elev= 30
  4708.0  485.13  4709.0  485.13  4731.4  485.07  4766.4  482.14  4824.7  479.68
  4859.6  477.64  4883.0  476.91  4890.7  476.21  4927.7  475.25  4941.3  475.47
  4949.1  474.04  4964.6  474.27  4970.4  473.24  4986.0  472.65  4992.4  471.54
  4994.7  471.35  4994.9  470.85  4998.4  470.85  4998.7  471.35  5019.9  472.33
  5027.5  472.16  5070.6  474.85  5088.3  475.06  5093.4  474.41  5101.0  474.29
  5121.2  475.44  5161.8  476.77  5184.8  478.12  5293.6  484.18  5303.7  484.32
#Mann=6,-1,0
  4708.0   0.035       0  4709.0    0.12       0  4992.4   0.035       0
  4994.7   0.035       0  4998.7   0.035       0  5184.8    0.07       0
Bank Sta=4994.7,4998.7
Exp/Cntr=0.3,0.1

Type RM Length L Ch R = 1,1771,283,283,283
BEGIN DESCRIPTION:
H21450
END DESCRIPTION:
XS GIS Cut Line= 2
      2498762.61     13861802.83      2498075.08     13861533.49
#Sta/Elev= 30
  4637.7  485.01  4678.2  484.48  4688.8  483.61  4732.4  482.08  4742.5  481.44
  4751.5  479.86  4779.5  480.31  4811.1  479.10  4817.7  478.04  4860.0  477.71
  4884.2  475.93  4925.1  474.04  4935.9  474.18  4957.3  472.77  4979.3  472.41
  5019.8  470.28  5020.0  469.78  5023.5  469.78  5023.8  470.28  5033.6  470.33
  5082.5  472.92  5087.8  472.62  5112.3  474.09  5146.8  474.87  5172.1  475.63
  5182.9  476.78  5250.6  479.05  5290.3  481.24  5359.2  482.06  5376.1  483.20
#Mann=6,-1,0
  4637.7    0.12       0  4779.5   0.035       0  4884.2    0.12       0
  5019.8    0.05       0  5023.8    0.12       0  5146.8    0.07       0
Bank Sta=5019.8,5023.8
Exp/Cntr=0.3,0.1

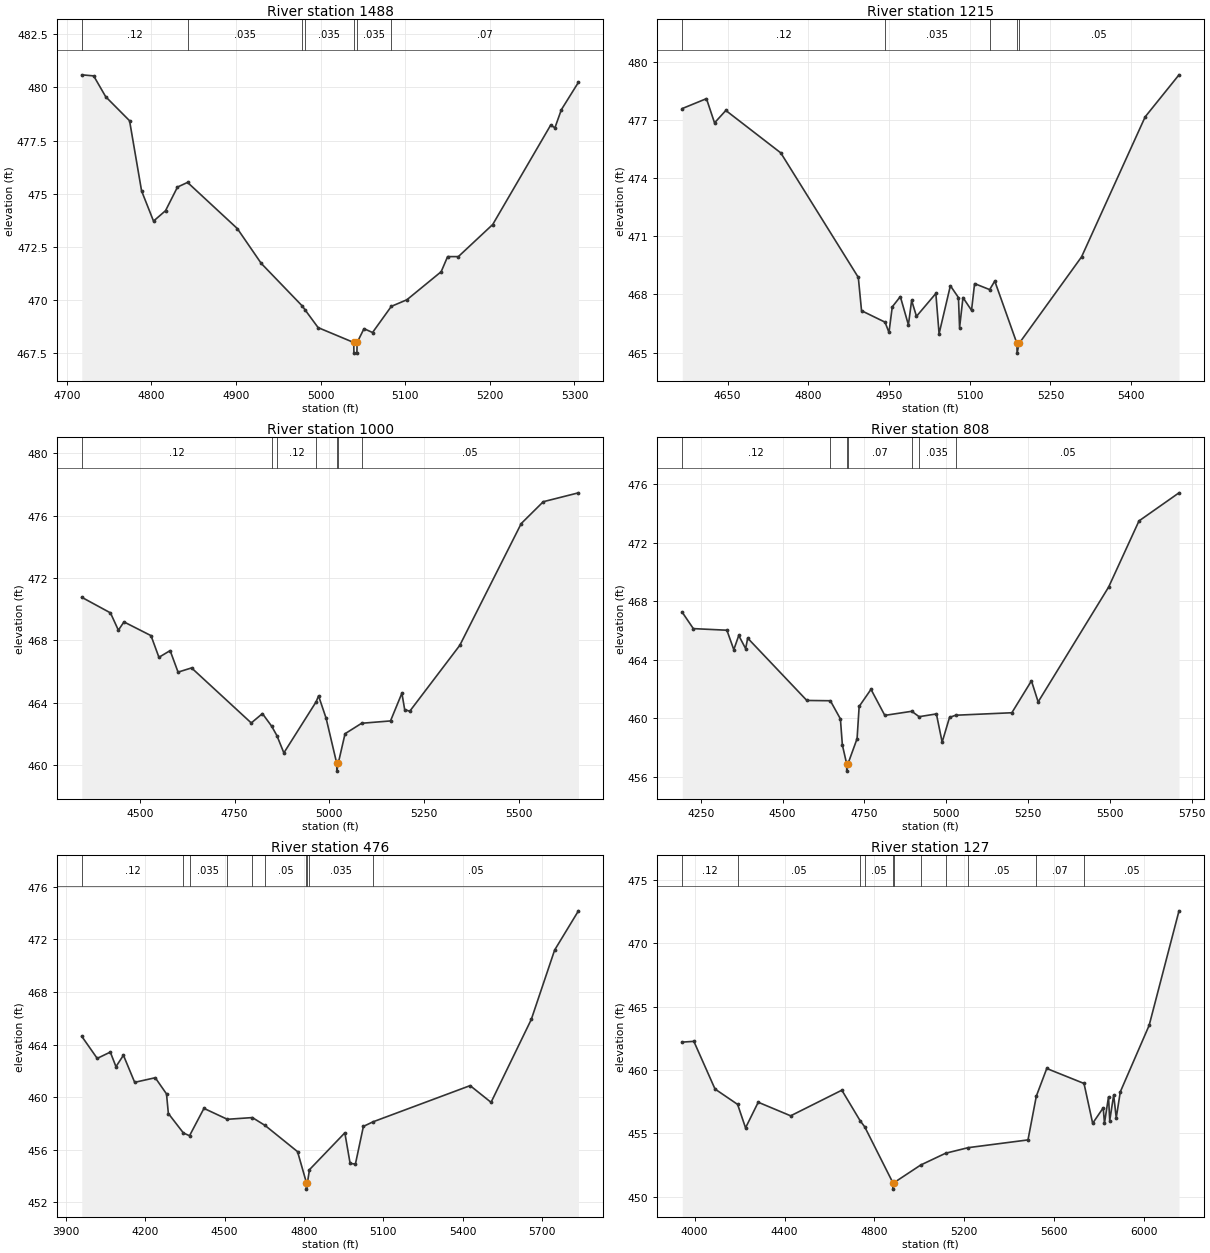
Type RM Length L Ch R = 1,1488,273,273,273
BEGIN DESCRIPTION:
StreamM063 2.0
END DESCRIPTION:
XS GIS Cut Line= 3
      2498724.98     13861624.98      2498525.00     13861425.00
      2498225.05     13861375.01
#Sta/Elev= 30
  4717.8  480.59  4731.9  480.54  4746.1  479.56  4774.3  478.43  4788.5  475.13
  4802.6  473.71  4816.8  474.20  4830.9  475.31  4842.8  475.53  4901.6  473.36
  4929.9  471.72  4978.3  469.72  4981.4  469.55  4997.1  468.70  5039.2  468.00
  5039.4  467.50  5042.9  467.50  5043.2  468.00  5051.3  468.65  5061.4  468.47
  5083.6  469.70  5102.0  470.01  5142.5  471.33  5150.1  472.04  5162.8  472.04
  5203.4  473.55  5271.8  478.22  5276.9  478.10  5284.5  478.95  5304.7  480.24
#Mann=7,-1,0
  4717.8    0.12       0  4842.8   0.035       0  4978.3    0.12       0
  4981.4   0.035       0  5039.2   0.035       0  5043.2   0.035       0
  5083.6    0.07       0
Bank Sta=5039.2,5043.2
Exp/Cntr=0.3,0.1

Type RM Length L Ch R = 1,1215,215,215,215
BEGIN DESCRIPTION:
StreamM063 1.0
END DESCRIPTION:
XS GIS Cut Line= 3
      2498854.73     13861547.65      2498567.67     13861118.83
      2498214.02     13861320.41
#Sta/Elev= 30
  4565.9  477.60  4610.8  478.11  4625.8  476.86  4646.8  477.50  4748.9  475.31
  4893.0  468.88  4899.0  467.16  4942.6  466.57  4950.0  466.04  4956.1  467.36
  4971.1  467.89  4986.1  466.43  4992.1  467.69  5001.1  466.87  5037.1  468.05
  5043.1  465.97  5064.1  468.45  5079.1  467.84  5081.2  466.28  5087.5  467.84
  5103.4  467.18  5109.1  468.56  5137.1  468.25  5146.6  468.69  5187.8  465.47
  5188.1  464.97  5191.8  465.47  5307.9  469.94  5426.1  477.17  5489.0  479.34
#Mann=5,-1,0
  4565.9    0.12       0  4942.6   0.035       0  5137.1    0.05       0
  5187.8   0.035       0  5191.8    0.05       0
Bank Sta=5187.8,5191.8
Exp/Cntr=0.3,0.1

Type RM Length L Ch R = 1,1000,192,192,192
BEGIN DESCRIPTION:
H21449
END DESCRIPTION:
XS GIS Cut Line= 4
      2499170.12     13861334.99      2498723.60     13861019.60
      2498415.27     13861012.51      2498011.29     13861225.13
#Sta/Elev= 30
  4346.6  470.76  4422.4  469.76  4443.3  468.65  4458.1  469.18  4529.5  468.30
  4550.4  466.91  4580.0  467.34  4600.9  465.96  4636.6  466.23  4794.2  462.70
  4823.7  463.30  4848.1  462.49  4861.9  461.89  4880.3  460.78  4965.6  464.06
  4971.9  464.44  4991.9  463.00  5019.9  460.11  5020.2  459.61  5023.9  460.11
  5041.9  462.01  5085.7  462.68  5161.9  462.83  5192.0  464.61  5199.3  463.56
  5212.7  463.45  5344.9  467.68  5507.1  475.49  5565.3  476.89  5658.2  477.46
#Mann=7,-1,0
  4346.6    0.12       0  4848.1    0.07       0  4861.9    0.12       0
  4965.6   0.035       0  5019.9   0.035       0  5023.9   0.035       0
  5085.7    0.05       0
Bank Sta=5019.9,5023.9
Exp/Cntr=0.3,0.1

Type RM Length L Ch R = 1,808,332,332,332
BEGIN DESCRIPTION:
H21448
END DESCRIPTION:
XS GIS Cut Line= 4
      2499262.26     13861235.76      2498649.18     13860835.31
      2498308.95     13860860.12      2497941.69     13861110.85
#Sta/Elev= 30
  4193.3  467.23  4227.0  466.12  4329.6  466.01  4350.7  464.68  4365.8  465.65
  4386.9  464.75  4393.1  465.47  4573.9  461.21  4645.8  461.19  4676.5  459.95
  4682.5  458.17  4695.6  456.88  4695.9  456.38  4699.6  456.88  4727.5  458.60
  4733.8  460.80  4770.0  461.97  4812.2  460.19  4894.7  460.47  4917.0  460.10
  4969.9  460.29  4987.5  458.36  5010.0  460.05  5028.7  460.20  5200.5  460.37
  5260.4  462.55  5280.9  461.11  5496.3  468.96  5589.1  473.48  5711.4  475.40
#Mann=7,-1,0
  4193.3    0.12       0  4645.8    0.07       0  4695.6   0.035       0
  4699.6    0.07       0  4894.7    0.05       0  4917.0   0.035       0
  5028.7    0.05       0
Bank Sta=4695.6,4699.6
Exp/Cntr=0.3,0.1

Type RM Length L Ch R = 1,476,349,349,349
BEGIN DESCRIPTION:
H21447
END DESCRIPTION:
XS GIS Cut Line= 4
      2499311.91     13861150.73      2498698.79     13860534.07
      2498312.50     13860512.81      2497982.93     13861037.29
#Sta/Elev= 30
  3960.8  464.63  4019.2  462.95  4068.7  463.43  4090.0  462.32  4118.2  463.19
  4160.7  461.13  4238.4  461.48  4280.9  460.25  4287.9  458.76  4344.7  457.28
  4367.9  457.07  4422.3  459.15  4510.6  458.32  4605.3  458.45  4653.3  457.85
  4775.8  455.86  4809.2  453.51  4809.5  453.01  4813.2  453.51  4820.9  454.49
  4954.4  457.29  4974.4  454.96  4994.4  454.92  5024.5  457.78  5061.2  458.13
  5427.6  460.88  5506.6  459.61  5658.5  465.91  5746.8  471.19  5836.7  474.17
#Mann=10,-1,0
  3960.8    0.12       0  4344.7    0.07       0  4367.9   0.035       0
  4510.6    0.05       0  4605.3   0.035       0  4653.3    0.05       0
  4809.2   0.035       0  4813.2    0.05       0  4820.9   0.035       0
  5061.2    0.05       0
Bank Sta=4809.2,4813.2
Exp/Cntr=0.3,0.1

Type RM Length L Ch R = 1,127,0,0,0
BEGIN DESCRIPTION:
H21446
END DESCRIPTION:
XS GIS Cut Line= 5
      2499347.32     13861065.64      2498794.48     13860310.80
      2498610.19     13860232.83      2498280.60     13860293.08
      2497987.20     13860971.79
#Sta/Elev= 30
  3945.1  462.20  3996.5  462.26  4090.7  458.50  4191.2  457.29  4226.5  455.44
  4282.9  457.46  4427.2  456.39  4655.0  458.41  4736.5  456.00  4756.8  455.52
  4882.2  451.11  4882.4  450.61  4886.2  451.11  5005.9  452.51  5116.8  453.44
  5217.5  453.88  5483.3  454.49  5520.4  457.94  5566.8  460.12  5732.6  458.94
  5771.1  455.80  5818.1  457.02  5823.6  455.81  5841.6  457.88  5847.1  456.02
  5864.6  458.03  5876.0  456.23  5894.1  458.28  6022.4  463.52  6155.3  472.55
#Mann=11,-1,0
  3945.1    0.12       0  4191.2    0.05       0  4736.5   0.035       0
  4756.8    0.05       0  4882.2    0.05       0  4886.2    0.05       0
  5005.9    0.07       0  5116.8   0.035       0  5217.5    0.05       0
  5520.4    0.07       0  5732.6    0.05       0
Bank Sta=4882.2,4886.2
Exp/Cntr=0.3,0.1

Chan Stop Cuts=-1