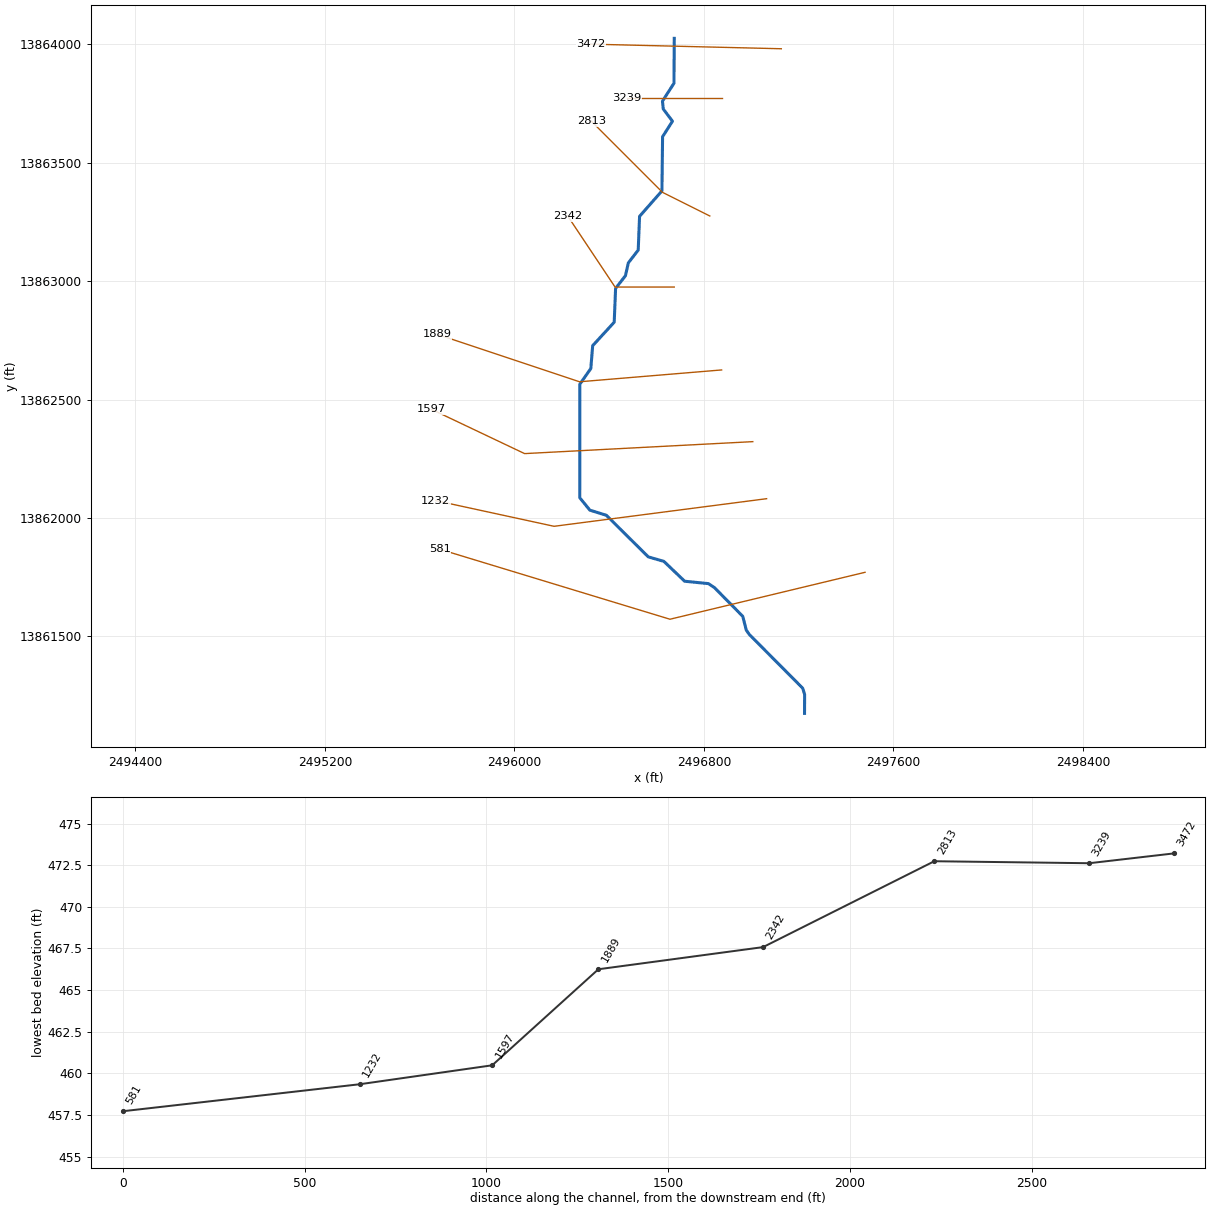
--- StreamM064.prj (project) ---

Proj Title=StreamM064 Base Level Engineering
Current Plan=p01
Default Exp/Contr=0.3,0.1
English Units
Geom File=g01
Flow File=f01
Plan File=p01
BEGIN DESCRIPTION:
StreamM064
END DESCRIPTION:

--- StreamM064.p01 (plan) ---

Plan Title=Multiple Run
Short Identifier=Multiple
Geom File=g01
Flow File=f01
Subcritical Flow
K Sum by GR= 0
Std Step Tol= 0.01
Critical Tol= 0.01
Num of Std Step Trials= 20
Max Error Tol= 0.3
Flow Tol Ratio= 0.001
Split Flow NTrial= 30
Split Flow Tol= 0.02
Split Flow Ratio= 0.02
Log Output Level= 0
Friction Slope Method= 1
Unsteady Friction Slope Method= 2
Unsteady Bridges Friction Slope Method= 1
Parabolic Critical Depth
Global Vel Dist=  1 , 1 , 1
Global Log Level= 0
CheckData=True
Encroach Param= -1, 0, 0, 0
BEGIN DESCRIPTION:
Multiple Run
END DESCRIPTION:

--- StreamM064.f01 (steady flow) ---

Flow Title=Multiple
Number of Profiles=7
Profile Names=10-year,25-year,50-year,1pct_min,100-year,1pct_plu,500-year
River Rch & RM= StreamM064,Reach-1,3472
     471     742     981     630    1256    2506    2036
Boundary for River Rch & Prof#=StreamM064,Reach-1,1
Up Type=0
Dn Type=3
Dn Slope=0.005
Boundary for River Rch & Prof#=StreamM064,Reach-1,2
Up Type=0
Dn Type=3
Dn Slope=0.005
Boundary for River Rch & Prof#=StreamM064,Reach-1,3
Up Type=0
Dn Type=3
Dn Slope=0.005
Boundary for River Rch & Prof#=StreamM064,Reach-1,4
Up Type=0
Dn Type=3
Dn Slope=0.005
Boundary for River Rch & Prof#=StreamM064,Reach-1,5
Up Type=0
Dn Type=3
Dn Slope=0.005
Boundary for River Rch & Prof#=StreamM064,Reach-1,6
Up Type=0
Dn Type=3
Dn Slope=0.005
Boundary for River Rch & Prof#=StreamM064,Reach-1,7
Up Type=0
Dn Type=3
Dn Slope=0.005

--- StreamM064.g01 (geometry) ---

Geom Title=Existing Conditions

River Reach=StreamM064,Reach-1
Reach XY= 30
      2496675.00     13864025.00      2496673.77     13863835.49
      2496625.15     13863759.58      2496628.61     13863726.64
      2496667.41     13863675.01      2496625.66     13863609.84
      2496622.93     13863380.86      2496528.56     13863273.53
      2496522.75     13863130.93      2496481.12     13863077.18
      2496468.88     13863022.82      2496427.25     13862969.07
      2496421.44     13862826.47      2496330.54     13862727.42
      2496322.64     13862630.98      2496276.22     13862564.50
      2496275.99     13862085.28      2496318.62     13862033.02
      2496388.20     13862011.36      2496565.32     13861835.78
      2496631.04     13861816.82      2496718.84     13861732.88
      2496819.11     13861722.85      2496845.16     13861705.37
      2496964.22     13861584.68      2496978.98     13861526.65
      2496991.65     13861508.33      2497217.26     13861281.22
      2497225.33     13861255.14      2497225.00     13861175.00

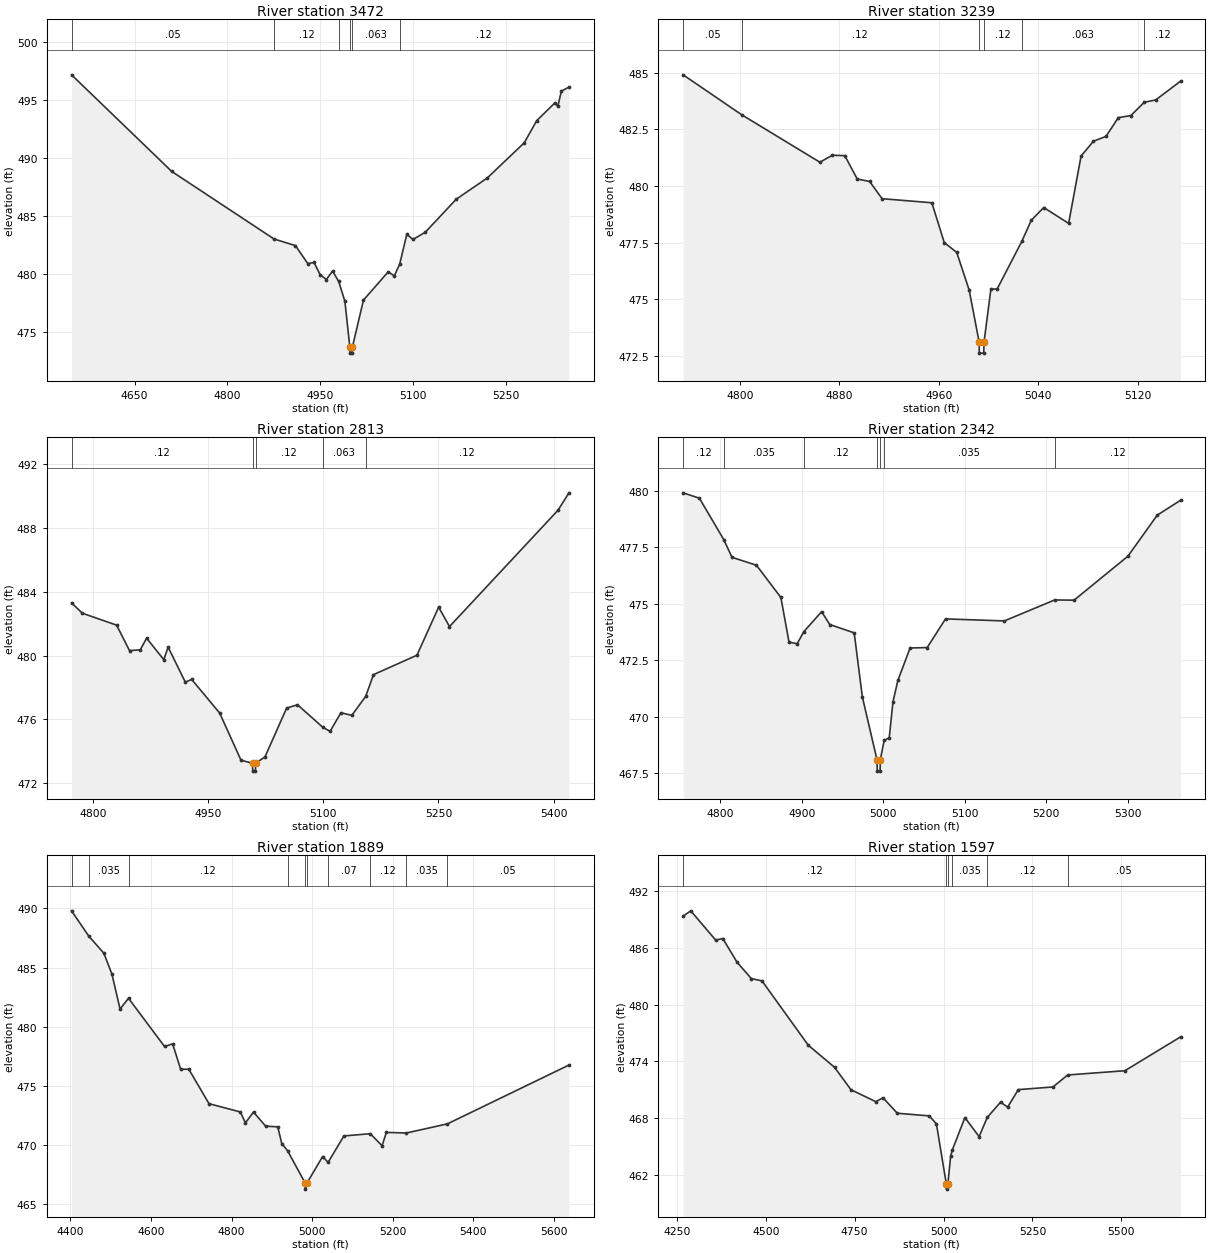
Type RM Length L Ch R = 1,3472,233,233,233
BEGIN DESCRIPTION:
H21456
END DESCRIPTION:
XS GIS Cut Line= 2
      2497126.99     13863981.03      2496322.83     13864000.46
#Sta/Elev= 30
  4547.9  497.18  4709.9  488.86  4875.4  483.04  4910.0  482.47  4930.0  480.92
  4940.0  481.02  4950.0  479.96  4960.0  479.55  4970.0  480.28  4980.0  479.38
  4990.0  477.66  4998.0  473.71  4998.3  473.21  5001.8  473.21  5002.0  473.71
  5020.0  477.78  5060.0  480.21  5070.0  479.87  5078.6  480.88  5090.1  483.44
  5100.1  483.00  5120.1  483.63  5170.1  486.47  5220.1  488.29  5280.1  491.33
  5300.1  493.23  5329.3  494.75  5334.3  494.48  5340.1  495.78  5352.3  496.12
#Mann=6,-1,0
  4547.9    0.05       0  4875.4    0.12       0  4980.0   0.063       0
  4998.0    0.05       0  5002.0   0.063       0  5078.6    0.12       0
Bank Sta=4998,5002
Exp/Cntr=0.3,0.1

Type RM Length L Ch R = 1,3239,426,426,426
BEGIN DESCRIPTION:
StreamM064 5.0
END DESCRIPTION:
XS GIS Cut Line= 3
      2496874.99     13863775.00      2496625.00     13863775.00
      2496474.99     13863775.00
#Sta/Elev= 30
  4754.3  484.91  4801.3  483.15  4864.3  481.05  4874.3  481.36  4884.3  481.34
  4894.3  480.31  4904.3  480.20  4914.3  479.44  4954.3  479.26  4964.3  477.50
  4974.3  477.07  4984.3  475.41  4992.3  473.12  4992.5  472.62  4996.0  472.62
  4996.3  473.12  5001.8  475.45  5006.8  475.45  5026.7  477.56  5034.3  478.49
  5044.3  479.05  5064.3  478.35  5074.3  481.32  5084.3  481.98  5094.3  482.19
  5104.3  483.02  5114.3  483.11  5125.2  483.70  5134.3  483.80  5154.3  484.63
#Mann=6,-1,0
  4754.3    0.05       0  4801.3    0.12       0  4992.3    0.05       0
  4996.3    0.12       0  5026.7   0.063       0  5125.2    0.12       0
Bank Sta=4992.3,4996.3
Exp/Cntr=0.3,0.1

Type RM Length L Ch R = 1,2813,471,471,471
BEGIN DESCRIPTION:
StreamM064 4.0
END DESCRIPTION:
XS GIS Cut Line= 3
      2496825.02     13863274.99      2496625.00     13863375.00
      2496324.99     13863675.01
#Sta/Elev= 30
  4772.1  483.31  4786.1  482.66  4830.8  481.91  4847.6  480.31  4861.6  480.36
  4869.9  481.09  4892.3  479.74  4897.9  480.53  4920.3  478.33  4928.6  478.50
  4965.0  476.39  4992.9  473.42  5007.9  473.24  5008.1  472.74  5011.6  472.74
  5011.9  473.24  5024.0  473.63  5052.3  476.70  5066.4  476.91  5099.5  475.49
  5108.9  475.24  5123.0  476.41  5137.1  476.24  5155.2  477.43  5165.4  478.80
  5222.0  480.02  5250.3  483.04  5264.4  481.82  5405.8  489.13  5420.0  490.22
#Mann=5,-1,0
  4772.1    0.12       0  5007.9    0.05       0  5011.9    0.12       0
  5099.5   0.063       0  5155.2    0.12       0
Bank Sta=5007.9,5011.9
Exp/Cntr=0.3,0.1

Type RM Length L Ch R = 1,2342,453,453,453
BEGIN DESCRIPTION:
StreamM064 3.0
END DESCRIPTION:
XS GIS Cut Line= 3
      2496675.04     13862975.00      2496425.00     13862975.00
      2496225.00     13863275.01
#Sta/Elev= 30
  4754.5  479.92  4774.5  479.68  4804.3  477.85  4814.5  477.06  4844.5  476.71
  4874.5  475.28  4884.5  473.30  4894.5  473.23  4902.8  473.77  4924.5  474.65
  4934.5  474.08  4964.5  473.71  4974.5  470.87  4992.5  468.08  4992.8  467.58
  4996.3  467.58  4996.5  468.08  5001.3  468.94  5007.5  469.06  5012.1  470.65
  5018.1  471.60  5033.1  473.04  5054.1  473.06  5076.6  474.33  5148.8  474.24
  5210.6  475.17  5234.4  475.16  5300.5  477.11  5336.5  478.93  5365.1  479.59
#Mann=7,-1,0
  4754.5    0.12       0  4804.3   0.035       0  4902.8    0.12       0
  4992.5    0.05       0  4996.5    0.12       0  5001.3   0.035       0
  5210.6    0.12       0
Bank Sta=4992.5,4996.5
Exp/Cntr=0.3,0.1

Type RM Length L Ch R = 1,1889,292,292,292
BEGIN DESCRIPTION:
StreamM064 2.0
END DESCRIPTION:
XS GIS Cut Line= 3
      2496875.00     13862625.00      2496275.00     13862575.00
      2495675.04     13862774.99
#Sta/Elev= 30
  4402.7  489.80  4445.5  487.66  4483.0  486.21  4503.0  484.44  4523.1  481.49
  4544.1  482.40  4633.5  478.32  4653.6  478.54  4673.6  476.39  4693.7  476.40
  4743.9  473.48  4821.6  472.78  4834.2  471.86  4854.3  472.77  4884.4  471.58
  4914.5  471.52  4924.5  470.10  4938.7  469.51  4982.7  466.75  4983.0  466.25
  4986.7  466.75  5025.9  469.01  5039.4  468.51  5078.6  470.75  5144.2  470.94
  5173.4  469.92  5184.0  471.05  5233.8  471.00  5335.4  471.77  5637.2  476.75
#Mann=10,-1,0
  4402.7    0.12       0  4445.5   0.035       0  4544.1    0.12       0
  4938.7   0.035       0  4982.7   0.035       0  4986.7   0.035       0
  5039.4    0.07       0  5144.2    0.12       0  5233.8   0.035       0
  5335.4    0.05       0
Bank Sta=4982.7,4986.7
Exp/Cntr=0.3,0.1

Type RM Length L Ch R = 1,1597,365,365,365
BEGIN DESCRIPTION:
H21455
END DESCRIPTION:
XS GIS Cut Line= 3
      2497006.49     13862322.24      2496043.11     13862271.74
      2495650.76     13862458.20
#Sta/Elev= 30
  4267.5  489.37  4289.0  489.93  4359.1  486.83  4379.1  487.00  4419.2  484.49
  4459.3  482.76  4489.3  482.52  4619.5  475.71  4693.4  473.37  4739.6  471.00
  4809.7  469.73  4829.8  470.15  4869.8  468.51  4959.9  468.23  4980.0  467.38
  5008.0  460.98  5008.3  460.48  5012.0  460.98  5020.0  463.98  5024.3  464.59
  5060.1  468.05  5100.1  466.03  5122.8  468.06  5160.2  469.68  5180.2  469.16
  5210.3  471.01  5307.6  471.29  5349.2  472.56  5510.1  473.01  5666.6  476.59
#Mann=6,-1,0
  4267.5    0.12       0  5008.0    0.05       0  5012.0    0.12       0
  5024.3   0.035       0  5122.8    0.12       0  5349.2    0.05       0
Bank Sta=5008,5012
Exp/Cntr=0.3,0.1

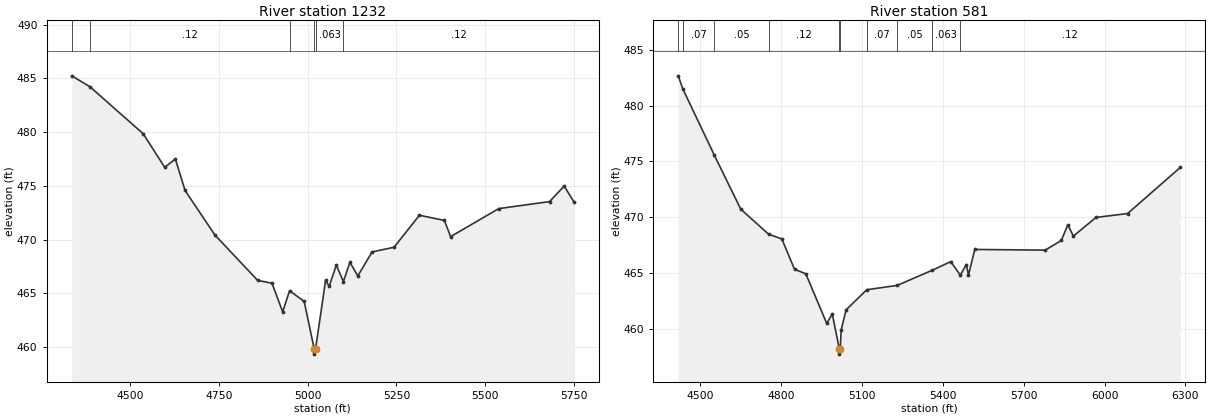
Type RM Length L Ch R = 1,1232,651,651,651
BEGIN DESCRIPTION:
H21454
END DESCRIPTION:
XS GIS Cut Line= 3
      2497064.81     13862081.39      2496167.43     13861964.84
      2495668.18     13862073.21
#Sta/Elev= 30
  4334.5  485.23  4385.5  484.22  4536.0  479.84  4596.5  476.72  4626.7  477.49
  4653.9  474.57  4738.1  470.42  4858.7  466.20  4899.0  465.94  4929.3  463.27
  4948.7  465.24  4989.8  464.25  5018.0  459.84  5018.3  459.34  5022.0  459.84
  5050.3  466.20  5060.4  465.65  5080.5  467.62  5100.5  466.09  5118.8  467.89
  5141.0  466.61  5181.4  468.85  5243.2  469.28  5314.8  472.26  5385.2  471.78
  5402.8  470.27  5538.7  472.88  5681.9  473.53  5722.9  474.97  5750.3  473.52
#Mann=6,-1,0
  4334.5    0.07       0  4385.5    0.12       0  4948.7   0.063       0
  5018.0    0.05       0  5022.0   0.063       0  5100.5    0.12       0
Bank Sta=5018,5022
Exp/Cntr=0.3,0.1

Type RM Length L Ch R = 1,581,0,0,0
BEGIN DESCRIPTION:
H21453
END DESCRIPTION:
XS GIS Cut Line= 3
      2497480.45     13861770.60      2496656.91     13861572.48
      2495685.73     13861867.72
#Sta/Elev= 30
  4419.0  482.66  4436.1  481.48  4553.2  475.53  4650.9  470.71  4754.5  468.46
  4803.2  468.05  4850.3  465.32  4892.2  464.92  4969.7  460.47  4990.3  461.32
  5016.1  458.22  5016.3  457.72  5020.1  458.22  5023.2  459.88  5041.7  461.69
  5118.2  463.49  5231.3  463.88  5361.4  465.24  5429.7  466.01  5465.3  464.80
  5487.5  465.75  5495.5  464.81  5518.9  467.10  5780.2  467.04  5839.8  467.91
  5863.8  469.30  5884.7  468.30  5968.3  469.97  6085.6  470.32  6281.1  474.45
#Mann=10,-1,0
  4419.0    0.05       0  4436.1    0.07       0  4553.2    0.05       0
  4754.5    0.12       0  5016.1    0.05       0  5020.1    0.12       0
  5118.2    0.07       0  5231.3    0.05       0  5361.4   0.063       0
  5465.3    0.12       0
Bank Sta=5016.1,5020.1
Exp/Cntr=0.3,0.1

Chan Stop Cuts=-1