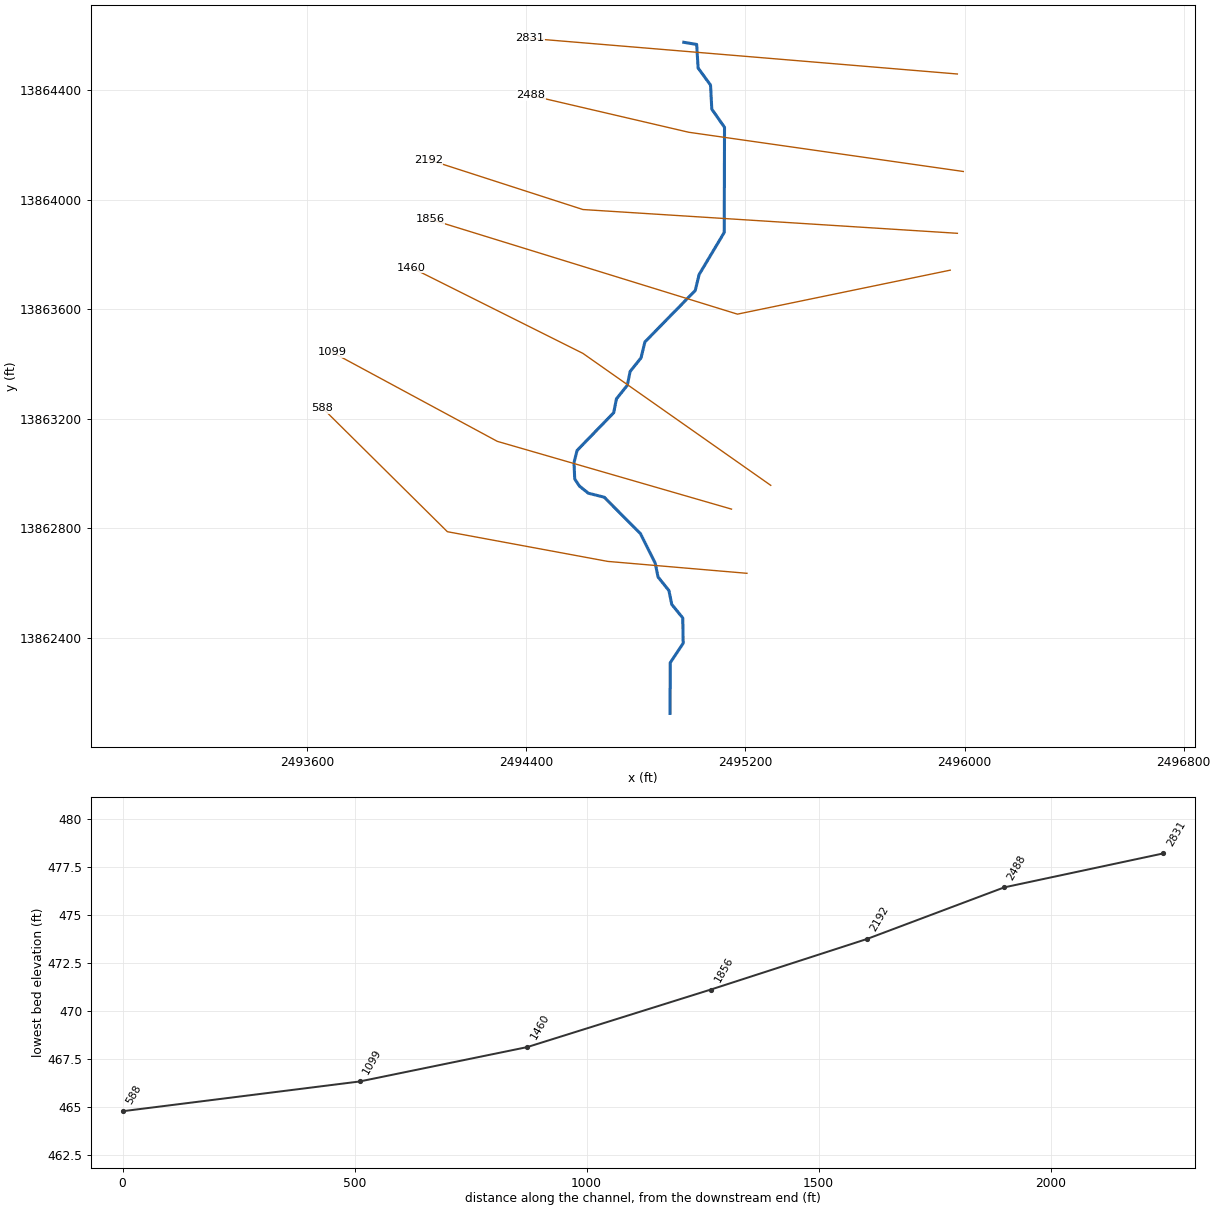
--- StreamM065.prj (project) ---

Proj Title=StreamM065 Base Level Engineering
Current Plan=p01
Default Exp/Contr=0.3,0.1
English Units
Geom File=g01
Flow File=f01
Plan File=p01
BEGIN DESCRIPTION:
StreamM065
END DESCRIPTION:

--- StreamM065.p01 (plan) ---

Plan Title=Multiple Run
Short Identifier=Multiple
Geom File=g01
Flow File=f01
Subcritical Flow
K Sum by GR= 0
Std Step Tol= 0.01
Critical Tol= 0.01
Num of Std Step Trials= 20
Max Error Tol= 0.3
Flow Tol Ratio= 0.001
Split Flow NTrial= 30
Split Flow Tol= 0.02
Split Flow Ratio= 0.02
Log Output Level= 0
Friction Slope Method= 1
Unsteady Friction Slope Method= 2
Unsteady Bridges Friction Slope Method= 1
Parabolic Critical Depth
Global Vel Dist=  1 , 1 , 1
Global Log Level= 0
CheckData=True
Encroach Param= -1, 0, 0, 0
BEGIN DESCRIPTION:
Multiple Run
END DESCRIPTION:

--- StreamM065.f01 (steady flow) ---

Flow Title=Multiple
Number of Profiles=7
Profile Names=10-year,25-year,50-year,1pct_min,100-year,1pct_plu,500-year
River Rch & RM= StreamM065,Reach-1,2831
     546     867    1152     743    1483    2959    2429
Boundary for River Rch & Prof#=StreamM065,Reach-1,1
Up Type=0
Dn Type=3
Dn Slope=0.005
Boundary for River Rch & Prof#=StreamM065,Reach-1,2
Up Type=0
Dn Type=3
Dn Slope=0.005
Boundary for River Rch & Prof#=StreamM065,Reach-1,3
Up Type=0
Dn Type=3
Dn Slope=0.005
Boundary for River Rch & Prof#=StreamM065,Reach-1,4
Up Type=0
Dn Type=3
Dn Slope=0.005
Boundary for River Rch & Prof#=StreamM065,Reach-1,5
Up Type=0
Dn Type=3
Dn Slope=0.005
Boundary for River Rch & Prof#=StreamM065,Reach-1,6
Up Type=0
Dn Type=3
Dn Slope=0.005
Boundary for River Rch & Prof#=StreamM065,Reach-1,7
Up Type=0
Dn Type=3
Dn Slope=0.005

--- StreamM065.g01 (geometry) ---

Geom Title=Existing Conditions

River Reach=StreamM065,Reach-1
Reach XY= 30
      2494975.00     13864575.00      2495022.16     13864567.24
      2495027.31     13864481.01      2495072.65     13864419.03
      2495077.36     13864330.98      2495123.78     13864264.50
      2495122.76     13863880.93      2495031.10     13863727.19
      2495016.86     13863668.94      2494833.14     13863481.06
      2494818.90     13863422.81      2494779.16     13863373.28
      2494768.92     13863322.80      2494729.19     13863273.26
      2494719.17     13863222.70      2494585.43     13863084.78
      2494574.21     13863040.07      2494576.88     13862980.71
      2494594.42     13862954.46      2494626.40     13862928.88
      2494684.66     13862914.21      2494816.86     13862781.06
      2494870.84     13862673.28      2494881.08     13862622.80
      2494920.84     13862573.28      2494931.12     13862522.82
      2494971.33     13862473.42      2494972.83     13862380.98
      2494925.51     13862309.79      2494925.00     13862125.00

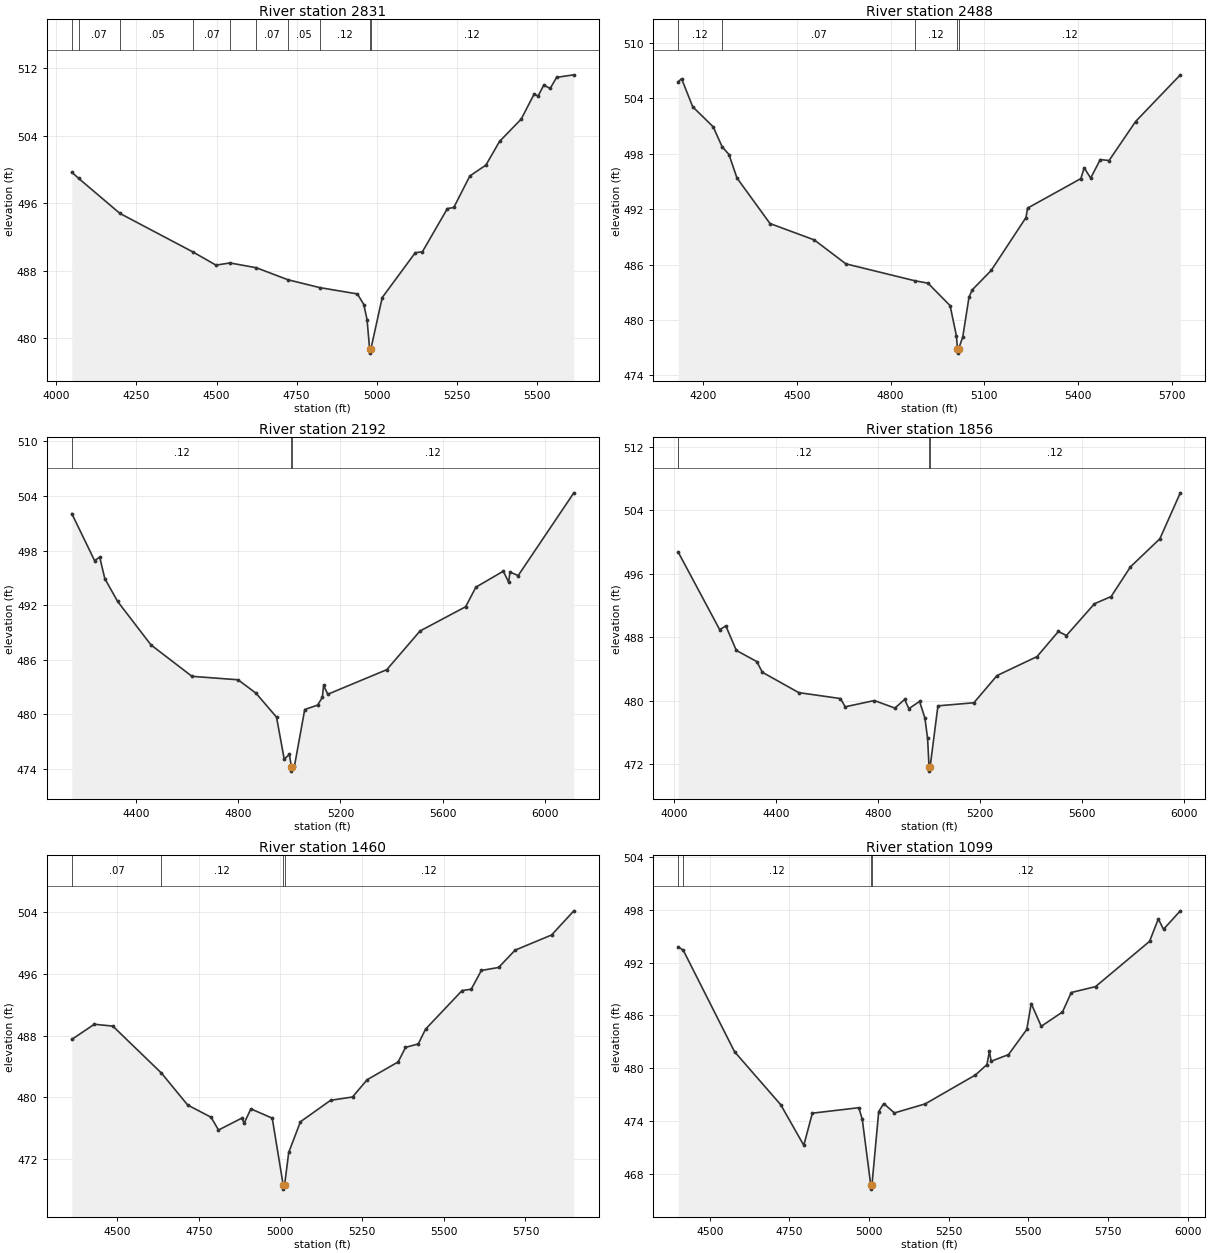
Type RM Length L Ch R = 1,2831,343,343,343
BEGIN DESCRIPTION:
H21463
END DESCRIPTION:
XS GIS Cut Line= 2
      2495973.87     13864459.29      2494411.39     13864589.50
#Sta/Elev= 30
  4047.9  499.68  4069.2  498.95  4198.3  494.78  4426.0  490.21  4498.3  488.64
  4541.9  488.90  4624.2  488.33  4723.3  486.90  4822.5  485.97  4939.9  485.22
  4959.9  483.96  4970.0  482.18  4978.0  478.69  4978.2  478.19  4982.0  478.69
  5017.4  484.79  5120.5  490.11  5142.9  490.23  5220.8  495.35  5240.9  495.49
  5291.1  499.23  5341.2  500.52  5383.7  503.33  5451.6  505.99  5491.8  508.96
  5504.1  508.72  5521.9  510.02  5541.9  509.62  5562.0  510.94  5615.8  511.24
#Mann=10,-1,0
  4047.9    0.12       0  4069.2    0.07       0  4198.3    0.05       0
  4426.0    0.07       0  4541.9    0.05       0  4624.2    0.07       0
  4723.3    0.05       0  4822.5    0.12       0  4978.0    0.05       0
  4982.0    0.12       0
Bank Sta=4978,4982
Exp/Cntr=0.3,0.1

Type RM Length L Ch R = 1,2488,296,296,296
BEGIN DESCRIPTION:
H21462
END DESCRIPTION:
XS GIS Cut Line= 3
      2495995.59     13864103.39      2494993.02     13864246.62
      2494415.74     13864381.17
#Sta/Elev= 30
  4121.0  505.79  4131.7  506.11  4167.4  503.07  4232.7  500.91  4261.3  498.75
  4283.2  497.91  4308.8  495.37  4414.5  490.44  4556.0  488.67  4657.0  486.08
  4877.5  484.25  4919.6  483.99  4990.3  481.56  5010.5  478.30  5013.9  476.92
  5014.2  476.42  5017.9  476.92  5030.7  478.15  5050.9  482.49  5061.0  483.26
  5121.6  485.36  5233.0  491.09  5238.1  492.11  5408.4  495.30  5419.2  496.47
  5439.8  495.36  5470.6  497.36  5498.7  497.26  5583.5  501.48  5726.5  506.53
#Mann=5,-1,0
  4121.0    0.12       0  4261.3    0.07       0  4877.5    0.12       0
  5013.9    0.05       0  5017.9    0.12       0
Bank Sta=5013.9,5017.9
Exp/Cntr=0.3,0.1

Type RM Length L Ch R = 1,2192,336,336,336
BEGIN DESCRIPTION:
H21461
END DESCRIPTION:
XS GIS Cut Line= 3
      2495973.94     13863877.69      2494606.73     13863964.50
      2494042.51     13864146.78
#Sta/Elev= 30
  4149.7  502.07  4238.8  496.90  4258.9  497.27  4278.9  494.91  4329.0  492.40
  4459.3  487.62  4619.6  484.16  4799.9  483.78  4870.1  482.30  4950.2  479.67
  4980.3  475.05  5000.4  475.57  5008.4  474.23  5008.6  473.73  5012.4  474.23
  5020.4  474.30  5060.5  480.51  5110.6  480.99  5129.3  481.84  5134.3  483.17
  5150.7  482.19  5381.1  484.89  5511.4  489.15  5689.6  491.82  5729.6  493.97
  5836.8  495.73  5857.7  494.52  5862.9  495.63  5895.0  495.25  6112.6  504.35
#Mann=3,-1,0
  4149.7    0.12       0  5008.4    0.05       0  5012.4    0.12       0
Bank Sta=5008.4,5012.4
Exp/Cntr=0.3,0.1

Type RM Length L Ch R = 1,1856,396,396,396
BEGIN DESCRIPTION:
H21460
END DESCRIPTION:
XS GIS Cut Line= 3
      2495947.85     13863743.14      2495170.97     13863582.55
      2494048.40     13863929.29
#Sta/Elev= 30
  4016.4  498.74  4178.8  488.96  4203.1  489.43  4244.0  486.34  4324.4  484.93
  4346.1  483.58  4489.0  481.01  4652.4  480.26  4670.9  479.22  4785.2  480.01
  4865.9  479.06  4903.8  480.15  4920.6  478.99  4962.5  479.90  4983.4  477.80
  4993.9  475.22  4999.7  471.60  5000.0  471.10  5003.7  471.60  5034.4  479.34
  5175.4  479.73  5266.0  483.16  5423.0  485.56  5506.7  488.73  5538.1  488.22
  5648.1  492.23  5713.4  493.14  5789.3  496.89  5904.4  500.43  5984.6  506.23
#Mann=3,-1,0
  4016.4    0.12       0  4999.7    0.05       0  5003.7    0.12       0
Bank Sta=4999.7,5003.7
Exp/Cntr=0.3,0.1

Type RM Length L Ch R = 1,1460,361,361,361
BEGIN DESCRIPTION:
H21459
END DESCRIPTION:
XS GIS Cut Line= 3
      2495292.48     13862957.56      2494606.73     13863439.32
      2493981.76     13863751.81
#Sta/Elev= 30
  4361.3  487.50  4430.3  489.47  4486.9  489.23  4635.6  483.15  4716.1  479.00
  4787.6  477.42  4810.4  475.76  4882.5  477.32  4888.6  476.62  4909.5  478.50
  4974.9  477.30  5008.6  468.60  5008.9  468.10  5012.6  468.60  5025.4  472.86
  5061.2  476.83  5153.5  479.61  5220.6  480.04  5265.4  482.28  5360.4  484.59
  5382.8  486.47  5421.9  486.92  5444.3  488.84  5556.1  493.84  5584.0  494.01
  5615.0  496.44  5667.9  496.83  5718.2  499.07  5830.0  501.04  5898.1  504.17
#Mann=4,-1,0
  4361.3    0.07       0  4635.6    0.12       0  5008.6    0.05       0
  5012.6    0.12       0
Bank Sta=5008.6,5012.6
Exp/Cntr=0.3,0.1

Type RM Length L Ch R = 1,1099,511,511,511
BEGIN DESCRIPTION:
H21458
END DESCRIPTION:
XS GIS Cut Line= 3
      2495149.29     13862870.74      2494294.23     13863118.14
      2493690.98     13863443.64
#Sta/Elev= 30
  4401.3  493.76  4416.8  493.41  4578.0  481.89  4722.9  475.88  4795.3  471.28
  4822.2  474.92  4967.9  475.54  4978.9  474.22  5005.3  466.81  5005.6  466.31
  5009.3  466.81  5030.4  475.10  5046.1  476.01  5079.7  474.95  5176.1  475.97
  5333.9  479.25  5370.1  480.43  5377.7  481.92  5383.4  480.81  5437.7  481.56
  5495.1  484.41  5509.0  487.35  5540.5  484.77  5607.1  486.39  5634.7  488.60
  5710.9  489.27  5880.4  494.40  5907.9  496.94  5924.2  495.77  5976.9  497.86
#Mann=4,-1,0
  4401.3    0.07       0  4416.8    0.12       0  5005.3    0.05       0
  5009.3    0.12       0
Bank Sta=5005.3,5009.3
Exp/Cntr=0.3,0.1

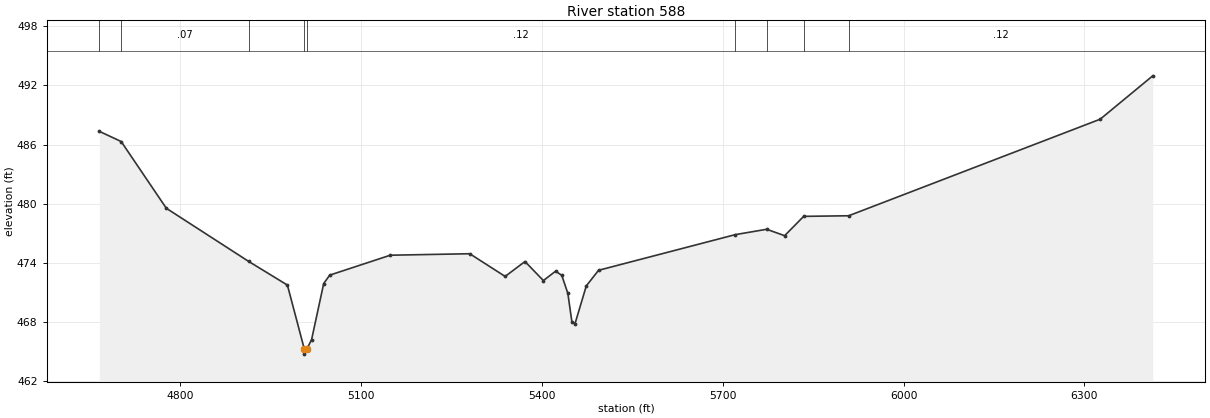
Type RM Length L Ch R = 1,588,0,0,0
BEGIN DESCRIPTION:
H21457
END DESCRIPTION:
XS GIS Cut Line= 4
      2495205.73     13862636.37      2494697.88     13862679.78
      2494111.94     13862788.28      2493656.24     13863239.64
#Sta/Elev= 30
  4666.3  487.35  4702.5  486.32  4777.4  479.55  4913.7  474.17  4978.2  471.76
  5006.3  465.26  5006.5  464.76  5010.3  465.26  5018.3  466.23  5038.4  471.92
  5048.4  472.77  5148.8  474.79  5280.6  474.94  5339.3  472.64  5372.2  474.15
  5402.7  472.22  5423.0  473.17  5433.2  472.75  5443.3  470.92  5450.1  467.99
  5455.2  467.85  5473.9  471.68  5494.2  473.26  5721.2  476.88  5773.1  477.42
  5802.8  476.77  5834.4  478.73  5909.0  478.79  6326.1  488.58  6413.3  492.98
#Mann=9,-1,0
  4666.3    0.05       0  4702.5    0.07       0  4913.7    0.12       0
  5006.3    0.05       0  5010.3    0.12       0  5721.2    0.07       0
  5773.1    0.12       0  5834.4    0.07       0  5909.0    0.12       0
Bank Sta=5006.3,5010.3
Exp/Cntr=0.3,0.1

Chan Stop Cuts=-1