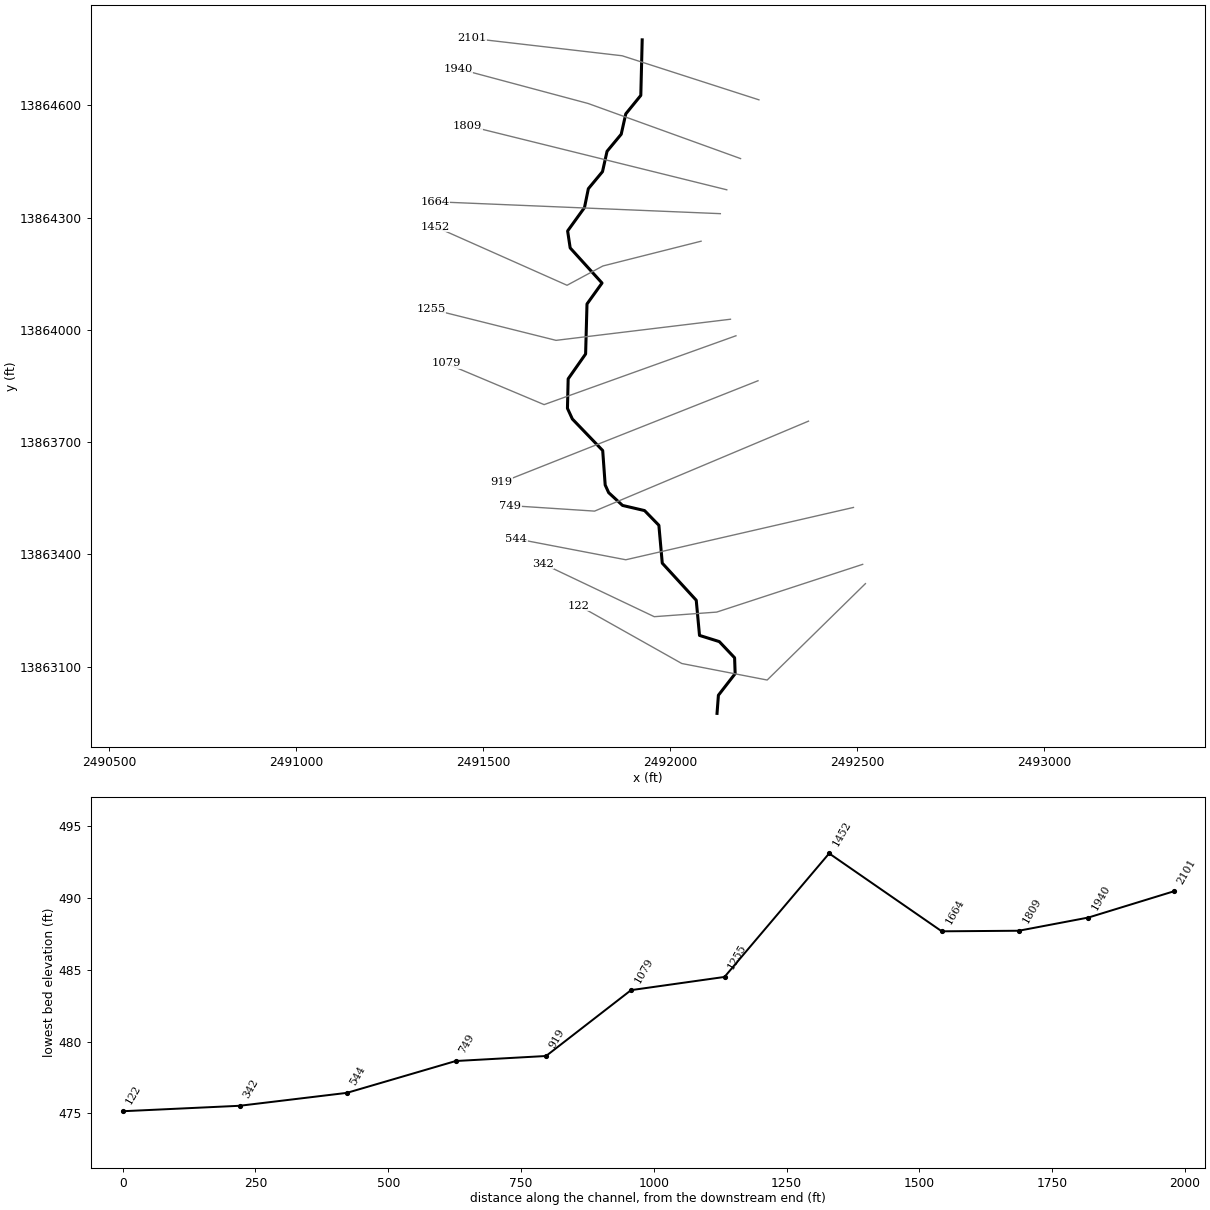
--- StreamM066.prj (project) ---

Proj Title=StreamM066 Base Level Engineering
Current Plan=p01
Default Exp/Contr=0.3,0.1
English Units
Geom File=g01
Flow File=f01
Plan File=p01
BEGIN DESCRIPTION:
StreamM066
END DESCRIPTION:

--- StreamM066.p01 (plan) ---

Plan Title=Multiple Run
Short Identifier=Multiple
Geom File=g01
Flow File=f01
Subcritical Flow
K Sum by GR= 0
Std Step Tol= 0.01
Critical Tol= 0.01
Num of Std Step Trials= 20
Max Error Tol= 0.3
Flow Tol Ratio= 0.001
Split Flow NTrial= 30
Split Flow Tol= 0.02
Split Flow Ratio= 0.02
Log Output Level= 0
Friction Slope Method= 1
Unsteady Friction Slope Method= 2
Unsteady Bridges Friction Slope Method= 1
Parabolic Critical Depth
Global Vel Dist=  1 , 1 , 1
Global Log Level= 0
CheckData=True
Encroach Param= -1, 0, 0, 0
BEGIN DESCRIPTION:
Multiple Run
END DESCRIPTION:

--- StreamM066.f01 (steady flow) ---

Flow Title=Multiple
Number of Profiles=7
Profile Names=10-year,25-year,50-year,1pct_min,100-year,1pct_plu,500-year
River Rch & RM= StreamM066,Reach-1,2101
     325     500     651     413     823    1643    1298
Boundary for River Rch & Prof#=StreamM066,Reach-1,1
Up Type=0
Dn Type=3
Dn Slope=0.005
Boundary for River Rch & Prof#=StreamM066,Reach-1,2
Up Type=0
Dn Type=3
Dn Slope=0.005
Boundary for River Rch & Prof#=StreamM066,Reach-1,3
Up Type=0
Dn Type=3
Dn Slope=0.005
Boundary for River Rch & Prof#=StreamM066,Reach-1,4
Up Type=0
Dn Type=3
Dn Slope=0.005
Boundary for River Rch & Prof#=StreamM066,Reach-1,5
Up Type=0
Dn Type=3
Dn Slope=0.005
Boundary for River Rch & Prof#=StreamM066,Reach-1,6
Up Type=0
Dn Type=3
Dn Slope=0.005
Boundary for River Rch & Prof#=StreamM066,Reach-1,7
Up Type=0
Dn Type=3
Dn Slope=0.005

--- StreamM066.g01 (geometry) ---

Geom Title=Existing Conditions

River Reach=StreamM066,Reach-1
Reach XY= 30
      2491925.00     13864775.00      2491921.28     13864626.54
      2491881.12     13864577.18      2491868.92     13864522.80
      2491831.08     13864477.20      2491818.92     13864422.80
      2491781.08     13864377.20      2491770.78     13864326.72
      2491725.70     13864264.30      2491732.52     13864218.94
      2491817.67     13864125.10      2491777.48     13864069.14
      2491773.77     13863935.51      2491727.16     13863869.02
      2491725.25     13863790.22      2491738.37     13863761.71
      2491819.46     13863677.42      2491826.10     13863585.33
      2491835.39     13863564.90      2491872.45     13863530.75
      2491931.35     13863516.97      2491969.58     13863477.67
      2491978.63     13863376.50      2492069.44     13863277.36
      2492078.19     13863183.35      2492131.08     13863166.82
      2492171.95     13863123.58      2492173.41     13863081.13
      2492128.69     13863023.51      2492125.00     13862975.00

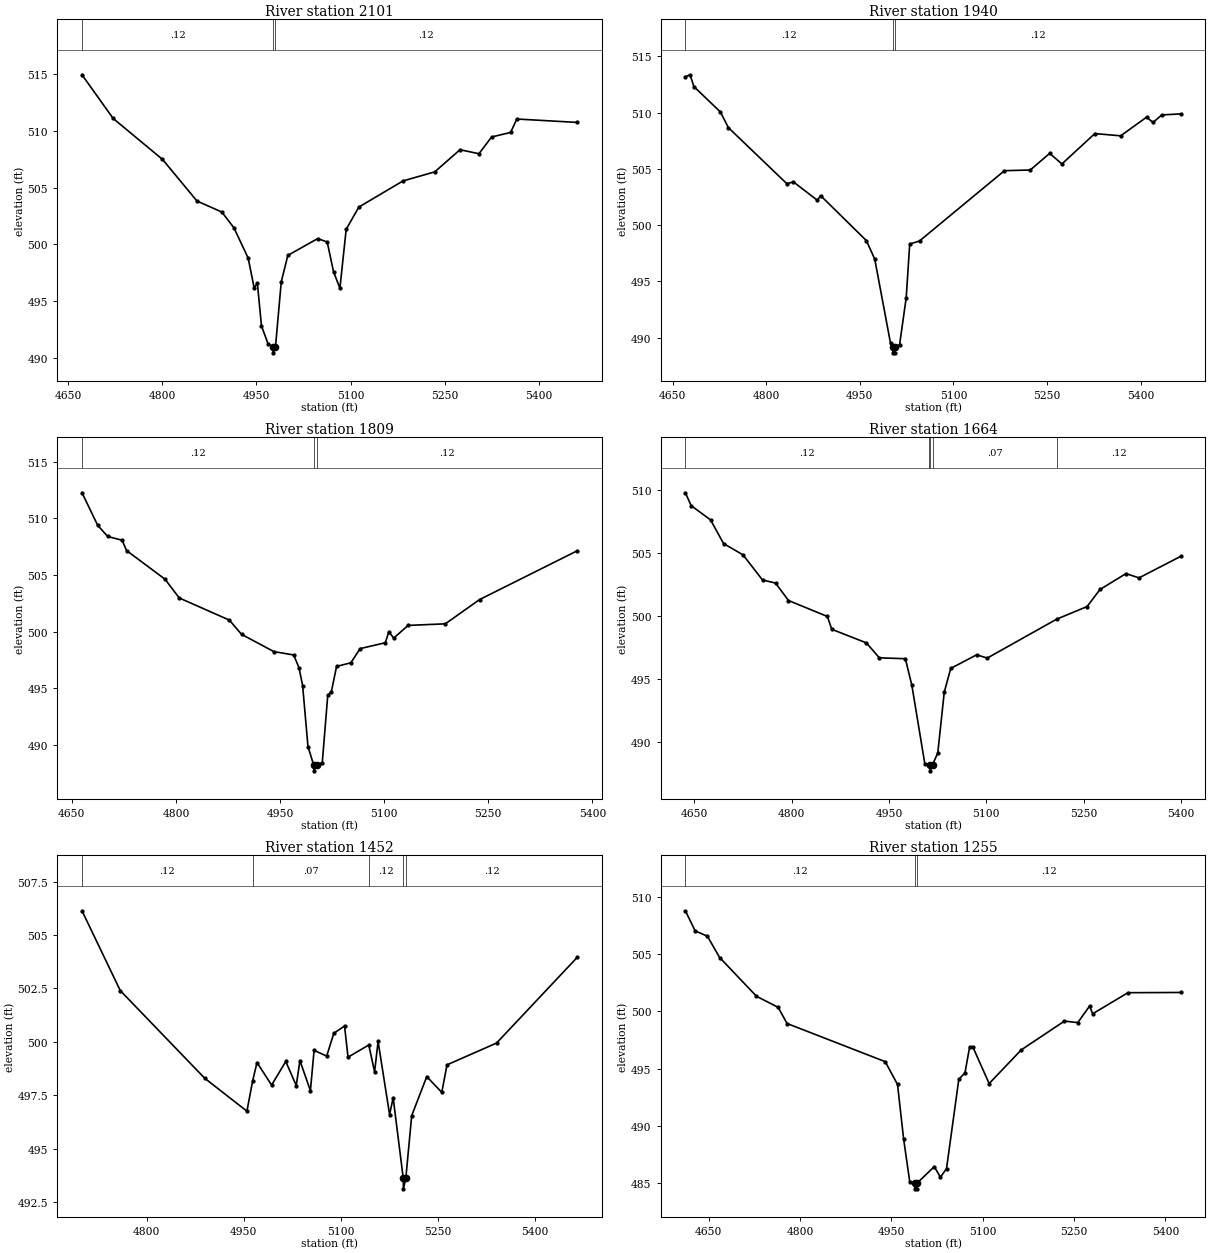
Type RM Length L Ch R = 1,2101,161,161,161
BEGIN DESCRIPTION:
H21475
END DESCRIPTION:
XS GIS Cut Line= 3
      2492236.99     13864614.72      2491871.37     13864732.51
      2491469.49     13864779.07
#Sta/Elev= 30
  4672.4  514.92  4722.0  511.08  4800.6  507.48  4855.5  503.82  4895.1  502.85
  4914.4  501.46  4937.1  498.79  4946.5  496.19  4951.7  496.58  4958.2  492.84
  4968.7  491.26  4976.5  490.97  4976.8  490.47  4980.5  490.97  4989.7  496.71
  5000.2  499.04  5047.9  500.52  5062.9  500.21  5073.0  497.60  5083.1  496.15
  5093.1  501.33  5113.3  503.29  5183.7  505.59  5234.1  506.38  5274.3  508.33
  5304.5  507.98  5324.7  509.45  5354.9  509.85  5364.9  511.03  5461.1  510.73
#Mann=3,-1,0
  4672.4    0.12       0  4976.5    0.05       0  4980.5    0.12       0
Bank Sta=4976.5,4980.5
Exp/Cntr=0.3,0.1

Type RM Length L Ch R = 1,1940,131,131,131
BEGIN DESCRIPTION:
H21474
END DESCRIPTION:
XS GIS Cut Line= 3
      2492187.87     13864457.72      2491780.59     13864604.93
      2491432.21     13864698.15
#Sta/Elev= 30
  4670.5  513.20  4678.0  513.37  4684.2  512.32  4726.7  510.06  4739.4  508.67
  4833.0  503.69  4843.7  503.84  4882.0  502.21  4887.3  502.62  4960.6  498.62
  4974.0  496.97  4999.3  489.48  5002.7  489.14  5002.9  488.64  5006.4  488.64
  5006.7  489.14  5013.8  489.37  5024.4  493.55  5030.0  498.31  5045.7  498.59
  5181.8  504.84  5223.2  504.90  5254.3  506.38  5273.9  505.44  5326.7  508.14
  5368.1  507.94  5409.6  509.60  5419.9  509.13  5434.0  509.80  5464.2  509.89
#Mann=3,-1,0
  4670.5    0.12       0  5002.7    0.05       0  5006.7    0.12       0
Bank Sta=5002.7,5006.7
Exp/Cntr=0.3,0.1

Type RM Length L Ch R = 1,1809,145,145,145
BEGIN DESCRIPTION:
H21473
END DESCRIPTION:
XS GIS Cut Line= 2
      2492151.06     13864374.30      2491458.34     13864545.64
#Sta/Elev= 30
  4664.6  512.27  4687.3  509.39  4701.7  508.41  4722.4  508.08  4728.8  507.17
  4784.2  504.64  4804.8  502.98  4876.9  501.03  4894.5  499.77  4941.0  498.25
  4969.6  497.95  4977.3  496.82  4982.5  495.24  4990.2  489.86  4998.5  488.22
  4998.7  487.72  5002.5  488.22  5010.8  488.45  5018.7  494.39  5023.9  494.71
  5031.4  496.94  5052.0  497.26  5065.3  498.51  5101.6  499.03  5106.7  499.99
  5113.8  499.44  5134.4  500.56  5188.1  500.70  5237.4  502.84  5378.2  507.15
#Mann=3,-1,0
  4664.6    0.12       0  4998.5    0.05       0  5002.5    0.12       0
Bank Sta=4998.5,5002.5
Exp/Cntr=0.3,0.1

Type RM Length L Ch R = 1,1664,212,212,212
BEGIN DESCRIPTION:
H21472
END DESCRIPTION:
XS GIS Cut Line= 2
      2492133.85     13864310.50      2491370.82     13864342.40
#Sta/Elev= 30
  4636.1  509.80  4645.0  508.78  4675.0  507.64  4695.0  505.76  4725.0  504.86
  4755.1  502.86  4775.1  502.62  4795.1  501.23  4855.1  499.96  4861.8  498.94
  4915.2  497.86  4935.2  496.67  4975.3  496.60  4985.3  494.49  5005.3  488.25
  5011.3  488.20  5013.3  488.18  5013.5  487.68  5017.3  488.18  5025.3  489.10
  5035.3  493.94  5045.3  495.83  5085.3  496.91  5101.6  496.65  5208.8  499.75
  5255.5  500.75  5275.5  502.11  5315.5  503.37  5335.6  503.03  5399.8  504.74
#Mann=5,-1,0
  4636.1    0.12       0  5011.3    0.07       0  5013.3    0.05       0
  5017.3    0.07       0  5208.8    0.12       0
Bank Sta=5013.3,5017.3
Exp/Cntr=0.3,0.1

Type RM Length L Ch R = 1,1452,197,197,197
BEGIN DESCRIPTION:
H21471
END DESCRIPTION:
XS GIS Cut Line= 4
      2492082.39     13864236.90      2491819.85     13864170.65
      2491724.16     13864119.13      2491370.84     13864276.16
#Sta/Elev= 30
  4699.9  506.14  4759.1  502.40  4889.8  498.29  4955.0  496.75  4963.8  498.16
  4970.6  499.03  4993.2  497.97  5015.1  499.08  5031.3  497.95  5037.0  499.12
  5053.2  497.71  5058.9  499.60  5078.4  499.33  5089.4  500.40  5106.0  500.74
  5111.4  499.28  5143.5  499.85  5152.5  498.59  5157.9  500.02  5175.7  496.59
  5181.2  497.38  5196.8  493.61  5197.1  493.11  5200.8  493.61  5209.9  496.54
  5233.2  498.37  5256.4  497.63  5264.5  498.92  5341.1  499.94  5466.0  503.96
#Mann=5,-1,0
  4699.9    0.12       0  4963.8    0.07       0  5143.5    0.12       0
  5196.8    0.05       0  5200.8    0.12       0
Bank Sta=5196.8,5200.8
Exp/Cntr=0.3,0.1

Type RM Length L Ch R = 1,1255,176,176,176
BEGIN DESCRIPTION:
H21470
END DESCRIPTION:
XS GIS Cut Line= 3
      2492160.93     13864028.35      2491694.72     13863971.91
      2491361.01     13864055.34
#Sta/Elev= 30
  4611.5  508.77  4627.5  507.02  4647.7  506.55  4667.8  504.69  4728.3  501.31
  4763.9  500.34  4778.6  498.93  4939.8  495.60  4960.0  493.61  4970.0  488.86
  4980.1  485.11  4988.2  485.00  4988.4  484.50  4991.9  484.50  4992.2  485.00
  5020.4  486.44  5030.5  485.51  5040.5  486.27  5060.7  494.07  5070.8  494.62
  5078.5  496.90  5083.6  496.90  5110.5  493.69  5163.3  496.63  5234.2  499.14
  5256.1  499.01  5275.5  500.45  5280.6  499.78  5338.5  501.62  5425.1  501.64
#Mann=3,-1,0
  4611.5    0.12       0  4988.2    0.05       0  4992.2    0.12       0
Bank Sta=4988.2,4992.2
Exp/Cntr=0.3,0.1

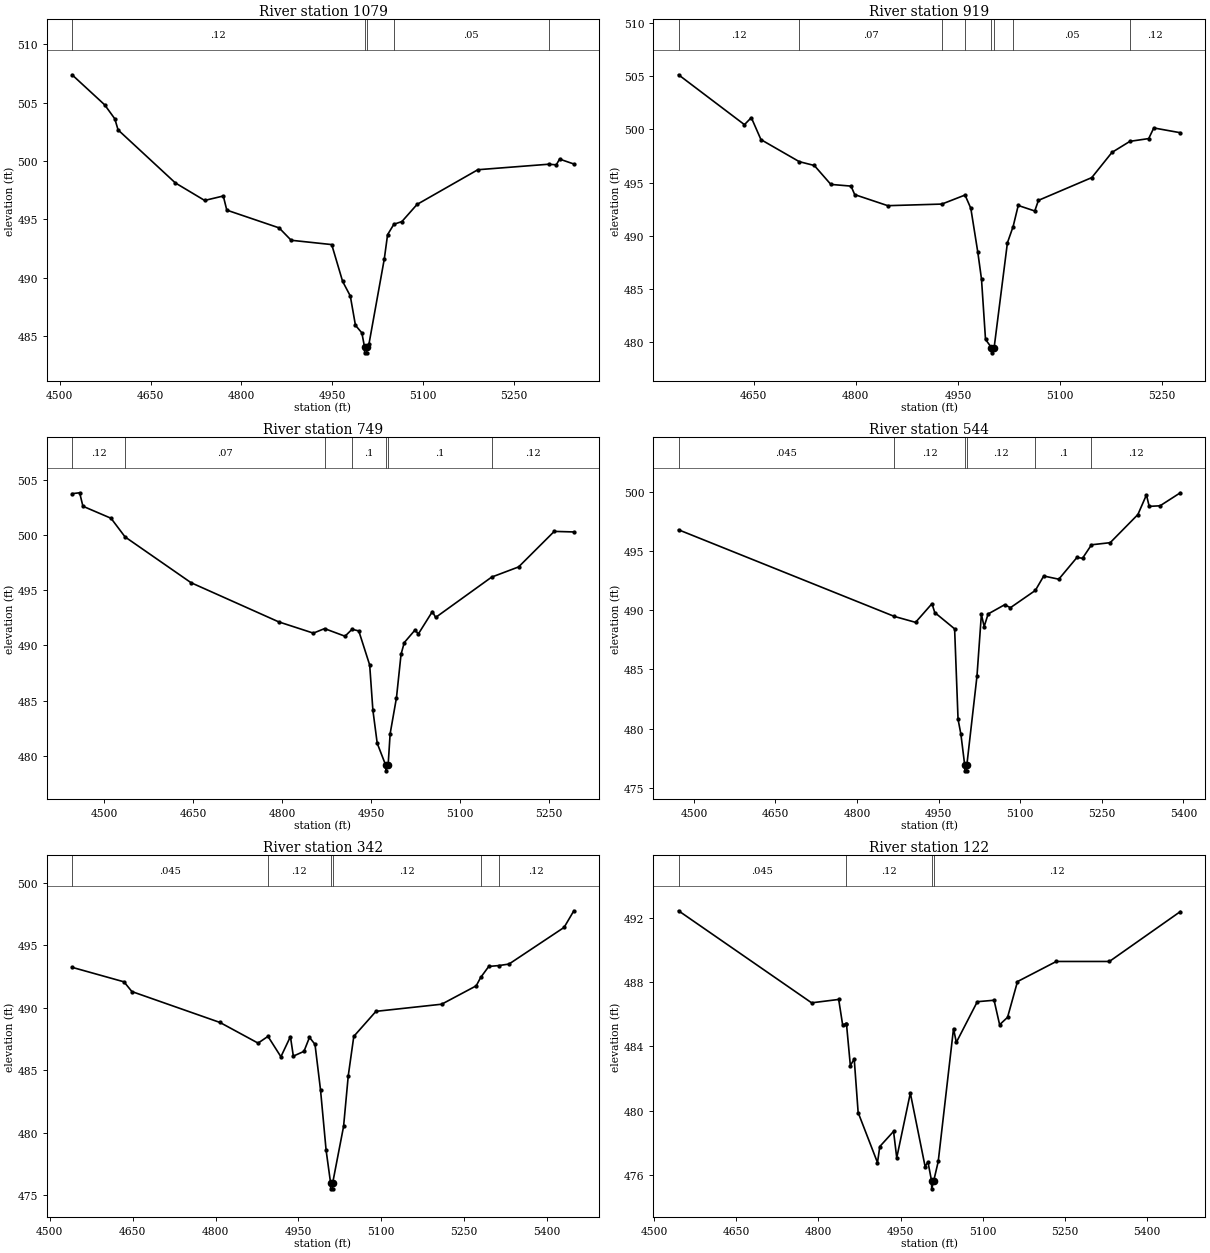
Type RM Length L Ch R = 1,1079,160,160,160
BEGIN DESCRIPTION:
H21469
END DESCRIPTION:
XS GIS Cut Line= 3
      2492175.61     13863984.18      2491662.82     13863800.17
      2491400.94     13863910.30
#Sta/Elev= 30
  4520.4  507.39  4574.2  504.82  4591.0  503.62  4596.4  502.67  4691.0  498.13
  4739.4  496.63  4770.2  497.01  4776.0  495.80  4862.4  494.28  4882.3  493.22
  4949.3  492.85  4967.3  489.70  4980.0  488.45  4988.5  485.94  4999.1  485.29
  5003.5  484.08  5003.7  483.58  5007.2  483.58  5007.5  484.08  5010.8  484.32
  5036.2  491.63  5041.6  493.70  5052.0  494.59  5065.2  494.82  5090.3  496.29
  5190.7  499.26  5307.5  499.73  5320.3  499.68  5325.7  500.17  5349.3  499.75
#Mann=5,-1,0
  4520.4    0.12       0  5003.5    0.05       0  5007.5    0.12       0
  5052.0    0.05       0  5307.5    0.12       0
Bank Sta=5003.5,5007.5
Exp/Cntr=0.3,0.1

Type RM Length L Ch R = 1,919,170,170,170
BEGIN DESCRIPTION:
H21468
END DESCRIPTION:
XS GIS Cut Line= 2
      2492234.50     13863863.96      2491548.72     13863592.10
#Sta/Elev= 30
  4539.3  505.14  4636.2  500.45  4646.3  501.11  4660.5  499.04  4716.8  496.97
  4738.9  496.61  4763.2  494.83  4792.9  494.67  4798.3  493.87  4846.9  492.83
  4926.4  492.98  4960.5  493.83  4969.0  492.58  4979.3  488.44  4984.7  485.92
  4990.6  480.25  4999.3  479.49  4999.6  478.99  5003.3  479.49  5022.8  489.34
  5031.2  490.87  5038.7  492.85  5063.0  492.33  5068.4  493.33  5146.8  495.47
  5176.5  497.84  5202.9  498.88  5230.5  499.14  5238.0  500.14  5277.0  499.69
#Mann=8,-1,0
  4539.3    0.12       0  4716.8    0.07       0  4926.4    0.12       0
  4960.5     0.1       0  4999.3    0.05       0  5003.3     0.1       0
  5031.2    0.05       0  5202.9    0.12       0
Bank Sta=4999.3,5003.3
Exp/Cntr=0.3,0.1

Type RM Length L Ch R = 1,749,205,205,205
BEGIN DESCRIPTION:
H21467
END DESCRIPTION:
XS GIS Cut Line= 3
      2492369.41     13863755.99      2491797.76     13863515.56
      2491571.99     13863530.28
#Sta/Elev= 30
  4445.6  503.76  4458.4  503.84  4463.9  502.62  4511.3  501.53  4535.0  499.84
  4646.3  495.69  4794.2  492.14  4852.6  491.12  4871.5  491.53  4906.0  490.84
  4917.9  491.47  4929.2  491.32  4947.6  488.23  4953.0  484.14  4960.3  481.14
  4974.7  479.14  4975.0  478.64  4978.7  479.14  4982.1  482.00  4992.8  485.27
  5000.5  489.20  5005.9  490.26  5024.2  491.41  5029.6  491.04  5053.4  493.08
  5058.8  492.54  5153.4  496.20  5198.8  497.12  5258.9  500.34  5292.0  500.29
#Mann=7,-1,0
  4445.6    0.12       0  4535.0    0.07       0  4871.5    0.12       0
  4917.9     0.1       0  4974.7    0.05       0  4978.7     0.1       0
  5153.4    0.12       0
Bank Sta=4974.7,4978.7
Exp/Cntr=0.3,0.1

Type RM Length L Ch R = 1,544,202,202,202
BEGIN DESCRIPTION:
H21466
END DESCRIPTION:
XS GIS Cut Line= 3
      2492489.62     13863525.36      2491881.18     13863385.52
      2491588.42     13863441.63
#Sta/Elev= 30
  4471.8  496.81  4868.6  489.48  4907.5  488.98  4937.7  490.56  4942.8  489.81
  4979.3  488.43  4985.6  480.79  4990.8  479.53  4997.8  476.92  4998.1  476.42
  5001.6  476.42  5001.8  476.92  5020.4  484.43  5028.5  489.66  5033.6  488.62
  5040.9  489.69  5071.3  490.47  5081.9  490.22  5127.7  491.68  5143.1  492.90
  5170.8  492.63  5204.2  494.47  5214.4  494.40  5230.9  495.54  5265.3  495.72
  5316.2  498.10  5331.9  499.76  5337.0  498.79  5357.0  498.84  5394.2  499.94
#Mann=6,-1,0
  4471.8   0.045       0  4868.6    0.12       0  4997.8    0.05       0
  5001.8    0.12       0  5127.7     0.1       0  5230.9    0.12       0
Bank Sta=4997.8,5001.8
Exp/Cntr=0.3,0.1

Type RM Length L Ch R = 1,342,220,220,220
BEGIN DESCRIPTION:
H21465
END DESCRIPTION:
XS GIS Cut Line= 4
      2492514.21     13863373.26      2492124.08     13863245.67
      2491957.24     13863233.40      2491658.98     13863375.20
#Sta/Elev= 30
  4540.4  493.23  4634.3  492.07  4648.7  491.29  4808.1  488.82  4877.0  487.17
  4894.9  487.71  4918.3  486.08  4935.5  487.69  4940.8  486.13  4960.0  486.51
  4970.0  487.63  4980.0  487.07  4990.0  483.42  5000.1  478.60  5008.1  476.02
  5008.4  475.52  5011.9  475.52  5012.1  476.02  5031.7  480.51  5040.2  484.57
  5050.2  487.71  5090.3  489.71  5209.2  490.28  5271.7  491.75  5279.8  492.42
  5294.4  493.30  5312.7  493.37  5331.0  493.49  5430.7  496.42  5448.4  497.75
#Mann=6,-1,0
  4540.4   0.045       0  4894.9    0.12       0  5008.1    0.05       0
  5012.1    0.12       0  5279.8     0.1       0  5312.7    0.12       0
Bank Sta=5008.1,5012.1
Exp/Cntr=0.3,0.1

Type RM Length L Ch R = 1,122,0,0,0
BEGIN DESCRIPTION:
H21464
END DESCRIPTION:
XS GIS Cut Line= 4
      2492521.58     13863321.75      2492259.03     13863064.11
      2492030.85     13863108.27      2491756.09     13863262.82
#Sta/Elev= 30
  4544.8  492.42  4787.6  486.70  4837.0  486.91  4844.2  485.33  4849.5  485.38
  4851.2  485.39  4858.3  482.79  4865.3  483.22  4872.5  479.88  4907.8  476.77
  4912.0  477.77  4937.1  478.71  4942.9  477.07  4967.7  481.09  4994.7  476.52
  4999.8  476.82  5006.4  475.64  5006.7  475.14  5010.4  475.64  5018.6  476.84
  5046.5  485.10  5051.6  484.24  5089.9  486.77  5120.5  486.86  5130.6  485.34
  5145.1  485.80  5163.2  488.02  5234.0  489.27  5330.9  489.27  5460.3  492.37
#Mann=4,-1,0
  4544.8   0.045       0  4849.5    0.12       0  5006.4    0.05       0
  5010.4    0.12       0
Bank Sta=5006.4,5010.4
Exp/Cntr=0.3,0.1

Chan Stop Cuts=-1