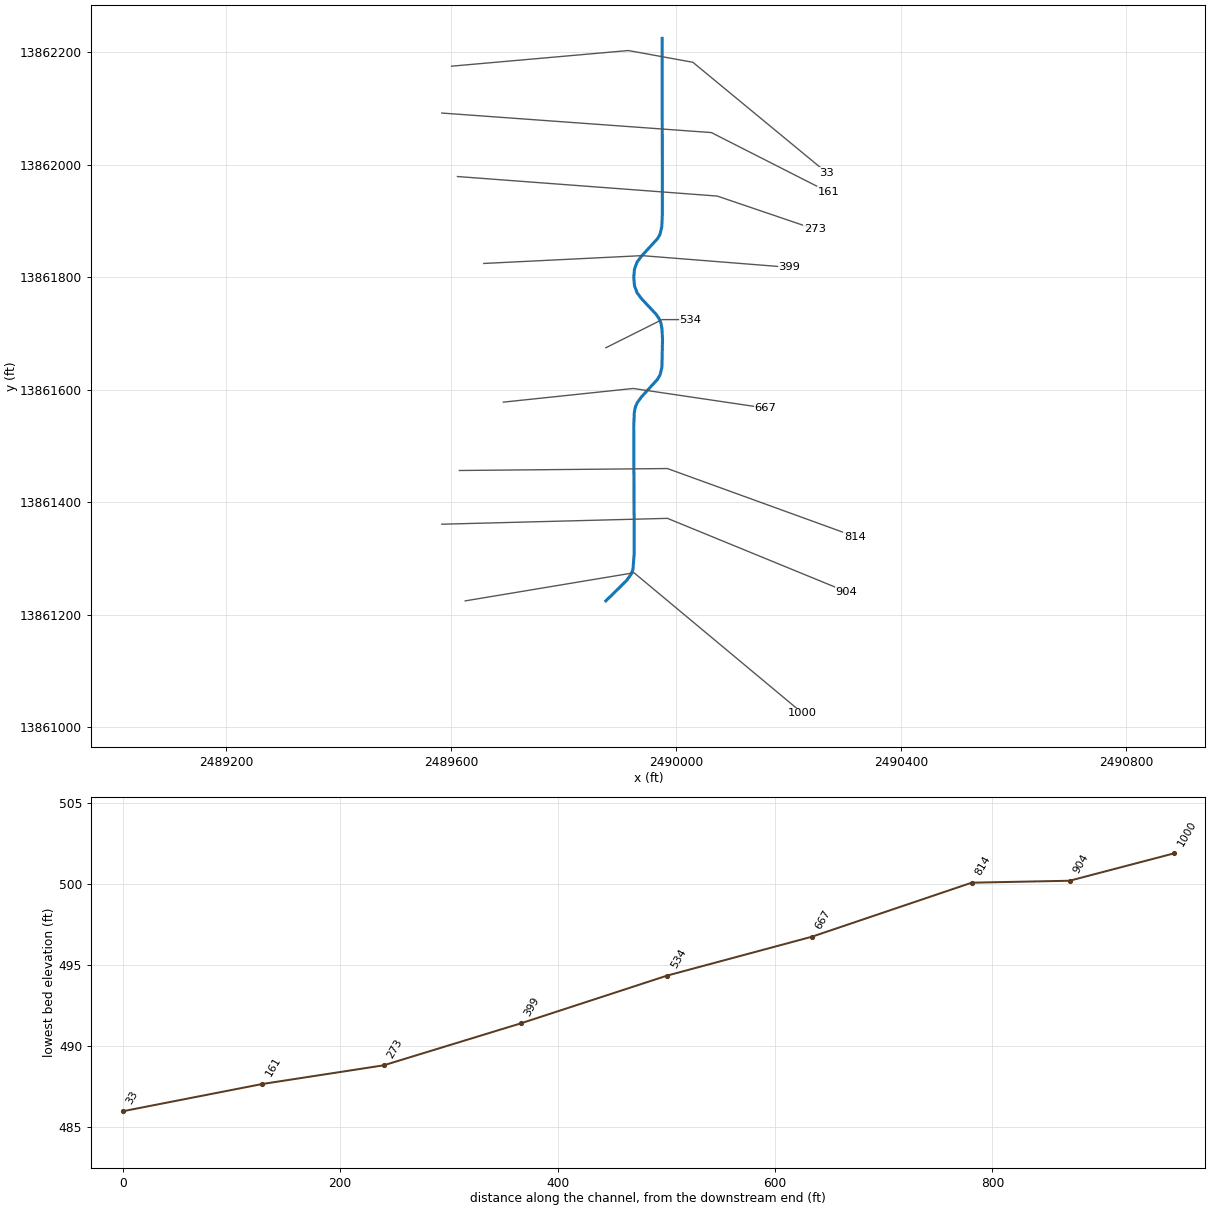
--- StreamM067.prj (project) ---

Proj Title=StreamM067 Base Level Engineering
Current Plan=p01
Default Exp/Contr=0.3,0.1
English Units
Geom File=g01
Flow File=f01
Plan File=p01
BEGIN DESCRIPTION:
StreamM067
END DESCRIPTION:

--- StreamM067.p01 (plan) ---

Plan Title=Multiple Run
Short Identifier=Multiple
Geom File=g01
Flow File=f01
Subcritical Flow
K Sum by GR= 0
Std Step Tol= 0.01
Critical Tol= 0.01
Num of Std Step Trials= 20
Max Error Tol= 0.3
Flow Tol Ratio= 0.001
Split Flow NTrial= 30
Split Flow Tol= 0.02
Split Flow Ratio= 0.02
Log Output Level= 0
Friction Slope Method= 1
Unsteady Friction Slope Method= 2
Unsteady Bridges Friction Slope Method= 1
Parabolic Critical Depth
Global Vel Dist=  1 , 1 , 1
Global Log Level= 0
CheckData=True
Encroach Param= -1, 0, 0, 0
BEGIN DESCRIPTION:
Multiple Run
END DESCRIPTION:

--- StreamM067.f01 (steady flow) ---

Flow Title=Multiple
Number of Profiles=7
Profile Names=10-year,25-year,50-year,1pct_min,100-year,1pct_plu,500-year
River Rch & RM= StreamM067,Reach-1,1000
     123     176     219     133     265     529     381
Boundary for River Rch & Prof#=StreamM067,Reach-1,1
Up Type=0
Dn Type=3
Dn Slope=0.005
Boundary for River Rch & Prof#=StreamM067,Reach-1,2
Up Type=0
Dn Type=3
Dn Slope=0.005
Boundary for River Rch & Prof#=StreamM067,Reach-1,3
Up Type=0
Dn Type=3
Dn Slope=0.005
Boundary for River Rch & Prof#=StreamM067,Reach-1,4
Up Type=0
Dn Type=3
Dn Slope=0.005
Boundary for River Rch & Prof#=StreamM067,Reach-1,5
Up Type=0
Dn Type=3
Dn Slope=0.005
Boundary for River Rch & Prof#=StreamM067,Reach-1,6
Up Type=0
Dn Type=3
Dn Slope=0.005
Boundary for River Rch & Prof#=StreamM067,Reach-1,7
Up Type=0
Dn Type=3
Dn Slope=0.005

--- StreamM067.g01 (geometry) ---

Geom Title=Existing Conditions

River Reach=StreamM067,Reach-1
Reach XY= 30
      2489875.00     13861225.00      2489912.08     13861261.49
      2489919.86     13861272.41      2489923.11     13861280.78
      2489925.41     13861309.83      2489924.55     13861535.19
      2489925.52     13861559.78      2489927.26     13861569.06
      2489930.75     13861577.34      2489938.80     13861588.15
      2489966.91     13861618.97      2489971.29     13861626.60
      2489974.62     13861640.27      2489975.70     13861690.06
      2489974.60     13861709.73      2489972.81     13861719.03
      2489969.28     13861727.32      2489964.13     13861734.65
      2489938.55     13861761.96      2489930.38     13861772.82
      2489925.77     13861785.69      2489924.60     13861800.00
      2489925.77     13861814.31      2489930.38     13861827.18
      2489938.55     13861838.04      2489966.81     13861868.92
      2489971.19     13861876.55      2489974.46     13861890.21
      2489975.45     13861914.81      2489975.00     13862225.00

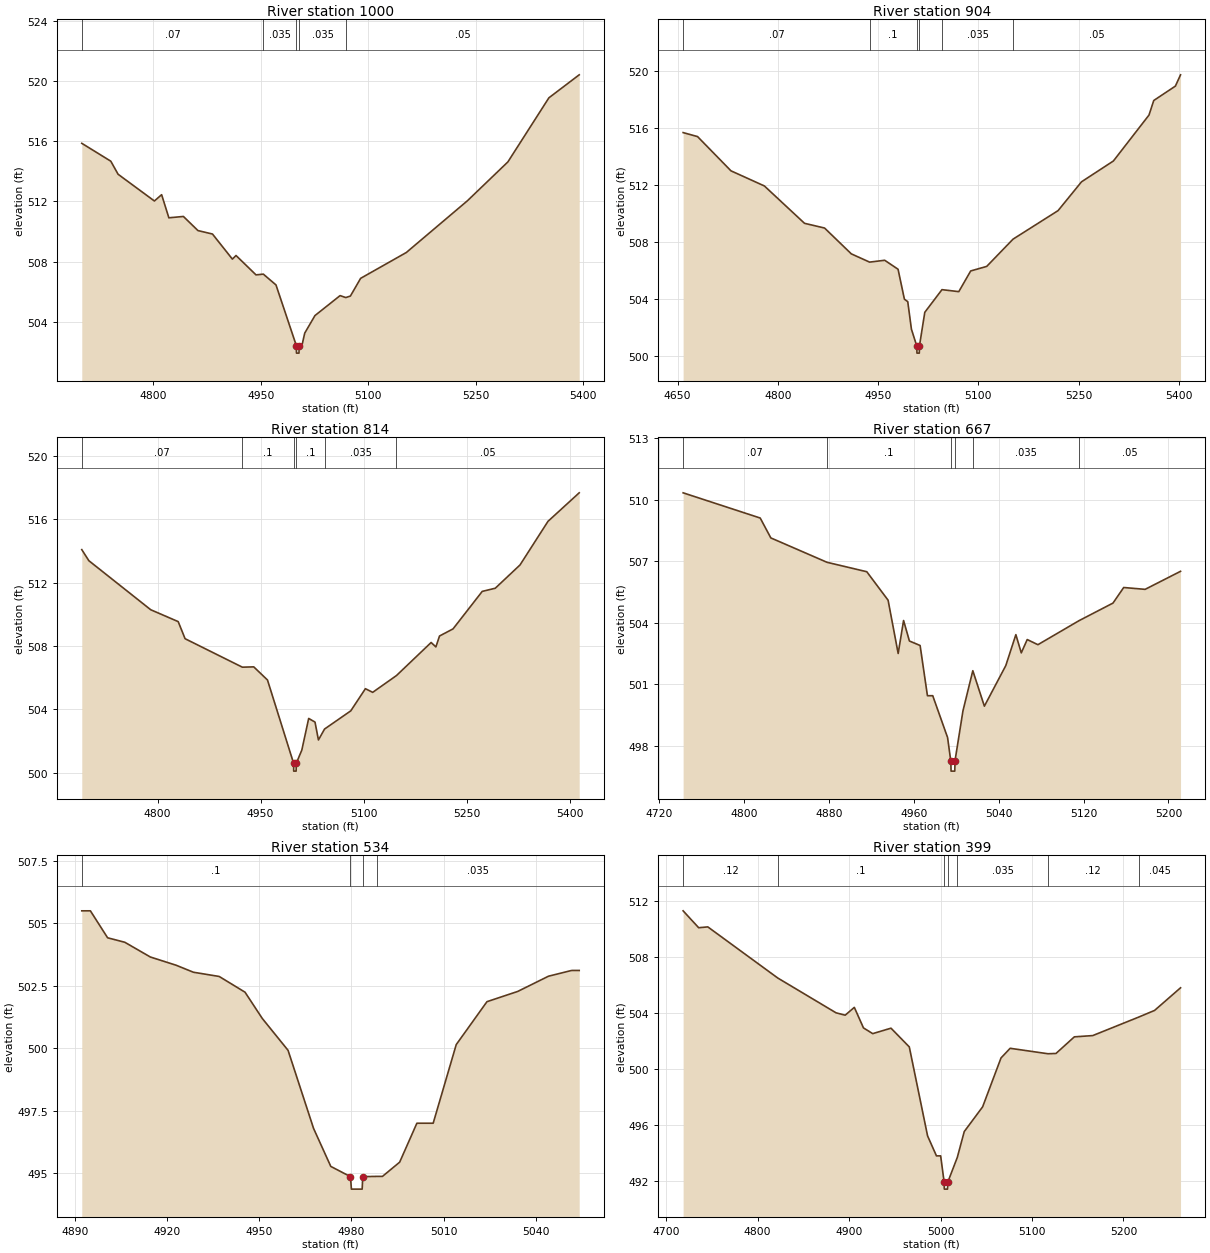
Type RM Length L Ch R = 1,1000,96,96,96
BEGIN DESCRIPTION:
StreamM067 2.0
END DESCRIPTION:
XS GIS Cut Line= 3
      2489625.02     13861225.00      2489925.00     13861275.00
      2490224.98     13861025.02
#Sta/Elev= 30
  4700.2  515.87  4740.7  514.68  4750.9  513.81  4801.6  512.03  4811.7  512.45
  4821.8  510.91  4842.1  511.00  4862.4  510.06  4882.7  509.83  4910.5  508.16
  4915.6  508.40  4943.5  507.11  4953.7  507.16  4971.4  506.44  4999.8  502.40
  5000.0  501.90  5003.5  501.90  5003.8  502.40  5007.6  502.40  5011.5  503.23
  5025.8  504.40  5060.9  505.73  5068.8  505.60  5075.3  505.70  5089.6  506.88
  5153.4  508.60  5238.6  512.04  5295.2  514.63  5352.5  518.90  5394.8  520.43
#Mann=5,-1,0
  4700.2    0.07       0  4953.7   0.035       0  4999.8   0.035       0
  5003.8   0.035       0  5068.8    0.05       0
Bank Sta=4999.8,5003.8
Exp/Cntr=0.3,0.1

Type RM Length L Ch R = 1,904,90,90,90
BEGIN DESCRIPTION:
H21482
END DESCRIPTION:
XS GIS Cut Line= 3
      2489583.41     13861361.29      2489984.43     13861371.70
      2490302.13     13861241.50
#Sta/Elev= 30
  4658.2  515.67  4679.8  515.39  4729.8  512.99  4779.8  511.93  4839.9  509.31
  4869.9  508.98  4909.9  507.17  4937.3  506.59  4959.9  506.72  4979.9  506.09
  4989.4  503.99  4994.4  503.82  4999.9  501.89  5007.9  500.71  5008.2  500.21
  5011.7  500.21  5011.9  500.71  5019.9  503.07  5045.6  504.66  5070.8  504.52
  5088.6  505.97  5112.6  506.29  5152.0  508.20  5219.4  510.20  5254.5  512.22
  5302.2  513.68  5355.5  516.90  5362.6  517.92  5395.0  518.93  5402.7  519.72
#Mann=6,-1,0
  4658.2    0.07       0  4937.3     0.1       0  5007.9    0.05       0
  5011.9     0.1       0  5045.6   0.035       0  5152.0    0.05       0
Bank Sta=5007.9,5011.9
Exp/Cntr=0.3,0.1

Type RM Length L Ch R = 1,814,147,147,147
BEGIN DESCRIPTION:
H21481
END DESCRIPTION:
XS GIS Cut Line= 3
      2489614.65     13861456.77      2489984.43     13861460.24
      2490317.69     13861339.37
#Sta/Elev= 30
  4689.7  514.09  4700.0  513.39  4790.1  510.29  4830.1  509.54  4840.1  508.46
  4923.5  506.66  4940.1  506.68  4960.1  505.85  4998.1  500.59  4998.3  500.09
  5001.8  500.09  5002.1  500.59  5010.1  501.42  5020.1  503.42  5029.3  503.19
  5034.3  502.06  5043.2  502.75  5081.4  503.90  5102.7  505.30  5113.3  505.07
  5147.9  506.13  5198.4  508.22  5205.3  507.94  5210.6  508.63  5230.3  509.08
  5272.8  511.45  5291.8  511.65  5327.8  513.12  5368.6  515.88  5414.0  517.68
#Mann=6,-1,0
  4689.7    0.07       0  4923.5     0.1       0  4998.1    0.05       0
  5002.1     0.1       0  5043.2   0.035       0  5147.9    0.05       0
Bank Sta=4998.1,5002.1
Exp/Cntr=0.3,0.1

Type RM Length L Ch R = 1,667,133,133,133
BEGIN DESCRIPTION:
H21480
END DESCRIPTION:
XS GIS Cut Line= 3
      2489692.73     13861578.30      2489923.67     13861602.60
      2490158.00     13861567.89
#Sta/Elev= 30
  4742.3  510.33  4815.0  509.10  4825.0  508.13  4878.0  506.94  4915.5  506.48
  4935.6  505.09  4945.1  502.49  4950.2  504.10  4955.7  503.10  4965.8  502.88
  4972.7  500.43  4977.7  500.43  4991.7  498.39  4994.7  497.25  4995.0  496.75
  4998.5  496.75  4998.7  497.25  5006.2  499.69  5015.5  501.65  5026.4  499.92
  5046.6  501.90  5056.1  503.41  5061.2  502.52  5066.8  503.17  5076.9  502.92
  5115.6  504.09  5147.7  504.95  5157.8  505.71  5178.0  505.62  5211.4  506.50
#Mann=6,-1,0
  4742.3    0.07       0  4878.0     0.1       0  4994.7    0.05       0
  4998.7     0.1       0  5015.5   0.035       0  5115.6    0.05       0
Bank Sta=4994.7,4998.7
Exp/Cntr=0.3,0.1

Type RM Length L Ch R = 1,534,135,135,135
BEGIN DESCRIPTION:
StreamM067 1.0
END DESCRIPTION:
XS GIS Cut Line= 3
      2489875.02     13861675.01      2489975.00     13861725.00
      2490025.02     13861725.00
#Sta/Elev= 29
  4892.3  505.50  4895.1  505.50  4900.7  504.42  4906.3  504.24  4914.6  503.65
  4923.0  503.32  4928.6  503.04  4937.0  502.87  4945.4  502.24  4951.0  501.19
  4959.4  499.91  4967.7  496.78  4973.3  495.26  4979.7  494.85  4980.0  494.35
  4983.5  494.35  4983.7  494.85  4988.2  494.86  4990.1  494.86  4995.7  495.43
  5001.3  496.99  5004.1  496.99  5006.6  496.99  5014.1  500.14  5024.1  501.86
  5034.1  502.27  5044.1  502.88  5051.6  503.11  5054.1  503.11
#Mann=4,-1,0
  4892.3     0.1       0  4979.7   0.035       0  4983.7     0.1       0
  4988.2   0.035       0
Bank Sta=4979.7,4983.7
Exp/Cntr=0.3,0.1

Type RM Length L Ch R = 1,399,126,126,126
BEGIN DESCRIPTION:
H21479
END DESCRIPTION:
XS GIS Cut Line= 3
      2489658.00     13861824.82      2489939.30     13861838.72
      2490200.73     13861817.94
#Sta/Elev= 30
  4718.5  511.31  4735.5  510.10  4745.5  510.16  4822.0  506.50  4885.7  504.01
  4895.7  503.84  4905.7  504.40  4915.7  502.93  4925.8  502.52  4945.8  502.91
  4965.8  501.57  4985.8  495.20  4995.5  493.77  5000.1  493.77  5003.9  491.89
  5004.1  491.39  5007.6  491.39  5007.9  491.89  5018.3  493.66  5025.9  495.51
  5046.0  497.28  5066.1  500.78  5076.1  501.47  5117.4  501.08  5126.2  501.10
  5146.3  502.29  5166.4  502.38  5216.5  503.70  5234.0  504.18  5262.4  505.80
#Mann=7,-1,0
  4718.5    0.12       0  4822.0     0.1       0  5003.9    0.05       0
  5007.9     0.1       0  5018.3   0.035       0  5117.4    0.12       0
  5216.5   0.045       0
Bank Sta=5003.9,5007.9
Exp/Cntr=0.3,0.1

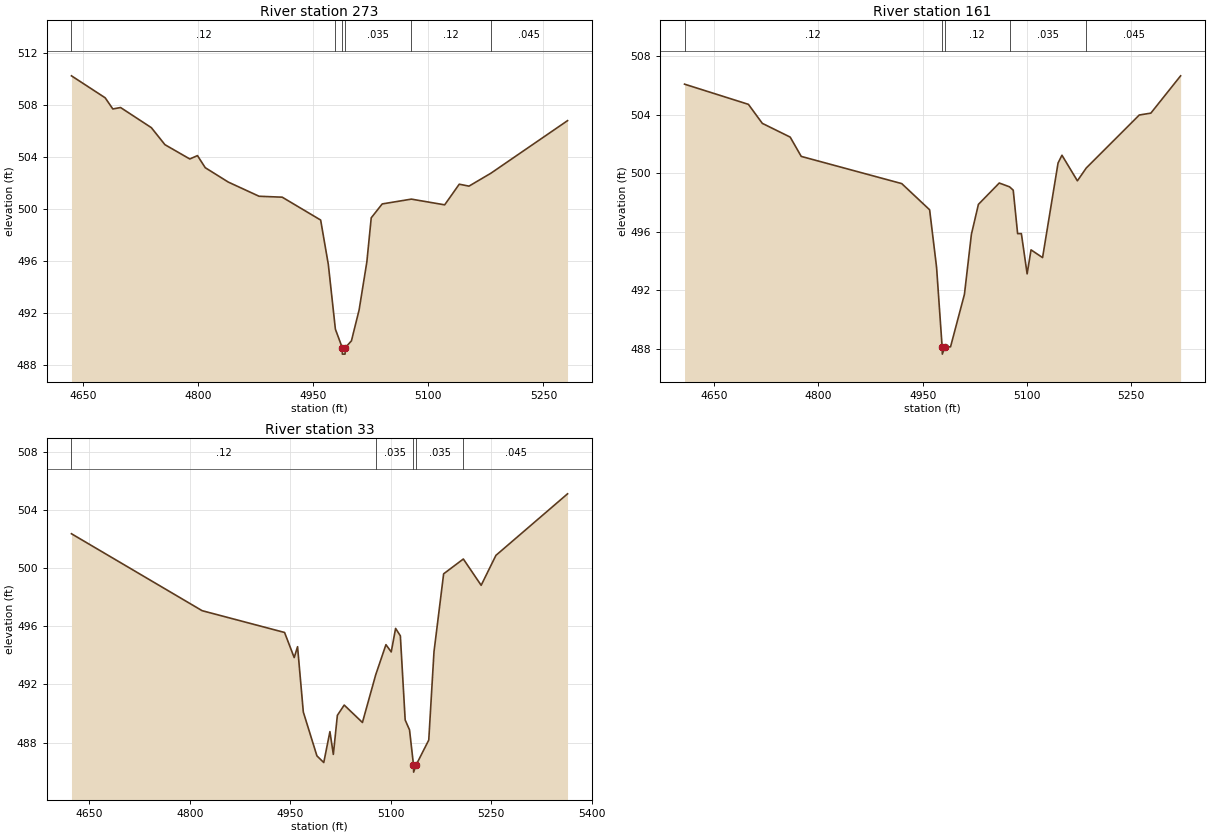
Type RM Length L Ch R = 1,273,112,112,112
BEGIN DESCRIPTION:
H21478
END DESCRIPTION:
XS GIS Cut Line= 3
      2489611.22     13861979.34      2490072.98     13861944.62
      2490246.56     13861885.60
#Sta/Elev= 30
  4635.0  510.22  4678.9  508.53  4688.9  507.67  4699.0  507.78  4739.1  506.23
  4756.8  504.92  4789.2  503.82  4799.2  504.08  4809.3  503.15  4839.4  502.04
  4879.5  500.95  4909.6  500.88  4959.7  499.12  4969.7  495.70  4978.9  490.72
  4987.8  489.30  4988.0  488.80  4991.5  488.80  4991.8  489.30  4999.8  489.82
  5009.8  492.20  5019.9  495.90  5025.6  499.29  5039.9  500.36  5077.9  500.73
  5121.3  500.29  5140.3  501.88  5153.0  501.73  5181.7  502.73  5281.4  506.77
#Mann=6,-1,0
  4635.0    0.12       0  4978.9   0.035       0  4987.8   0.035       0
  4991.8   0.035       0  5077.9    0.12       0  5181.7   0.045       0
Bank Sta=4987.8,4991.8
Exp/Cntr=0.3,0.1

Type RM Length L Ch R = 1,161,128,128,128
BEGIN DESCRIPTION:
H21477
END DESCRIPTION:
XS GIS Cut Line= 3
      2489583.35     13862092.19      2490062.56     13862057.47
      2490270.47     13861951.78
#Sta/Elev= 30
  4607.3  506.10  4699.2  504.72  4719.2  503.42  4759.3  502.48  4775.2  501.16
  4919.8  499.30  4959.9  497.51  4969.9  493.58  4977.9  488.14  4978.2  487.64
  4981.9  488.14  4990.0  488.14  5010.0  491.73  5020.0  495.83  5030.1  497.88
  5060.1  499.34  5074.9  499.08  5080.2  498.85  5086.5  495.88  5091.9  495.88
  5100.2  493.13  5105.8  494.77  5122.4  494.24  5144.7  500.71  5150.3  501.24
  5172.5  499.49  5185.3  500.37  5261.5  503.99  5278.2  504.12  5321.0  506.67
#Mann=5,-1,0
  4607.3    0.12       0  4977.9    0.05       0  4981.9    0.12       0
  5074.9   0.035       0  5185.3   0.045       0
Bank Sta=4977.9,4981.9
Exp/Cntr=0.3,0.1

Type RM Length L Ch R = 1,33,0,0,0
BEGIN DESCRIPTION:
H21476
END DESCRIPTION:
XS GIS Cut Line= 4
      2489600.71     13862175.52      2489914.99     13862203.30
      2490029.57     13862182.47      2490267.44     13861986.27
#Sta/Elev= 30
  4623.5  502.38  4818.5  497.08  4941.5  495.58  4955.9  493.85  4960.9  494.60
  4969.5  490.10  4989.8  487.08  5000.0  486.62  5009.2  488.75  5014.3  487.18
  5020.3  489.87  5030.5  490.58  5057.7  489.38  5077.5  492.66  5092.8  494.74
  5100.7  494.24  5107.2  495.86  5114.3  495.35  5121.5  489.55  5128.0  488.87
  5133.9  486.46  5134.1  485.96  5137.9  486.46  5156.7  488.17  5164.5  494.25
  5178.9  499.62  5208.3  500.64  5234.9  498.83  5256.9  500.89  5363.8  505.13
#Mann=5,-1,0
  4623.5    0.12       0  5077.5   0.035       0  5133.9    0.05       0
  5137.9   0.035       0  5208.3   0.045       0
Bank Sta=5133.9,5137.9
Exp/Cntr=0.3,0.1

Chan Stop Cuts=-1