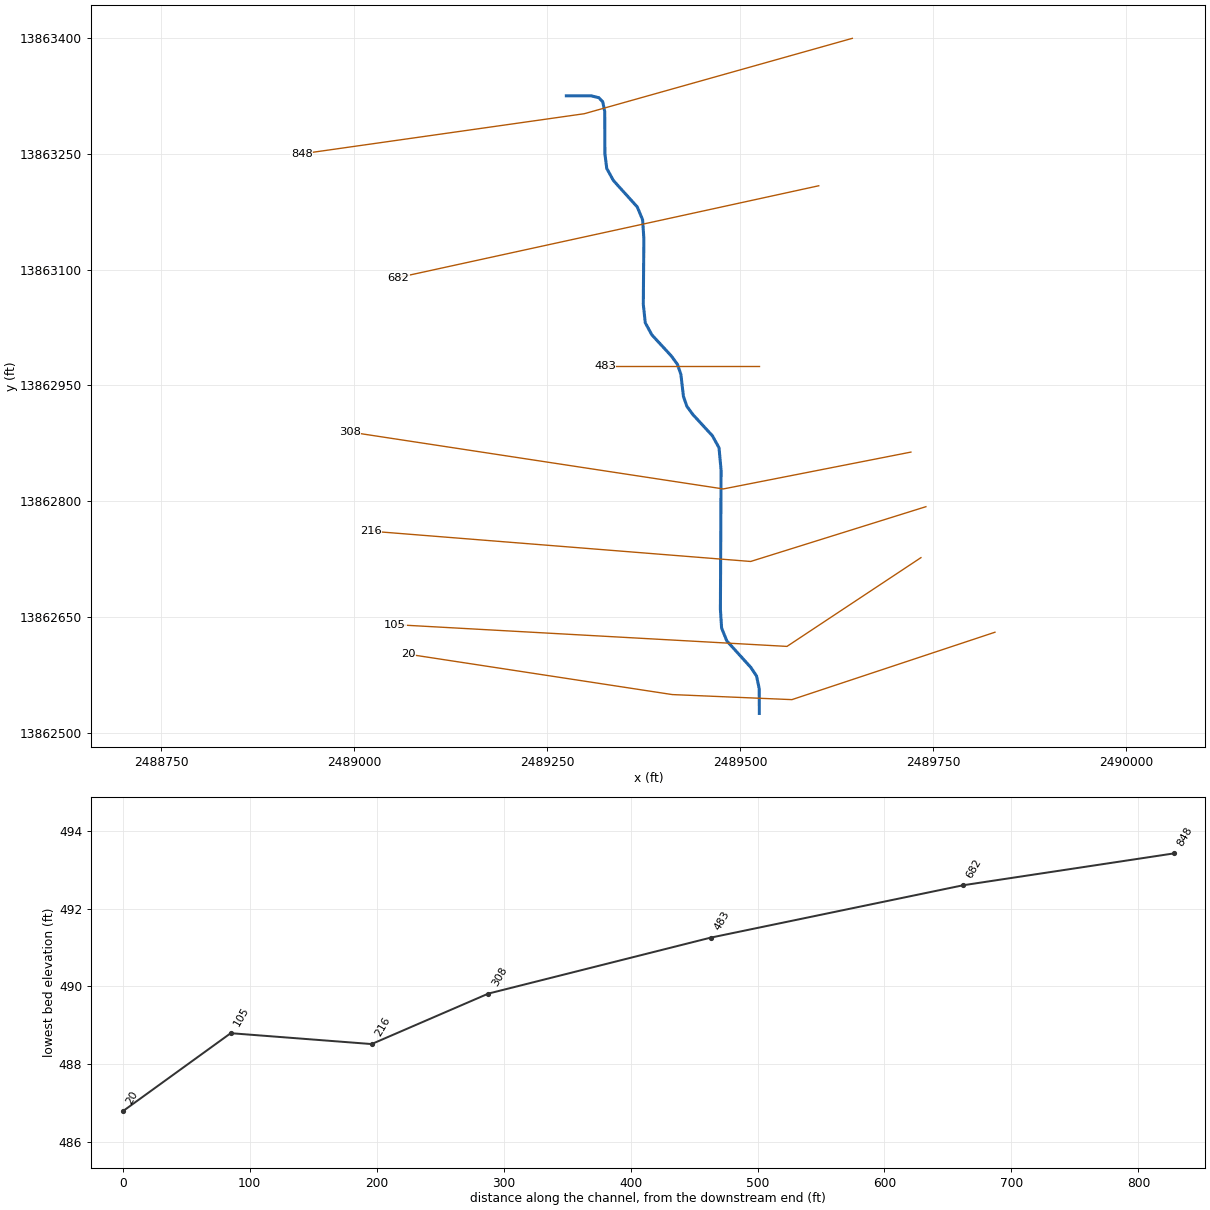
--- StreamM068.prj (project) ---

Proj Title=StreamM068 Base Level Engineering
Current Plan=p01
Default Exp/Contr=0.3,0.1
English Units
Geom File=g01
Flow File=f01
Plan File=p01
BEGIN DESCRIPTION:
StreamM068
END DESCRIPTION:

--- StreamM068.p01 (plan) ---

Plan Title=Multiple Run
Short Identifier=Multiple
Geom File=g01
Flow File=f01
Subcritical Flow
K Sum by GR= 0
Std Step Tol= 0.01
Critical Tol= 0.01
Num of Std Step Trials= 20
Max Error Tol= 0.3
Flow Tol Ratio= 0.001
Split Flow NTrial= 30
Split Flow Tol= 0.02
Split Flow Ratio= 0.02
Log Output Level= 0
Friction Slope Method= 1
Unsteady Friction Slope Method= 2
Unsteady Bridges Friction Slope Method= 1
Parabolic Critical Depth
Global Vel Dist=  1 , 1 , 1
Global Log Level= 0
CheckData=True
Encroach Param= -1, 0, 0, 0
BEGIN DESCRIPTION:
Multiple Run
END DESCRIPTION:

--- StreamM068.f01 (steady flow) ---

Flow Title=Multiple
Number of Profiles=7
Profile Names=10-year,25-year,50-year,1pct_min,100-year,1pct_plu,500-year
River Rch & RM= StreamM068,Reach-1,848
     224     336     431     269     537    1071     822
River Rch & RM= StreamM068,Reach-1,20
     650    1046    1404     914    1823    3638    3042
Boundary for River Rch & Prof#=StreamM068,Reach-1,1
Up Type=0
Dn Type=3
Dn Slope=0.005
Boundary for River Rch & Prof#=StreamM068,Reach-1,2
Up Type=0
Dn Type=3
Dn Slope=0.005
Boundary for River Rch & Prof#=StreamM068,Reach-1,3
Up Type=0
Dn Type=3
Dn Slope=0.005
Boundary for River Rch & Prof#=StreamM068,Reach-1,4
Up Type=0
Dn Type=3
Dn Slope=0.005
Boundary for River Rch & Prof#=StreamM068,Reach-1,5
Up Type=0
Dn Type=3
Dn Slope=0.005
Boundary for River Rch & Prof#=StreamM068,Reach-1,6
Up Type=0
Dn Type=3
Dn Slope=0.005
Boundary for River Rch & Prof#=StreamM068,Reach-1,7
Up Type=0
Dn Type=3
Dn Slope=0.005

--- StreamM068.g01 (geometry) ---

Geom Title=Existing Conditions

River Reach=StreamM068,Reach-1
Reach XY= 30
      2489275.00     13863325.00      2489306.90     13863325.08
      2489317.09     13863322.59      2489322.16     13863317.24
      2489324.67     13863304.80      2489324.92     13863250.08
      2489327.31     13863231.01      2489335.89     13863215.39
      2489366.86     13863181.06      2489373.77     13863164.49
      2489375.39     13863140.16      2489374.67     13863054.86
      2489377.25     13863030.93      2489385.80     13863015.33
      2489410.96     13862988.04      2489418.88     13862977.18
      2489423.33     13862964.31      2489426.67     13862935.69
      2489431.12     13862922.82      2489439.04     13862911.96
      2489464.20     13862884.67      2489472.76     13862869.07
      2489475.44     13862840.18      2489474.56     13862659.82
      2489476.12     13862635.46      2489482.89     13862618.84
      2489513.94     13862584.56      2489521.35     13862573.49
      2489524.88     13862556.80      2489525.00     13862525.00

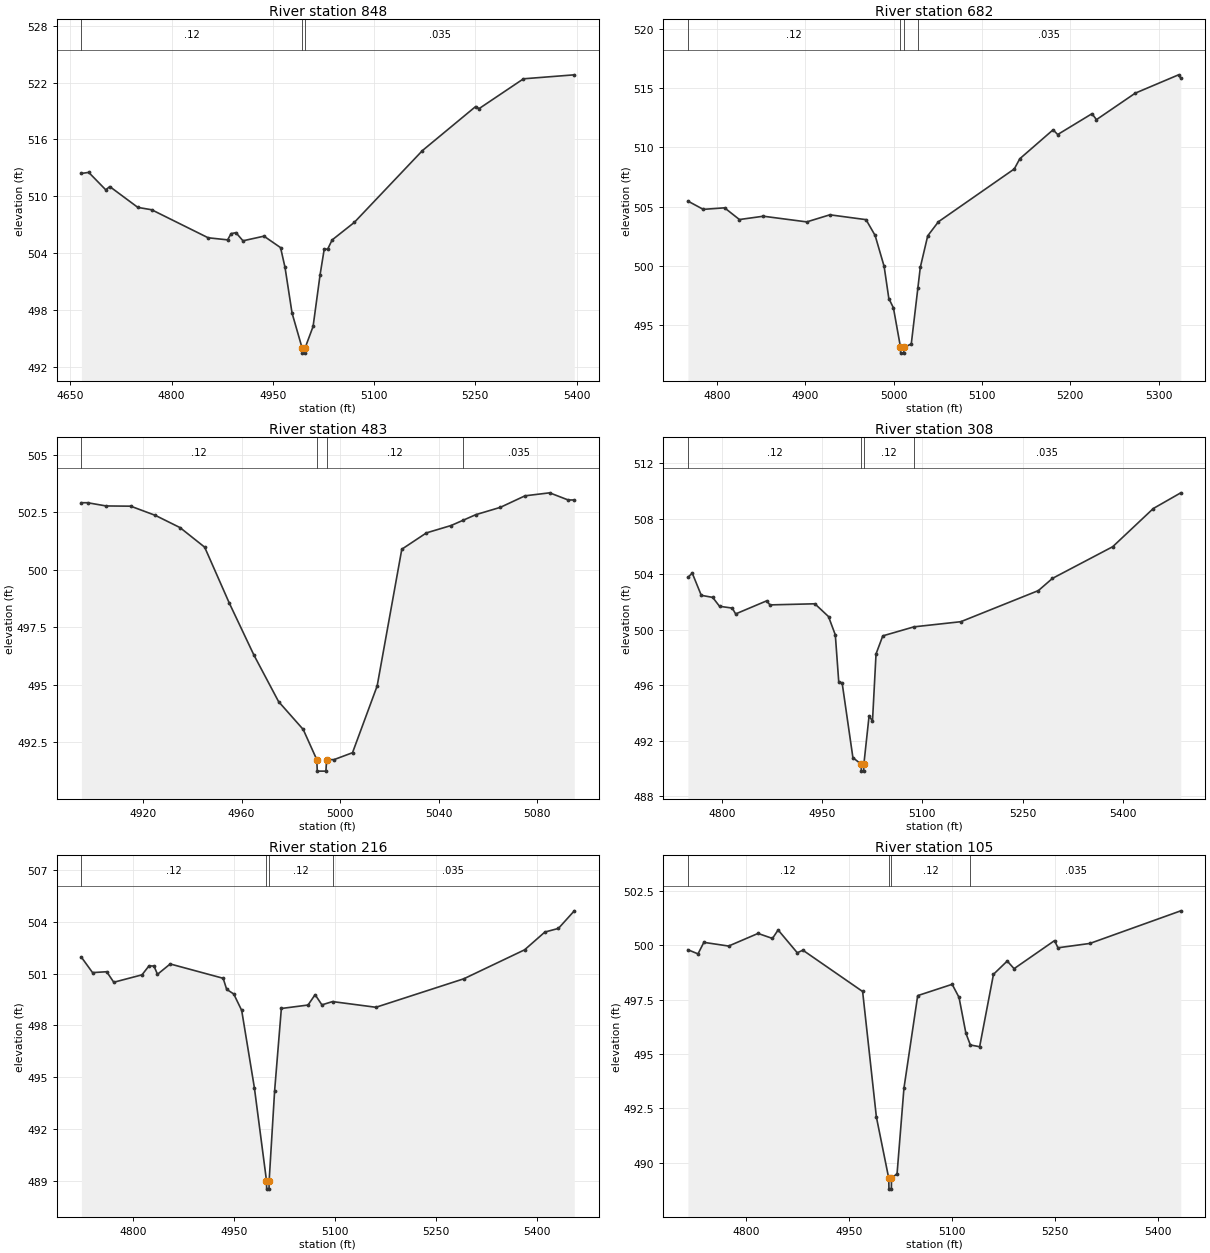
Type RM Length L Ch R = 1,848,166,166,166
BEGIN DESCRIPTION:
MXS18489
END DESCRIPTION:
XS GIS Cut Line= 3
      2489645.44     13863399.53      2489298.21     13863301.87
      2488932.19     13863249.89
#Sta/Elev= 30
  4666.3  512.41  4677.1  512.52  4702.3  510.68  4708.3  511.02  4749.9  508.82
  4770.4  508.57  4854.1  505.61  4882.9  505.39  4888.1  506.05  4895.3  506.15
  4905.7  505.29  4936.8  505.78  4961.4  504.57  4968.0  502.48  4978.4  497.66
  4993.5  493.92  4993.7  493.42  4997.2  493.42  4997.5  493.92  5009.6  496.24
  5020.0  501.72  5026.1  504.41  5031.2  504.41  5037.8  505.38  5070.6  507.23
  5171.7  514.83  5250.5  519.48  5255.6  519.26  5321.4  522.41  5396.7  522.83
#Mann=3,-1,0
  4666.3    0.12       0  4993.5   0.035       0  4997.5   0.035       0
Bank Sta=4993.5,4997.5
Exp/Cntr=0.3,0.1

Type RM Length L Ch R = 1,682,199,199,199
BEGIN DESCRIPTION:
MXS18488
END DESCRIPTION:
XS GIS Cut Line= 2
      2489601.99     13863208.54      2489057.02     13863089.60
#Sta/Elev= 30
  4767.2  505.46  4784.6  504.76  4808.7  504.89  4825.5  503.90  4852.6  504.18
  4901.7  503.70  4927.9  504.30  4968.8  503.89  4979.1  502.55  4989.3  499.93
  4994.6  497.22  4999.8  496.43  5007.8  493.10  5008.0  492.60  5011.5  492.60
  5011.8  493.10  5020.0  493.37  5027.5  498.13  5030.2  499.85  5038.6  502.52
  5050.7  503.71  5136.6  508.18  5142.8  509.04  5180.5  511.49  5185.7  511.09
  5224.5  512.85  5229.6  512.35  5273.5  514.59  5322.5  516.14  5325.0  515.85
#Mann=4,-1,0
  4767.2    0.12       0  5007.8    0.05       0  5011.8    0.12       0
  5027.5   0.035       0
Bank Sta=5007.8,5011.8
Exp/Cntr=0.3,0.1

Type RM Length L Ch R = 1,483,175,175,175
BEGIN DESCRIPTION:
StreamM068 1.0
END DESCRIPTION:
XS GIS Cut Line= 3
      2489524.96     13862975.00      2489425.00     13862975.00
      2489324.96     13862975.00
#Sta/Elev= 28
  4895.0  502.91  4897.5  502.91  4905.0  502.77  4915.0  502.76  4925.0  502.36
  4935.0  501.83  4945.0  500.98  4955.0  498.55  4965.0  496.29  4975.0  494.27
  4985.0  493.06  4990.5  491.75  4990.7  491.25  4994.2  491.25  4994.5  491.75
  4997.5  491.75  5005.0  492.05  5015.0  494.95  5025.0  500.89  5035.0  501.60
  5045.0  501.92  5049.7  502.14  5055.0  502.39  5065.0  502.71  5075.0  503.21
  5085.0  503.34  5092.5  503.03  5095.0  503.03
#Mann=4,-1,0
  4895.0    0.12       0  4990.5    0.05       0  4994.5    0.12       0
  5049.7   0.035       0
Bank Sta=4990.5,4994.5
Exp/Cntr=0.3,0.1

Type RM Length L Ch R = 1,308,92,92,92
BEGIN DESCRIPTION:
MXS18487
END DESCRIPTION:
XS GIS Cut Line= 3
      2489721.36     13862863.50      2489478.33     13862815.76
      2488994.40     13862889.54
#Sta/Elev= 30
  4749.3  503.76  4755.8  504.07  4769.3  502.47  4786.4  502.32  4796.6  501.68
  4815.6  501.55  4820.7  501.13  4867.0  502.07  4872.1  501.78  4939.2  501.86
  4959.6  500.94  4969.8  499.62  4974.9  496.25  4980.0  496.16  4996.1  490.78
  5008.5  490.31  5008.7  489.81  5012.2  489.81  5012.5  490.31  5020.3  493.79
  5025.4  493.41  5030.7  498.25  5040.8  499.55  5087.5  500.20  5157.5  500.57
  5273.5  502.81  5294.6  503.69  5384.7  505.97  5445.4  508.72  5486.5  509.85
#Mann=4,-1,0
  4749.3    0.12       0  5008.5    0.05       0  5012.5    0.12       0
  5087.5   0.035       0
Bank Sta=5008.5,5012.5
Exp/Cntr=0.3,0.1

Type RM Length L Ch R = 1,216,111,111,111
BEGIN DESCRIPTION:
H21484
END DESCRIPTION:
XS GIS Cut Line= 3
      2489740.77     13862792.76      2489513.71     13862721.80
      2489021.46     13862761.09
#Sta/Elev= 30
  4723.2  501.95  4739.7  501.06  4760.7  501.11  4771.2  500.50  4813.1  500.93
  4823.5  501.45  4830.9  501.44  4836.1  500.96  4855.0  501.56  4933.6  500.73
  4938.8  500.09  4949.3  499.82  4961.1  498.87  4979.9  494.40  4997.9  489.01
  4998.2  488.51  5001.7  488.51  5001.9  489.01  5010.0  494.21  5020.0  498.98
  5059.6  499.18  5070.1  499.78  5080.2  499.19  5096.0  499.38  5160.4  499.05
  5290.8  500.70  5381.1  502.38  5411.2  503.41  5431.3  503.62  5454.9  504.64
#Mann=4,-1,0
  4723.2    0.12       0  4997.9    0.05       0  5001.9    0.12       0
  5096.0   0.035       0
Bank Sta=4997.9,5001.9
Exp/Cntr=0.3,0.1

Type RM Length L Ch R = 1,105,85,85,85
BEGIN DESCRIPTION:
MXS18486
END DESCRIPTION:
XS GIS Cut Line= 3
      2489734.37     13862726.76      2489560.79     13862611.76
      2489052.99     13862639.97
#Sta/Elev= 30
  4715.9  499.80  4730.6  499.61  4739.1  500.14  4775.1  499.97  4817.9  500.55
  4838.9  500.32  4847.1  500.71  4875.0  499.66  4883.1  499.78  4970.0  497.88
  4990.0  492.11  5008.0  489.29  5008.3  488.79  5011.8  488.79  5012.0  489.29
  5020.1  489.50  5030.1  493.43  5050.1  497.69  5100.2  498.21  5110.2  497.61
  5120.2  495.96  5126.7  495.42  5140.2  495.34  5160.3  498.67  5180.3  499.28
  5190.3  498.93  5249.1  500.22  5254.1  499.89  5300.5  500.09  5432.7  501.59
#Mann=4,-1,0
  4715.9    0.12       0  5008.0    0.05       0  5012.0    0.12       0
  5126.7   0.035       0
Bank Sta=5008,5012
Exp/Cntr=0.3,0.1

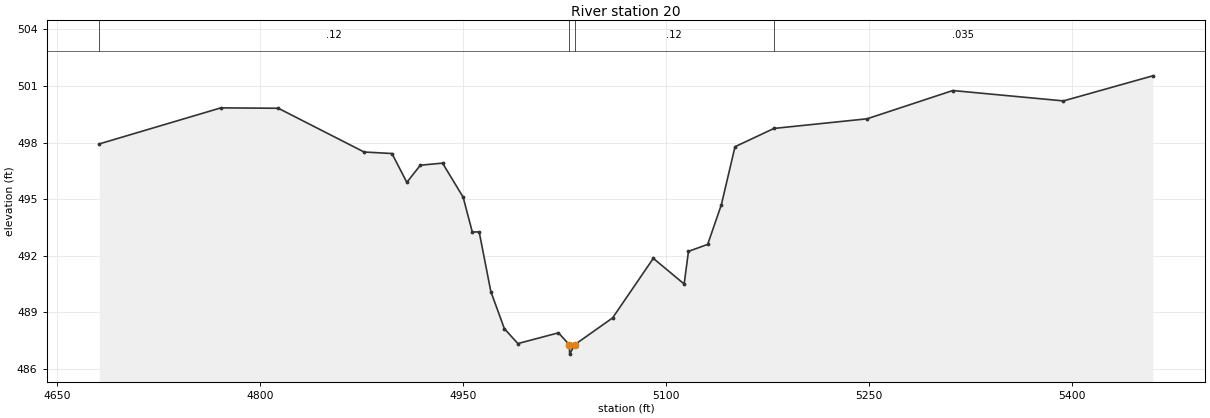
Type RM Length L Ch R = 1,20,0,0,0
BEGIN DESCRIPTION:
H21483
END DESCRIPTION:
XS GIS Cut Line= 4
      2489830.24     13862630.13      2489567.19     13862542.81
      2489412.21     13862549.36      2489069.77     13862601.71
#Sta/Elev= 30
  4681.0  497.93  4770.8  499.84  4813.3  499.82  4876.7  497.50  4897.3  497.42
  4908.3  495.89  4918.3  496.80  4934.7  496.91  4949.9  495.11  4956.7  493.26
  4961.8  493.26  4970.4  490.10  4980.4  488.13  4990.4  487.34  5020.4  487.91
  5028.4  487.28  5028.7  486.78  5032.4  487.28  5060.4  488.70  5090.5  491.86
  5113.3  490.50  5116.5  492.23  5130.7  492.60  5140.8  494.70  5150.9  497.78
  5179.7  498.75  5248.5  499.26  5311.9  500.76  5393.7  500.21  5459.7  501.54
#Mann=4,-1,0
  4681.0    0.12       0  5028.4    0.05       0  5032.4    0.12       0
  5179.7   0.035       0
Bank Sta=5028.4,5032.4
Exp/Cntr=0.3,0.1

Chan Stop Cuts=-1