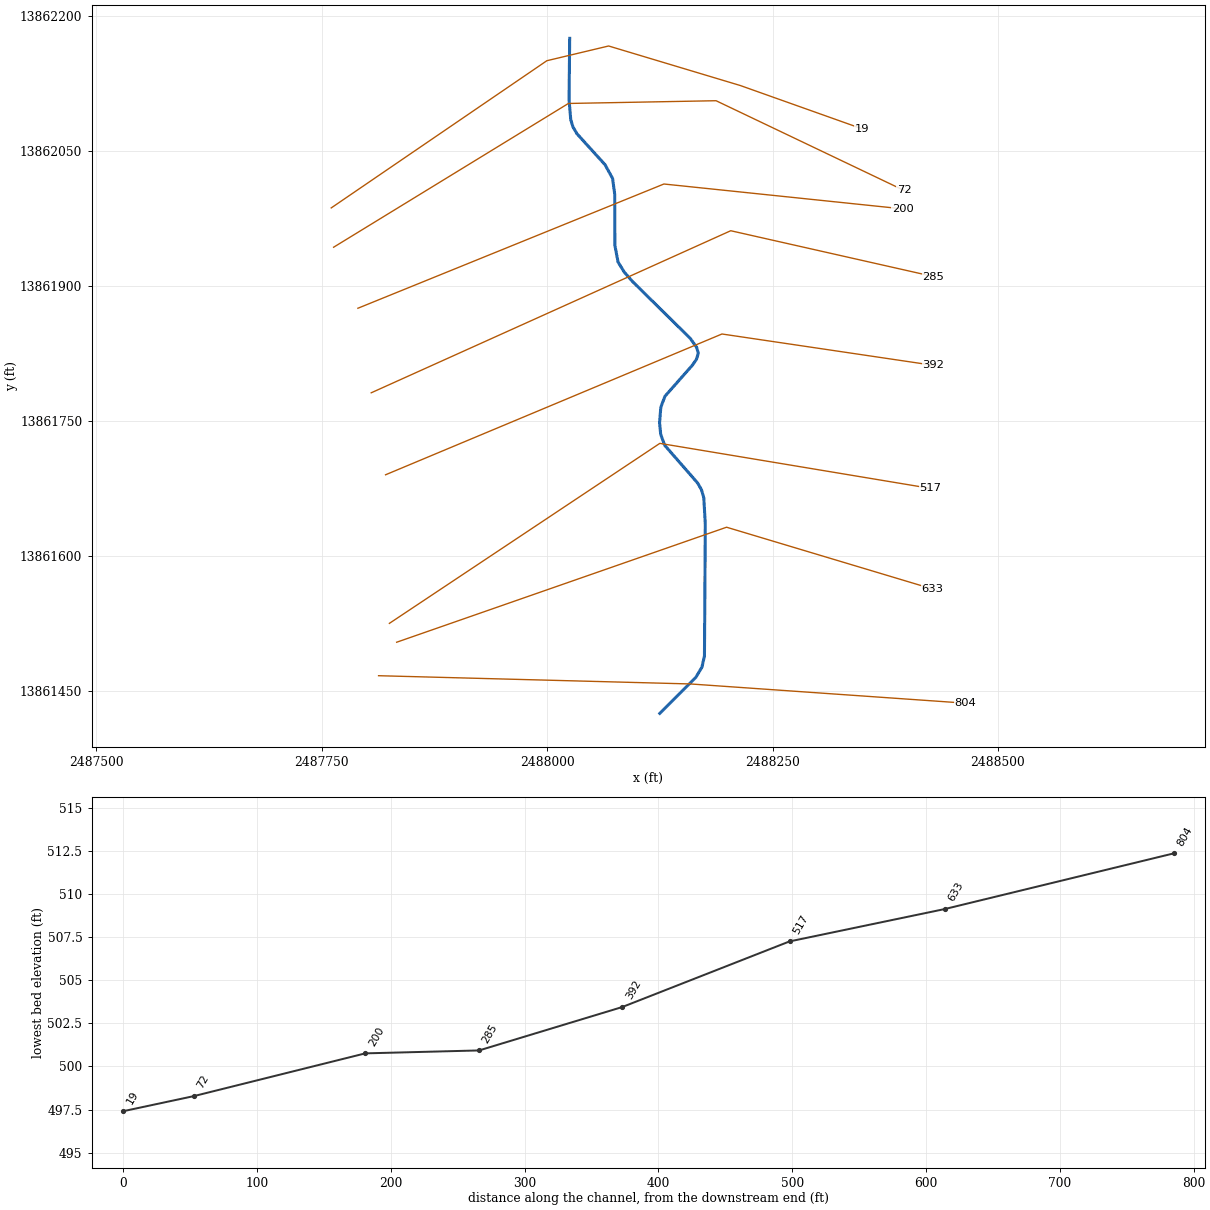
--- StreamM069.prj (project) ---

Proj Title=StreamM069 Base Level Engineering
Current Plan=p01
Default Exp/Contr=0.3,0.1
English Units
Geom File=g01
Flow File=f01
Plan File=p01
BEGIN DESCRIPTION:
StreamM069
END DESCRIPTION:

--- StreamM069.p01 (plan) ---

Plan Title=Multiple Run
Short Identifier=Multiple
Geom File=g01
Flow File=f01
Subcritical Flow
K Sum by GR= 0
Std Step Tol= 0.01
Critical Tol= 0.01
Num of Std Step Trials= 20
Max Error Tol= 0.3
Flow Tol Ratio= 0.001
Split Flow NTrial= 30
Split Flow Tol= 0.02
Split Flow Ratio= 0.02
Log Output Level= 0
Friction Slope Method= 1
Unsteady Friction Slope Method= 2
Unsteady Bridges Friction Slope Method= 1
Parabolic Critical Depth
Global Vel Dist=  1 , 1 , 1
Global Log Level= 0
CheckData=True
Encroach Param= -1, 0, 0, 0
BEGIN DESCRIPTION:
Multiple Run
END DESCRIPTION:

--- StreamM069.f01 (steady flow) ---

Flow Title=Multiple
Number of Profiles=7
Profile Names=10-year,25-year,50-year,1pct_min,100-year,1pct_plu,500-year
River Rch & RM= StreamM069,Reach-1,804
     107     151     186     113     225     448     319
River Rch & RM= StreamM069,Reach-1,19
     380     593     780     499     996    1988    1603
Boundary for River Rch & Prof#=StreamM069,Reach-1,1
Up Type=0
Dn Type=3
Dn Slope=0.005
Boundary for River Rch & Prof#=StreamM069,Reach-1,2
Up Type=0
Dn Type=3
Dn Slope=0.005
Boundary for River Rch & Prof#=StreamM069,Reach-1,3
Up Type=0
Dn Type=3
Dn Slope=0.005
Boundary for River Rch & Prof#=StreamM069,Reach-1,4
Up Type=0
Dn Type=3
Dn Slope=0.005
Boundary for River Rch & Prof#=StreamM069,Reach-1,5
Up Type=0
Dn Type=3
Dn Slope=0.005
Boundary for River Rch & Prof#=StreamM069,Reach-1,6
Up Type=0
Dn Type=3
Dn Slope=0.005
Boundary for River Rch & Prof#=StreamM069,Reach-1,7
Up Type=0
Dn Type=3
Dn Slope=0.005

--- StreamM069.g01 (geometry) ---

Geom Title=Existing Conditions

River Reach=StreamM069,Reach-1
Reach XY= 30
      2488125.00     13861425.00      2488164.95     13861465.02
      2488171.71     13861476.36      2488174.50     13861488.84
      2488175.45     13861635.19      2488173.76     13861664.50
      2488171.19     13861673.45      2488166.81     13861681.08
      2488130.40     13861722.83      2488125.98     13861734.87
      2488124.71     13861747.84      2488126.11     13861765.22
      2488130.66     13861777.30      2488161.09     13861811.81
      2488165.66     13861818.45      2488167.64     13861825.08
      2488165.83     13861831.72      2488158.66     13861841.69
      2488094.71     13861904.85      2488085.56     13861915.21
      2488078.64     13861926.50      2488075.13     13861945.05
      2488074.91     13862002.23      2488072.55     13862019.44
      2488064.16     13862034.65      2488033.11     13862068.93
      2488028.66     13862076.52      2488026.19     13862084.58
      2488024.33     13862106.54      2488025.00     13862175.00

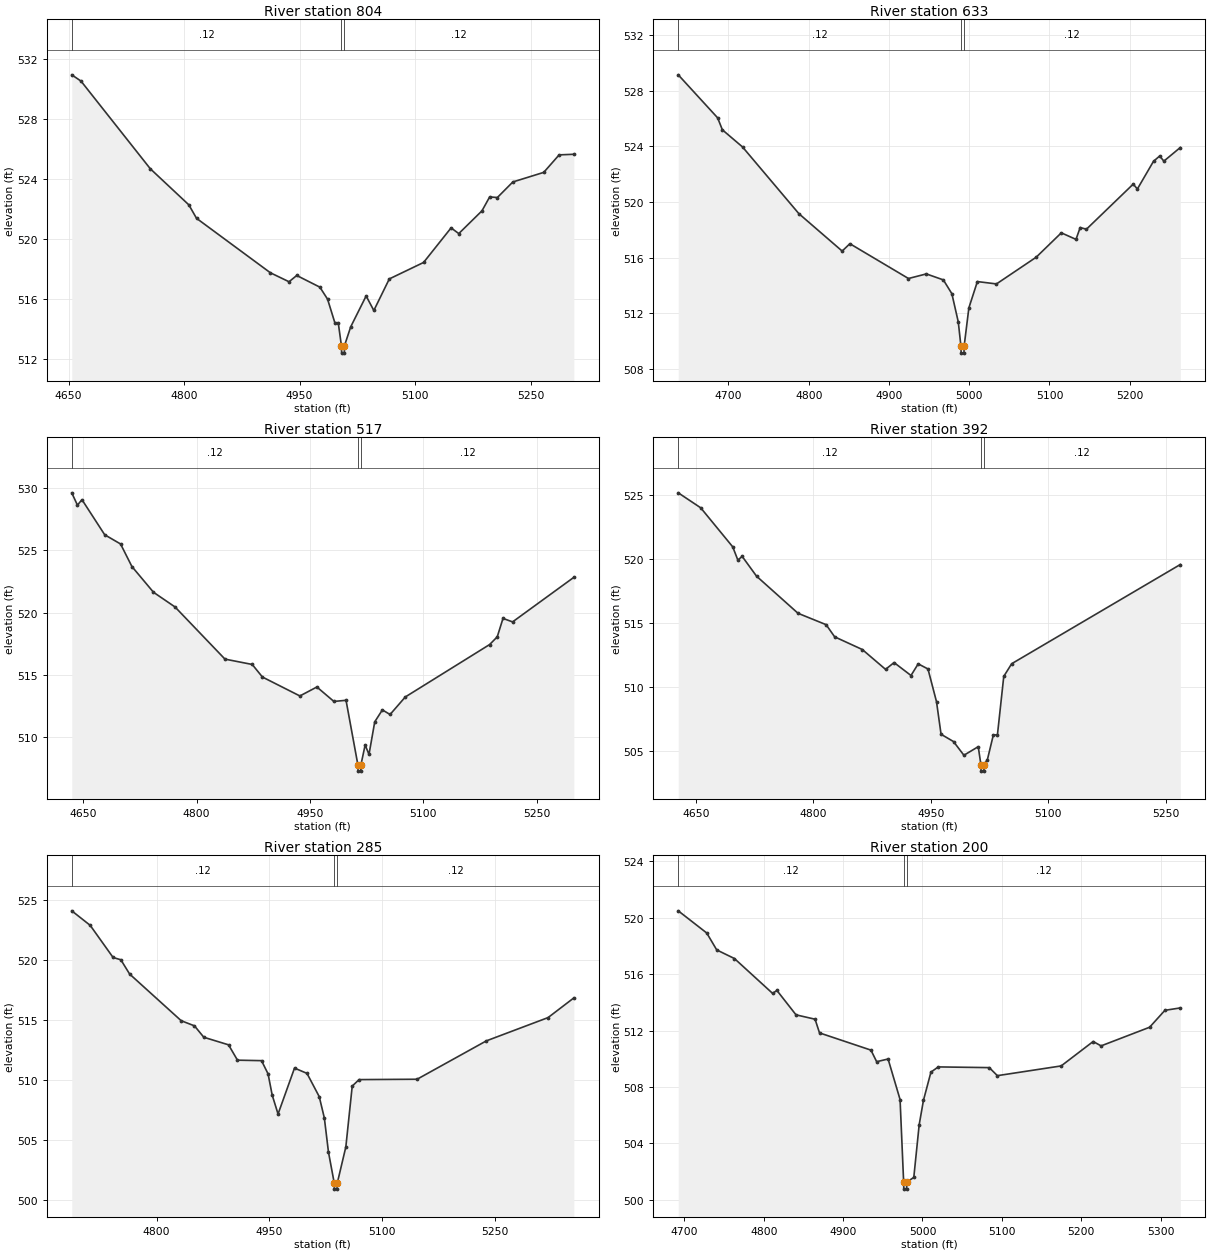
Type RM Length L Ch R = 1,804,171,171,171
BEGIN DESCRIPTION:
MXS18492
END DESCRIPTION:
XS GIS Cut Line= 3
      2487813.01     13861466.85      2488158.88     13861457.69
      2488464.04     13861436.33
#Sta/Elev= 30
  4654.2  530.97  4666.2  530.55  4756.2  524.69  4806.2  522.28  4816.2  521.38
  4912.1  517.74  4936.3  517.14  4946.3  517.56  4976.3  516.78  4986.3  515.98
  4995.8  514.40  5000.2  514.40  5004.3  512.87  5004.6  512.37  5008.1  512.37
  5008.3  512.87  5016.4  514.13  5036.4  516.19  5046.4  515.22  5066.5  517.33
  5111.0  518.43  5146.7  520.74  5156.7  520.36  5186.8  521.88  5196.8  522.81
  5206.8  522.77  5226.9  523.81  5267.0  524.45  5287.0  525.62  5306.1  525.66
#Mann=3,-1,0
  4654.2    0.12       0  5004.3    0.05       0  5008.3    0.12       0
Bank Sta=5004.3,5008.3
Exp/Cntr=0.3,0.1

Type RM Length L Ch R = 1,633,116,116,116
BEGIN DESCRIPTION:
H21488
END DESCRIPTION:
XS GIS Cut Line= 3
      2487833.06     13861504.04      2488199.04     13861631.83
      2488427.02     13861563.33
#Sta/Elev= 30
  4637.4  529.13  4686.5  526.04  4692.4  525.18  4717.5  523.95  4787.7  519.16
  4841.7  516.47  4851.3  517.00  4924.3  514.50  4946.6  514.83  4967.8  514.40
  4978.4  513.41  4986.4  511.38  4989.7  509.64  4990.0  509.14  4993.5  509.14
  4993.7  509.64  4999.6  512.39  5010.2  514.28  5034.0  514.11  5083.5  516.03
  5114.8  517.78  5133.1  517.31  5138.3  518.16  5146.1  518.04  5204.4  521.28
  5209.6  520.93  5229.7  522.92  5237.4  523.30  5242.6  522.93  5263.1  523.91
#Mann=3,-1,0
  4637.4    0.12       0  4989.7    0.05       0  4993.7    0.12       0
Bank Sta=4989.7,4993.7
Exp/Cntr=0.3,0.1

Type RM Length L Ch R = 1,517,125,125,125
BEGIN DESCRIPTION:
StreamM069 1.0
END DESCRIPTION:
XS GIS Cut Line= 3
      2487825.01     13861525.01      2488125.00     13861725.00
      2488425.02     13861675.00
#Sta/Elev= 30
  4634.7  529.62  4642.2  528.63  4648.2  529.07  4678.3  526.25  4699.3  525.51
  4714.3  523.70  4742.9  521.63  4771.4  520.45  4837.5  516.26  4873.6  515.83
  4887.1  514.82  4936.7  513.30  4959.2  514.02  4981.7  512.86  4997.8  512.95
  5013.5  507.76  5013.8  507.26  5017.3  507.26  5017.5  507.76  5023.1  509.36
  5028.2  508.60  5035.8  511.22  5045.9  512.18  5056.1  511.81  5076.3  513.22
  5187.9  517.43  5198.0  518.05  5205.6  519.53  5218.3  519.25  5299.4  522.83
#Mann=3,-1,0
  4634.7    0.12       0  5013.5    0.05       0  5017.5    0.12       0
Bank Sta=5013.5,5017.5
Exp/Cntr=0.3,0.1

Type RM Length L Ch R = 1,392,107,107,107
BEGIN DESCRIPTION:
H21487
END DESCRIPTION:
XS GIS Cut Line= 3
      2487820.77     13861690.09      2488193.93     13861846.51
      2488428.05     13861811.76
#Sta/Elev= 30
  4627.4  525.19  4656.1  524.02  4697.0  520.97  4703.6  519.93  4709.0  520.23
  4727.4  518.68  4780.4  515.78  4816.3  514.89  4827.2  513.94  4862.5  512.95
  4892.2  511.40  4903.1  511.93  4924.7  510.92  4933.9  511.83  4946.4  511.43
  4957.3  508.87  4963.1  506.33  4979.0  505.76  4992.3  504.69  5010.6  505.36
  5014.0  503.95  5014.3  503.45  5017.8  503.45  5018.0  503.95  5022.3  504.35
  5029.9  506.28  5035.1  506.28  5043.2  510.85  5053.3  511.84  5268.7  519.59
#Mann=3,-1,0
  4627.4    0.12       0  5014.0    0.05       0  5018.0    0.12       0
Bank Sta=5014,5018
Exp/Cntr=0.3,0.1

Type RM Length L Ch R = 1,285,85,85,85
BEGIN DESCRIPTION:
MXS18491
END DESCRIPTION:
XS GIS Cut Line= 3
      2487804.85     13861781.17      2488203.64     13861961.24
      2488428.50     13861910.36
#Sta/Elev= 30
  4687.1  524.13  4711.6  522.92  4742.1  520.24  4752.4  520.05  4764.1  518.86
  4832.7  514.97  4850.4  514.54  4862.8  513.59  4895.7  512.96  4907.6  511.68
  4939.6  511.64  4948.3  510.54  4953.8  508.77  4961.6  507.19  4983.5  511.02
  5000.1  510.58  5016.4  508.64  5023.2  506.86  5028.7  504.01  5036.4  501.43
  5036.6  500.93  5040.1  500.93  5040.4  501.43  5051.8  504.45  5060.3  509.52
  5069.4  510.06  5146.6  510.09  5238.8  513.29  5320.9  515.23  5355.2  516.87
#Mann=3,-1,0
  4687.1    0.12       0  5036.4    0.05       0  5040.4    0.12       0
Bank Sta=5036.4,5040.4
Exp/Cntr=0.3,0.1

Type RM Length L Ch R = 1,200,128,128,128
BEGIN DESCRIPTION:
H21486
END DESCRIPTION:
XS GIS Cut Line= 3
      2487790.08     13861875.12      2488129.52     13862013.15
      2488394.25     13861985.55
#Sta/Elev= 30
  4692.3  520.48  4728.2  518.91  4740.8  517.71  4763.1  517.10  4811.2  514.63
  4816.6  514.84  4840.7  513.11  4864.7  512.80  4870.3  511.83  4935.1  510.61
  4942.3  509.79  4956.7  509.98  4971.8  507.11  4976.3  501.26  4976.5  500.76
  4980.0  500.76  4980.3  501.26  4989.1  501.59  4995.9  505.33  5001.3  507.06
  5010.7  509.05  5019.9  509.42  5084.2  509.37  5094.4  508.80  5174.8  509.49
  5215.1  511.22  5225.1  510.91  5286.2  512.23  5305.5  513.43  5324.9  513.60
#Mann=3,-1,0
  4692.3    0.12       0  4976.3    0.05       0  4980.3    0.12       0
Bank Sta=4976.3,4980.3
Exp/Cntr=0.3,0.1

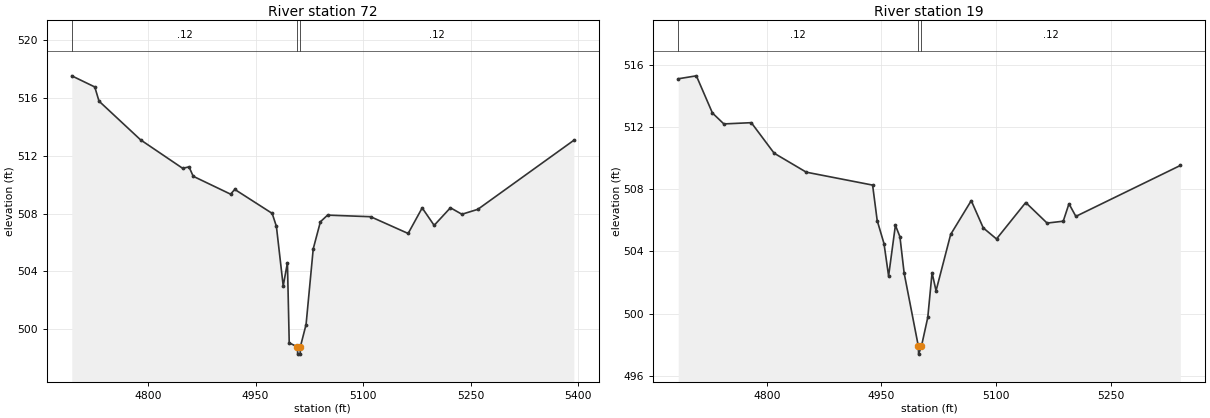
Type RM Length L Ch R = 1,72,53,53,53
BEGIN DESCRIPTION:
MXS18490
END DESCRIPTION:
XS GIS Cut Line= 4
      2487763.14     13861942.91      2488023.58     13862102.64
      2488187.36     13862105.69      2488395.93     13862005.98
#Sta/Elev= 30
  4693.6  517.54  4725.7  516.77  4731.6  515.79  4789.6  513.11  4848.3  511.14
  4857.2  511.24  4863.0  510.59  4915.2  509.35  4921.0  509.68  4973.2  508.02
  4979.1  507.12  4988.6  503.00  4994.5  504.61  4997.0  499.06  5008.5  498.78
  5008.8  498.28  5012.3  498.28  5012.5  498.78  5020.5  500.33  5030.5  505.57
  5040.5  507.44  5050.5  507.90  5110.6  507.79  5162.9  506.63  5182.5  508.40
  5199.2  507.19  5221.9  508.41  5237.9  507.96  5260.1  508.30  5394.1  513.08
#Mann=3,-1,0
  4693.6    0.12       0  5008.5    0.05       0  5012.5    0.12       0
Bank Sta=5008.5,5012.5
Exp/Cntr=0.3,0.1

Type RM Length L Ch R = 1,19,0,0,0
BEGIN DESCRIPTION:
H21485
END DESCRIPTION:
XS GIS Cut Line= 5
      2487760.48     13861986.58      2487999.69     13862150.14
      2488068.19     13862166.50      2488214.38     13862122.54
      2488349.32     13862074.49
#Sta/Elev= 30
  4684.4  515.09  4708.1  515.28  4729.1  512.89  4744.0  512.19  4779.9  512.27
  4809.7  510.31  4851.7  509.09  4938.4  508.26  4944.4  505.98  4953.3  504.50
  4959.3  502.42  4968.2  505.68  4974.1  504.94  4979.6  502.61  4998.2  497.90
  4998.5  497.40  5002.2  497.90  5010.5  499.76  5016.1  502.63  5021.3  501.47
  5040.4  505.09  5067.3  507.26  5083.0  505.51  5100.3  504.80  5138.5  507.14
  5166.4  505.82  5187.5  505.94  5195.0  507.06  5204.0  506.25  5340.5  509.52
#Mann=3,-1,0
  4684.4    0.12       0  4998.2    0.05       0  5002.2    0.12       0
Bank Sta=4998.2,5002.2
Exp/Cntr=0.3,0.1

Chan Stop Cuts=-1