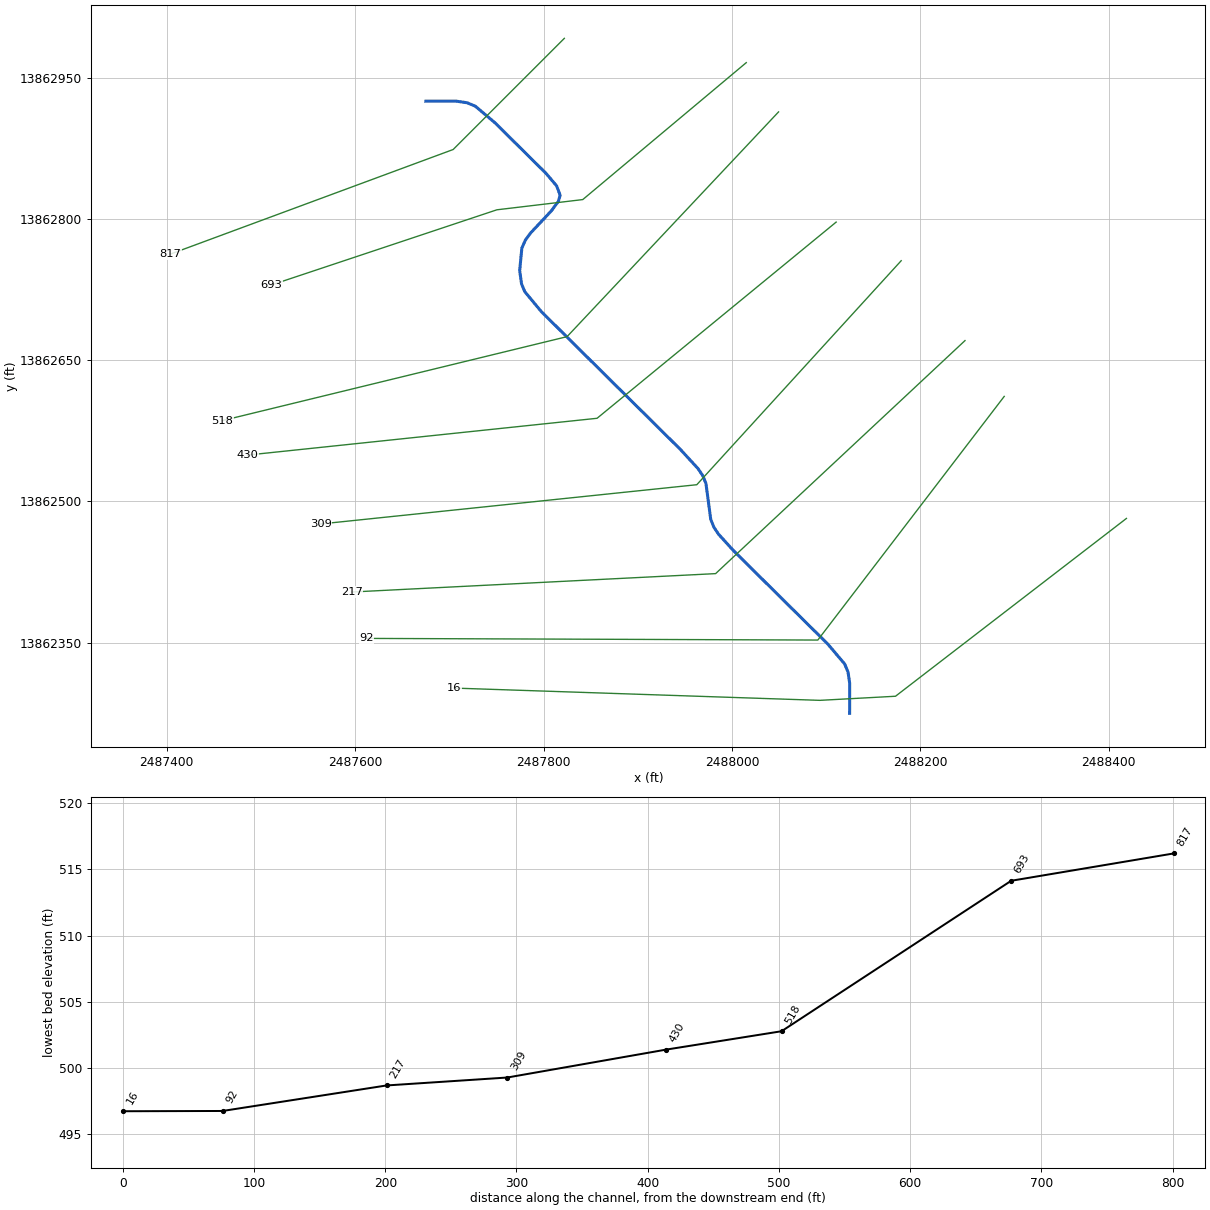
--- StreamM070.prj (project) ---

Proj Title=StreamM070 Base Level Engineering
Current Plan=p01
Default Exp/Contr=0.3,0.1
English Units
Geom File=g01
Flow File=f01
Plan File=p01
BEGIN DESCRIPTION:
StreamM070
END DESCRIPTION:

--- StreamM070.p01 (plan) ---

Plan Title=Multiple Run
Short Identifier=Multiple
Geom File=g01
Flow File=f01
Subcritical Flow
K Sum by GR= 0
Std Step Tol= 0.01
Critical Tol= 0.01
Num of Std Step Trials= 20
Max Error Tol= 0.3
Flow Tol Ratio= 0.001
Split Flow NTrial= 30
Split Flow Tol= 0.02
Split Flow Ratio= 0.02
Log Output Level= 0
Friction Slope Method= 1
Unsteady Friction Slope Method= 2
Unsteady Bridges Friction Slope Method= 1
Parabolic Critical Depth
Global Vel Dist=  1 , 1 , 1
Global Log Level= 0
CheckData=True
Encroach Param= -1, 0, 0, 0
BEGIN DESCRIPTION:
Multiple Run
END DESCRIPTION:

--- StreamM070.f01 (steady flow) ---

Flow Title=Multiple
Number of Profiles=7
Profile Names=10-year,25-year,50-year,1pct_min,100-year,1pct_plu,500-year
River Rch & RM= StreamM070,Reach-1,817
     187     278     355     221     441     881     671
River Rch & RM= StreamM070,Reach-1,16
     514     816    1086     701    1399    2791    2295
Boundary for River Rch & Prof#=StreamM070,Reach-1,1
Up Type=0
Dn Type=3
Dn Slope=0.005
Boundary for River Rch & Prof#=StreamM070,Reach-1,2
Up Type=0
Dn Type=3
Dn Slope=0.005
Boundary for River Rch & Prof#=StreamM070,Reach-1,3
Up Type=0
Dn Type=3
Dn Slope=0.005
Boundary for River Rch & Prof#=StreamM070,Reach-1,4
Up Type=0
Dn Type=3
Dn Slope=0.005
Boundary for River Rch & Prof#=StreamM070,Reach-1,5
Up Type=0
Dn Type=3
Dn Slope=0.005
Boundary for River Rch & Prof#=StreamM070,Reach-1,6
Up Type=0
Dn Type=3
Dn Slope=0.005
Boundary for River Rch & Prof#=StreamM070,Reach-1,7
Up Type=0
Dn Type=3
Dn Slope=0.005

--- StreamM070.g01 (geometry) ---

Geom Title=Existing Conditions

River Reach=StreamM070,Reach-1
Reach XY= 30
      2487675.00     13862925.00      2487706.90     13862925.07
      2487718.88     13862923.32      2487727.56     13862919.69
      2487748.59     13862901.96      2487802.60     13862848.40
      2487813.92     13862835.07      2487817.67     13862825.10
      2487815.68     13862818.46      2487808.26     13862808.49
      2487785.93     13862784.68      2487780.64     13862777.29
      2487776.99     13862768.95      2487774.68     13862745.16
      2487776.66     13862731.05      2487780.12     13862722.71
      2487797.71     13862701.53      2487945.38     13862555.16
      2487964.22     13862534.68      2487969.14     13862527.29
      2487972.47     13862518.95      2487977.53     13862481.05
      2487980.86     13862472.71      2487985.78     13862465.32
      2488001.30     13862448.18      2488101.96     13862348.45
      2488119.69     13862327.52      2488123.32     13862318.86
      2488125.07     13862306.88      2488125.00     13862275.00

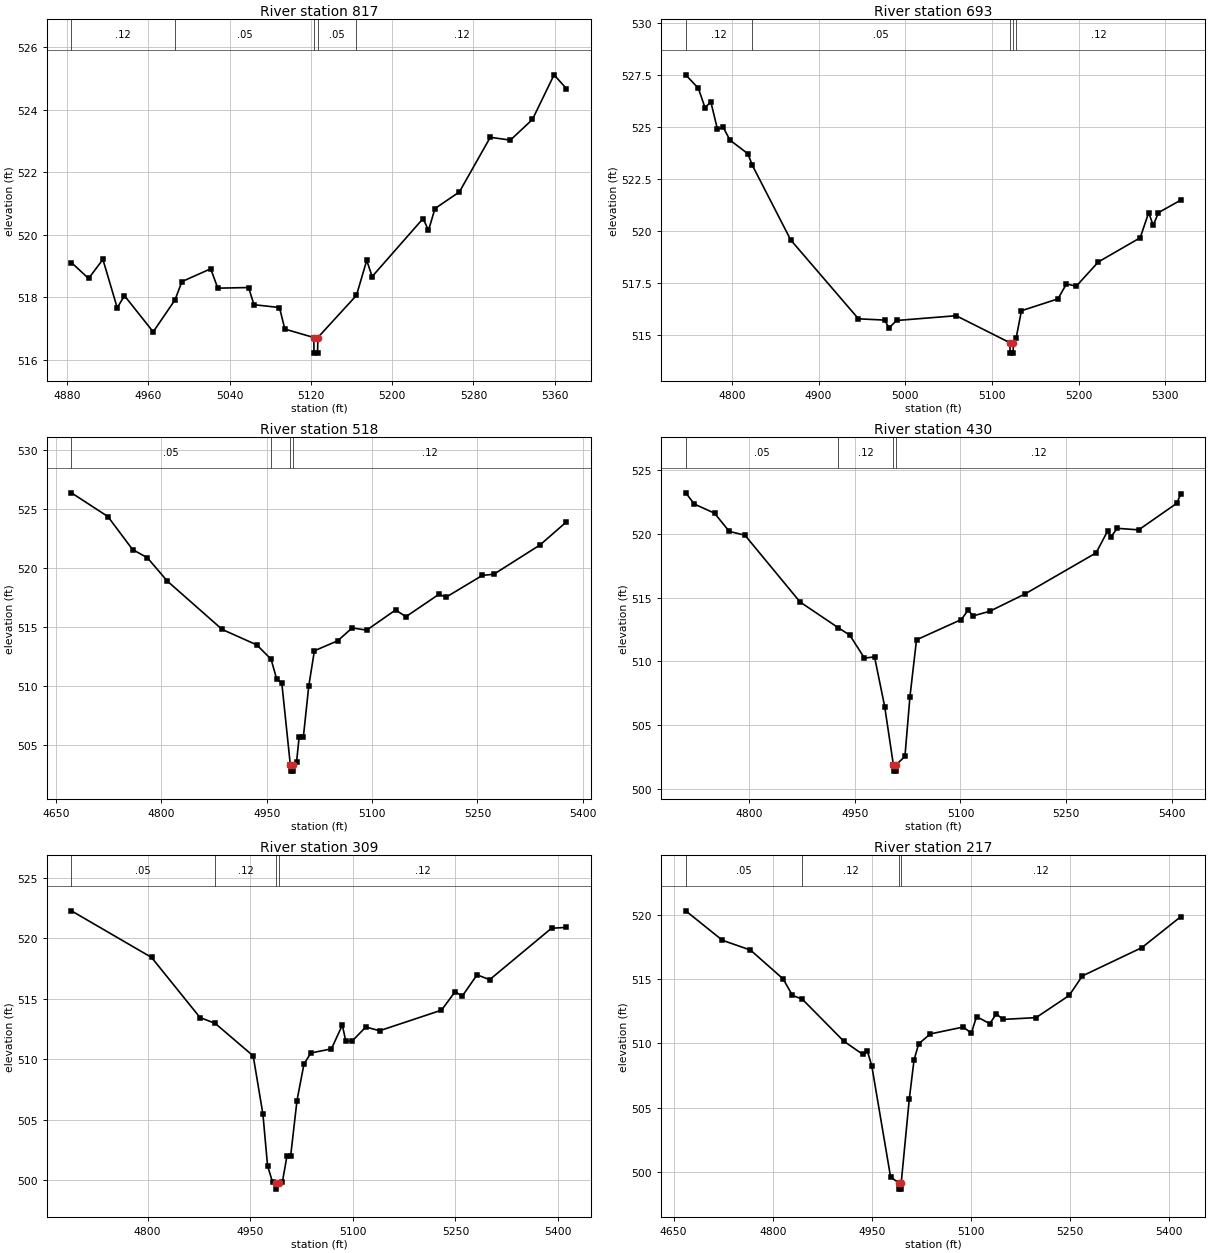
Type RM Length L Ch R = 1,817,124,124,124
BEGIN DESCRIPTION:
MXS18495
END DESCRIPTION:
XS GIS Cut Line= 3
      2487822.11     13862991.72      2487704.07     13862873.69
      2487403.69     13862762.57
#Sta/Elev= 30
  4884.2  519.11  4901.1  518.60  4915.2  519.21  4929.3  517.66  4936.4  518.05
  4964.7  516.89  4986.1  517.91  4993.0  518.50  5021.3  518.91  5028.3  518.29
  5058.6  518.31  5063.9  517.76  5089.0  517.67  5094.3  516.98  5122.8  516.71
  5123.0  516.21  5126.5  516.21  5126.8  516.71  5164.8  518.06  5174.9  519.18
  5180.2  518.66  5230.4  520.52  5235.7  520.14  5242.1  520.84  5266.1  521.37
  5296.5  523.12  5316.3  523.03  5338.0  523.69  5359.3  525.12  5371.4  524.68
#Mann=5,-1,0
  4884.2    0.12       0  4986.1    0.05       0  5122.8    0.05       0
  5126.8    0.05       0  5164.8    0.12       0
Bank Sta=5122.8,5126.8
Exp/Cntr=0.3,0.1

Type RM Length L Ch R = 1,693,175,175,175
BEGIN DESCRIPTION:
H21492
END DESCRIPTION:
XS GIS Cut Line= 4
      2488015.26     13862965.91      2487841.66     13862820.52
      2487750.51     13862809.67      2487510.71     13862729.74
#Sta/Elev= 30
  4746.7  527.53  4761.3  526.88  4769.0  525.94  4775.6  526.24  4783.3  524.91
  4789.9  525.01  4797.7  524.39  4818.5  523.73  4823.5  523.18  4867.9  519.58
  4946.0  515.79  4976.2  515.73  4981.2  515.35  4989.9  515.71  5058.7  515.94
  5120.7  514.64  5120.9  514.14  5124.4  514.14  5124.7  514.64  5127.9  514.87
  5134.0  516.18  5176.1  516.75  5185.9  517.47  5197.2  517.36  5222.8  518.53
  5271.0  519.69  5280.8  520.90  5286.0  520.29  5292.1  520.90  5317.7  521.50
#Mann=5,-1,0
  4746.7    0.12       0  4823.5    0.05       0  5120.7    0.05       0
  5124.7    0.05       0  5127.9    0.12       0
Bank Sta=5120.7,5124.7
Exp/Cntr=0.3,0.1

Type RM Length L Ch R = 1,518,88,88,88
BEGIN DESCRIPTION:
StreamM070 1.0
END DESCRIPTION:
XS GIS Cut Line= 3
      2488049.55     13862913.61      2487825.00     13862675.00
      2487458.76     13862585.79
#Sta/Elev= 30
  4672.0  526.35  4723.9  524.34  4759.1  521.54  4780.1  520.85  4808.5  518.87
  4886.6  514.77  4935.9  513.46  4956.2  512.25  4964.2  510.57  4971.5  510.23
  4983.7  503.26  4984.0  502.76  4987.5  502.76  4987.7  503.26  4992.6  503.57
  4996.2  505.65  5002.2  505.65  5009.9  509.97  5017.9  512.96  5051.1  513.81
  5071.7  514.90  5092.3  514.71  5133.5  516.42  5148.2  515.85  5195.2  517.75
  5205.5  517.51  5257.0  519.35  5273.4  519.45  5339.3  521.94  5376.6  523.88
#Mann=4,-1,0
  4672.0    0.05       0  4956.2    0.12       0  4983.7    0.05       0
  4987.7    0.12       0
Bank Sta=4983.7,4987.7
Exp/Cntr=0.3,0.1

Type RM Length L Ch R = 1,430,121,121,121
BEGIN DESCRIPTION:
H21491
END DESCRIPTION:
XS GIS Cut Line= 3
      2488110.71     13862796.62      2487856.85     13862588.31
      2487485.78     13862549.25
#Sta/Elev= 30
  4710.6  523.24  4722.7  522.36  4751.4  521.64  4772.3  520.21  4794.5  519.91
  4872.7  514.66  4927.0  512.63  4943.1  512.06  4963.9  510.25  4978.2  510.35
  4992.6  506.44  5004.9  501.87  5005.2  501.37  5008.7  501.37  5008.9  501.87
  5021.3  502.53  5028.4  507.22  5037.7  511.69  5101.2  513.28  5111.2  514.05
  5117.3  513.56  5141.4  513.93  5191.7  515.30  5292.2  518.52  5308.4  520.22
  5313.4  519.80  5322.4  520.45  5352.6  520.33  5406.4  522.41  5412.1  523.12
#Mann=4,-1,0
  4710.6    0.05       0  4927.0    0.12       0  5004.9    0.05       0
  5008.9    0.12       0
Bank Sta=5004.9,5008.9
Exp/Cntr=0.3,0.1

Type RM Length L Ch R = 1,309,92,92,92
BEGIN DESCRIPTION:
MXS18494
END DESCRIPTION:
XS GIS Cut Line= 3
      2488179.75     13862755.61      2487962.75     13862517.78
      2487563.47     13862476.12
#Sta/Elev= 30
  4688.7  522.26  4805.8  518.41  4876.7  513.44  4898.8  512.96  4954.4  510.27
  4968.6  505.46  4975.4  501.19  4982.8  499.81  4987.6  499.76  4987.8  499.26
  4991.6  499.76  4997.0  499.84  5003.8  502.00  5009.1  501.98  5018.4  506.58
  5028.5  509.57  5038.5  510.51  5068.7  510.85  5084.7  512.82  5089.7  511.48
  5098.9  511.49  5119.0  512.66  5139.1  512.35  5229.6  514.05  5249.7  515.59
  5259.7  515.19  5281.6  516.97  5300.0  516.57  5390.4  520.82  5412.1  520.89
#Mann=4,-1,0
  4688.7    0.05       0  4898.8    0.12       0  4987.6    0.05       0
  4991.6    0.12       0
Bank Sta=4987.6,4991.6
Exp/Cntr=0.3,0.1

Type RM Length L Ch R = 1,217,125,125,125
BEGIN DESCRIPTION:
H21490
END DESCRIPTION:
XS GIS Cut Line= 3
      2488247.50     13862670.80      2487982.71     13862423.38
      2487596.40     13862403.85
#Sta/Elev= 30
  4668.3  520.29  4723.8  518.00  4766.3  517.24  4815.7  515.00  4829.8  513.72
  4844.8  513.42  4907.5  510.16  4935.9  509.15  4943.2  509.40  4950.0  508.22
  4978.4  499.60  4990.5  499.16  4990.8  498.66  4994.3  498.66  4994.5  499.16
  5006.7  505.66  5013.9  508.70  5020.9  509.95  5038.4  510.72  5088.5  511.26
  5100.6  510.78  5108.5  512.07  5128.5  511.52  5138.5  512.28  5148.6  511.85
  5198.6  511.99  5248.7  513.71  5268.7  515.23  5358.8  517.43  5417.5  519.83
#Mann=4,-1,0
  4668.3    0.05       0  4844.8    0.12       0  4990.5    0.05       0
  4994.5    0.12       0
Bank Sta=4990.5,4994.5
Exp/Cntr=0.3,0.1

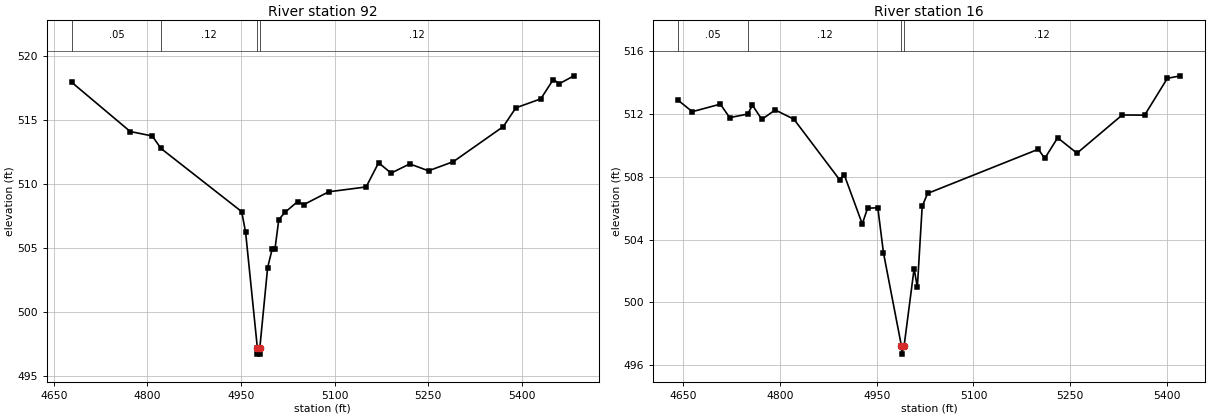
Type RM Length L Ch R = 1,92,76,76,76
BEGIN DESCRIPTION:
MXS18493
END DESCRIPTION:
XS GIS Cut Line= 3
      2488289.15     13862611.55      2488091.22     13862352.85
      2487612.05     13862354.59
#Sta/Elev= 30
  4678.8  517.96  4772.5  514.12  4807.9  513.77  4821.7  512.80  4951.2  507.86
  4957.5  506.24  4976.3  497.23  4976.5  496.73  4980.0  496.73  4980.3  497.23
  4992.8  503.49  5000.0  504.92  5004.5  504.92  5010.7  507.24  5020.7  507.81
  5040.7  508.64  5050.7  508.41  5090.7  509.41  5150.7  509.79  5170.7  511.68
  5190.7  510.87  5220.7  511.59  5250.7  511.05  5290.7  511.77  5370.7  514.51
  5390.7  515.97  5430.7  516.67  5450.7  518.18  5460.7  517.86  5483.7  518.47
#Mann=4,-1,0
  4678.8    0.05       0  4821.7    0.12       0  4976.3    0.05       0
  4980.3    0.12       0
Bank Sta=4976.3,4980.3
Exp/Cntr=0.3,0.1

Type RM Length L Ch R = 1,16,0,0,0
BEGIN DESCRIPTION:
H21489
END DESCRIPTION:
XS GIS Cut Line= 4
      2488418.92     13862481.99      2488173.69     13862293.18
      2488093.39     13862288.83      2487704.92     13862301.86
#Sta/Elev= 30
  4642.2  512.85  4664.0  512.13  4707.5  512.61  4722.0  511.75  4749.9  511.98
  4757.3  512.54  4771.8  511.64  4792.6  512.24  4821.6  511.65  4892.3  507.81
  4899.6  508.12  4927.6  504.99  4935.8  505.99  4951.7  506.02  4960.4  503.17
  4988.4  497.21  4988.7  496.71  4992.4  497.21  5008.0  502.15  5013.0  500.96
  5020.5  506.10  5028.8  506.93  5200.6  509.74  5210.6  509.16  5230.6  510.47
  5260.6  509.49  5330.7  511.92  5365.5  511.91  5400.7  514.25  5420.8  514.41
#Mann=4,-1,0
  4642.2    0.05       0  4749.9    0.12       0  4988.4    0.05       0
  4992.4    0.12       0
Bank Sta=4988.4,4992.4
Exp/Cntr=0.3,0.1

Chan Stop Cuts=-1