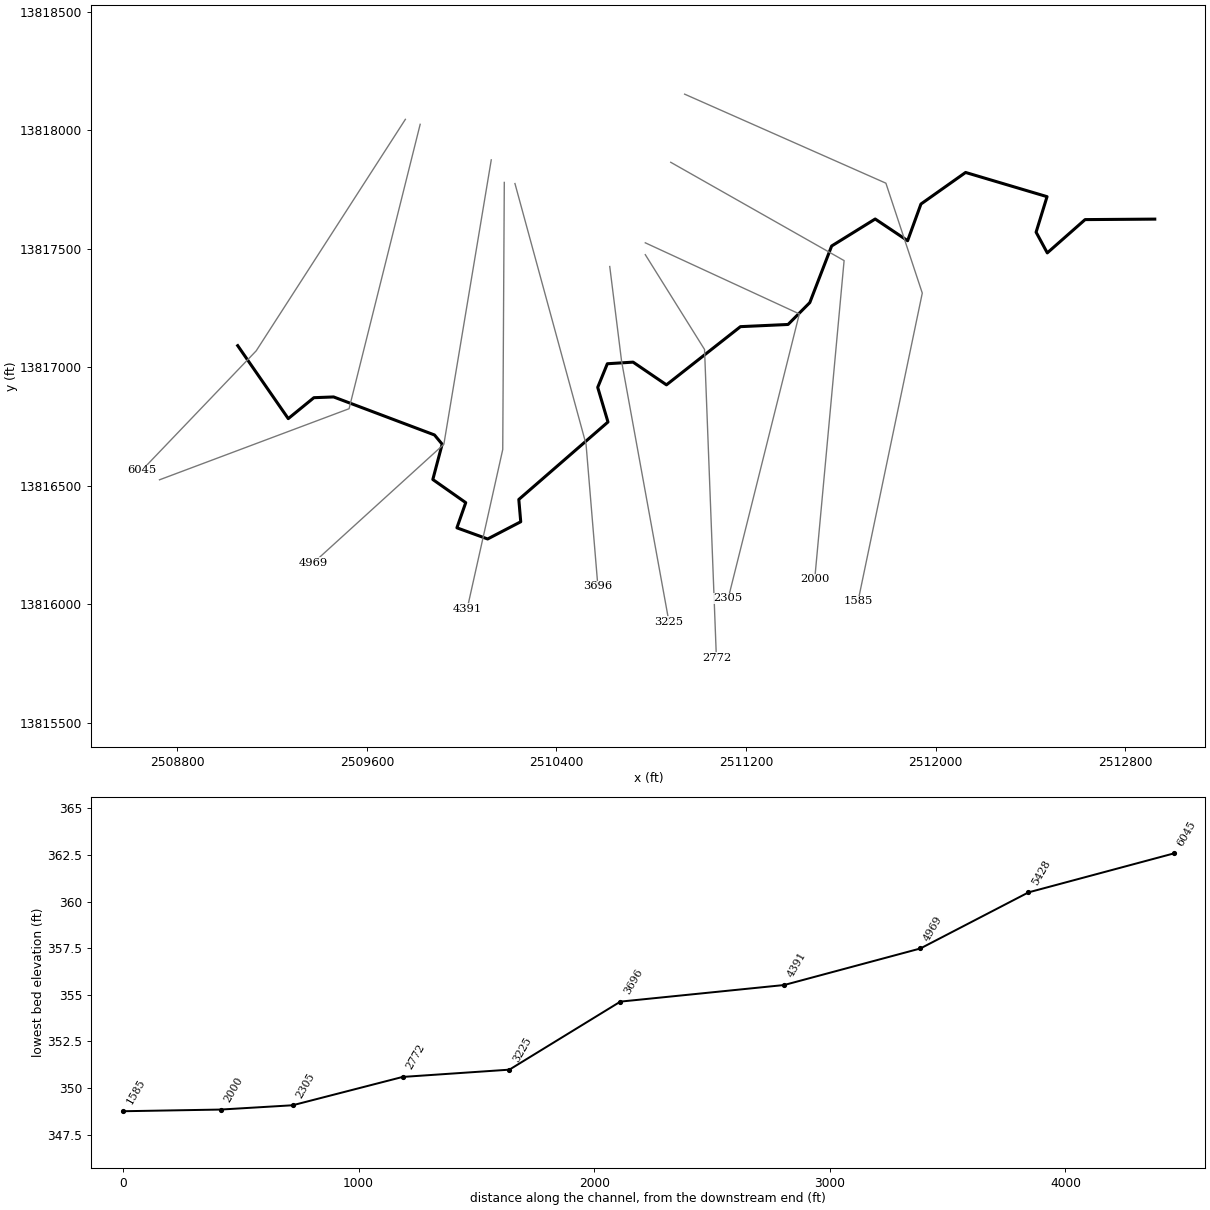
--- StreamM09.prj (project) ---

Proj Title=StreamM09 Base Level Engineering
Current Plan=p01
Default Exp/Contr=0.3,0.1
English Units
Geom File=g01
Flow File=f01
Plan File=p01
BEGIN DESCRIPTION:
StreamM09
END DESCRIPTION:

--- StreamM09.p01 (plan) ---

Plan Title=Multiple Run
Short Identifier=Multiple
Geom File=g01
Flow File=f01
Subcritical Flow
K Sum by GR= 0
Std Step Tol= 0.01
Critical Tol= 0.01
Num of Std Step Trials= 20
Max Error Tol= 0.3
Flow Tol Ratio= 0.001
Split Flow NTrial= 30
Split Flow Tol= 0.02
Split Flow Ratio= 0.02
Log Output Level= 0
Friction Slope Method= 1
Unsteady Friction Slope Method= 2
Unsteady Bridges Friction Slope Method= 1
Parabolic Critical Depth
Global Vel Dist=  1 , 1 , 1
Global Log Level= 0
CheckData=True
Encroach Param= -1, 0, 0, 0
BEGIN DESCRIPTION:
Multiple Run
END DESCRIPTION:

--- StreamM09.f01 (steady flow) ---

Flow Title=Multiple
Number of Profiles=7
Profile Names=10-year,25-year,50-year,1pct_min,100-year,1pct_plu,500-year
River Rch & RM= StreamM09,Reach-1,6045
     792    1276    1713    1112    2219    4428    3689
Boundary for River Rch & Prof#=StreamM09,Reach-1,1
Up Type=0
Dn Type=3
Dn Slope=0.005
Boundary for River Rch & Prof#=StreamM09,Reach-1,2
Up Type=0
Dn Type=3
Dn Slope=0.005
Boundary for River Rch & Prof#=StreamM09,Reach-1,3
Up Type=0
Dn Type=3
Dn Slope=0.005
Boundary for River Rch & Prof#=StreamM09,Reach-1,4
Up Type=0
Dn Type=3
Dn Slope=0.005
Boundary for River Rch & Prof#=StreamM09,Reach-1,5
Up Type=0
Dn Type=3
Dn Slope=0.005
Boundary for River Rch & Prof#=StreamM09,Reach-1,6
Up Type=0
Dn Type=3
Dn Slope=0.005
Boundary for River Rch & Prof#=StreamM09,Reach-1,7
Up Type=0
Dn Type=3
Dn Slope=0.005

--- StreamM09.g01 (geometry) ---

Geom Title=Existing Conditions

River Reach=StreamM09,Reach-1
Reach XY= 30
      2509055.03     13817091.05      2509268.33     13816783.20
      2509376.49     13816871.52      2509459.73     13816874.64
      2509885.42     13816714.25      2509917.77     13816675.31
      2509878.38     13816526.28      2510017.28     13816428.65
      2509980.00     13816322.42      2510109.72     13816275.36
      2510249.36     13816348.01      2510241.24     13816442.04
      2510617.53     13816768.93      2510574.20     13816914.97
      2510614.83     13817014.72      2510723.50     13817021.53
      2510864.30     13816925.70      2511176.55     13817171.25
      2511377.47     13817180.45      2511469.18     13817272.69
      2511561.37     13817511.54      2511745.16     13817625.47
      2511882.00     13817533.83      2511938.26     13817688.65
      2512126.64     13817821.86      2512470.38     13817719.75
      2512424.16     13817569.88      2512471.38     13817482.47
      2512630.85     13817622.94      2512925.00     13817625.00

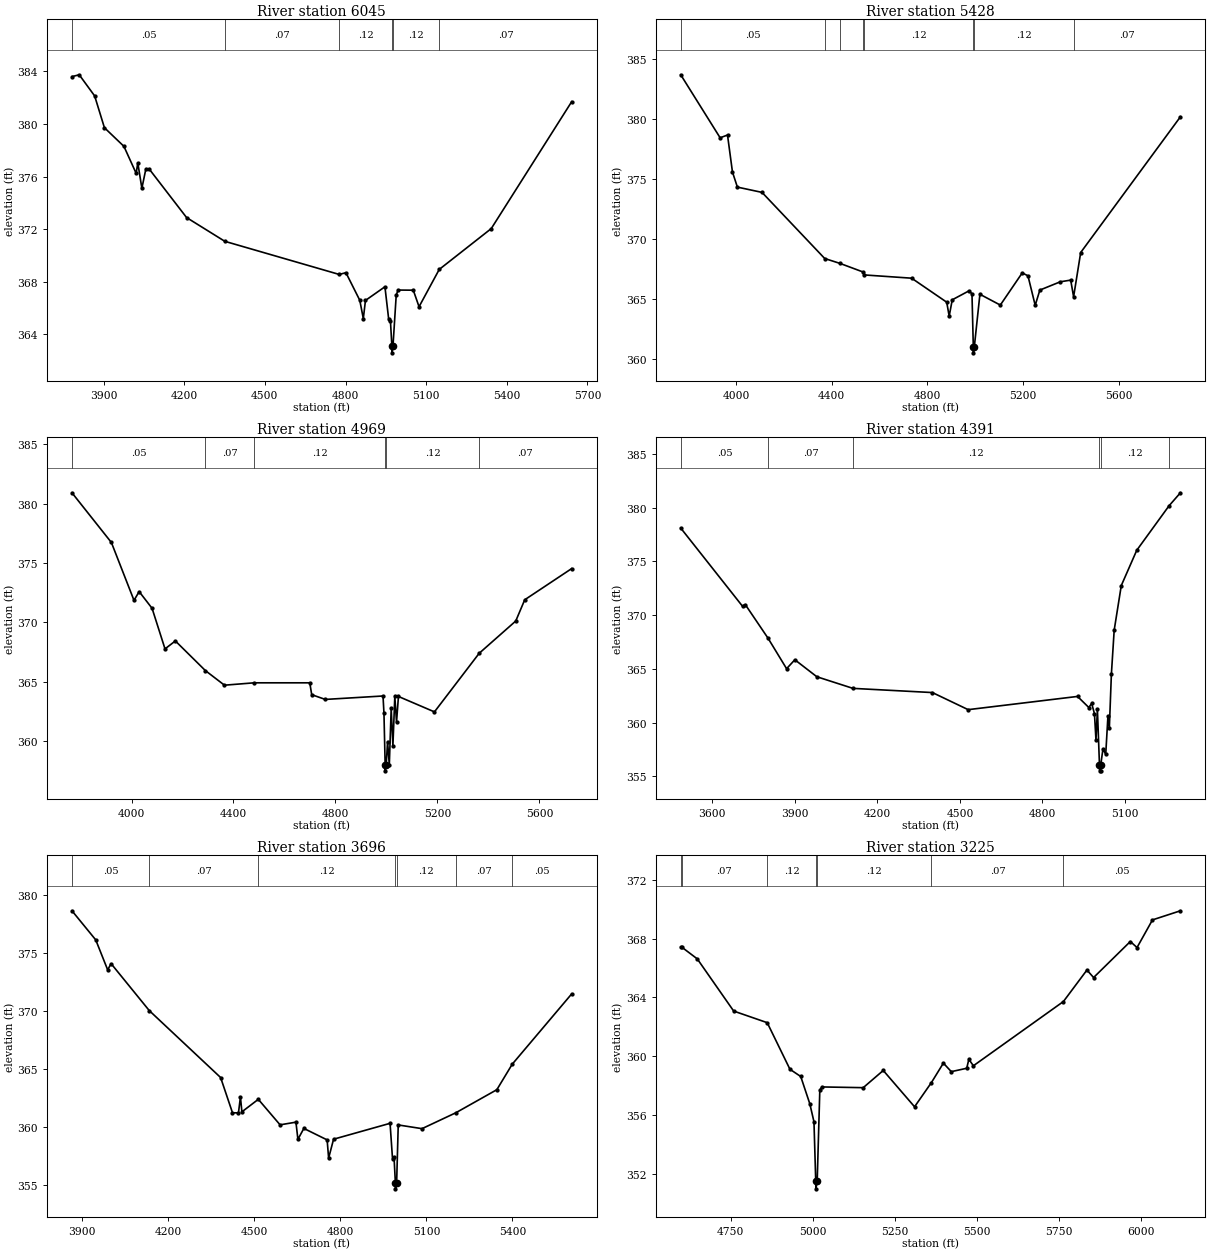
Type RM Length L Ch R = 1,6045,617,617,617
BEGIN DESCRIPTION:
Z21514
END DESCRIPTION:
XS GIS Cut Line= 3
      2509762.52     13818045.94      2509133.16     13817069.35
      2508651.36     13816565.85
#Sta/Elev= 30
  3782.5  383.61  3809.5  383.75  3866.9  382.14  3903.2  379.72  3975.8  378.30
  4021.4  376.24  4027.3  377.05  4042.5  375.11  4057.2  376.56  4069.6  376.58
  4208.8  372.88  4351.1  371.07  4776.4  368.55  4801.6  368.68  4853.1  366.58
  4866.2  365.19  4874.2  366.57  4946.6  367.61  4960.3  365.19  4967.2  364.98
  4972.5  363.08  4972.7  362.58  4976.5  363.08  4988.6  366.97  4995.5  367.36
  5052.1  367.35  5073.5  366.09  5148.6  368.93  5342.1  372.04  5641.2  381.70
#Mann=6,-1,0
  3782.5    0.05       0  4351.1    0.07       0  4776.4    0.12       0
  4972.5    0.05       0  4976.5    0.12       0  5148.6    0.07       0
Bank Sta=4972.5,4976.5
Exp/Cntr=0.3,0.1

Type RM Length L Ch R = 1,5428,459,459,459
BEGIN DESCRIPTION:
StreamM09 6.0
END DESCRIPTION:
XS GIS Cut Line= 3
      2509825.00     13818025.00      2509525.00     13816825.00
      2508725.03     13816525.01
#Sta/Elev= 30
  3767.7  383.66  3932.6  378.41  3963.5  378.64  3984.2  375.56  4004.8  374.30
  4107.9  373.86  4370.3  368.35  4434.6  367.94  4529.0  367.24  4536.7  366.98
  4734.1  366.71  4880.9  364.71  4891.2  363.55  4904.1  364.91  4973.7  365.65
  4986.6  365.42  4992.2  360.99  4992.5  360.49  4996.4  360.99  5019.8  365.37
  5105.2  364.47  5196.9  367.15  5220.9  366.91  5251.2  364.45  5270.7  365.72
  5356.2  366.41  5399.8  366.55  5411.9  365.16  5441.6  368.85  5859.0  380.16
#Mann=8,-1,0
  3767.7    0.05       0  4370.3    0.07       0  4434.6    0.05       0
  4529.0    0.07       0  4536.7    0.12       0  4992.2    0.05       0
  4996.4    0.12       0  5411.9    0.07       0
Bank Sta=4992.2,4996.4
Exp/Cntr=0.3,0.1

Type RM Length L Ch R = 1,4969,578,578,578
BEGIN DESCRIPTION:
StreamM09 5.0
END DESCRIPTION:
XS GIS Cut Line= 3
      2510124.99     13817874.96      2509925.00     13816675.00
      2509375.01     13816175.01
#Sta/Elev= 30
  3766.5  380.92  3921.1  376.73  4009.8  371.85  4030.0  372.59  4080.7  371.18
  4131.4  367.76  4172.0  368.43  4289.8  365.93  4364.6  364.70  4481.1  364.90
  4699.2  364.90  4706.8  363.90  4760.0  363.50  4986.4  363.79  4990.1  362.35
  4994.8  357.98  4995.0  357.48  4999.0  357.98  5004.3  359.95  5011.1  357.98
  5018.5  362.74  5025.2  359.60  5032.7  363.75  5039.4  361.58  5046.9  363.75
  5188.1  362.45  5363.6  367.39  5507.0  370.11  5542.2  371.90  5726.3  374.53
#Mann=6,-1,0
  3766.5    0.05       0  4289.8    0.07       0  4481.1    0.12       0
  4994.8    0.05       0  4999.0    0.12       0  5363.6    0.07       0
Bank Sta=4994.8,4999
Exp/Cntr=0.3,0.1

Type RM Length L Ch R = 1,4391,695,695,695
BEGIN DESCRIPTION:
H21495
END DESCRIPTION:
XS GIS Cut Line= 3
      2510179.99     13817779.82      2510173.46     13816652.94
      2510023.19     13815980.01
#Sta/Elev= 30
  3485.1  378.10  3709.9  370.82  3719.9  370.98  3802.6  367.85  3869.9  365.02
  3899.9  365.85  3979.9  364.27  4111.1  363.19  4399.9  362.80  4529.9  361.21
  4927.5  362.44  4968.5  361.41  4978.8  361.79  4989.0  360.84  4994.5  358.38
  4999.7  361.24  5007.3  356.02  5007.6  355.52  5011.3  355.52  5011.6  356.02
  5019.7  357.53  5030.0  357.07  5038.0  360.62  5043.1  359.49  5050.5  364.50
  5060.7  368.60  5086.5  372.75  5142.7  376.03  5260.4  380.18  5301.5  381.38
#Mann=6,-1,0
  3485.1    0.05       0  3802.6    0.07       0  4111.1    0.12       0
  5007.3    0.05       0  5011.6    0.12       0  5260.4    0.07       0
Bank Sta=5007.3,5011.6
Exp/Cntr=0.3,0.1

Type RM Length L Ch R = 1,3696,471,471,471
BEGIN DESCRIPTION:
StreamM09 4.0
END DESCRIPTION:
XS GIS Cut Line= 3
      2510225.00     13817775.00      2510525.00     13816675.00
      2510575.00     13816074.96
#Sta/Elev= 30
  3864.2  378.61  3947.1  376.10  3988.6  373.52  4000.7  374.05  4133.8  370.00
  4382.5  364.23  4423.9  361.19  4444.7  361.18  4451.6  362.55  4456.7  361.27
  4513.9  362.35  4589.8  360.15  4645.1  360.38  4652.0  358.90  4672.7  359.84
  4753.9  358.85  4759.1  357.28  4776.3  358.91  4973.3  360.28  4981.9  357.21
  4987.1  357.38  4991.9  355.13  4992.2  354.63  4996.2  355.13  5001.8  360.14
  5084.7  359.82  5202.6  361.19  5345.6  363.18  5399.3  365.38  5606.5  371.44
#Mann=7,-1,0
  3864.2    0.05       0  4133.8    0.07       0  4513.9    0.12       0
  4991.9    0.05       0  4996.2    0.12       0  5202.6    0.07       0
  5399.3    0.05       0
Bank Sta=4991.9,4996.2
Exp/Cntr=0.3,0.1

Type RM Length L Ch R = 1,3225,453,453,453
BEGIN DESCRIPTION:
StreamM09 3.0
END DESCRIPTION:
XS GIS Cut Line= 3
      2510625.01     13817424.96      2510675.00     13817025.00
      2510875.00     13815925.00
#Sta/Elev= 30
  4597.8  367.43  4600.2  367.43  4648.1  366.62  4759.0  363.07  4861.1  362.28
  4930.3  359.11  4963.1  358.62  4990.8  356.76  5003.4  355.54  5008.8  351.48
  5009.1  350.98  5013.2  351.48  5021.2  357.70  5027.6  357.91  5153.3  357.86
  5214.3  359.03  5309.6  356.56  5361.0  358.21  5397.3  359.53  5421.4  358.95
  5468.4  359.18  5474.8  359.79  5488.7  359.35  5762.8  363.72  5834.3  365.86
  5854.6  365.35  5966.4  367.80  5986.8  367.39  6033.8  369.27  6118.9  369.89
#Mann=7,-1,0
  4597.8    0.05       0  4600.2    0.07       0  4861.1    0.12       0
  5008.8    0.05       0  5013.2    0.12       0  5361.0    0.07       0
  5762.8    0.05       0
Bank Sta=5008.8,5013.2
Exp/Cntr=0.3,0.1

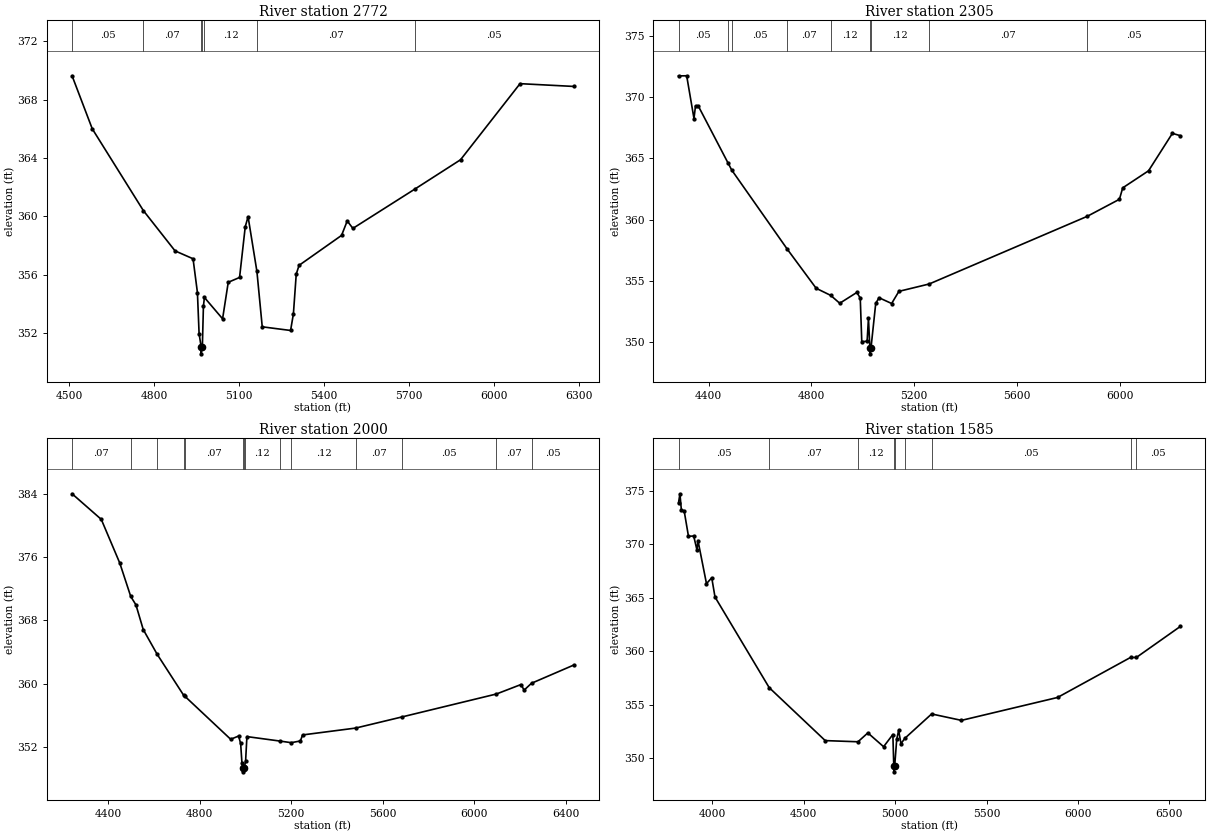
Type RM Length L Ch R = 1,2772,467,467,467
BEGIN DESCRIPTION:
StreamM09 2.0
END DESCRIPTION:
XS GIS Cut Line= 3
      2510775.02     13817474.97      2511025.00     13817075.00
      2511075.00     13815775.02
#Sta/Elev= 30
  4511.0  369.63  4582.3  366.00  4762.8  360.40  4874.8  357.64  4938.4  357.10
  4953.8  354.79  4959.7  351.98  4966.8  351.09  4967.1  350.59  4971.3  351.09
  4975.0  353.85  4978.5  354.45  5042.7  352.99  5062.7  355.49  5102.7  355.82
  5122.8  359.30  5132.8  359.98  5164.0  356.23  5182.8  352.44  5282.9  352.19
  5292.9  353.33  5302.9  356.05  5312.9  356.65  5463.0  358.70  5483.0  359.69
  5503.0  359.18  5721.8  361.87  5883.3  363.88  6093.5  369.09  6283.6  368.90
#Mann=7,-1,0
  4511.0    0.05       0  4762.8    0.07       0  4966.8    0.05       0
  4971.3    0.07       0  4978.5    0.12       0  5164.0    0.07       0
  5721.8    0.05       0
Bank Sta=4966.8,4971.3
Exp/Cntr=0.3,0.1

Type RM Length L Ch R = 1,2305,305,305,305
BEGIN DESCRIPTION:
StreamM09 1.0
END DESCRIPTION:
XS GIS Cut Line= 3
      2510774.99     13817525.00      2511425.00     13817225.00
      2511125.01     13816025.03
#Sta/Elev= 30
  4283.2  371.71  4314.9  371.72  4343.3  368.24  4349.3  369.28  4360.3  369.25
  4476.2  364.60  4490.2  364.04  4706.9  357.58  4818.8  354.41  4875.5  353.83
  4910.5  353.19  4977.1  354.07  4990.4  353.61  4996.3  350.07  5017.1  350.09
  5022.3  351.97  5027.8  349.57  5028.1  349.07  5032.3  349.57  5050.6  353.18
  5063.5  353.64  5112.5  353.17  5140.8  354.16  5258.7  354.76  5873.6  360.27
  5999.0  361.66  6011.8  362.59  6112.3  363.98  6205.1  367.03  6236.0  366.84
#Mann=9,-1,0
  4283.2    0.05       0  4476.2    0.07       0  4490.2    0.05       0
  4706.9    0.07       0  4875.5    0.12       0  5027.8    0.05       0
  5032.3    0.12       0  5258.7    0.07       0  5873.6    0.05       0
Bank Sta=5027.8,5032.3
Exp/Cntr=0.3,0.1

Type RM Length L Ch R = 1,2000,415,415,415
BEGIN DESCRIPTION:
H21494
END DESCRIPTION:
XS GIS Cut Line= 3
      2510882.29     13817864.79      2511613.96     13817449.96
      2511489.92     13816105.05
#Sta/Elev= 30
  4243.1  384.03  4370.7  380.79  4451.5  375.26  4499.3  371.04  4522.1  369.97
  4553.9  366.85  4614.3  363.74  4730.5  358.53  4734.4  358.44  4935.9  352.96
  4970.4  353.37  4979.4  352.43  4985.2  349.90  4991.2  349.34  4991.5  348.84
  4995.7  349.34  4996.4  349.46  5001.1  350.24  5006.8  353.30  5152.3  352.73
  5200.3  352.53  5240.5  352.75  5249.8  353.51  5481.9  354.38  5684.3  355.79
  6096.5  358.69  6203.9  359.89  6217.5  359.18  6249.8  360.05  6434.8  362.36
#Mann=14,-1,0
  4243.1    0.07       0  4499.3    0.05       0  4614.3    0.07       0
  4730.5    0.05       0  4734.4    0.07       0  4991.2    0.05       0
  4995.7    0.07       0  4996.4    0.12       0  5152.3    0.07       0
  5200.3    0.12       0  5481.9    0.07       0  5684.3    0.05       0
  6096.5    0.07       0  6249.8    0.05       0
Bank Sta=4991.2,4995.7
Exp/Cntr=0.3,0.1

Type RM Length L Ch R = 1,1585,0,0,0
BEGIN DESCRIPTION:
H21493
END DESCRIPTION:
XS GIS Cut Line= 4
      2510941.06     13818152.25      2511790.35     13817776.60
      2511943.88     13817312.77      2511672.75     13816012.68
#Sta/Elev= 30
  3814.6  373.90  3822.3  374.74  3829.8  373.27  3845.6  373.12  3868.9  370.77
  3897.6  370.79  3915.5  369.48  3920.9  370.37  3967.5  366.34  3996.3  366.89
  4014.1  365.09  4310.6  356.62  4617.1  351.67  4796.4  351.56  4850.3  352.39
  4936.5  351.10  4987.2  352.24  4992.3  349.25  4992.7  348.75  4996.9  349.25
  5008.3  351.79  5018.8  352.62  5031.6  351.38  5052.6  351.88  5199.3  354.16
  5362.4  353.56  5888.0  355.70  6287.3  359.44  6319.3  359.44  6559.9  362.34
#Mann=9,-1,0
  3814.6    0.05       0  4310.6    0.07       0  4796.4    0.12       0
  4992.3    0.05       0  4996.9    0.12       0  5052.6    0.07       0
  5199.3    0.05       0  6287.3    0.07       0  6319.3    0.05       0
Bank Sta=4992.3,4996.9
Exp/Cntr=0.3,0.1

Chan Stop Cuts=-1