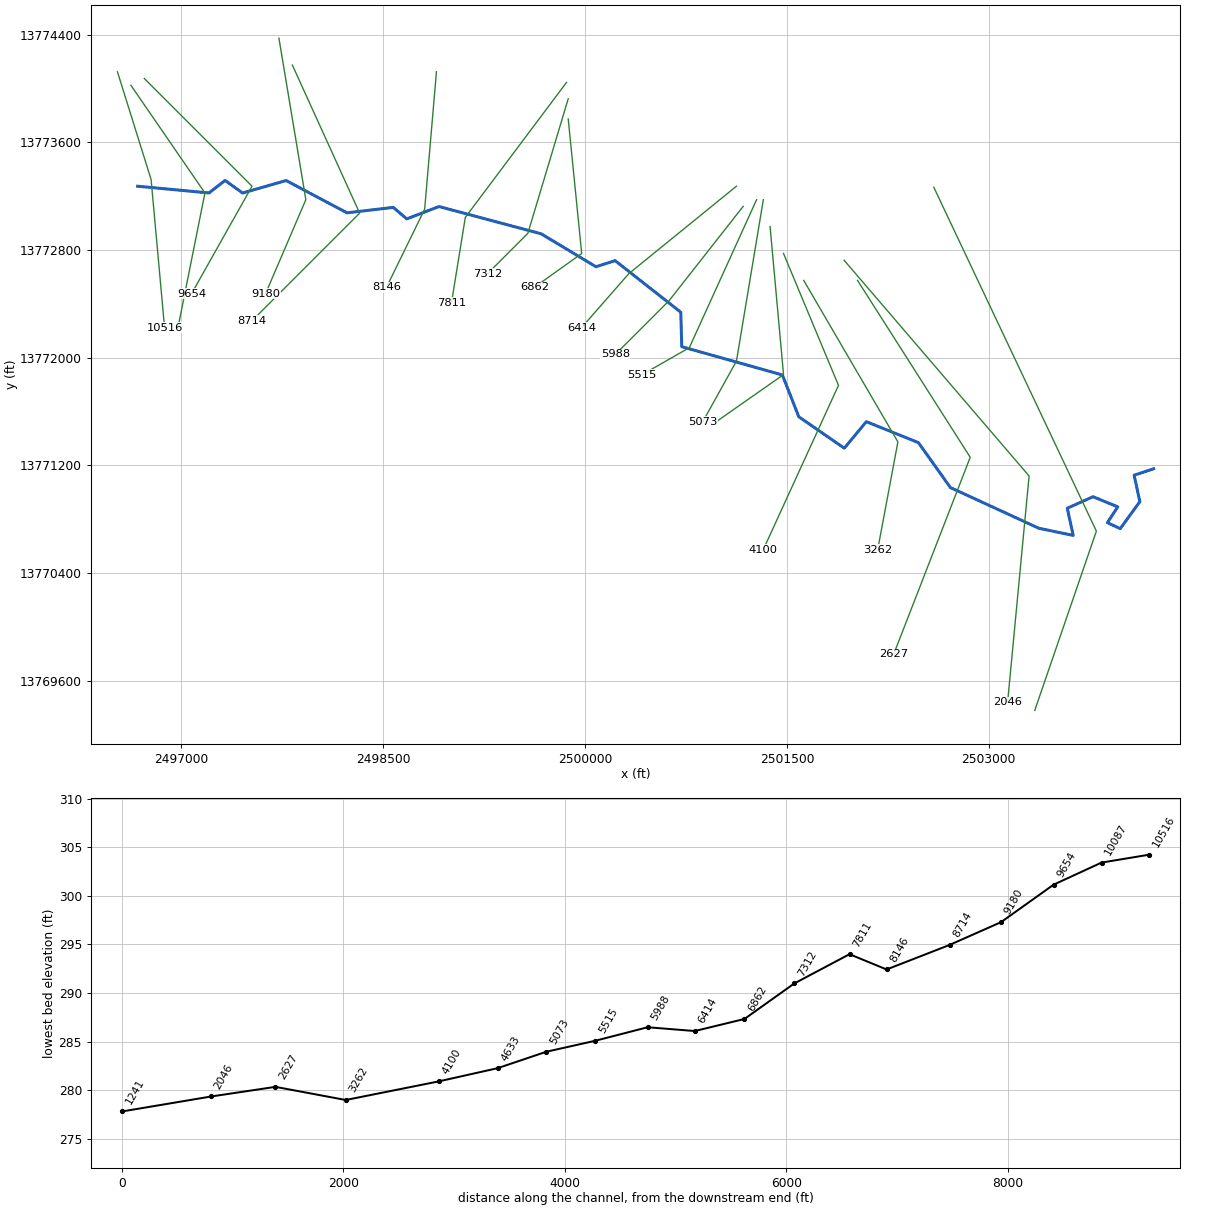
--- THOMPSON BRANCH.prj (project) ---

Proj Title=THOMPSON BRANCH Base Level Engineering
Current Plan=p01
Default Exp/Contr=0.3,0.1
English Units
Geom File=g01
Flow File=f01
Plan File=p01
BEGIN DESCRIPTION:
THOMPSON BRANCH
END DESCRIPTION:

--- THOMPSON BRANCH.p01 (plan) ---

Plan Title=Multiple Run
Short Identifier=Multiple
Geom File=g01
Flow File=f01
Subcritical Flow
K Sum by GR= 0
Std Step Tol= 0.01
Critical Tol= 0.01
Num of Std Step Trials= 20
Max Error Tol= 0.3
Flow Tol Ratio= 0.001
Split Flow NTrial= 30
Split Flow Tol= 0.02
Split Flow Ratio= 0.02
Log Output Level= 0
Friction Slope Method= 1
Unsteady Friction Slope Method= 2
Unsteady Bridges Friction Slope Method= 1
Parabolic Critical Depth
Global Vel Dist=  1 , 1 , 1
Global Log Level= 0
CheckData=True
Encroach Param= -1, 0, 0, 0
BEGIN DESCRIPTION:
Multiple Run
END DESCRIPTION:

--- THOMPSON BRANCH.f01 (steady flow) ---

Flow Title=Multiple
Number of Profiles=7
Profile Names=10-year,25-year,50-year,1pct_min,100-year,1pct_plu,500-year
River Rch & RM= THOMPSON BRANCH,Reach-1,10516
     726    1170    1571    1021    2037    4064    3392
River Rch & RM= THOMPSON BRANCH,Reach-1,8714
    1094    1793    2433    1596    3185    6354    5402
River Rch & RM= THOMPSON BRANCH,Reach-1,4100
    1183    1937    2627    1721    3433    6850    5808
Boundary for River Rch & Prof#=THOMPSON BRANCH,Reach-1,1
Up Type=0
Dn Type=3
Dn Slope=0.005
Boundary for River Rch & Prof#=THOMPSON BRANCH,Reach-1,2
Up Type=0
Dn Type=3
Dn Slope=0.005
Boundary for River Rch & Prof#=THOMPSON BRANCH,Reach-1,3
Up Type=0
Dn Type=3
Dn Slope=0.005
Boundary for River Rch & Prof#=THOMPSON BRANCH,Reach-1,4
Up Type=0
Dn Type=3
Dn Slope=0.005
Boundary for River Rch & Prof#=THOMPSON BRANCH,Reach-1,5
Up Type=0
Dn Type=3
Dn Slope=0.005
Boundary for River Rch & Prof#=THOMPSON BRANCH,Reach-1,6
Up Type=0
Dn Type=3
Dn Slope=0.005
Boundary for River Rch & Prof#=THOMPSON BRANCH,Reach-1,7
Up Type=0
Dn Type=3
Dn Slope=0.005

--- THOMPSON BRANCH.g01 (geometry) ---

Geom Title=Existing Conditions

River Reach=THOMPSON BRANCH,Reach-1
Reach XY= 30
      2496675.00     13773275.00      2497205.02     13773224.97
      2497325.00     13773317.90      2497454.79     13773224.65
      2497778.42     13773317.21      2498230.93     13773077.24
      2498575.10     13773117.66      2498675.00     13773032.11
      2498914.56     13773123.96      2499673.53     13772921.44
      2500081.04     13772676.63      2500223.36     13772721.86
      2500711.47     13772338.39      2500718.62     13772082.37
      2501466.50     13771872.33      2501588.36     13771561.65
      2501926.68     13771328.08      2502090.22     13771525.17
      2502477.45     13771369.54      2502715.00     13771035.65
      2503371.78     13770733.28      2503627.62     13770679.98
      2503583.83     13770882.00      2503775.00     13770967.44
      2503958.99     13770892.12      2503882.01     13770774.72
      2503977.25     13770730.06      2504123.20     13770931.11
      2504080.39     13771127.45      2504225.00     13771175.00

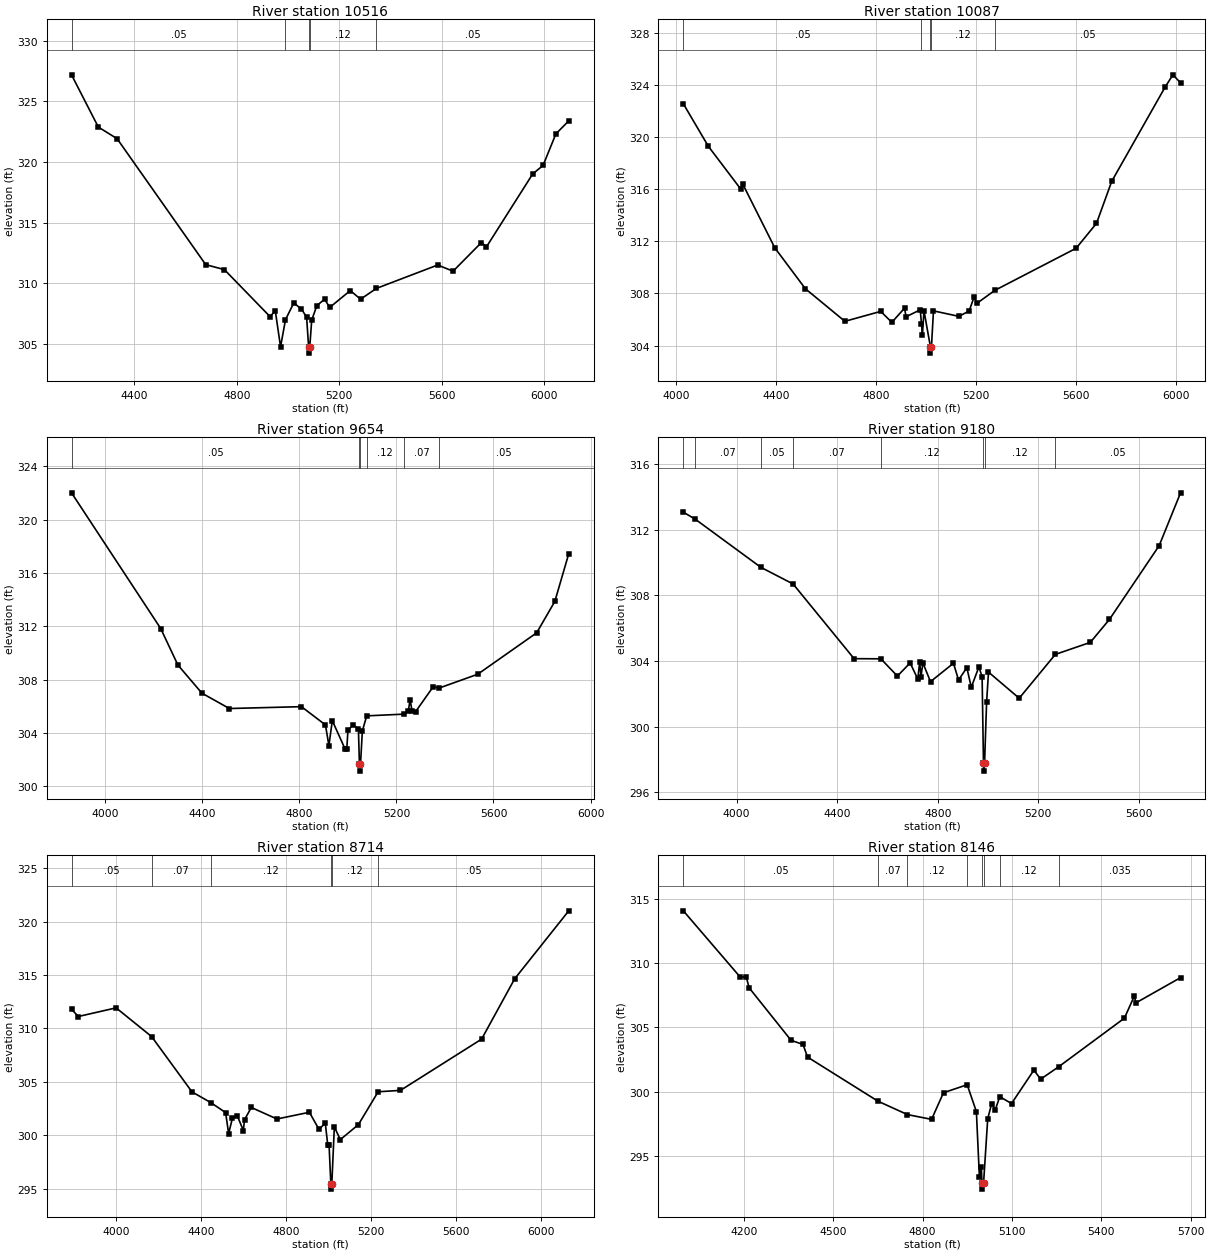
Type RM Length L Ch R = 1,10516,429,429,429
BEGIN DESCRIPTION:
THOMPSON BRANCH 19.0
END DESCRIPTION:
XS GIS Cut Line= 3
      2496525.01     13774124.98      2496775.00     13773325.00
      2496875.00     13772224.97
#Sta/Elev= 30
  4154.4  327.19  4259.1  322.88  4332.5  321.92  4678.7  311.53  4751.6  311.12
  4929.7  307.25  4950.6  307.71  4971.1  304.75  4990.4  306.99  5022.7  308.37
  5052.8  307.87  5072.9  307.19  5080.8  304.73  5081.1  304.23  5085.1  304.73
  5092.9  306.96  5113.0  308.15  5143.2  308.68  5163.2  308.00  5243.6  309.39
  5283.7  308.68  5345.6  309.57  5585.0  311.50  5645.2  310.99  5755.7  313.35
  5775.7  313.00  5956.5  319.02  5996.7  319.71  6046.9  322.32  6097.1  323.39
#Mann=5,-1,0
  4154.4    0.05       0  4990.4    0.12       0  5080.8    0.05       0
  5085.1    0.12       0  5345.6    0.05       0
Bank Sta=5080.8,5085.1
Exp/Cntr=0.3,0.1

Type RM Length L Ch R = 1,10087,433,433,433
BEGIN DESCRIPTION:
THOMPSON BRANCH 18.0
END DESCRIPTION:
XS GIS Cut Line= 3
      2496624.98     13774025.03      2497175.00     13773225.00
      2496974.99     13772224.96
#Sta/Elev= 30
  4028.7  322.54  4128.8  319.28  4259.3  315.98  4266.2  316.40  4394.7  311.50
  4517.2  308.36  4675.5  305.86  4818.9  306.62  4863.6  305.78  4914.3  306.87
  4920.4  306.21  4977.2  306.74  4982.1  305.68  4986.0  304.83  4992.1  306.68
  5017.8  303.92  5018.1  303.42  5022.1  303.92  5030.2  306.66  5132.1  306.24
  5172.9  306.65  5193.3  307.75  5203.5  307.23  5275.6  308.23  5601.2  311.46
  5682.8  313.37  5744.0  316.60  5958.2  323.84  5988.8  324.76  6019.4  324.15
#Mann=5,-1,0
  4028.7    0.05       0  4982.1    0.12       0  5017.8    0.05       0
  5022.1    0.12       0  5275.6    0.05       0
Bank Sta=5017.8,5022.1
Exp/Cntr=0.3,0.1

Type RM Length L Ch R = 1,9654,474,474,474
BEGIN DESCRIPTION:
THOMPSON BRANCH 17.0
END DESCRIPTION:
XS GIS Cut Line= 3
      2496724.97     13774075.03      2497525.00     13773275.00
      2497074.99     13772474.99
#Sta/Elev= 30
  3860.9  322.00  4228.6  311.83  4299.3  309.10  4398.3  306.99  4511.5  305.84
  4808.5  305.98  4907.5  304.61  4921.6  303.06  4935.7  304.93  4988.8  302.79
  4995.2  302.79  5000.3  304.23  5021.9  304.60  5043.3  304.32  5047.5  301.65
  5047.8  301.15  5051.9  301.65  5059.6  304.17  5077.6  305.29  5231.1  305.42
  5248.9  305.62  5256.2  306.51  5264.8  305.62  5279.1  305.61  5351.5  307.47
  5377.1  307.38  5535.1  308.41  5777.9  311.51  5852.8  313.86  5910.2  317.44
#Mann=6,-1,0
  3860.9    0.05       0  5047.5    0.05       0  5051.9    0.05       0
  5077.6    0.12       0  5231.1    0.07       0  5377.1    0.05       0
Bank Sta=5047.5,5051.9
Exp/Cntr=0.3,0.1

Type RM Length L Ch R = 1,9180,466,466,466
BEGIN DESCRIPTION:
THOMPSON BRANCH 16.0
END DESCRIPTION:
XS GIS Cut Line= 3
      2497724.99     13774375.04      2497925.00     13773175.00
      2497624.99     13772474.98
#Sta/Elev= 30
  3787.8  313.07  3834.7  312.65  4096.5  309.71  4224.3  308.70  4467.1  304.15
  4573.7  304.14  4639.4  303.09  4690.1  303.89  4720.5  302.91  4728.1  303.94
  4733.2  303.05  4740.8  303.89  4771.2  302.75  4862.5  303.87  4882.7  302.85
  4915.7  303.60  4933.4  302.41  4963.8  303.65  4976.5  303.04  4981.9  297.80
  4982.2  297.30  4986.3  297.80  4994.3  301.48  5001.9  303.33  5124.1  301.74
  5267.9  304.41  5406.9  305.14  5483.1  306.54  5680.8  311.03  5766.0  314.25
#Mann=8,-1,0
  3787.8    0.12       0  3834.7    0.07       0  4096.5    0.05       0
  4224.3    0.07       0  4573.7    0.12       0  4981.9    0.05       0
  4986.3    0.12       0  5267.9    0.05       0
Bank Sta=4981.9,4986.3
Exp/Cntr=0.3,0.1

Type RM Length L Ch R = 1,8714,568,568,568
BEGIN DESCRIPTION:
THOMPSON BRANCH 15.0
END DESCRIPTION:
XS GIS Cut Line= 3
      2497825.01     13774174.98      2498325.00     13773075.00
      2497525.03     13772275.03
#Sta/Elev= 30
  3791.6  311.80  3823.4  311.12  4001.4  311.93  4168.5  309.24  4358.4  304.06
  4446.6  303.06  4516.6  302.12  4530.8  300.16  4548.4  301.57  4571.5  301.83
  4600.0  300.44  4605.5  301.44  4637.4  302.60  4758.2  301.52  4910.9  302.15
  4955.9  300.55  4985.6  301.13  4997.1  299.11  5003.4  299.11  5011.7  295.45
  5012.0  294.95  5016.4  295.45  5028.2  300.78  5056.4  299.59  5141.3  300.99
  5234.4  304.07  5339.3  304.20  5721.1  309.00  5876.7  314.65  6131.2  321.02
#Mann=6,-1,0
  3791.6    0.05       0  4168.5    0.07       0  4446.6    0.12       0
  5011.7    0.05       0  5016.4    0.12       0  5234.4    0.05       0
Bank Sta=5011.7,5016.4
Exp/Cntr=0.3,0.1

Type RM Length L Ch R = 1,8146,335,335,335
BEGIN DESCRIPTION:
THOMPSON BRANCH 14.0
END DESCRIPTION:
XS GIS Cut Line= 3
      2498895.65     13774125.43      2498808.01     13773104.07
      2498525.02     13772525.04
#Sta/Elev= 30
  3996.4  314.05  4187.5  308.90  4207.6  308.91  4217.6  308.06  4358.2  303.99
  4398.3  303.67  4413.4  302.69  4650.0  299.26  4749.0  298.22  4829.9  297.85
  4870.0  299.92  4949.5  300.54  4980.4  298.45  4990.5  293.41  4996.9  294.18
  4999.3  292.93  4999.7  292.43  5004.6  292.93  5018.5  297.90  5031.6  299.06
  5044.0  298.60  5058.9  299.61  5098.4  299.08  5173.6  301.68  5196.1  300.97
  5257.6  301.95  5477.4  305.71  5510.2  307.40  5516.9  306.91  5666.0  308.86
#Mann=8,-1,0
  3996.4    0.05       0  4650.0    0.07       0  4749.0    0.12       0
  4949.5   0.035       0  4999.3   0.035       0  5004.6   0.035       0
  5058.9    0.12       0  5257.6   0.035       0
Bank Sta=4999.3,5004.6
Exp/Cntr=0.3,0.1

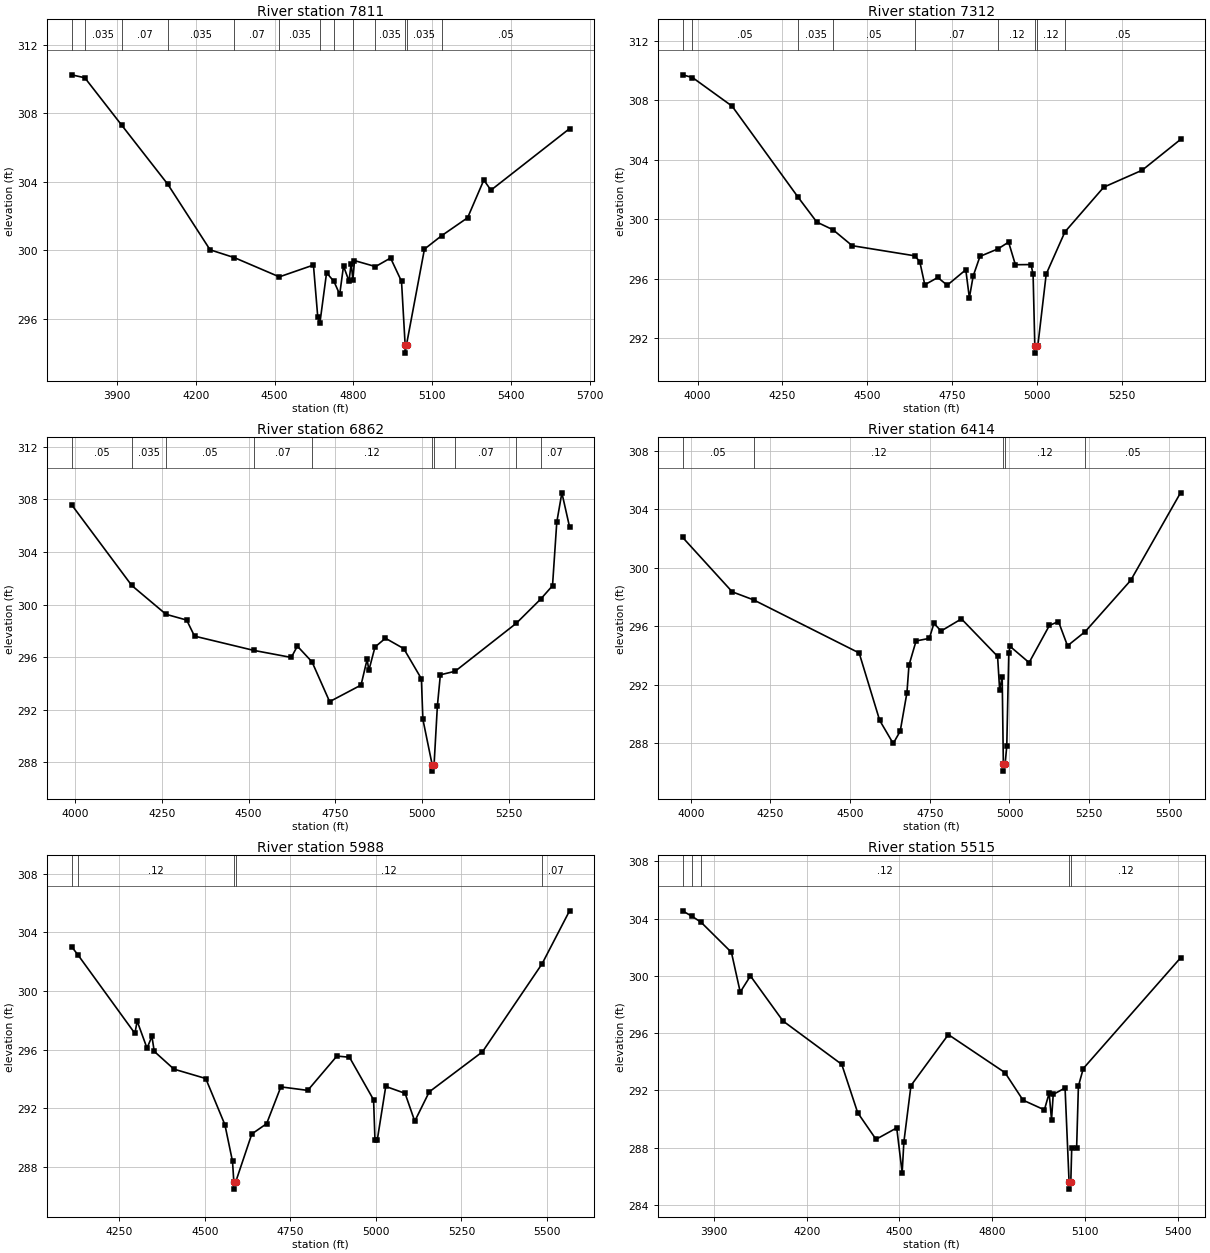
Type RM Length L Ch R = 1,7811,499,499,499
BEGIN DESCRIPTION:
THOMPSON BRANCH 13.0
END DESCRIPTION:
XS GIS Cut Line= 3
      2499862.62     13774046.88      2499110.18     13773043.64
      2499007.52     13772409.55
#Sta/Elev= 30
  3726.9  310.24  3777.2  310.07  3918.4  307.29  4093.5  303.85  4254.3  300.03
  4347.3  299.57  4518.1  298.45  4648.0  299.14  4664.6  296.08  4672.6  295.76
  4698.0  298.69  4726.2  298.18  4748.0  297.43  4762.5  299.08  4783.4  298.20
  4791.7  299.23  4798.3  298.28  4804.3  299.40  4884.3  299.05  4941.7  299.55
  4983.4  298.19  4997.1  294.50  4997.5  294.00  5002.5  294.50  5070.7  300.07
  5135.9  300.85  5235.1  301.90  5296.8  304.10  5324.0  303.51  5623.3  307.10
#Mann=13,-1,0
  3726.9    0.07       0  3777.2   0.035       0  3918.4    0.07       0
  4093.5   0.035       0  4347.3    0.07       0  4518.1   0.035       0
  4672.6    0.07       0  4726.2   0.035       0  4798.3    0.07       0
  4884.3   0.035       0  4997.1   0.035       0  5002.5   0.035       0
  5135.9    0.05       0
Bank Sta=4997.1,5002.5
Exp/Cntr=0.3,0.1

Type RM Length L Ch R = 1,7312,450,450,450
BEGIN DESCRIPTION:
THOMPSON BRANCH 12.0
END DESCRIPTION:
XS GIS Cut Line= 3
      2499875.00     13773925.00      2499575.00     13772925.00
      2499275.00     13772625.00
#Sta/Elev= 30
  3955.5  309.72  3984.7  309.54  4101.7  307.61  4295.7  301.50  4351.4  299.81
  4399.3  299.29  4455.8  298.22  4640.0  297.54  4655.0  297.15  4669.8  295.59
  4708.1  296.08  4735.9  295.56  4790.7  296.60  4801.2  294.71  4812.5  296.18
  4832.5  297.50  4885.9  298.01  4916.9  298.46  4936.9  296.94  4983.0  296.95
  4989.1  296.30  4994.2  291.49  4994.6  290.99  4999.6  291.49  5003.1  291.49
  5027.8  296.31  5083.0  299.15  5197.5  302.16  5310.7  303.30  5423.8  305.37
#Mann=9,-1,0
  3955.5    0.07       0  3984.7    0.05       0  4295.7   0.035       0
  4399.3    0.05       0  4640.0    0.07       0  4885.9    0.12       0
  4994.2    0.05       0  4999.6    0.12       0  5083.0    0.05       0
Bank Sta=4994.2,4999.6
Exp/Cntr=0.3,0.1

Type RM Length L Ch R = 1,6862,448,448,448
BEGIN DESCRIPTION:
THOMPSON BRANCH 11.0
END DESCRIPTION:
XS GIS Cut Line= 3
      2499875.00     13773775.02      2499975.00     13772775.00
      2499625.02     13772525.01
#Sta/Elev= 30
  3989.7  307.59  4163.1  301.45  4261.8  299.26  4321.4  298.82  4344.0  297.60
  4514.0  296.52  4622.9  295.98  4640.4  296.84  4682.7  295.64  4733.4  292.62
  4823.9  293.88  4841.4  295.83  4846.5  295.00  4864.1  296.77  4894.2  297.44
  4947.0  296.65  4997.8  294.36  5002.1  291.28  5028.8  287.84  5029.2  287.34
  5034.4  287.84  5043.9  292.29  5052.5  294.66  5095.1  294.93  5271.5  298.58
  5341.8  300.42  5375.7  301.43  5388.0  306.26  5402.7  308.49  5424.8  305.90
#Mann=10,-1,0
  3989.7    0.05       0  4163.1   0.035       0  4261.8    0.05       0
  4514.0    0.07       0  4682.7    0.12       0  5028.8    0.05       0
  5034.4    0.12       0  5095.1    0.07       0  5271.5    0.05       0
  5341.8    0.07       0
Bank Sta=5028.8,5034.4
Exp/Cntr=0.3,0.1

Type RM Length L Ch R = 1,6414,426,426,426
BEGIN DESCRIPTION:
THOMPSON BRANCH 10.0
END DESCRIPTION:
XS GIS Cut Line= 3
      2501125.03     13773275.03      2500325.00     13772625.00
      2499975.02     13772225.02
#Sta/Elev= 30
  3974.3  302.09  4130.2  298.36  4197.2  297.81  4528.4  294.18  4592.8  289.57
  4635.2  287.99  4657.2  288.83  4678.3  291.46  4684.7  293.34  4707.0  295.00
  4748.7  295.18  4763.0  296.21  4785.3  295.68  4849.3  296.51  4962.7  293.95
  4969.2  291.63  4977.1  292.56  4980.8  286.60  4981.2  286.10  4986.4  286.60
  4991.5  287.82  4997.9  294.19  5001.9  294.63  5061.6  293.52  5125.2  296.06
  5153.7  296.33  5182.1  294.67  5237.6  295.64  5380.5  299.15  5536.6  305.13
#Mann=5,-1,0
  3974.3    0.05       0  4197.2    0.12       0  4980.8    0.05       0
  4986.4    0.12       0  5237.6    0.05       0
Bank Sta=4980.8,4986.4
Exp/Cntr=0.3,0.1

Type RM Length L Ch R = 1,5988,473,473,473
BEGIN DESCRIPTION:
THOMPSON BRANCH 9.0
END DESCRIPTION:
XS GIS Cut Line= 3
      2501175.03     13773125.04      2500625.00     13772425.00
      2500224.97     13772024.97
#Sta/Elev= 30
  4110.1  303.02  4129.6  302.43  4295.4  297.10  4301.8  297.95  4330.7  296.10
  4345.1  296.90  4351.8  295.88  4409.3  294.67  4502.4  294.03  4558.4  290.88
  4580.7  288.38  4584.5  286.99  4585.0  286.49  4590.1  286.99  4637.1  290.25
  4680.4  290.95  4722.0  293.46  4800.6  293.22  4885.9  295.56  4922.6  295.48
  4993.1  292.58  4997.2  289.84  5003.9  289.84  5028.7  293.49  5085.2  293.02
  5113.5  291.12  5155.9  293.12  5311.5  295.85  5485.8  301.85  5566.1  305.46
#Mann=5,-1,0
  4110.1    0.05       0  4129.6    0.12       0  4584.5    0.05       0
  4590.1    0.12       0  5485.8    0.07       0
Bank Sta=4584.5,4590.1
Exp/Cntr=0.3,0.1

Type RM Length L Ch R = 1,5515,442,442,442
BEGIN DESCRIPTION:
THOMPSON BRANCH 8.0
END DESCRIPTION:
XS GIS Cut Line= 3
      2501274.99     13773174.98      2500775.00     13772075.00
      2500424.99     13771875.00
#Sta/Elev= 30
  3798.2  304.55  3829.3  304.16  3857.8  303.76  3956.4  301.65  3984.9  298.87
  4017.9  300.00  4123.3  296.85  4313.4  293.82  4365.0  290.44  4424.3  288.58
  4491.3  289.38  4508.9  286.24  4514.4  288.39  4537.4  292.34  4658.3  295.90
  4841.7  293.24  4899.9  291.32  4969.1  290.64  4984.5  291.81  4992.2  289.94
  4997.7  291.72  5036.0  292.17  5049.0  285.60  5049.5  285.10  5054.6  285.60
  5057.6  287.99  5073.4  287.97  5079.2  292.30  5095.0  293.53  5409.6  301.26
#Mann=5,-1,0
  3798.2    0.05       0  3829.3    0.07       0  3857.8    0.12       0
  5049.0    0.05       0  5054.6    0.12       0
Bank Sta=5049,5054.6
Exp/Cntr=0.3,0.1

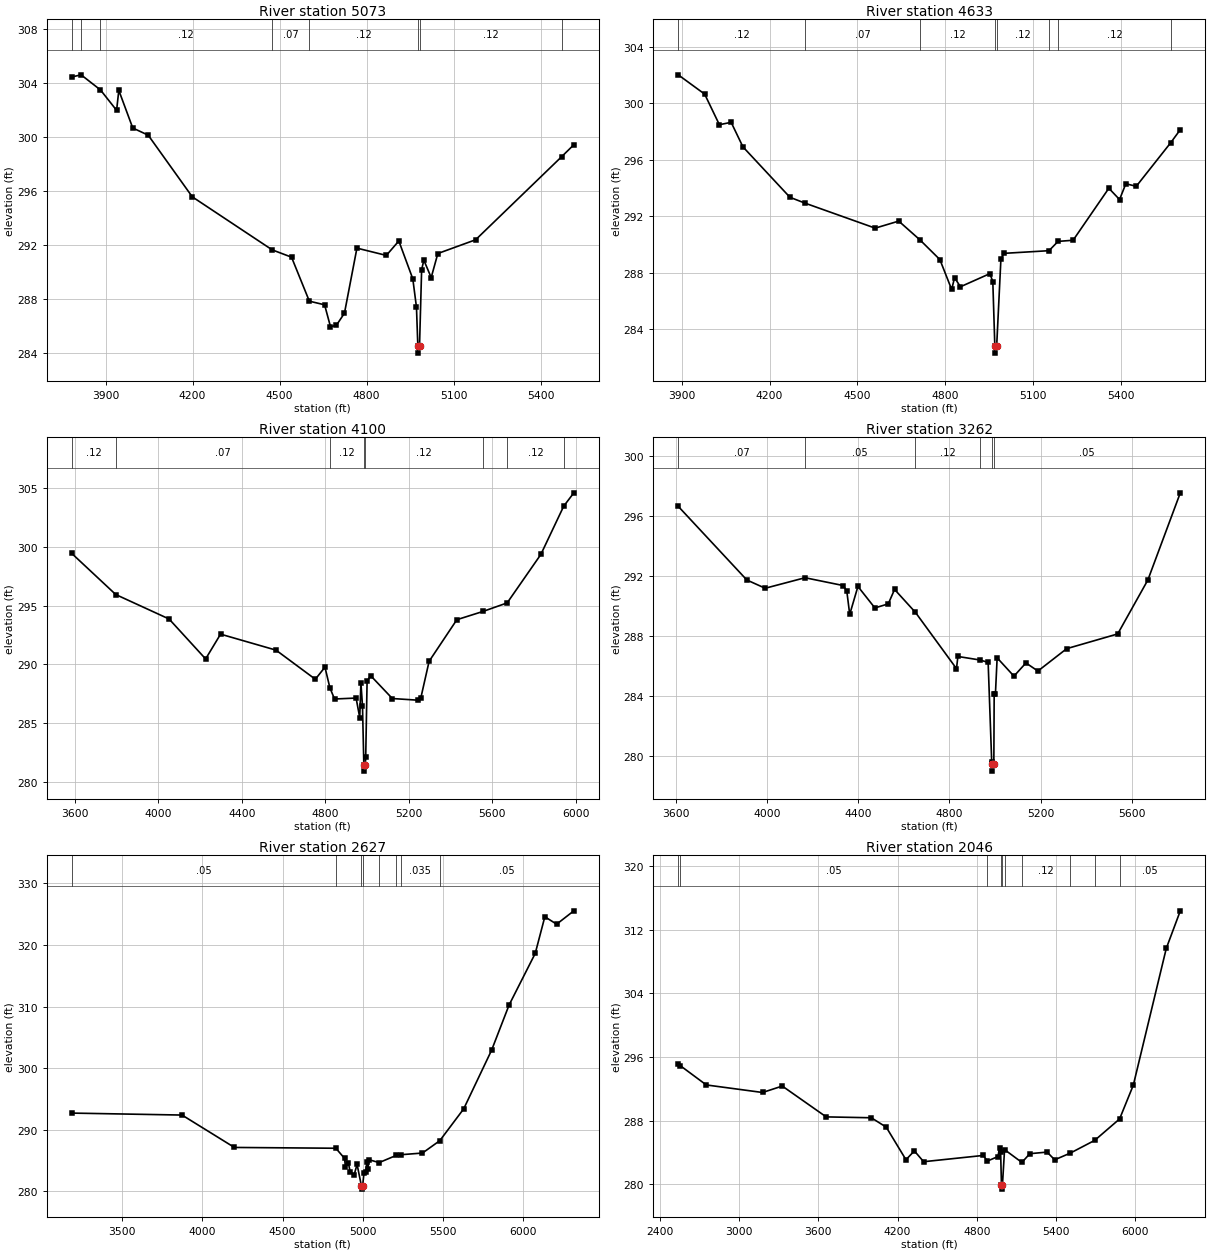
Type RM Length L Ch R = 1,5073,440,440,440
BEGIN DESCRIPTION:
THOMPSON BRANCH 7.0
END DESCRIPTION:
XS GIS Cut Line= 3
      2501324.99     13773174.96      2501125.00     13771975.00
      2500875.00     13771525.00
#Sta/Elev= 30
  3783.5  304.43  3815.7  304.59  3882.5  303.47  3938.1  301.96  3945.7  303.44
  3993.8  300.65  4047.0  300.12  4199.1  295.55  4474.7  291.62  4541.3  291.08
  4602.7  287.82  4655.3  287.55  4675.6  285.93  4695.9  286.03  4723.8  286.93
  4766.8  291.75  4868.2  291.21  4911.3  292.28  4959.5  289.47  4972.1  287.38
  4976.9  284.47  4977.3  283.97  4982.6  284.47  4989.9  290.14  4997.5  290.86
  5022.9  289.57  5045.8  291.35  5176.2  292.37  5472.5  298.52  5514.8  299.41
#Mann=8,-1,0
  3783.5    0.05       0  3815.7    0.07       0  3882.5    0.12       0
  4474.7    0.07       0  4602.7    0.12       0  4976.9    0.05       0
  4982.6    0.12       0  5472.5    0.07       0
Bank Sta=4976.9,4982.6
Exp/Cntr=0.3,0.1

Type RM Length L Ch R = 1,4633,533,533,533
BEGIN DESCRIPTION:
THOMPSON BRANCH 6.0
END DESCRIPTION:
XS GIS Cut Line= 3
      2501375.00     13772974.96      2501475.00     13771875.00
      2500975.02     13771525.02
#Sta/Elev= 30
  3887.9  302.03  3978.2  300.66  4028.4  298.49  4068.6  298.66  4108.8  296.92
  4269.4  293.34  4320.1  292.93  4560.6  291.15  4641.0  291.65  4713.8  290.31
  4781.5  288.92  4821.7  286.80  4831.7  287.63  4851.8  286.99  4952.2  287.92
  4962.3  287.36  4969.2  282.78  4969.7  282.28  4975.5  282.78  4989.9  288.93
  4999.8  289.36  5154.2  289.55  5185.2  290.21  5236.5  290.29  5358.6  293.98
  5395.2  293.18  5416.6  294.30  5452.3  294.12  5570.2  297.22  5602.7  298.14
#Mann=8,-1,0
  3887.9    0.12       0  4320.1    0.07       0  4713.8    0.12       0
  4969.2    0.05       0  4975.5    0.12       0  5154.2    0.07       0
  5185.2    0.12       0  5570.2    0.07       0
Bank Sta=4969.2,4975.5
Exp/Cntr=0.3,0.1

Type RM Length L Ch R = 1,4100,838,838,838
BEGIN DESCRIPTION:
THOMPSON BRANCH 5.0
END DESCRIPTION:
XS GIS Cut Line= 3
      2501475.01     13772774.98      2501883.33     13771795.14
      2501325.01     13770575.03
#Sta/Elev= 30
  3586.6  299.45  3797.3  295.95  4052.4  293.87  4227.3  290.47  4298.8  292.58
  4564.2  291.22  4752.5  288.74  4798.5  289.77  4822.3  288.00  4844.5  287.06
  4947.6  287.14  4965.1  285.47  4970.6  288.45  4978.2  286.48  4984.7  281.42
  4985.2  280.92  4991.6  281.42  4993.6  282.10  5000.2  288.55  5016.6  289.06
  5121.1  287.10  5242.1  286.96  5257.8  287.18  5297.1  290.27  5429.9  293.81
  5554.5  294.51  5670.7  295.24  5832.1  299.37  5941.6  303.48  5989.9  304.61
#Mann=8,-1,0
  3586.6    0.12       0  3797.3    0.07       0  4822.3    0.12       0
  4984.7    0.05       0  4991.6    0.12       0  5554.5    0.07       0
  5670.7    0.12       0  5941.6    0.07       0
Bank Sta=4984.7,4991.6
Exp/Cntr=0.3,0.1

Type RM Length L Ch R = 1,3262,635,635,635
BEGIN DESCRIPTION:
THOMPSON BRANCH 4.0
END DESCRIPTION:
XS GIS Cut Line= 3
      2501624.99     13772575.02      2502325.00     13771375.00
      2502175.00     13770575.00
#Sta/Elev= 30
  3610.3  296.63  3911.3  291.73  3991.9  291.18  4166.8  291.88  4334.3  291.36
  4350.0  290.99  4362.8  289.44  4398.8  291.30  4473.2  289.87  4531.9  290.14
  4559.6  291.10  4651.4  289.57  4831.3  285.83  4837.5  286.64  4932.5  286.41
  4970.2  286.25  4985.9  279.62  4988.2  279.51  4988.7  279.01  4995.2  279.51
  4996.7  284.12  5002.1  284.12  5009.7  286.55  5083.5  285.33  5136.1  286.21
  5188.6  285.67  5315.0  287.16  5538.8  288.14  5671.1  291.73  5813.5  297.53
#Mann=6,-1,0
  3610.3    0.07       0  4166.8    0.05       0  4651.4    0.12       0
  4932.5    0.05       0  4988.2    0.05       0  4995.2    0.05       0
Bank Sta=4988.2,4995.2
Exp/Cntr=0.3,0.1

Type RM Length L Ch R = 1,2627,581,581,581
BEGIN DESCRIPTION:
THOMPSON BRANCH 3.0
END DESCRIPTION:
XS GIS Cut Line= 3
      2502024.98     13772575.04      2502862.50     13771260.42
      2502293.05     13769795.12
#Sta/Elev= 30
  3185.6  292.71  3873.3  292.39  4199.7  287.13  4832.2  287.00  4886.8  285.35
  4892.1  283.90  4911.1  284.55  4922.0  283.09  4946.6  282.71  4964.7  284.37
  4992.0  280.86  4992.5  280.36  4999.2  280.86  5007.6  282.94  5018.4  283.11
  5025.5  284.74  5030.9  283.56  5039.8  285.13  5102.3  284.67  5209.1  285.84
  5237.8  285.95  5372.4  286.22  5480.5  288.23  5629.6  293.40  5803.6  302.93
  5912.5  310.26  6075.7  318.65  6135.5  324.60  6209.1  323.39  6316.4  325.56
#Mann=8,-1,0
  3185.6    0.05       0  4832.2    0.12       0  4992.0    0.05       0
  4999.2    0.12       0  5102.3   0.035       0  5209.1    0.05       0
  5237.8   0.035       0  5480.5    0.05       0
Bank Sta=4992,4999.2
Exp/Cntr=0.3,0.1

Type RM Length L Ch R = 1,2046,805,805,805
BEGIN DESCRIPTION:
THOMPSON BRANCH 2.0
END DESCRIPTION:
XS GIS Cut Line= 3
      2501924.99     13772725.01      2503300.00     13771121.53
      2503140.28     13769441.00
#Sta/Elev= 30
  2539.5  295.10  2554.7  294.91  2751.9  292.48  3177.7  291.53  3327.0  292.34
  3659.5  288.46  4000.9  288.35  4113.9  287.17  4263.2  283.07  4326.8  284.18
  4397.1  282.82  4849.2  283.61  4879.2  282.90  4959.7  283.47  4971.8  284.60
  4979.8  284.00  4986.2  279.87  4986.7  279.37  4993.4  279.87  5009.6  284.34
  5140.7  282.73  5200.8  283.83  5331.4  284.03  5389.1  283.06  5508.0  283.91
  5692.3  285.51  5880.2  288.20  5984.3  292.46  6233.8  309.67  6339.9  314.39
#Mann=10,-1,0
  2539.5    0.07       0  2554.7    0.05       0  4879.2    0.12       0
  4986.2    0.05       0  4993.4    0.12       0  5009.6    0.05       0
  5140.7    0.12       0  5508.0    0.05       0  5692.3   0.035       0
  5880.2    0.05       0
Bank Sta=4986.2,4993.4
Exp/Cntr=0.3,0.1

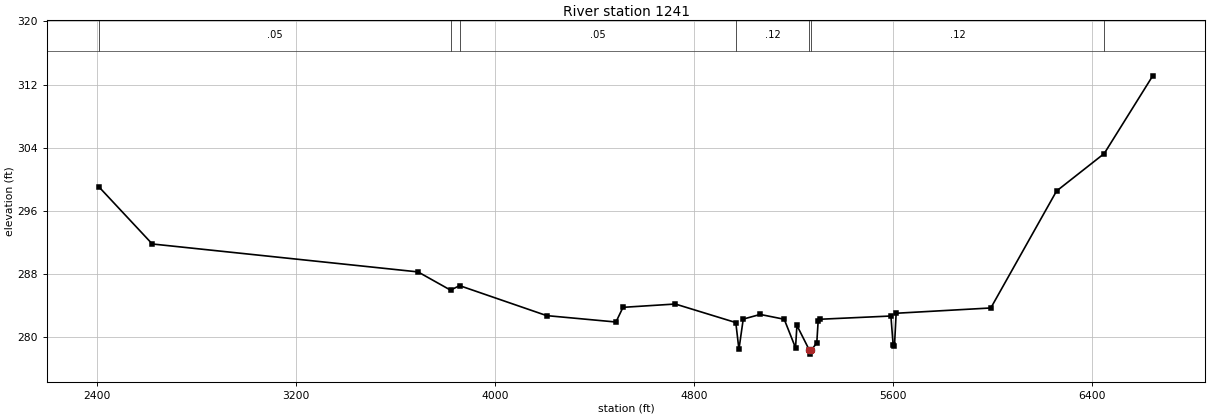
Type RM Length L Ch R = 1,1241,0,0,0
BEGIN DESCRIPTION:
THOMPSON BRANCH 1.0
END DESCRIPTION:
XS GIS Cut Line= 3
      2502591.67     13773267.35      2503800.00     13770711.81
      2503341.93     13769379.25
#Sta/Elev= 30
  2409.1  298.97  2621.9  291.79  3690.6  288.25  3821.4  285.94  3857.8  286.51
  4207.9  282.71  4486.5  281.90  4514.8  283.76  4725.2  284.18  4968.4  281.83
  4981.0  278.43  4998.3  282.27  5066.5  282.86  5163.1  282.25  5208.6  278.63
  5214.2  281.47  5264.3  278.33  5264.8  277.83  5271.9  278.33  5294.1  279.26
  5299.4  281.97  5306.6  282.25  5592.1  282.66  5601.2  278.97  5606.5  278.90
  5613.2  283.01  5993.9  283.68  6258.2  298.50  6449.9  303.25  6645.0  313.10
#Mann=7,-1,0
  2409.1    0.05       0  3821.4   0.035       0  3857.8    0.05       0
  4968.4    0.12       0  5264.3    0.05       0  5271.9    0.12       0
  6449.9    0.05       0
Bank Sta=5264.3,5271.9
Exp/Cntr=0.3,0.1

Chan Stop Cuts=-1