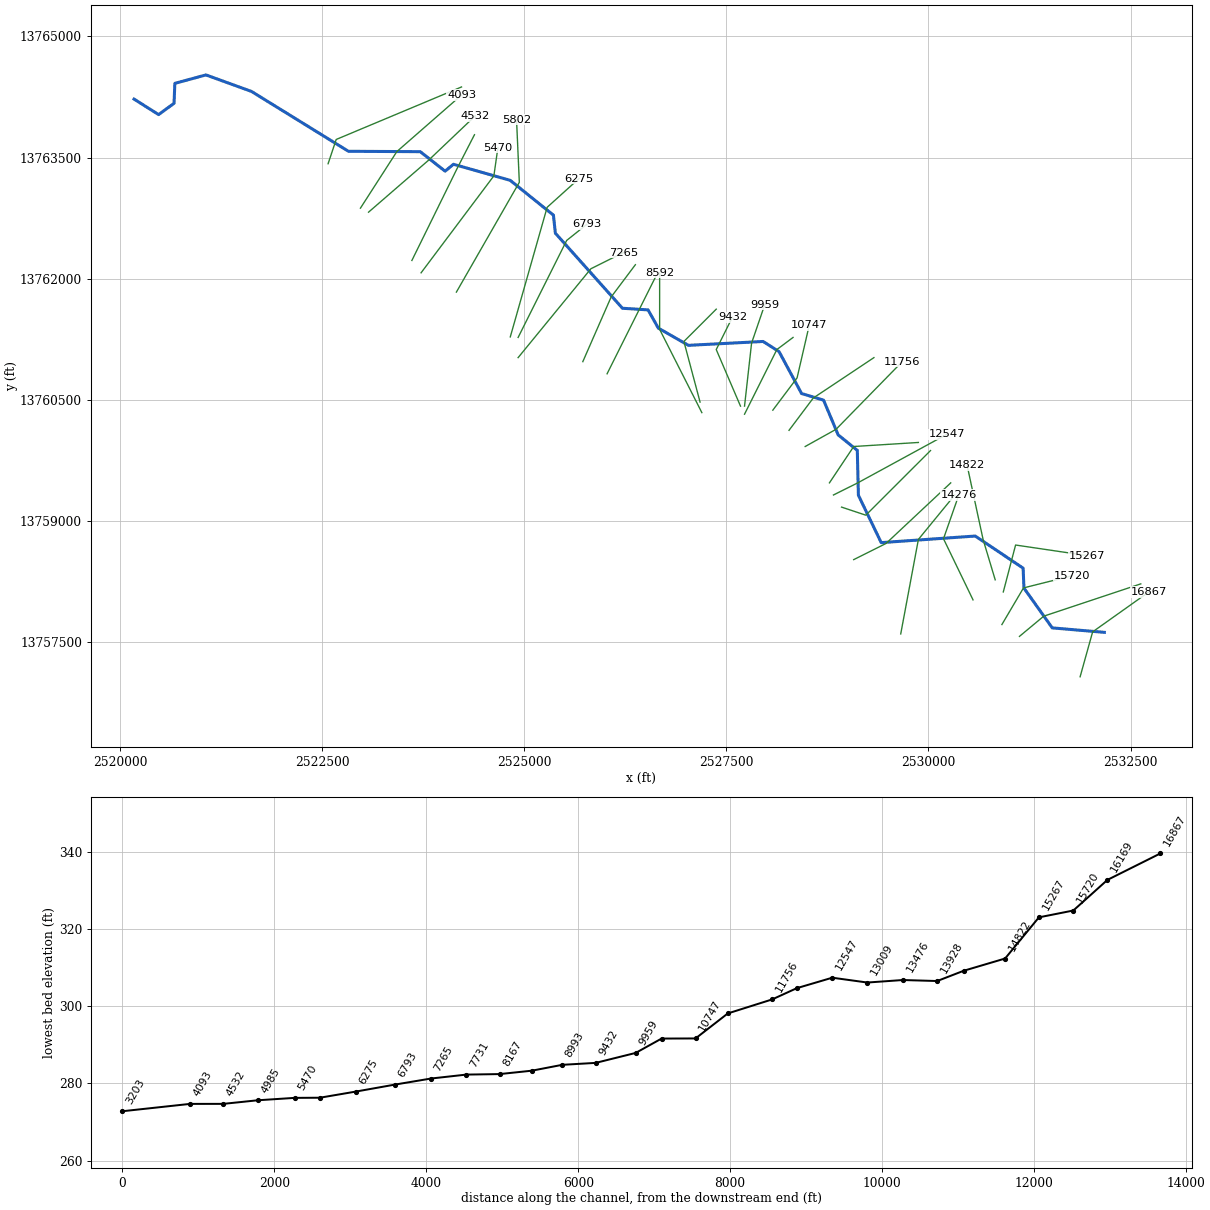
--- VALLEY BRANCH.prj (project) ---

Proj Title=VALLEY BRANCH Base Level Engineering
Current Plan=p01
Default Exp/Contr=0.3,0.1
English Units
Geom File=g01
Flow File=f01
Plan File=p01
Y Axis Title=Elevation
X Axis Title(PF)=Main Channel Distance
X Axis Title(XS)=Station
BEGIN DESCRIPTION:
VALLEY BRANCH
END DESCRIPTION:
DSS Export Rating Curves= 0
DSS Export Rating Curve Sorted= 0
DSS Export Volume Flow Curves= 0
DXF OffsetX= 0
DXF OffsetY= 0
DXF ScaleX= 1
DXF ScaleY= 10

--- VALLEY BRANCH.p01 (plan) ---

Plan Title=Multiple Run
Short Identifier=Multiple
Geom File=g01
Flow File=f01
Subcritical Flow
K Sum by GR= 0
Std Step Tol= 0.01
Critical Tol= 0.01
Num of Std Step Trials= 20
Max Error Tol= 0.3
Flow Tol Ratio= 0.001
Split Flow NTrial= 30
Split Flow Tol= 0.02
Split Flow Ratio= 0.02
Log Output Level= 0
Friction Slope Method= 1
Unsteady Friction Slope Method= 2
Unsteady Bridges Friction Slope Method= 1
Parabolic Critical Depth
Global Vel Dist=  1 , 1 , 1
Global Log Level= 0
CheckData=True
Encroach Param= -1, 0, 0, 0
BEGIN DESCRIPTION:
Multiple Run
END DESCRIPTION:

--- VALLEY BRANCH.f01 (steady flow) ---

Flow Title=Multiple
Number of Profiles=7
Profile Names=10-year,25-year,50-year,1pct_min,100-year,1pct_plu,500-year
River Rch & RM= VALLEY BRANCH,Reach-1,16867
     674    1095    1479     970    1936    3863    3277
River Rch & RM= VALLEY BRANCH,Reach-1,14822
    1137    1877    2561    1690    3372    6728    5789
River Rch & RM= VALLEY BRANCH,Reach-1,8167
    1624    2711    3726    2472    4932    9841    8560
Boundary for River Rch & Prof#=VALLEY BRANCH,Reach-1,1
Up Type=0
Dn Type=3
Dn Slope=0.005
Boundary for River Rch & Prof#=VALLEY BRANCH,Reach-1,2
Up Type=0
Dn Type=3
Dn Slope=0.005
Boundary for River Rch & Prof#=VALLEY BRANCH,Reach-1,3
Up Type=0
Dn Type=3
Dn Slope=0.005
Boundary for River Rch & Prof#=VALLEY BRANCH,Reach-1,4
Up Type=0
Dn Type=3
Dn Slope=0.005
Boundary for River Rch & Prof#=VALLEY BRANCH,Reach-1,5
Up Type=0
Dn Type=3
Dn Slope=0.005
Boundary for River Rch & Prof#=VALLEY BRANCH,Reach-1,6
Up Type=0
Dn Type=3
Dn Slope=0.005
Boundary for River Rch & Prof#=VALLEY BRANCH,Reach-1,7
Up Type=0
Dn Type=3
Dn Slope=0.005

--- VALLEY BRANCH.g01 (geometry) ---

Geom Title=Existing Conditions
Program Version=4.10

River Reach=VALLEY BRANCH   ,Reach-1
Reach XY= 30
        2532175.       13757625.      2531530.44     13757680.18
      2531180.52     13758172.57       2531170.2     13758419.38
      2530578.31     13758816.98      2529415.19     13758735.43
       2529133.1     13759321.71      2529119.54     13759877.45
        2528883.     13760068.67      2528702.19     13760498.97
      2528430.55     13760580.59      2528152.28     13761098.89
      2527955.01     13761225.04      2527030.85     13761177.06
      2526658.22     13761390.69      2526531.95     13761615.82
      2526214.95     13761636.11      2525385.47     13762565.18
      2525361.63     13762788.32       2524827.3     13763219.17
        2524125.     13763417.89      2524021.77     13763332.85
      2523714.57     13763573.95       2522826.5     13763578.61
      2521627.43     13764319.48       2521064.5     13764523.81
      2520679.79     13764419.41      2520669.58     13764172.33
      2520478.41     13764032.81        2520175.       13764225.

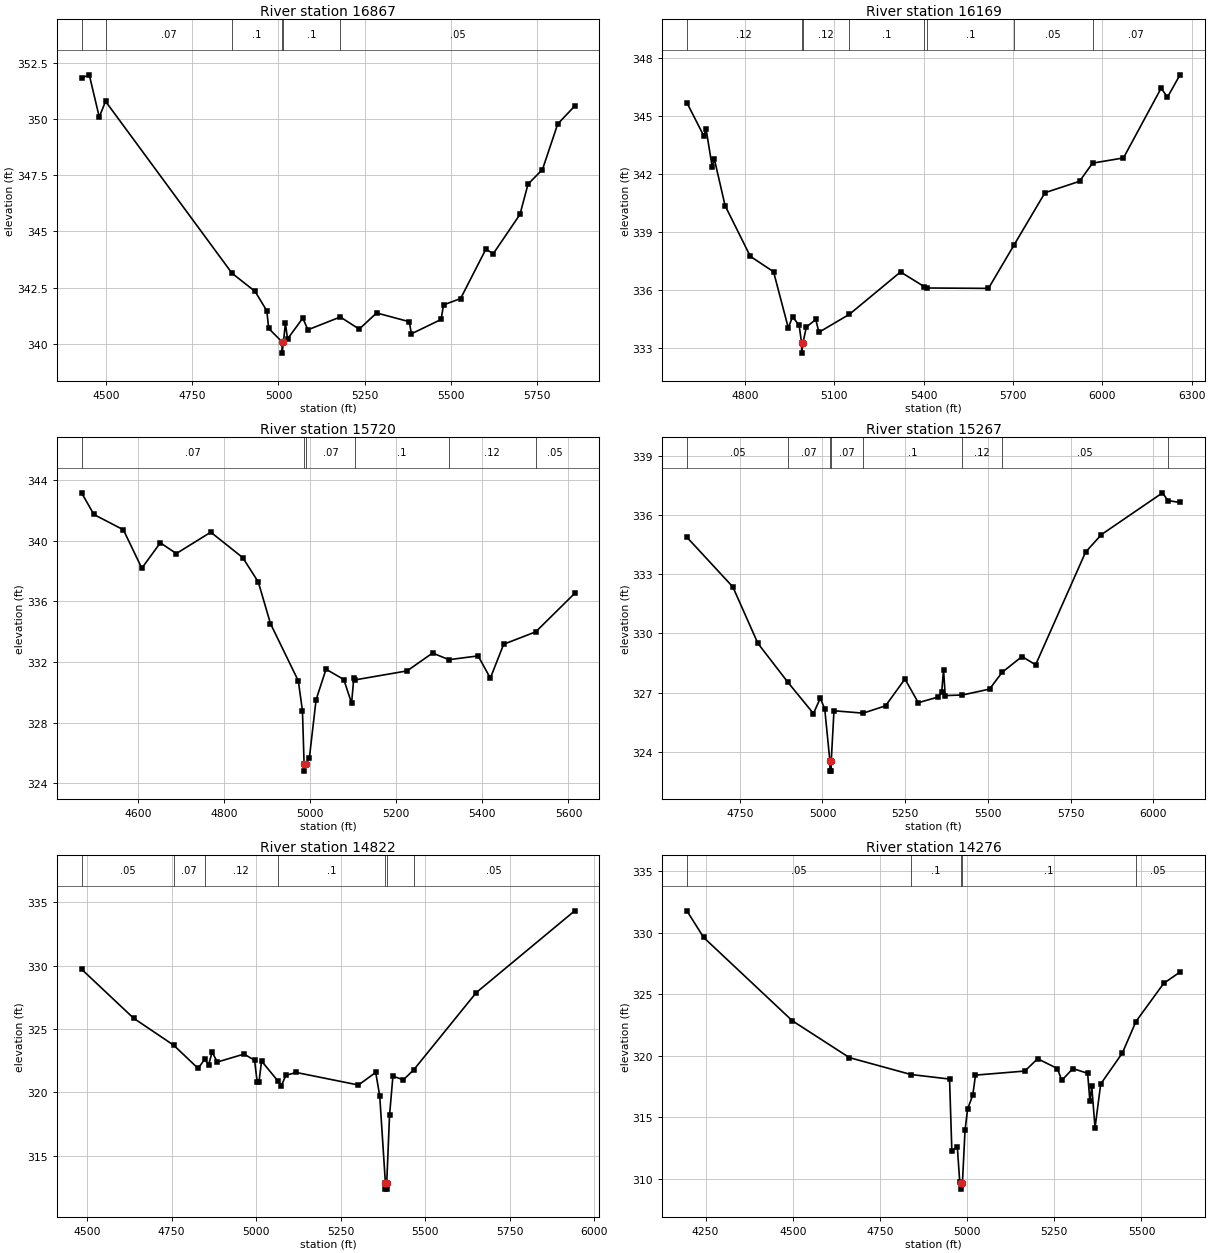
Type RM Length L Ch R = 1 ,16867   ,698,698,698
BEGIN DESCRIPTION:
VALLEY BRANCH 34.0
END DESCRIPTION:
XS GIS Cut Line= 3
      2531875.01     13757075.03        2532030.     13757631.13
        2532725.       13758125.
#Sta/Elev= 30
  4429.1  351.84  4451.4  351.98  4480.4   350.1  4498.6   350.8  4865.3  343.14
  4932.2  342.33  4966.4  341.46  4971.6  340.68  5010.5  340.08  5010.8  339.58
  5014.5  340.08  5020.2  340.91  5026.3  340.21  5070.6  341.14  5085.4  340.62
  5179.3  341.19  5234.2  340.65  5284.6  341.37  5379.3  340.98  5385.5  340.44
  5471.6  341.08  5478.7  341.73  5528.1  342.01  5601.4  344.21  5622.9  344.01
  5700.3  345.76  5723.7  347.11  5765.5  347.76  5809.8  349.79    5859  350.59
#Mann= 6 ,-1 , 0
  4429.1     .12       0  4498.6     .07       0  4865.3      .1       0
  5010.5     .05       0  5014.5      .1       0  5179.3     .05       0
Bank Sta=5010.5,5014.5
XS Rating Curve= 0 ,0
Exp/Cntr=0.3,0.1

Type RM Length L Ch R = 1 ,16169   ,449,449,449
BEGIN DESCRIPTION:
VALLEY BRANCH 33.0
END DESCRIPTION:
XS GIS Cut Line= 3
      2531124.97     13757574.98        2531425.       13757825.
      2532625.04     13758225.01
#Sta/Elev= 30
  4605.5  345.68  4662.2  343.96    4670  344.31  4690.8  342.33  4697.3  342.79
  4733.8  340.35  4818.4  337.73  4896.5  336.93  4945.9  334.03  4960.3   334.6
  4982.4  334.16  4990.8  333.22    4991  332.72  4994.8  333.22  5006.6  334.07
  5038.2  334.46  5048.8   333.8  5151.2  334.73  5322.8  336.92  5402.5  336.16
  5412.4  336.09    5618  336.07    5704  338.32  5807.7  341.02  5923.7  341.61
  5967.3  342.55  6071.2  342.82  6197.7  346.43  6218.8  345.96    6261  347.12
#Mann= 8 ,-1 , 0
  4605.5     .12       0  4990.8     .05       0  4994.8     .12       0
  5151.2      .1       0  5402.5     .12       0  5412.4      .1       0
    5704     .05       0  5967.3     .07       0
Bank Sta=4990.8,4994.8
XS Rating Curve= 0 ,0
Exp/Cntr=0.3,0.1

Type RM Length L Ch R = 1 ,15720   ,453,453,453
BEGIN DESCRIPTION:
VALLEY BRANCH 32.0
END DESCRIPTION:
XS GIS Cut Line= 3
      2530907.79     13757721.45        2531175.       13758175.
      2531775.02       13758325.
#Sta/Elev= 30
  4469.6  343.17  4498.2  341.74  4566.6  340.73  4609.5  338.19  4652.4  339.87
  4689.6  339.16  4769.6  340.57  4843.8  338.89  4879.9  337.28  4908.2  334.53
  4972.8  330.75  4982.4  328.79  4986.2  325.29  4986.4  324.79  4990.2  325.29
  4998.6  325.69  5014.1  329.51  5037.2  331.52  5078.5  330.84  5096.5  329.27
  5101.7  330.96  5105.4  330.82  5225.4  331.41  5284.6  332.59  5322.5  332.15
  5390.3   332.4  5418.6  330.93  5449.6  333.17  5524.1  333.99  5614.5  336.53
#Mann= 6 ,-1 , 0
  4469.6     .07       0  4986.2     .05       0  4990.2     .07       0
  5105.4      .1       0  5322.5     .12       0  5524.1     .05       0
Bank Sta=4986.2,4990.2
XS Rating Curve= 0 ,0
Exp/Cntr=0.3,0.1

Type RM Length L Ch R = 1 ,15267   ,445,445,445
BEGIN DESCRIPTION:
VALLEY BRANCH 31.0
END DESCRIPTION:
XS GIS Cut Line= 3
        2530925.       13758125.      2531077.08     13758705.73
      2531957.29     13758575.52
#Sta/Elev= 30
  4590.2  334.88  4729.1  332.36  4804.7   329.5  4895.2  327.53  4972.7  325.94
  4993.4  326.72  5006.8  326.17  5022.4  323.52  5022.6  323.02  5026.1  323.02
  5026.4  323.52  5034.7  326.08  5122.8  325.96  5190.5  326.33  5249.1  327.69
  5289.5  326.49  5350.1  326.78  5360.3  327.05  5365.8  328.15  5370.9  326.85
    5423  326.88  5504.9  327.18  5542.8  328.03  5602.9  328.83    5644  328.41
  5794.9  334.12  5842.6  335.01  6027.4  337.13  6043.5  336.74  6080.3  336.64
#Mann= 8 ,-1 , 0
  4590.2     .05       0  4895.2     .07       0  5022.4     .05       0
  5026.4     .07       0  5122.8      .1       0    5423     .12       0
  5542.8     .05       0  6043.5     .07       0
Bank Sta=5022.4,5026.4
XS Rating Curve= 0 ,0
Exp/Cntr=0.3,0.1

Type RM Length L Ch R = 1 ,14822   ,546,546,546
BEGIN DESCRIPTION:
VALLEY BRANCH 30.0
END DESCRIPTION:
XS GIS Cut Line= 3
      2530825.01     13758274.96        2530675.       13758775.
      2530477.88     13759690.36
#Sta/Elev= 30
  4483.7  329.72  4637.7  325.85  4756.2  323.72  4828.3  321.89  4847.6   322.6
  4859.6  322.19    4870  323.19  4884.8  322.39    4964  323.02  4995.3  322.54
  5003.1   320.8  5008.3   320.8    5016  322.47  5063.4  320.93  5074.6  320.52
  5087.6  321.34  5118.3  321.57  5302.4  320.58  5353.6  321.57  5365.5  319.72
  5382.2  312.86  5382.5  312.36    5386  312.36  5386.2  312.86  5394.5  318.18
  5404.5  321.28  5435.4  320.99  5466.1  321.78  5651.2  327.88  5942.1  334.33
#Mann= 7 ,-1 , 0
  4483.7     .05       0  4756.2     .07       0  4847.6     .12       0
  5063.4      .1       0  5382.2     .05       0  5386.2      .1       0
  5466.1     .05       0
Bank Sta=5382.2,5386.2
XS Rating Curve= 0 ,0
Exp/Cntr=0.3,0.1

Type RM Length L Ch R = 1 ,14276   ,348,348,348
BEGIN DESCRIPTION:
VALLEY BRANCH 29.0
END DESCRIPTION:
XS GIS Cut Line= 3
      2530550.92     13758026.67      2530185.43     13758783.45
        2530375.     13759325.01
#Sta/Elev= 30
  4196.4  331.76  4244.5   329.6  4498.7  322.84  4662.5  319.85  4838.8  318.48
  4949.7  318.11  4956.3  312.28  4971.9  312.62  4978.9  309.78  4982.2  309.68
  4982.5  309.18  4986.6  309.68  4994.1  313.96  5001.5  315.68  5016.3  316.81
  5024.1  318.43  5165.6  318.76  5202.3  319.76  5259.1  318.96  5271.5     318
  5303.3  318.96  5345.7  318.58  5352.2  316.32  5357.5  317.51  5366.9  314.16
  5383.2  317.71  5445.2  320.22  5484.3  322.78    5564  325.88  5610.6  326.79
#Mann= 5 ,-1 , 0
  4196.4     .05       0  4838.8      .1       0  4982.2     .05       0
  4986.6      .1       0  5484.3     .05       0
Bank Sta=4982.2,4986.6
XS Rating Curve= 0 ,0
Exp/Cntr=0.3,0.1

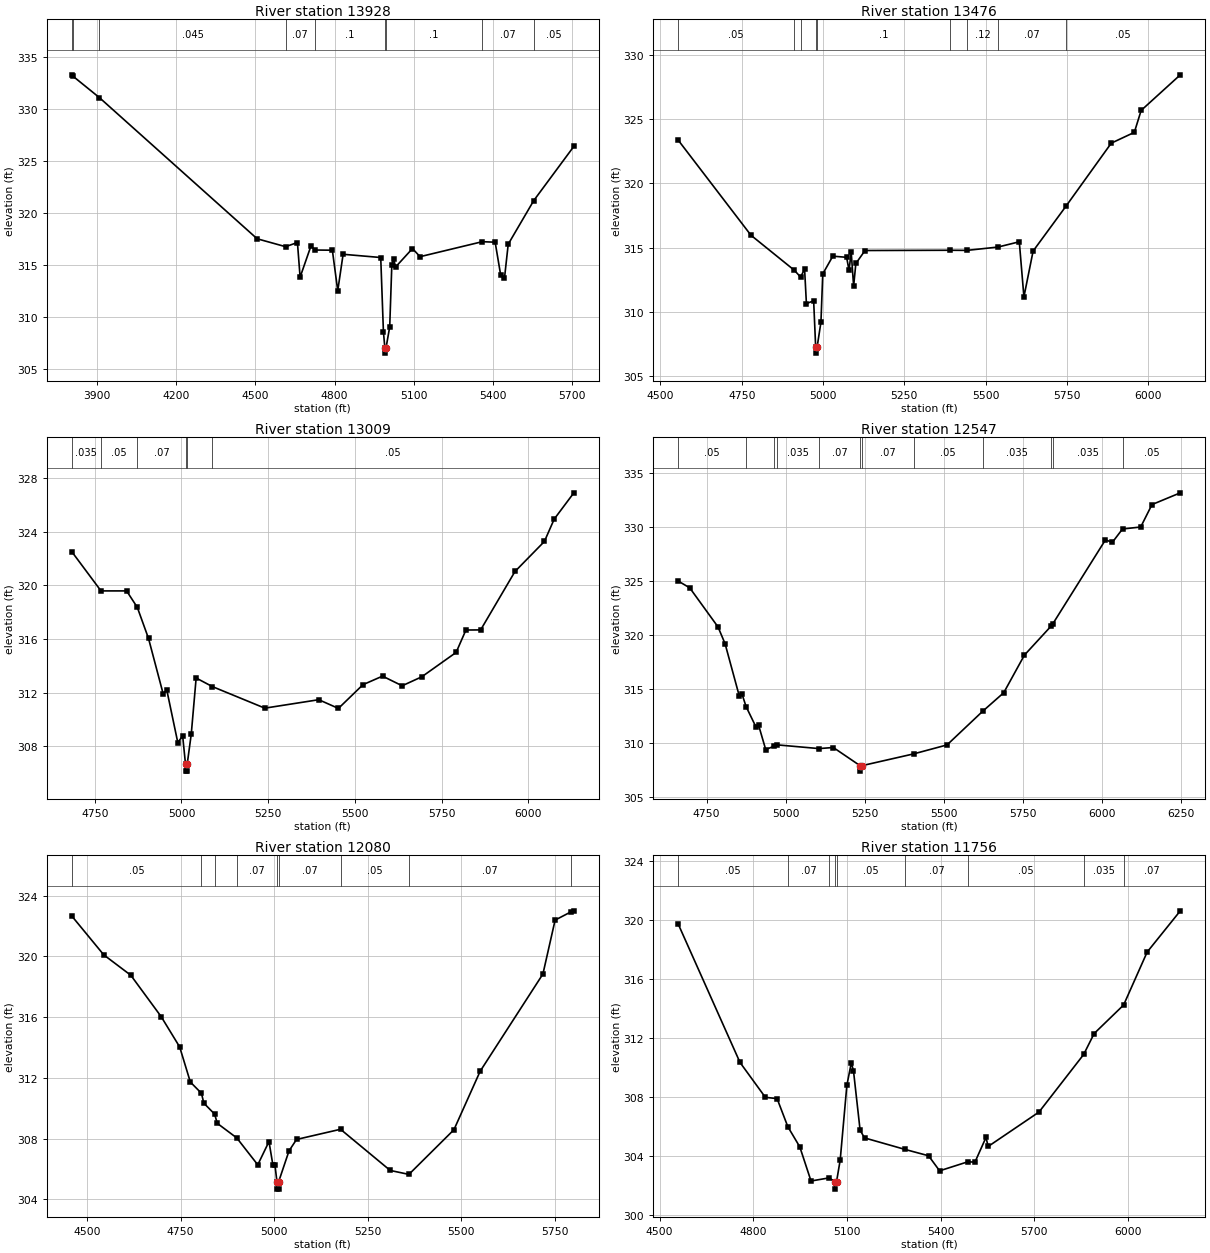
Type RM Length L Ch R = 1 ,13928   ,452,452,452
BEGIN DESCRIPTION:
VALLEY BRANCH 28.0
END DESCRIPTION:
XS GIS Cut Line= 3
      2529656.57     13757605.35        2529875.       13758775.
        2530325.       13759325.
#Sta/Elev= 30
  3805.3  333.25  3809.3  333.13    3910  331.06  4506.9  317.51  4614.6  316.75
  4659.5  317.15  4669.6  313.82  4710.3  316.79  4726.1  316.43  4791.7  316.41
  4812.1  312.52  4832.4  316.02  4974.8  315.71    4985  308.58  4990.4  307.03
  4990.7  306.53  4994.8  307.03  5008.8  309.05  5016.7  314.95  5023.2   315.6
  5031.1   314.8  5094.9  316.57  5123.7  315.79  5359.3  317.23  5407.9  317.18
  5428.7  314.05  5443.1   313.7  5457.4  316.99  5554.1  321.18  5705.8  326.38
#Mann= 9 ,-1 , 0
  3805.3     .07       0  3809.3     .12       0    3910    .045       0
  4614.6     .07       0  4726.1      .1       0  4990.4     .05       0
  4994.8      .1       0  5359.3     .07       0  5554.1     .05       0
Bank Sta=4990.4,4994.8
XS Rating Curve= 0 ,0
Exp/Cntr=0.3,0.1

Type RM Length L Ch R = 1 ,13476   ,467,467,467
BEGIN DESCRIPTION:
VALLEY BRANCH 27.0
END DESCRIPTION:
XS GIS Cut Line= 3
      2529075.03     13758525.01        2529475.       13758725.
      2530275.02     13759475.02
#Sta/Elev= 30
  4554.7  323.37  4778.3  315.97  4911.8  313.24    4931  312.71  4943.2  313.34
  4948.8  310.65  4971.1  310.86  4977.2  307.29  4977.5  306.79  4981.9  307.29
  4993.5   309.2  4999.1  312.96    5030  314.34  5072.5  314.25  5079.8  313.24
  5086.6  314.64    5094     312  5100.8  313.77  5129.1  314.78  5389.7   314.8
  5442.1  314.79    5538  315.05  5603.4  315.46  5617.6  311.17  5645.9  314.74
  5747.5  318.25  5886.2  323.14  5957.1  323.98  5978.1  325.69  6098.5  328.46
#Mann= 9 ,-1 , 0
  4554.7     .05       0  4911.8     .07       0    4931      .1       0
  4977.2     .05       0  4981.9      .1       0  5389.7     .07       0
  5442.1     .12       0    5538     .07       0  5747.5     .05       0
Bank Sta=4977.2,4981.9
XS Rating Curve= 0 ,0
Exp/Cntr=0.3,0.1

Type RM Length L Ch R = 1 ,13009   ,462,462,462
BEGIN DESCRIPTION:
VALLEY BRANCH 26.0
END DESCRIPTION:
XS GIS Cut Line= 3
      2528925.02     13759174.99        2529225.       13759075.
      2530025.02     13759875.02
#Sta/Elev= 30
  4683.8  322.52  4768.1  319.59  4841.9  319.59  4872.8  318.36  4905.1  316.04
  4947.3  311.91  4957.8  312.19  4989.5  308.27  5003.5  308.77  5011.8  306.64
  5012.1  306.14  5016.2  306.14  5016.5  306.64  5028.3   308.9  5042.4  313.09
  5089.1  312.45  5240.4  310.84    5396  311.47  5452.6  310.82  5523.3  312.59
  5579.8  313.23  5636.4  312.51    5693  313.18    5792     315  5820.2  316.67
  5862.7  316.68  5961.7  321.04  6046.5  323.28  6074.8  324.95  6131.4  326.91
#Mann= 6 ,-1 , 0
  4683.8    .035       0  4768.1     .05       0  4872.8     .07       0
  5011.8     .05       0  5016.5     .07       0  5089.1     .05       0
Bank Sta=5011.8,5016.5
XS Rating Curve= 0 ,0
Exp/Cntr=0.3,0.1

Type RM Length L Ch R = 1 ,12547   ,467,467,467
BEGIN DESCRIPTION:
VALLEY BRANCH 25.0
END DESCRIPTION:
XS GIS Cut Line= 3
      2528824.98     13759324.99        2529125.       13759475.
      2530224.97     13760074.99
#Sta/Elev= 30
  4660.4  325.01  4696.8  324.38  4786.2  320.76  4808.6   319.2  4853.3  314.38
  4861.7  314.57  4875.1  313.37  4906.4  311.48  4914.8  311.63  4937.1  309.39
  4961.9  309.68  4971.3  309.83  5105.6  309.48    5151  309.58    5236  307.89
  5236.3  307.39  5240.7  307.89  5405.4  308.99  5510.8  309.82  5623.2  312.93
  5690.2  314.66  5755.7  318.15  5839.9  320.83  5845.1  321.03    6012  328.83
  6033.8   328.6    6066  329.84  6123.5  330.02  6159.1   332.1  6248.8  333.19
#Mann= 12 ,-1 , 0
  4660.4     .05       0  4875.1    .035       0  4961.9     .05       0
  4971.3    .035       0  5105.6     .07       0    5236    .035       0
  5240.7     .07       0  5405.4     .05       0  5623.2    .035       0
  5839.9     .07       0  5845.1    .035       0    6066     .05       0
Bank Sta=5236,5240.7
XS Rating Curve= 0 ,0
Exp/Cntr=0.3,0.1

Type RM Length L Ch R = 1 ,12080   ,324,324,324
BEGIN DESCRIPTION:
VALLEY BRANCH 24.0
END DESCRIPTION:
XS GIS Cut Line= 3
        2528775.     13759474.99        2529075.       13759925.
        2529875.       13759975.
#Sta/Elev= 30
  4458.8  322.66  4544.4   320.1  4616.6  318.76  4697.7  316.04  4747.3  314.04
  4775.8  311.73  4805.5  310.99  4811.9  310.34  4840.7  309.62  4847.9  309.01
    4900  308.05  4956.1  306.28  4986.1  307.81  4996.6  306.26  5002.1  306.26
  5007.3  305.18  5007.6  304.68  5011.7  304.68  5012.1  305.18  5039.7   307.2
  5059.8  307.95  5177.4  308.62  5310.2  305.91  5360.2  305.65  5480.6  308.59
  5550.7  312.44  5718.5  318.84  5751.1  322.39  5794.1  322.94  5801.2     323
#Mann= 9 ,-1 , 0
  4458.8     .05       0  4805.5     .07       0  4840.7     .05       0
    4900     .07       0  5007.3     .05       0  5012.1     .07       0
  5177.4     .05       0  5360.2     .07       0  5794.1    .035       0
Bank Sta=5007.3,5012.1
XS Rating Curve= 0 ,0
Exp/Cntr=0.3,0.1

Type RM Length L Ch R = 1 ,11756   ,584,584,584
BEGIN DESCRIPTION:
VALLEY BRANCH 23.0
END DESCRIPTION:
XS GIS Cut Line= 3
      2528474.96     13759924.98      2528856.82     13760137.85
      2529675.03     13760975.03
#Sta/Elev= 30
  4559.8  319.72  4757.6  310.35  4838.7  307.99  4876.4   307.9  4910.7     306
  4949.1  304.63    4985  302.32  5042.6  302.53  5061.9  302.27  5062.3  301.77
  5066.7  302.27  5078.5  303.75  5099.8   308.8  5113.9  310.32  5120.9   309.8
  5142.2  305.76  5156.4  305.24  5285.9  304.46  5361.4  304.03  5396.8  303.01
  5486.9  303.62    5510   303.6  5545.3  305.27  5552.3  304.66    5715  306.99
  5858.1  310.89  5891.7  312.31    5986  314.24  6061.5  317.83  6167.6  320.62
#Mann= 9 ,-1 , 0
  4559.8     .05       0  4910.7     .07       0  5042.6     .05       0
  5061.9     .05       0  5066.7     .05       0  5285.9     .07       0
  5486.9     .05       0  5858.1    .035       0    5986     .07       0
Bank Sta=5061.9,5066.7
XS Rating Curve= 0 ,0
Exp/Cntr=0.3,0.1

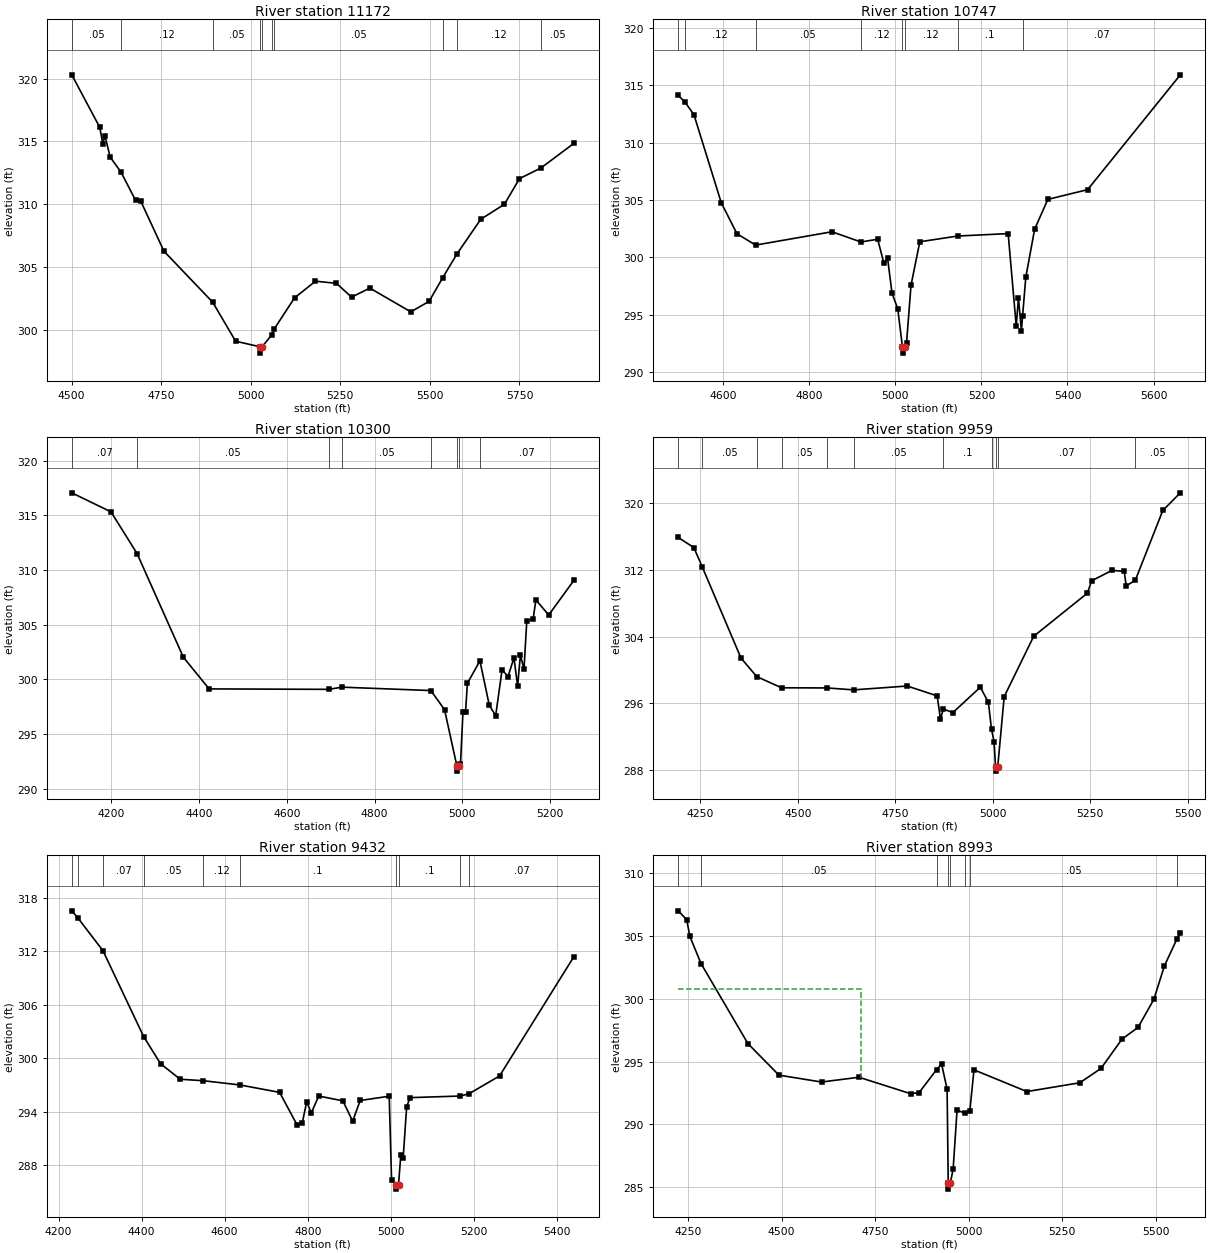
Type RM Length L Ch R = 1 ,11172   ,425,425,425
BEGIN DESCRIPTION:
VALLEY BRANCH 22.0
END DESCRIPTION:
XS GIS Cut Line= 3
      2528274.99     13760124.99        2528575.       13760525.
        2529325.       13761025.
#Sta/Elev= 30
  4500.4  320.31  4578.5  316.13  4586.9  314.83  4593.1  315.44  4607.7  313.75
  4637.6  312.57  4678.5  310.31  4693.1  310.24  4757.7  306.26  4893.9  302.19
  4957.7  299.09  5026.6  298.64  5026.9  298.14  5031.4  298.64  5059.4  299.62
  5065.8  300.08  5122.1  302.54  5180.7  303.87  5239.3   303.7  5281.3   302.6
  5332.4  303.32  5446.6  301.43  5497.7  302.26  5535.4  304.13  5575.5  306.04
  5641.9   308.8    5708     310  5750.1  312.04  5810.5   312.9  5901.8  314.85
#Mann= 10 ,-1 , 0
  4500.4     .05       0  4637.6     .12       0  4893.9     .05       0
  5026.6     .05       0  5031.4     .05       0  5059.4     .12       0
  5065.8     .05       0  5535.4     .07       0  5575.5     .12       0
  5810.5     .05       0
Bank Sta=5026.6,5031.4
XS Rating Curve= 0 ,0
Exp/Cntr=0.3,0.1

Type RM Length L Ch R = 1 ,10747   ,447,447,447
BEGIN DESCRIPTION:
VALLEY BRANCH 21.0
END DESCRIPTION:
XS GIS Cut Line= 3
      2528074.97     13760374.97        2528375.       13760775.
      2528524.99     13761424.97
#Sta/Elev= 30
  4495.2   314.1  4510.2  313.56  4531.7  312.43  4595.2  304.76  4631.7  302.06
  4675.1  301.07  4852.5  302.23    4920  301.34  4958.8  301.58  4973.4  299.47
  4981.7  299.97  4992.1  296.88  5005.5  295.52  5016.5  292.16    5017  291.66
  5021.8  292.16    5026  292.58  5036.3  297.58  5056.8  301.36  5145.1  301.86
  5262.1  302.07  5280.9  294.01    5286  296.46  5292.9  293.63  5295.6  294.86
  5303.1  298.26  5323.7  302.46  5354.4  305.05  5446.8   305.9  5662.3   315.9
#Mann= 8 ,-1 , 0
  4495.2     .07       0  4510.2     .12       0  4675.1     .05       0
    4920     .12       0  5016.5     .05       0  5021.8     .12       0
  5145.1      .1       0  5295.6     .07       0
Bank Sta=5016.5,5021.8
XS Rating Curve= 0 ,0
Exp/Cntr=0.3,0.1

Type RM Length L Ch R = 1 ,10300   ,341,341,341
BEGIN DESCRIPTION:
VALLEY BRANCH 20.0
END DESCRIPTION:
XS GIS Cut Line= 3
      2527724.98     13760324.96        2528125.       13761125.
      2528325.03     13761275.02
#Sta/Elev= 30
  4109.7  317.05  4199.2  315.31  4258.7  311.49  4364.1  302.03  4422.8  299.14
  4695.8   299.1  4725.3   299.3  4928.3  298.99  4959.4  297.25  4987.4  292.13
  4987.8  291.63    4993  292.13  4995.8  292.27  5001.4  296.99  5007.3  296.99
  5011.5  299.65  5040.1   301.7  5061.5  297.64    5076   296.7  5090.6  300.88
  5104.2  300.27  5117.7  301.98    5126  299.41  5132.3   302.2  5140.6  300.97
  5146.9  305.35  5161.5  305.56  5167.7  307.27  5196.9  305.89  5254.2  309.05
#Mann= 8 ,-1 , 0
  4109.7     .07       0  4258.7     .05       0  4695.8     .12       0
  4725.3     .05       0  4928.3      .1       0  4987.4     .05       0
    4993      .1       0  5040.1     .07       0
Bank Sta=4987.4,4993
XS Rating Curve= 0 ,0
Exp/Cntr=0.3,0.1

Type RM Length L Ch R = 1 ,9959    ,527,527,527
BEGIN DESCRIPTION:
VALLEY BRANCH 19.0
END DESCRIPTION:
XS GIS Cut Line= 3
        2527725.       13760425.      2527811.99     13761204.18
      2527975.13     13761680.71
#Sta/Elev= 30
  4193.3  315.86  4233.4  314.65  4254.7  312.36  4354.3  301.43  4394.6  299.22
  4458.2  297.88  4575.2  297.86  4643.2  297.63  4780.5  298.09  4857.4  296.91
  4865.8  294.16  4873.3  295.34  4897.6  294.91  4968.1  297.95  4988.8  296.13
  4996.8   292.9  5003.3  291.45  5007.1  288.41  5007.5  287.91  5012.7  288.41
  5029.3  296.82    5105  304.04  5242.4  309.19  5253.7  310.68  5305.7  311.92
    5337  311.81  5342.3  310.07  5365.6  310.74  5436.1  319.09    5481   321.2
#Mann= 11 ,-1 , 0
  4193.3     .07       0  4254.7     .05       0  4394.6     .07       0
  4458.2     .05       0  4575.2     .12       0  4643.2     .05       0
  4873.3      .1       0  4996.8     .07       0  5007.1     .05       0
  5012.7     .07       0  5365.6     .05       0
Bank Sta=5007.1,5012.7
XS Rating Curve= 0 ,0
Exp/Cntr=0.3,0.1

Type RM Length L Ch R = 1 ,9432    ,439,439,439
BEGIN DESCRIPTION:
VALLEY BRANCH 18.0
END DESCRIPTION:
XS GIS Cut Line= 3
      2527674.99     13760425.03        2527375.       13761125.
      2527575.02     13761525.04
#Sta/Elev= 30
  4231.9  316.54    4246  315.78  4307.1  312.06    4405  302.43  4445.8  299.39
    4493  297.65  4548.6  297.49  4637.1  297.01  4732.3  296.18    4774  292.56
  4786.7  292.73  4797.6  295.13  4808.5  293.88  4826.6  295.77  4884.6  295.23
  4908.2  292.95  4926.3  295.27  4996.2  295.75  5001.8  286.37    5013  285.83
  5013.5  285.33  5018.6  285.83  5024.2  289.21  5029.8  288.84  5038.2  294.57
  5046.5  295.59    5167  295.77  5188.1  296.02  5261.8  298.02  5440.7  311.39
#Mann= 10 ,-1 , 0
  4231.9     .07       0    4246     .05       0  4307.1     .07       0
    4405     .05       0  4548.6     .12       0  4637.1      .1       0
    5013     .05       0  5018.6      .1       0    5167     .05       0
  5188.1     .07       0
Bank Sta=5013,5018.6
XS Rating Curve= 0 ,0
Exp/Cntr=0.3,0.1

Type RM Length L Ch R = 1 ,8993    ,401,401,401
BEGIN DESCRIPTION:
VALLEY BRANCH 17.0
END DESCRIPTION:
XS GIS Cut Line= 3
        2527175.     13760474.99        2526975.       13761225.
        2527375.       13761625.
#Sta/Elev= 30
  4223.9  307.02  4246.5  306.32    4255  304.98  4284.7  302.82  4410.2  296.43
    4493  293.92  4606.8  293.37  4707.1  293.75  4844.9  292.44  4867.5  292.52
  4914.2  294.35  4927.7  294.81  4942.5   292.8  4945.5  285.33    4946  284.83
  4951.2  285.33  4958.7  286.45  4969.1  291.14  4990.3  290.87  5003.2  291.05
  5014.3  294.34  5155.7  292.61  5297.1  293.31  5353.7  294.45  5410.2   296.8
  5452.7  297.72  5495.1  299.96  5523.4  302.64  5557.2   304.8  5565.8  305.29
#Mann= 8 ,-1 , 0
  4223.9     .07       0  4284.7     .05       0  4914.2      .1       0
  4945.5     .05       0  4951.2      .1       0  4990.3     .12       0
  5003.2     .05       0  5557.2     .07       0
#XS Ineff= 2 , 0
       0  4711.5  300.82               0
Permanent Ineff=
       F       F
Bank Sta=4945.5,4951.2
XS Rating Curve= 0 ,0
Exp/Cntr=0.3,0.1

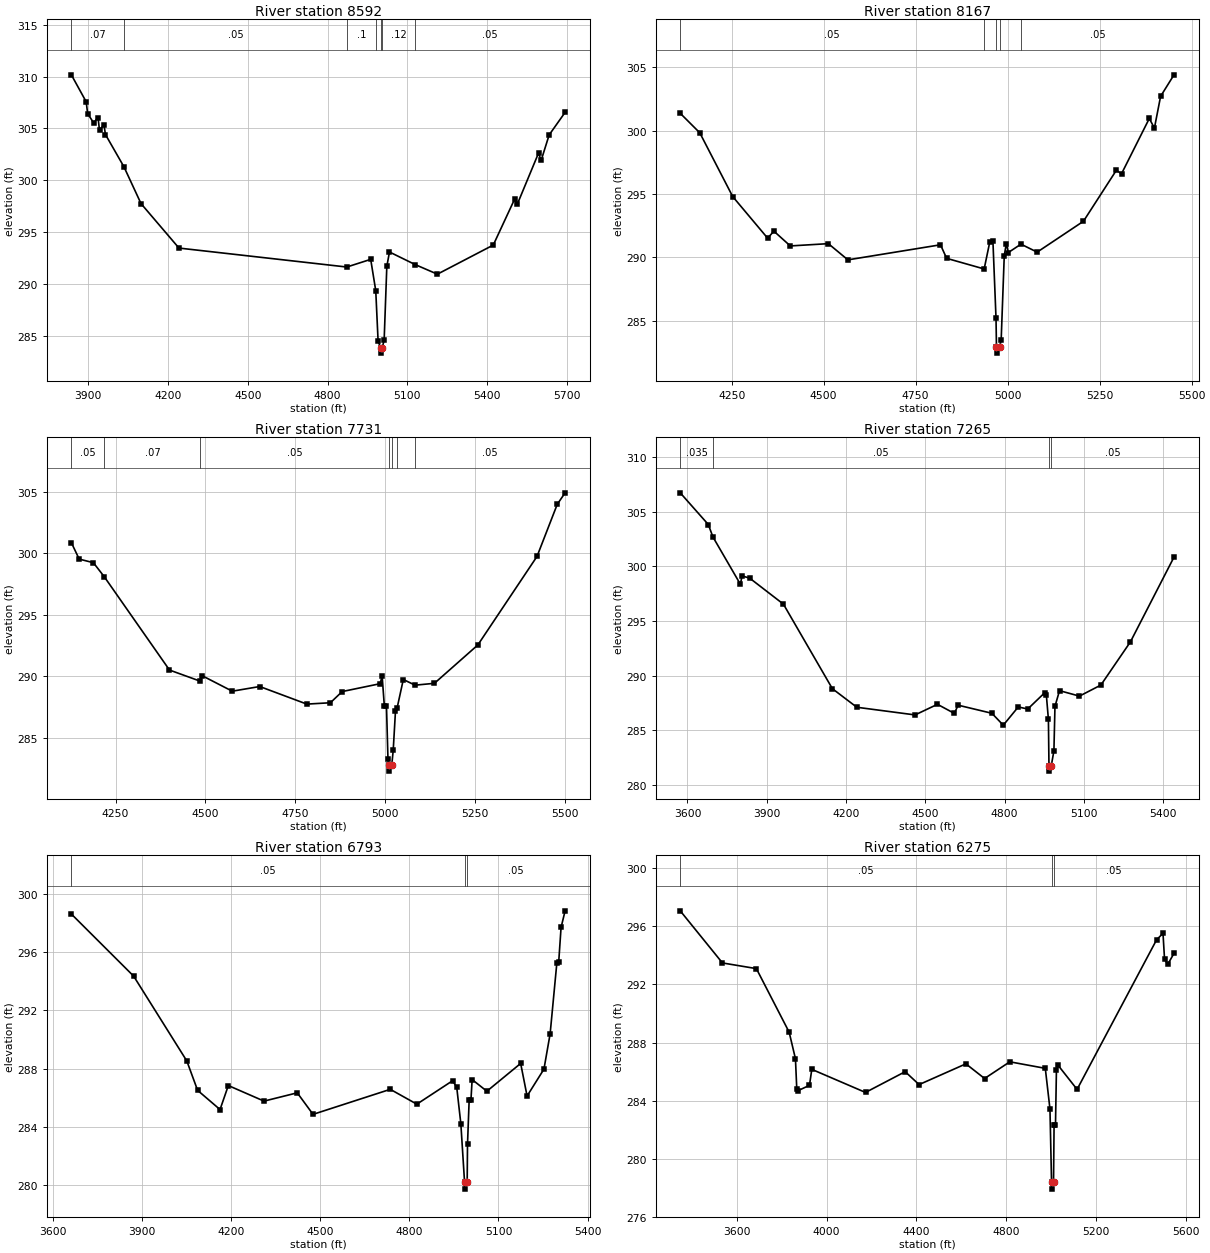
Type RM Length L Ch R = 1 ,8592    ,425,425,425
BEGIN DESCRIPTION:
VALLEY BRANCH 16.0
END DESCRIPTION:
XS GIS Cut Line= 3
      2527197.14     13760344.23        2526675.       13761375.
        2526675.     13762075.03
#Sta/Elev= 30
  3837.3  310.17    3893  307.57  3898.6  306.42  3920.9  305.54  3937.5  306.04
  3943.1  304.83  3959.8  305.35  3965.4  304.41    4035  301.29  4099.1  297.74
  4241.7  293.45  4872.4  291.62  4962.2  292.36  4981.2  289.34    4990  284.47
  4999.8  283.81  5000.3  283.31  5005.7  283.81  5012.8   284.6  5022.8  291.69
  5032.8  293.07    5129  291.86  5212.8  290.93  5422.8  293.74  5502.8  298.16
  5512.8  297.66  5592.8  302.61  5602.8  301.91  5632.8  304.37  5692.8  306.55
#Mann= 7 ,-1 , 0
  3837.3     .07       0    4035     .05       0  4872.4      .1       0
  4981.2     .12       0  4999.8     .05       0  5005.7     .12       0
    5129     .05       0
Bank Sta=4999.8,5005.7
XS Rating Curve= 0 ,0
Exp/Cntr=0.3,0.1

Type RM Length L Ch R = 1 ,8167    ,436,436,436
BEGIN DESCRIPTION:
VALLEY BRANCH 15.0
END DESCRIPTION:
XS GIS Cut Line= 3
      2526024.99     13760824.99        2526425.       13761625.
      2526625.02     13762025.04
#Sta/Elev= 30
  4110.3  301.38  4163.4  299.84  4252.9   294.8  4347.9  291.51  4364.7  292.07
  4409.4   290.9  4512.8  291.08  4565.9   289.8  4817.5  290.99  4834.2  289.92
  4936.2  289.08  4951.6  291.24    4960  291.27  4968.4  285.18  4969.6  282.93
  4970.1  282.43  4978.3  282.93  4982.4  283.47  4990.8  290.14  4996.4  291.08
  5001.9  290.38  5036.2  291.04  5080.2  290.41    5206  292.85  5295.4  296.88
  5309.4   296.6  5384.9  300.97  5398.8  300.21  5415.6  302.72    5452  304.42
#Mann= 5 ,-1 , 0
  4110.3     .05       0  4936.2     .12       0  4969.6     .05       0
  4978.3     .12       0  5036.2     .05       0
Bank Sta=4969.6,4978.3
XS Rating Curve= 0 ,0
Exp/Cntr=0.3,0.1

Type RM Length L Ch R = 1 ,7731    ,466,466,466
BEGIN DESCRIPTION:
VALLEY BRANCH 14.0
END DESCRIPTION:
XS GIS Cut Line= 3
      2525724.99     13760974.98        2526075.       13761775.
      2526374.98     13762174.98
#Sta/Elev= 30
    4127  300.88  4148.8  299.54  4188.2  299.25  4218.7   298.1  4399.9  290.52
  4485.8  289.61  4490.7  290.06  4574.5   288.8  4650.9  289.18  4781.9  287.75
  4847.4  287.86  4880.2  288.77  4985.8  289.41  4991.3  290.04  4997.5  287.58
  5003.4  287.58  5007.5  283.31  5009.4   282.8  5009.9   282.3  5018.1   282.8
  5022.1  283.98  5028.4  287.17  5032.8  287.41  5050.2  289.75    5083  289.29
  5136.7  289.44  5257.5  292.56  5422.1  299.76  5478.4     304  5500.2  304.93
#Mann= 7 ,-1 , 0
    4127     .05       0  4218.7     .07       0  4485.8     .05       0
  5009.4     .05       0  5018.1     .05       0  5032.8     .12       0
    5083     .05       0
Bank Sta=5009.4,5018.1
XS Rating Curve= 0 ,0
Exp/Cntr=0.3,0.1

Type RM Length L Ch R = 1 ,7265    ,472,472,472
BEGIN DESCRIPTION:
VALLEY BRANCH 13.0
END DESCRIPTION:
XS GIS Cut Line= 3
      2524924.98     13761024.98        2525825.       13762125.
      2526224.99       13762325.
#Sta/Elev= 30
  3572.6  306.73  3678.9  303.83  3696.2   302.7  3800.2  298.37  3806.6  299.13
  3835.3  298.93  3963.1  296.55  4148.3  288.82  4240.9  287.12  4461.3  286.42
    4546  287.39  4609.9  286.56  4624.2  287.31    4752  286.57  4795.1  285.48
  4851.8  287.15  4887.7  286.96  4951.5  288.44    4958  288.26  4965.9  286.01
    4968  281.78  4968.5  281.28  4976.8  281.78  4986.7  283.14  4990.7   287.2
  5007.9  288.64  5083.3  288.14  5164.4  289.15  5276.2   293.1  5441.1  300.85
#Mann= 4 ,-1 , 0
  3572.6    .035       0  3696.2     .05       0    4968     .05       0
  4976.8     .05       0
Bank Sta=4968,4976.8
XS Rating Curve= 0 ,0
Exp/Cntr=0.3,0.1

Type RM Length L Ch R = 1 ,6793    ,518,518,518
BEGIN DESCRIPTION:
VALLEY BRANCH 12.0
END DESCRIPTION:
XS GIS Cut Line= 3
      2524924.98     13761274.96        2525525.       13762475.
      2525774.96     13762674.97
#Sta/Elev= 30
  3662.5  298.63  3872.2  294.36  4051.1  288.53  4087.4  286.51  4162.9  285.19
  4190.8  286.84    4311  285.77  4422.8  286.34  4475.9  284.86  4735.9  286.58
  4825.3  285.56  4945.5  287.17  4959.5  286.73  4973.4  284.21  4985.8  280.22
  4986.3  279.72  4994.7  280.22  4995.8   282.8  5001.4  285.86  5007.4  285.86
  5011.4  287.25    5061  286.45  5174.7  288.36  5196.3  286.12  5253.1  287.97
  5273.9   290.4  5296.3  295.23  5302.7  295.32  5310.7  297.71  5324.3  298.85
#Mann= 3 ,-1 , 0
  3662.5     .05       0  4985.8     .05       0  4994.7     .05       0
Bank Sta=4985.8,4994.7
XS Rating Curve= 0 ,0
Exp/Cntr=0.3,0.1

Type RM Length L Ch R = 1 ,6275    ,473,473,473
BEGIN DESCRIPTION:
VALLEY BRANCH 11.0
END DESCRIPTION:
XS GIS Cut Line= 3
      2524827.99     13761281.54      2525283.77     13762885.36
      2525678.09      13763241.1
#Sta/Elev= 30
  3348.1  297.07    3536  293.48  3687.1  293.09  3833.1  288.71  3861.1  286.88
  3866.9  284.83  3872.1  284.68  3923.5  285.05  3933.9  286.15    4173  284.56
  4349.7  285.99  4411.6   285.1    4620  286.53  4703.2  285.52  4815.5  286.67
  4973.5  286.22  4994.3  283.42  5001.3   278.4  5001.8   277.9  5010.2   278.4
  5012.6  282.31  5018.9  282.31  5023.1  286.12  5030.5  286.43    5115  284.77
  5469.2  295.08  5497.6  295.52  5504.4  293.74  5518.6  293.38  5546.5  294.14
#Mann= 3 ,-1 , 0
  3348.1     .05       0  5001.3     .05       0  5010.2     .05       0
Bank Sta=5001.3,5010.2
XS Rating Curve= 0 ,0
Exp/Cntr=0.3,0.1

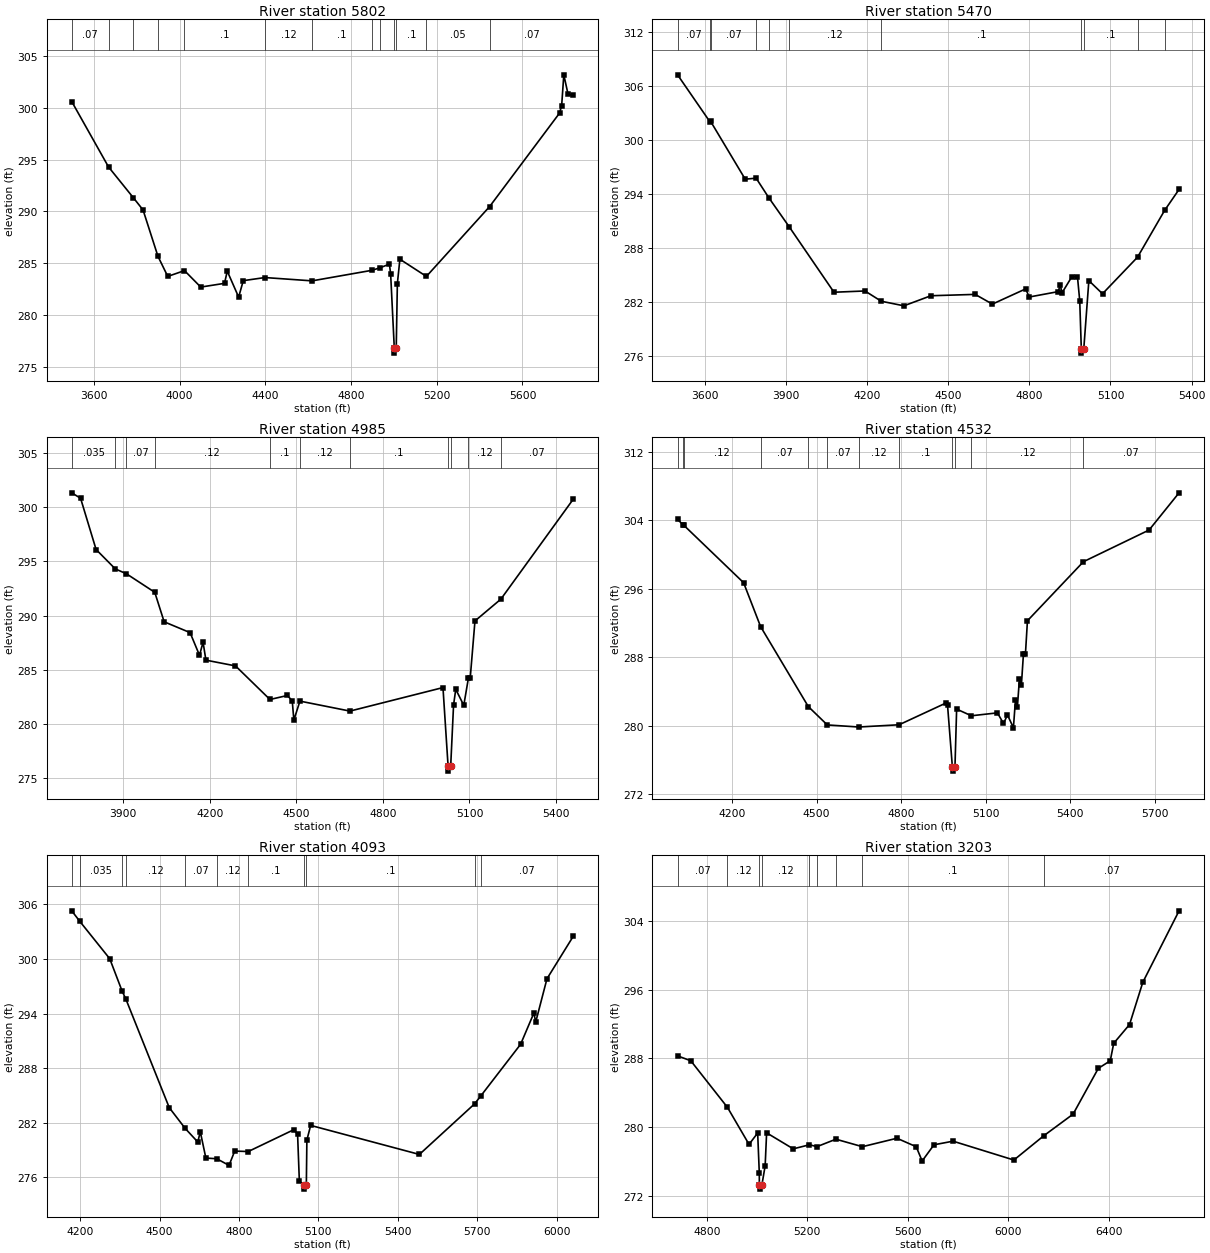
Type RM Length L Ch R = 1 ,5802    ,332,332,332
BEGIN DESCRIPTION:
VALLEY BRANCH 10.0
END DESCRIPTION:
XS GIS Cut Line= 3
      2524161.53      13761836.2      2524939.79     13763194.94
      2524905.39     13763968.94
#Sta/Elev= 30
  3496.2  300.61    3668  294.29  3783.3  291.33    3829  290.14  3898.6  285.66
  3944.3  283.72  4022.4  284.28  4098.3  282.69  4209.3  283.05    4222  284.23
  4275.2  281.72  4296.8  283.31    4398  283.61  4617.9  283.29  4897.6  284.31
  4936.2  284.56  4978.8  284.91  4984.6  283.96  5001.6  276.81  5002.1  276.31
  5010.7  276.81    5016  283.03  5027.8  285.38  5151.5  283.72  5446.7  290.47
  5772.8  299.49  5782.8  300.22  5792.8  303.19  5812.8   301.3  5836.8  301.21
#Mann= 13 ,-1 , 0
  3496.2     .07       0    3668    .035       0  3783.3     .07       0
  3898.6     .12       0  4022.4      .1       0    4398     .12       0
  4617.9      .1       0  4897.6    .035       0  4936.2      .1       0
  5001.6     .05       0  5010.7      .1       0  5151.5     .05       0
  5446.7     .07       0
Bank Sta=5001.6,5010.7
XS Rating Curve= 0 ,0
Exp/Cntr=0.3,0.1

Type RM Length L Ch R = 1 ,5470    ,485,485,485
BEGIN DESCRIPTION:
VALLEY BRANCH 9.0
END DESCRIPTION:
XS GIS Cut Line= 3
      2523724.99     13762074.99        2524625.       13763275.
      2524675.01     13763625.04
#Sta/Elev= 30
  3499.9  307.21  3618.8  302.02  3621.8  302.05  3749.9  295.61  3790.3  295.72
  3837.3  293.54  3912.9   290.3    4078  283.04  4192.6  283.18  4252.8  282.04
  4336.4  281.53  4436.4  282.65  4599.9   282.8  4663.5  281.72  4786.4  283.41
  4799.9  282.51  4907.2  283.11  4913.5  283.83  4921.8  283.01  4957.2  284.76
    4978  284.77  4986.4  282.09  4992.2  276.77  4992.7  276.27  5001.4  276.77
  5020.1  284.33  5070.6  282.87  5200.1  286.94    5300  292.13  5353.5  294.47
#Mann= 11 ,-1 , 0
  3499.9     .07       0  3618.8    .035       0  3621.8     .07       0
  3790.3     .12       0  3837.3     .07       0  3912.9     .12       0
  4252.8      .1       0  4992.2     .05       0  5001.4      .1       0
  5200.1     .05       0    5300     .07       0
Bank Sta=4992.2,5001.4
XS Rating Curve= 0 ,0
Exp/Cntr=0.3,0.1

Type RM Length L Ch R = 1 ,4985    ,453,453,453
BEGIN DESCRIPTION:
VALLEY BRANCH 8.0
END DESCRIPTION:
XS GIS Cut Line= 3
       2523611.2     13762227.54        2524175.       13763375.
      2524385.13     13763783.99
#Sta/Elev= 30
  3721.4  301.33    3752  300.83  3805.8   296.1  3872.3  294.31    3911  293.86
  4009.2  292.15  4041.7  289.43  4131.6  288.43  4164.2  286.34  4176.6  287.54
  4186.5  285.89    4289  285.36  4408.5  282.26  4468.8  282.63  4485.7  282.14
  4491.3  280.36  4512.4  282.11  4685.8  281.19  5008.2  283.36  5025.8  276.15
  5026.3  275.65    5035  276.15  5044.9  281.75  5052.5   283.2  5080.3  281.72
  5096.6  284.27  5102.5   284.2  5119.1  289.51  5208.9  291.52  5459.7  300.74
#Mann= 11 ,-1 , 0
  3721.4    .035       0  3872.3     .12       0    3911     .07       0
  4009.2     .12       0  4408.5      .1       0  4512.4     .12       0
  4685.8      .1       0  5025.8     .05       0    5035      .1       0
  5096.6     .12       0  5208.9     .07       0
Bank Sta=5025.8,5035
XS Rating Curve= 0 ,0
Exp/Cntr=0.3,0.1

Type RM Length L Ch R = 1 ,4532    ,439,439,439
BEGIN DESCRIPTION:
VALLEY BRANCH 7.0
END DESCRIPTION:
XS GIS Cut Line= 3
      2523074.99     13762824.99        2523825.       13763475.
      2524393.76     13764016.21
#Sta/Elev= 30
  4007.5  304.09  4028.4  303.43  4029.5  303.42  4241.6  296.71  4301.8  291.59
  4470.8  282.26  4538.3  280.11  4649.7  279.87  4792.7  280.13  4957.7  282.65
  4964.4  282.44  4981.6  275.22  4982.1  274.72  4990.8  275.22  4996.7  281.96
  5048.9  281.18  5141.4  281.52  5162.8  280.28  5176.9  281.28    5198  279.78
  5205.2  283.04  5212.1  282.23  5219.4  285.52  5226.3   284.8  5233.6  288.43
  5240.5  288.35  5247.7  292.27  5446.1  299.16  5678.9  302.86  5785.1   307.2
#Mann= 12 ,-1 , 0
  4007.5     .12       0  4028.4    .035       0  4029.5     .12       0
  4301.8     .07       0  4470.8     .12       0  4538.3     .07       0
  4649.7     .12       0  4792.7      .1       0  4981.6     .05       0
  4990.8      .1       0  5048.9     .12       0  5446.1     .07       0
Bank Sta=4981.6,4990.8
XS Rating Curve= 0 ,0
Exp/Cntr=0.3,0.1

Type RM Length L Ch R = 1 ,4093    ,890,890,890
BEGIN DESCRIPTION:
VALLEY BRANCH 6.0
END DESCRIPTION:
XS GIS Cut Line= 3
      2522975.01     13762875.01        2523425.       13763575.
      2524225.03     13764275.02
#Sta/Elev= 30
  4167.8  305.28  4198.1  304.13  4311.4  300.02  4358.2  296.46  4372.6  295.57
  4536.3  283.66  4596.5  281.38  4644.3  279.88  4653.5  281.03  4674.7  278.12
  4715.7  278.05  4762.2  277.32  4783.7  278.89  4834.9  278.84  5007.1  281.24
  5021.3  280.74    5028  275.57  5045.2  275.21  5045.7  274.71  5054.4  275.21
  5056.4   280.1  5070.7  281.71  5481.6  278.52    5690  284.07  5712.7  284.91
  5864.1  290.62  5914.4  294.06  5921.1  293.05  5963.8  297.82    6063  302.48
#Mann= 11 ,-1 , 0
  4167.8     .07       0  4198.1    .035       0  4358.2     .07       0
  4372.6     .12       0  4596.5     .07       0  4715.7     .12       0
  4834.9      .1       0  5045.2     .05       0  5054.4      .1       0
    5690     .12       0  5712.7     .07       0
Bank Sta=5045.2,5054.4
XS Rating Curve= 0 ,0
Exp/Cntr=0.3,0.1

Type RM Length L Ch R = 1 ,3203    ,421,421,421
BEGIN DESCRIPTION:
VALLEY BRANCH 5.0
END DESCRIPTION:
XS GIS Cut Line= 3
      2522574.99     13763424.96        2522675.       13763725.
      2524224.96     13764374.98
#Sta/Elev= 30
  4683.5  288.29  4736.2  287.72  4882.1  282.31  4968.1  278.01  5002.5  279.33
  5008.9  274.74  5009.3  273.31  5009.8  272.81  5019.4  273.31  5032.3  275.52
  5038.1  279.35  5144.1  277.49  5208.5  277.96    5239  277.75    5314  278.61
  5419.5  277.74    5557  278.72  5633.7  277.74  5657.5  276.08  5704.6  277.96
  5780.5  278.38  6022.8  276.19  6141.8  279.01  6258.5  281.52    6359  286.84
  6406.5  287.72  6420.3  289.75  6483.3  291.93  6536.2  296.84  6680.5  305.14
#Mann= 9 ,-1 , 0
  4683.5     .07       0  4882.1     .12       0  5009.3     .05       0
  5019.4     .12       0  5208.5    .035       0    5239      .1       0
    5314    .035       0  5419.5      .1       0  6141.8     .07       0
Bank Sta=5009.3,5019.4
XS Rating Curve= 0 ,0
Exp/Cntr=0.3,0.1