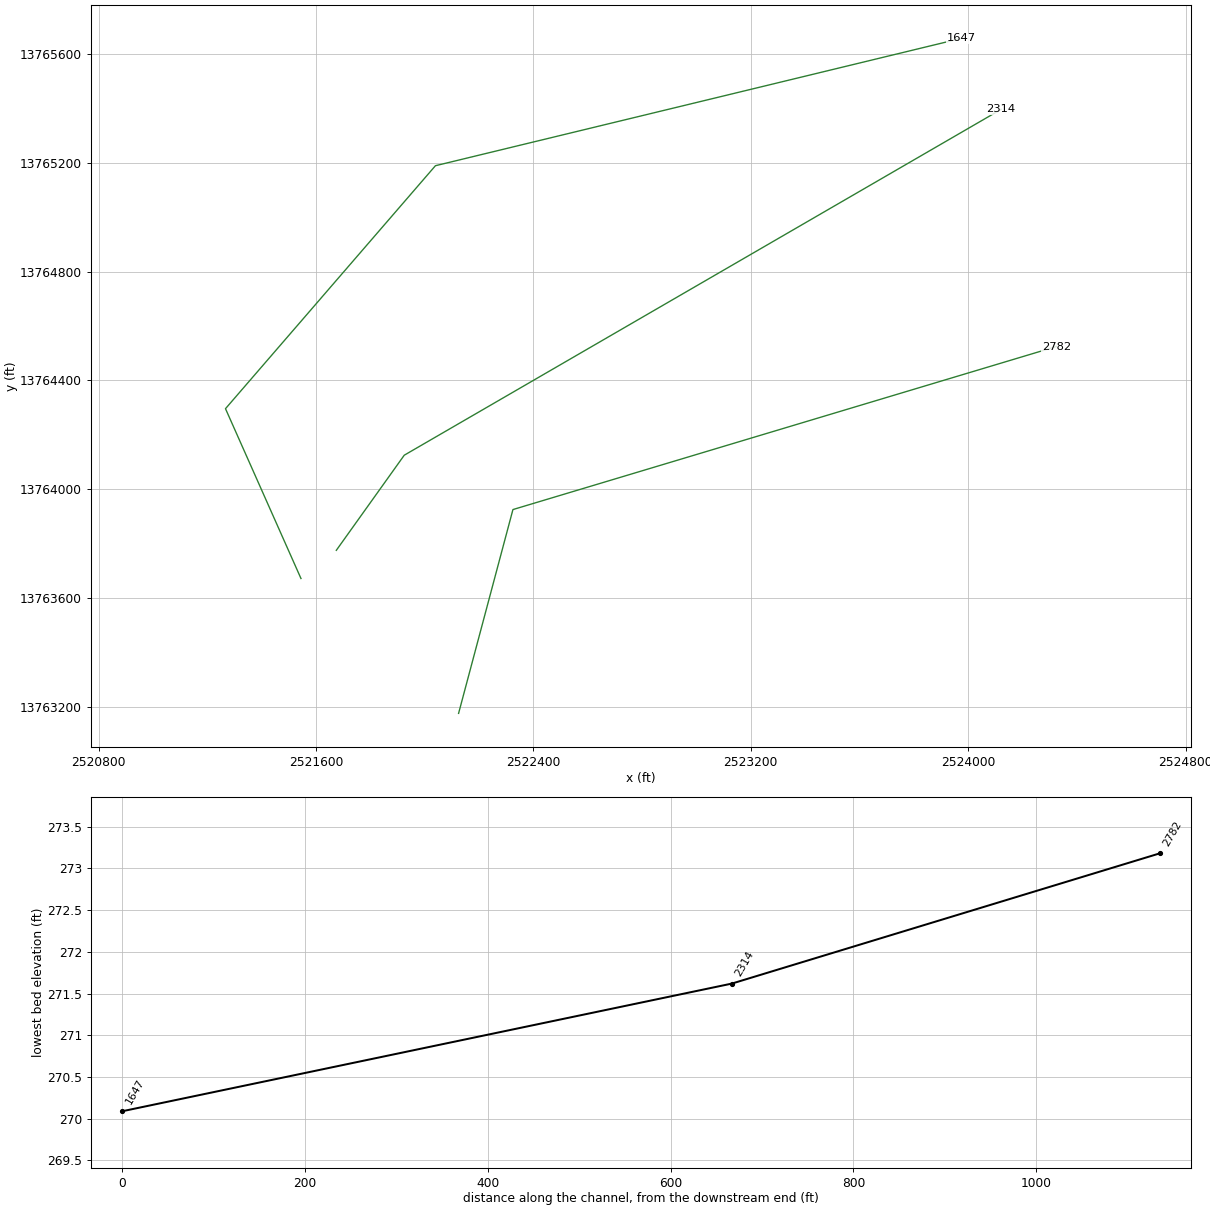
HEC-RAS study VALLEY BRANCH.prj: VALLEY BRANCH Base Level Engineering

--- VALLEY BRANCH.g01 (geometry) --- (continued)

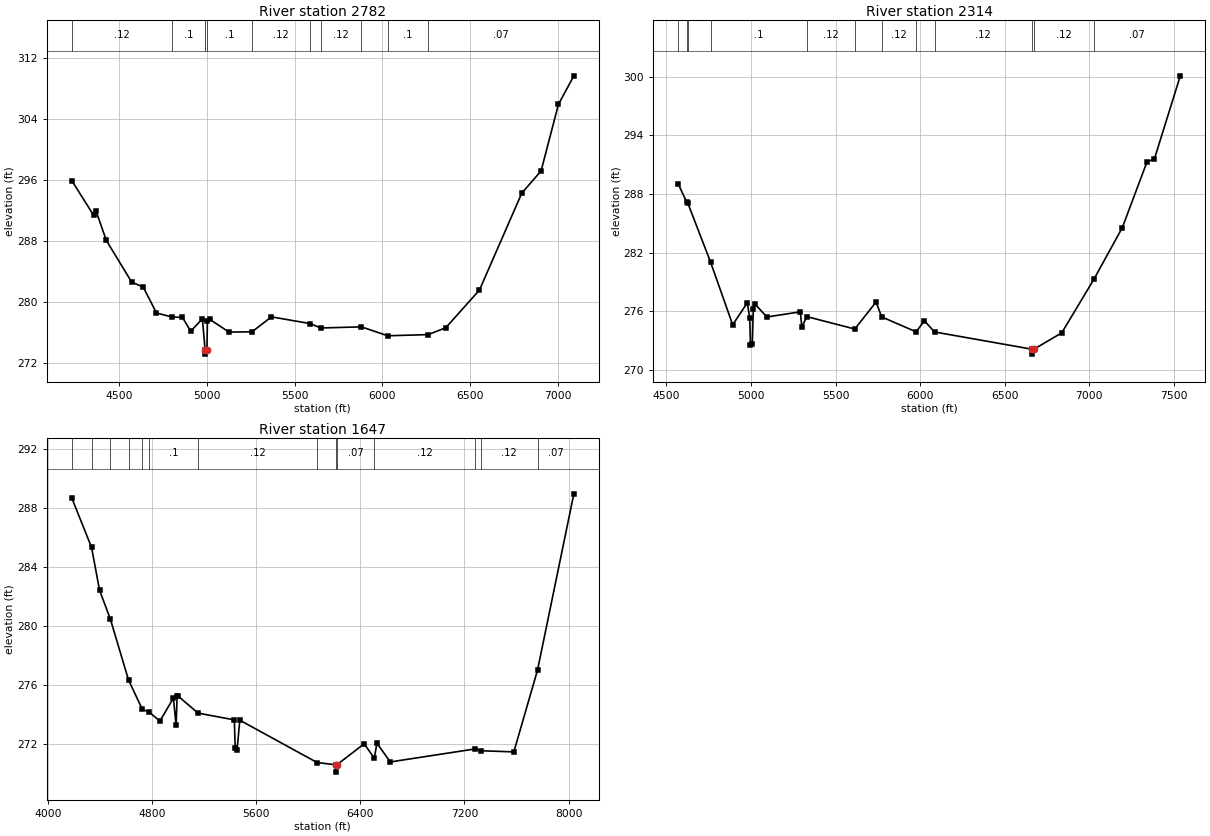
Type RM Length L Ch R = 1 ,2782    ,468,468,468
BEGIN DESCRIPTION:
VALLEY BRANCH 4.0
END DESCRIPTION:
XS GIS Cut Line= 3
      2522124.99     13763174.96        2522325.       13763925.
      2524324.98       13764525.
#Sta/Elev= 30
  4228.1  295.95  4352.3  291.42  4365.9  292.01  4424.8  288.12  4569.7  282.64
  4636.3  281.96  4711.3  278.58  4799.6  278.05  4859.5     278  4906.7  276.19
  4973.3  277.81    4989  273.68  4989.5  273.18  4999.1  273.68  5001.8   277.5
  5014.8  277.75  5125.3  276.07  5256.6  276.11  5367.2  278.07  5587.9  277.19
    5649  276.61  5880.1  276.76  6030.4  275.59  6261.2  275.74  6361.6  276.64
  6553.9  281.59  6795.7  294.32  6905.4  297.21  7004.5  305.95  7092.4   309.7
#Mann= 10 ,-1 , 0
  4228.1     .12       0  4799.6      .1       0    4989     .05       0
  4999.1      .1       0  5256.6     .12       0  5587.9      .1       0
    5649     .12       0  5880.1    .035       0  6030.4      .1       0
  6261.2     .07       0
Bank Sta=4989,4999.1
XS Rating Curve= 0 ,0
Exp/Cntr=0.3,0.1

Type RM Length L Ch R = 1 ,2314    ,667,667,667
BEGIN DESCRIPTION:
VALLEY BRANCH 3.0
END DESCRIPTION:
XS GIS Cut Line= 3
      2521674.99     13763774.99        2521925.       13764125.
      2524121.56     13765397.77
#Sta/Elev= 30
  4569.8  289.04  4620.1  287.16  4626.7  287.06  4760.9  281.04  4891.8  274.62
  4977.8  276.87  4992.6  275.35  4996.9  272.58  5007.8  272.61  5013.6  276.22
    5023  276.76  5093.9  275.42  5291.9  275.95  5300.4  274.38  5329.8  275.46
  5613.6  274.19  5739.6  276.95  5772.8  275.43  5976.7   273.9    6025  275.04
  6085.1  273.89  6662.6  272.12  6663.1  271.62  6672.8  272.12  6837.6   273.8
  7028.6  279.31  7195.8  284.57  7341.9  291.31    7385  291.58  7538.6   300.1
#Mann= 12 ,-1 , 0
  4569.8     .12       0  4620.1     .07       0  4626.7     .12       0
  4760.9      .1       0  5329.8     .12       0  5613.6     .05       0
  5772.8     .12       0  5976.7     .05       0  6085.1     .12       0
  6662.6     .05       0  6672.8     .12       0  7028.6     .07       0
Bank Sta=6662.6,6672.8
XS Rating Curve= 0 ,0
Exp/Cntr=0.3,0.1

Type RM Length L Ch R = 1 ,1647    ,0,0,0
BEGIN DESCRIPTION:
VALLEY BRANCH 2.0
END DESCRIPTION:
XS GIS Cut Line= 4
      2521544.96     13763671.26      2521267.19     13764296.23
      2522039.76     13765190.33      2523975.56     13765659.09
#Sta/Elev= 30
  4183.7  288.67  4335.8  285.32    4397  282.42  4480.6  280.45  4619.8  276.33
  4726.2  274.34  4776.7  274.17  4860.7  273.55  4964.4   275.1  4985.3  273.28
  4992.9  275.22  4999.5  275.25  5154.4  274.09  5432.7  273.63  5439.3  271.74
  5453.6  271.59  5474.5  273.61  6068.6  270.74  6210.8  270.59  6211.3  270.09
  6221.1  270.59  6430.2  272.01  6508.4  271.03  6527.9  272.05  6630.8  270.78
  7281.2  271.66  7326.5  271.54    7580  271.46  7761.8     277    8041  288.95
#Mann= 14 ,-1 , 0
  4183.7     .12       0  4335.8     .07       0  4480.6     .12       0
  4619.8     .07       0  4726.2     .12       0  4776.7      .1       0
  5154.4     .12       0  6068.6     .07       0  6210.8     .05       0
  6221.1     .07       0  6508.4     .12       0  7281.2      .1       0
  7326.5     .12       0  7761.8     .07       0
Bank Sta=6210.8,6221.1
XS Rating Curve= 0 ,0
Exp/Cntr=0.3,0.1

Chan Stop Cuts=-1
Use User Specified Reach Order=0
Composite Channel Slope=5