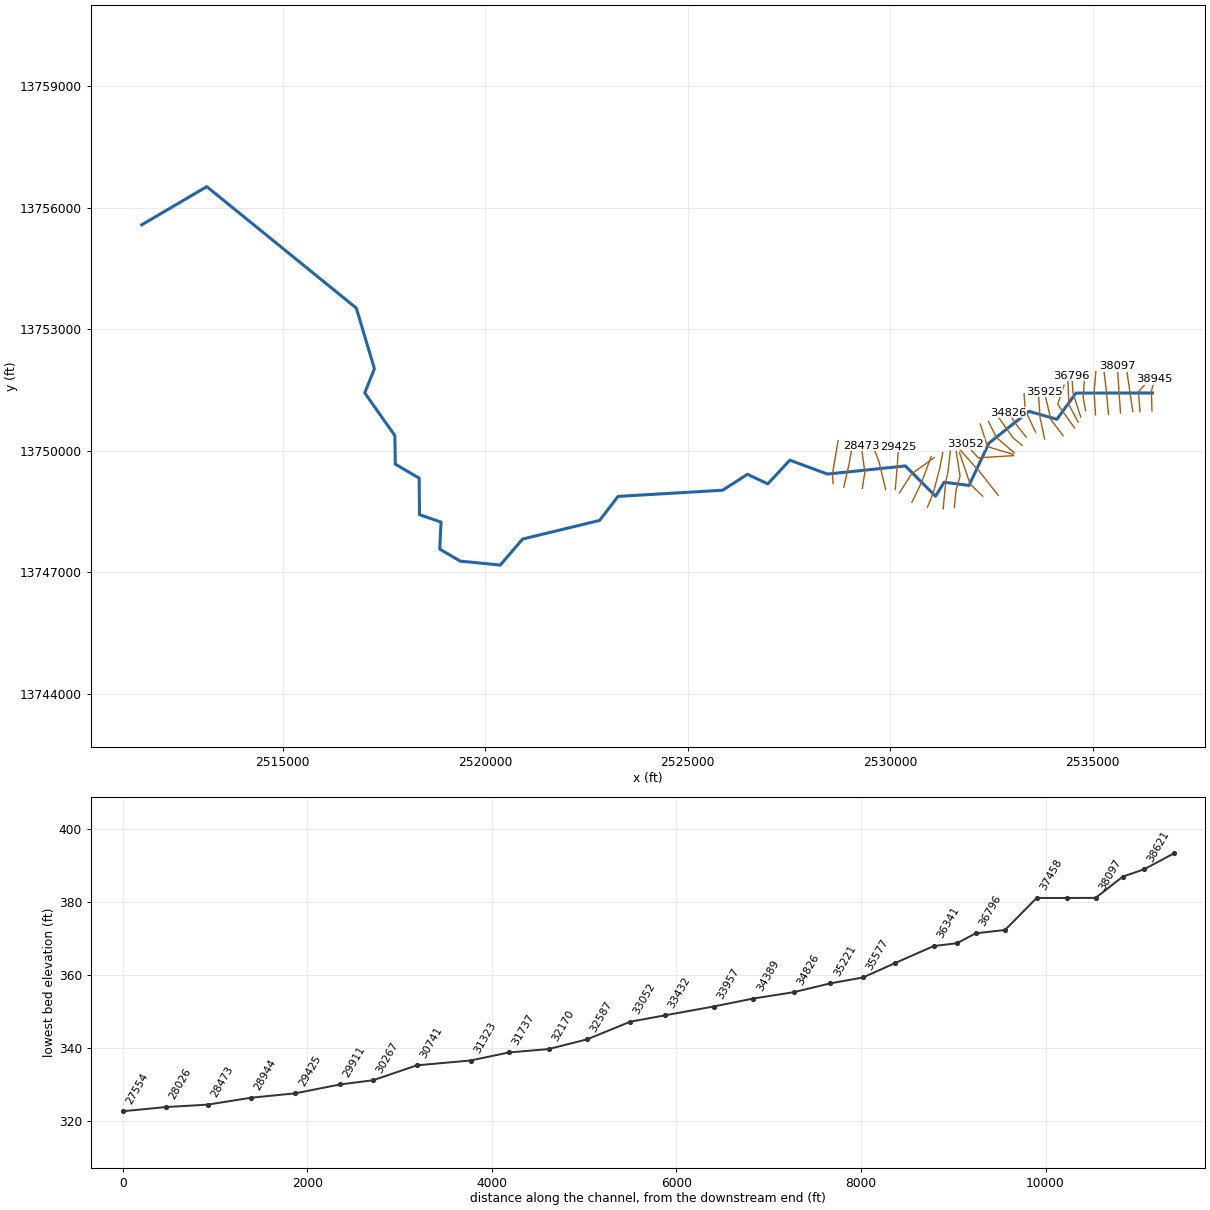
--- VANHAM CREEK.prj (project) ---

Proj Title=VANHAM CREEK Base Level Engineering
Current Plan=p01
Default Exp/Contr=0.3,0.1
English Units
Geom File=g01
Flow File=f01
Plan File=p01
Y Axis Title=Elevation
X Axis Title(PF)=Main Channel Distance
X Axis Title(XS)=Station
BEGIN DESCRIPTION:
VANHAM CREEK
END DESCRIPTION:
DSS Export Rating Curves= 0
DSS Export Rating Curve Sorted= 0
DSS Export Volume Flow Curves= 0
DXF OffsetX= 0
DXF OffsetY= 0
DXF ScaleX= 1
DXF ScaleY= 10

--- VANHAM CREEK.p01 (plan) ---

Plan Title=Multiple Run
Short Identifier=Multiple
Geom File=g01
Flow File=f01
Subcritical Flow
K Sum by GR= 0
Std Step Tol= 0.01
Critical Tol= 0.01
Num of Std Step Trials= 20
Max Error Tol= 0.3
Flow Tol Ratio= 0.001
Split Flow NTrial= 30
Split Flow Tol= 0.02
Split Flow Ratio= 0.02
Log Output Level= 0
Friction Slope Method= 1
Unsteady Friction Slope Method= 2
Unsteady Bridges Friction Slope Method= 1
Parabolic Critical Depth
Global Vel Dist=  1 , 1 , 1
Global Log Level= 0
CheckData=True
Encroach Param= -1, 0, 0, 0
BEGIN DESCRIPTION:
Multiple Run
END DESCRIPTION:

--- VANHAM CREEK.f01 (steady flow) ---

Flow Title=Multiple
Program Version=4.10
Number of Profiles= 7
Profile Names=10-year,25-year,50-year,1pct_min,100-year,1pct_plu,500-year
River Rch & RM=VANHAM CREEK,Reach-1         ,38945
     424     664     874     560    1117    2228    1799
River Rch & RM=VANHAM CREEK,Reach-1         ,38392
     799    1302    1763    1156    2307    4603    3909
River Rch & RM=VANHAM CREEK,Reach-1         ,35221
     875    1437    1954    1288    2570    5128    4399
River Rch & RM=VANHAM CREEK,Reach-1         ,32587
    1478    2493    3452    2311    4611    9200    8149
River Rch & RM=VANHAM CREEK,Reach-1         ,29425
    1646    2778    3848    2575    5138   10251    9074
River Rch & RM=VANHAM CREEK,Reach-1         ,24847
    2832    4875    6840    4627    9232   18421   16668
River Rch & RM=VANHAM CREEK,Reach-1         ,16083
    3555    6126    8600    5814   11601   23148   20918
Boundary for River Rch & Prof#=VANHAM CREEK,Reach-1         , 1
Up Type= 0
Dn Type= 3
Dn Slope=0.0016
Boundary for River Rch & Prof#=VANHAM CREEK,Reach-1         , 2
Up Type= 0
Dn Type= 3
Dn Slope=0.0016
Boundary for River Rch & Prof#=VANHAM CREEK,Reach-1         , 3
Up Type= 0
Dn Type= 3
Dn Slope=0.0016
Boundary for River Rch & Prof#=VANHAM CREEK,Reach-1         , 4
Up Type= 0
Dn Type= 3
Dn Slope=0.0016
Boundary for River Rch & Prof#=VANHAM CREEK,Reach-1         , 5
Up Type= 0
Dn Type= 3
Dn Slope=0.0016
Boundary for River Rch & Prof#=VANHAM CREEK,Reach-1         , 6
Up Type= 0
Dn Type= 3
Dn Slope=0.0016
Boundary for River Rch & Prof#=VANHAM CREEK,Reach-1         , 7
Up Type= 0
Dn Type= 3
Dn Slope=0.0016
DSS Import GetInterval= 0
DSS Import GetPeak= 0
DSS Import FillOption= 0

--- VANHAM CREEK.g01 (geometry) ---

Geom Title=Existing Conditions
Program Version=4.10

River Reach=VANHAM CREEK    ,Reach-1
Reach XY= 30
        2536475.       13751425.      2534586.53      13751423.5
      2534114.72     13750775.98      2533426.63     13750971.87
      2532438.62     13750189.06      2531945.39      13749144.2
      2531330.94     13749222.87      2531119.31     13748876.87
        2530375.       13749625.       2528449.8     13749424.64
      2527521.65     13749767.01      2526978.41     13749182.77
      2526475.12     13749418.13      2525864.29     13749025.82
      2523280.69     13748873.12      2522827.31     13748280.82
      2520926.48     13747821.55      2520373.54     13747178.54
      2519385.44     13747276.05      2518880.36      13747572.3
      2518911.78     13748238.67      2518380.34     13748422.26
      2518371.46     13749323.54      2517782.86     13749668.83
      2517771.46     13750373.54      2517028.67     13751426.58
      2517267.41     13752024.99      2516819.97     13753520.07
      2513128.42     13756517.21        2511525.       13755575.

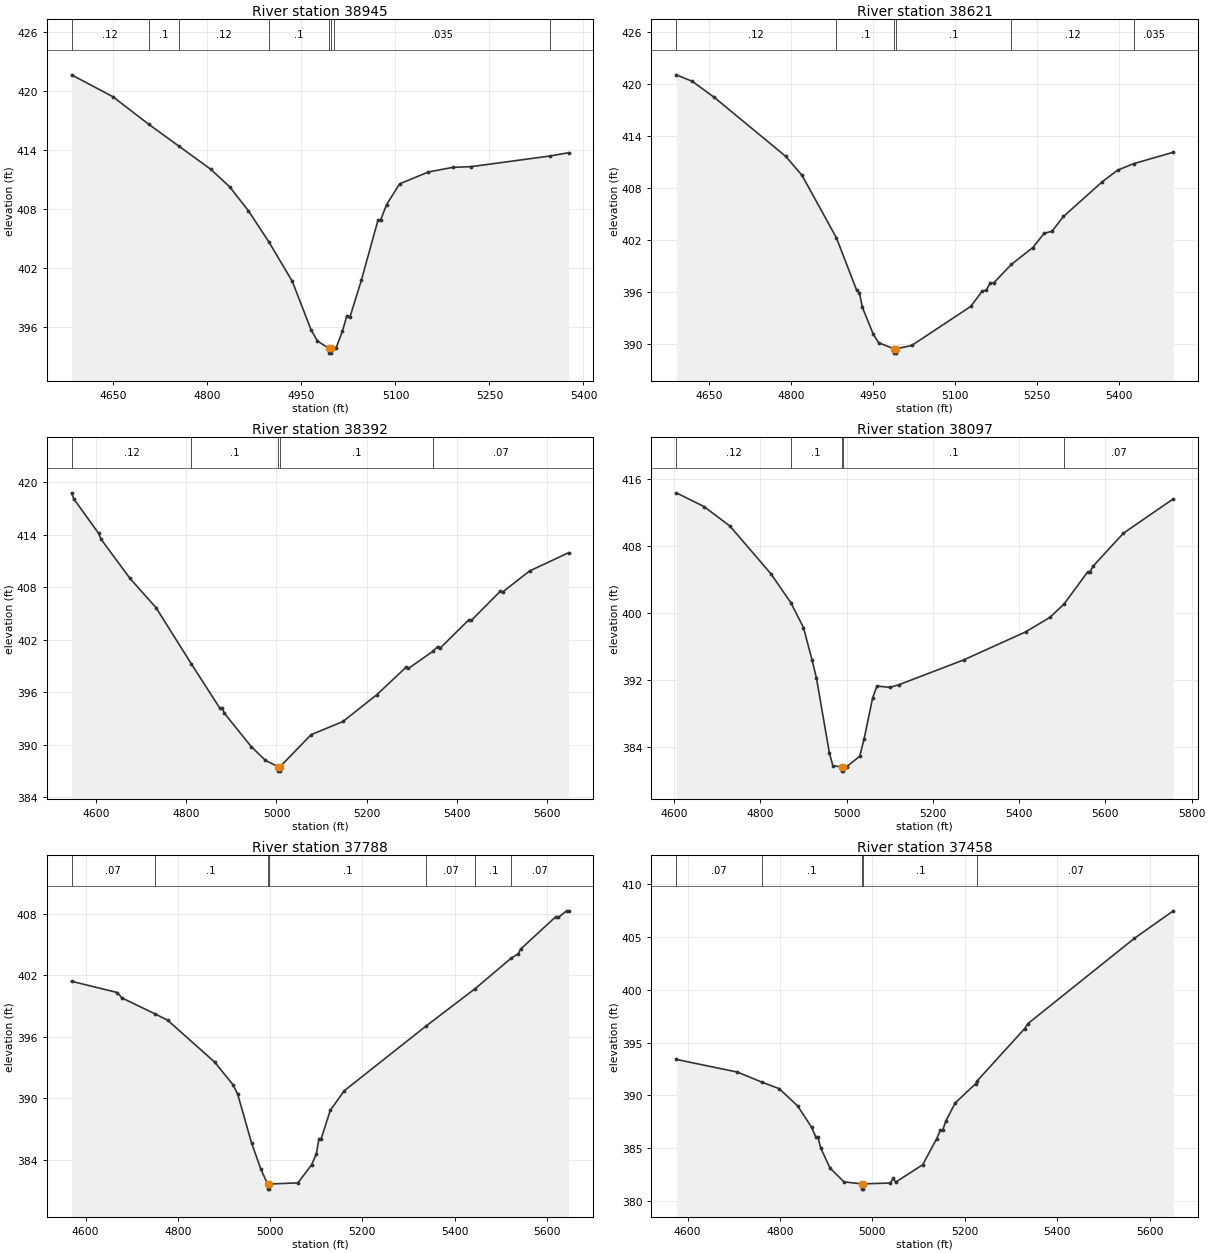
Type RM Length L Ch R = 1 ,38945   ,324,324,324
BEGIN DESCRIPTION:
H21538
END DESCRIPTION:
XS GIS Cut Line= 3
      2536461.71     13750982.89      2536448.69     13751473.36
      2536531.15     13751764.15
#Sta/Elev= 30
  4583.2  421.63    4649  419.41  4706.7  416.58  4754.7  414.36  4805.4  412.01
  4835.4  410.23  4865.4  407.79  4898.5  404.57  4935.4   400.6  4965.4  395.66
  4975.5  394.53  4993.5  393.79  4993.7  393.29  4997.2  393.29  4997.5  393.79
  5001.9  393.83  5005.5  393.86  5015.5  395.53  5022.5  397.12  5027.5  396.98
  5045.5  400.69  5072.2  406.84  5076.2  406.84  5085.9  408.42  5106.7  410.53
  5152.7  411.74  5191.8  412.21  5220.6  412.28  5347.3  413.37  5376.1   413.7
#Mann= 8 ,-1 , 0
  4583.2     .12       0  4706.7      .1       0  4754.7     .12       0
  4898.5      .1       0  4993.5     .05       0  4997.5      .1       0
  5001.9    .035       0  5347.3     .12       0
Bank Sta=4993.5,4997.5
XS Rating Curve= 0 ,0
Exp/Cntr=0.3,0.1

Type RM Length L Ch R = 1 ,38621   ,229,229,229
BEGIN DESCRIPTION:
H21537
END DESCRIPTION:
XS GIS Cut Line= 3
      2536166.57     13750965.57      2536127.51       13751456.
      2536409.64     13751764.18
#Sta/Elev= 30
  4589.6  421.02  4619.1  420.26  4659.3  418.41  4789.7  411.63  4819.8  409.42
  4882.7  402.22  4919.7  396.18  4924.7  395.89  4930.1  394.22  4950.2  391.09
  4960.2  390.11  4988.3  389.42  4988.5  388.92    4992  388.92  4992.3  389.42
  5020.4   389.8  5128.7  394.31  5149.7  396.08  5157.1  396.17  5163.8  396.97
  5171.2  397.06  5202.9  399.15  5242.2   401.1  5263.1  402.74  5277.3  402.98
  5298.3  404.68  5369.2  408.68  5397.5  410.03  5427.6  410.79  5499.4  412.09
#Mann= 6 ,-1 , 0
  4589.6     .12       0  4882.7      .1       0  4988.3     .05       0
  4992.3      .1       0  5202.9     .12       0  5427.6    .035       0
Bank Sta=4988.3,4992.3
XS Rating Curve= 0 ,0
Exp/Cntr=0.3,0.1

Type RM Length L Ch R = 1 ,38392   ,295,295,295
BEGIN DESCRIPTION:
H21536
END DESCRIPTION:
XS GIS Cut Line= 2
      2535988.62     13750969.89      2535828.03     13752059.31
#Sta/Elev= 30
  4545.9  418.81  4551.1  418.11  4605.8  414.18  4611.7  413.48  4675.5  409.01
    4733  405.68  4811.3  399.24  4874.4  394.17  4879.4  394.23  4884.6  393.58
  4944.1  389.77  4975.6  388.19  5003.9  387.46  5004.2  386.96  5007.7  386.96
  5007.9  387.46  5076.7  391.13  5147.4  392.64  5222.7  395.72  5287.3  398.86
  5292.4  398.71  5346.2  400.66    5357  401.21    5362     401  5426.6   404.3
  5431.7   404.2  5496.3  407.57  5501.4  407.47  5560.9  409.87  5647.1  411.95
#Mann= 5 ,-1 , 0
  4545.9     .12       0  4811.3      .1       0  5003.9     .05       0
  5007.9      .1       0  5346.2     .07       0
Bank Sta=5003.9,5007.9
XS Rating Curve= 0 ,0
Exp/Cntr=0.3,0.1

Type RM Length L Ch R = 1 ,38097   ,309,309,309
BEGIN DESCRIPTION:
H21535
END DESCRIPTION:
XS GIS Cut Line= 2
       2535684.8     13750930.84      2535606.71      13752080.5
#Sta/Elev= 30
  4605.2  414.33  4669.5  412.69  4729.6  410.36  4824.2  404.69  4870.6  401.24
    4900  398.26  4920.1  394.35  4930.1  392.24  4960.2  383.27  4968.2  381.78
  4988.2  381.63  4988.5  381.13    4992  381.13  4992.2  381.63  5000.3  381.67
  5030.3   382.9  5040.4  384.93  5060.4  389.87  5070.4  391.28  5100.5  391.12
  5122.1  391.45  5271.1  394.39    5415  397.74  5471.3  399.47  5504.1  401.06
    5559   404.9    5564   404.9  5571.6  405.59  5641.7  409.51  5757.5  413.61
#Mann= 5 ,-1 , 0
  4605.2     .12       0  4870.6      .1       0  4988.2     .05       0
  4992.2      .1       0  5504.1     .07       0
Bank Sta=4988.2,4992.2
XS Rating Curve= 0 ,0
Exp/Cntr=0.3,0.1

Type RM Length L Ch R = 1 ,37788   ,330,330,330
BEGIN DESCRIPTION:
H21534
END DESCRIPTION:
XS GIS Cut Line= 3
      2535389.66     13750896.15      2535333.24     13751503.74
      2535276.82     13751968.12
#Sta/Elev= 30
  4569.3  401.41  4668.6  400.31  4678.7  399.78  4749.8  398.24    4778   397.6
  4879.5  393.53  4919.7   391.3  4929.7  390.39  4959.8  385.62  4979.9  383.07
  4994.6  381.61  4994.9  381.11  4998.4  381.11  4998.6  381.61  5060.3  381.72
  5090.4  383.51  5100.4  384.57  5105.9  386.02  5110.9  386.05  5130.6  388.81
  5160.7  390.71  5339.2  397.07  5445.1   400.7    5523  403.67  5538.2  404.09
  5543.4  404.55    5620  407.73    5625  407.64  5643.2  408.29  5647.3  408.29
#Mann= 7 ,-1 , 0
  4569.3     .07       0  4749.8      .1       0  4994.6     .05       0
  4998.6      .1       0  5339.2     .07       0  5445.1      .1       0
    5523     .07       0
Bank Sta=4994.6,4998.6
XS Rating Curve= 0 ,0
Exp/Cntr=0.3,0.1

Type RM Length L Ch R = 1 ,37458   ,342,342,342
BEGIN DESCRIPTION:
H21533
END DESCRIPTION:
XS GIS Cut Line= 3
      2535068.49     13750883.04      2535033.76       13751456.
      2535077.16      13751955.1
#Sta/Elev= 30
  4575.8   393.4    4708   392.2  4760.2  391.26  4798.2  390.63  4838.2     389
  4868.3  386.98  4877.3  386.08  4882.3  386.01  4888.3  384.99  4908.4   383.1
  4938.4   381.8  4976.5  381.61  4976.7  381.11  4980.2  381.11  4980.5  381.61
  5038.6  381.69  5045.1  382.14  5050.2  381.77  5108.7  383.42  5138.8  385.87
  5146.8  386.69  5151.8  386.69  5158.8  387.56  5178.9  389.27    5223  391.09
  5227.2   391.4  5329.5  396.33  5335.9  396.78  5566.8  404.88  5650.8  407.48
#Mann= 5 ,-1 , 0
  4575.8     .07       0  4760.2      .1       0  4976.5     .05       0
  4980.5      .1       0  5227.2     .07       0
Bank Sta=4976.5,4980.5
XS Rating Curve= 0 ,0
Exp/Cntr=0.3,0.1

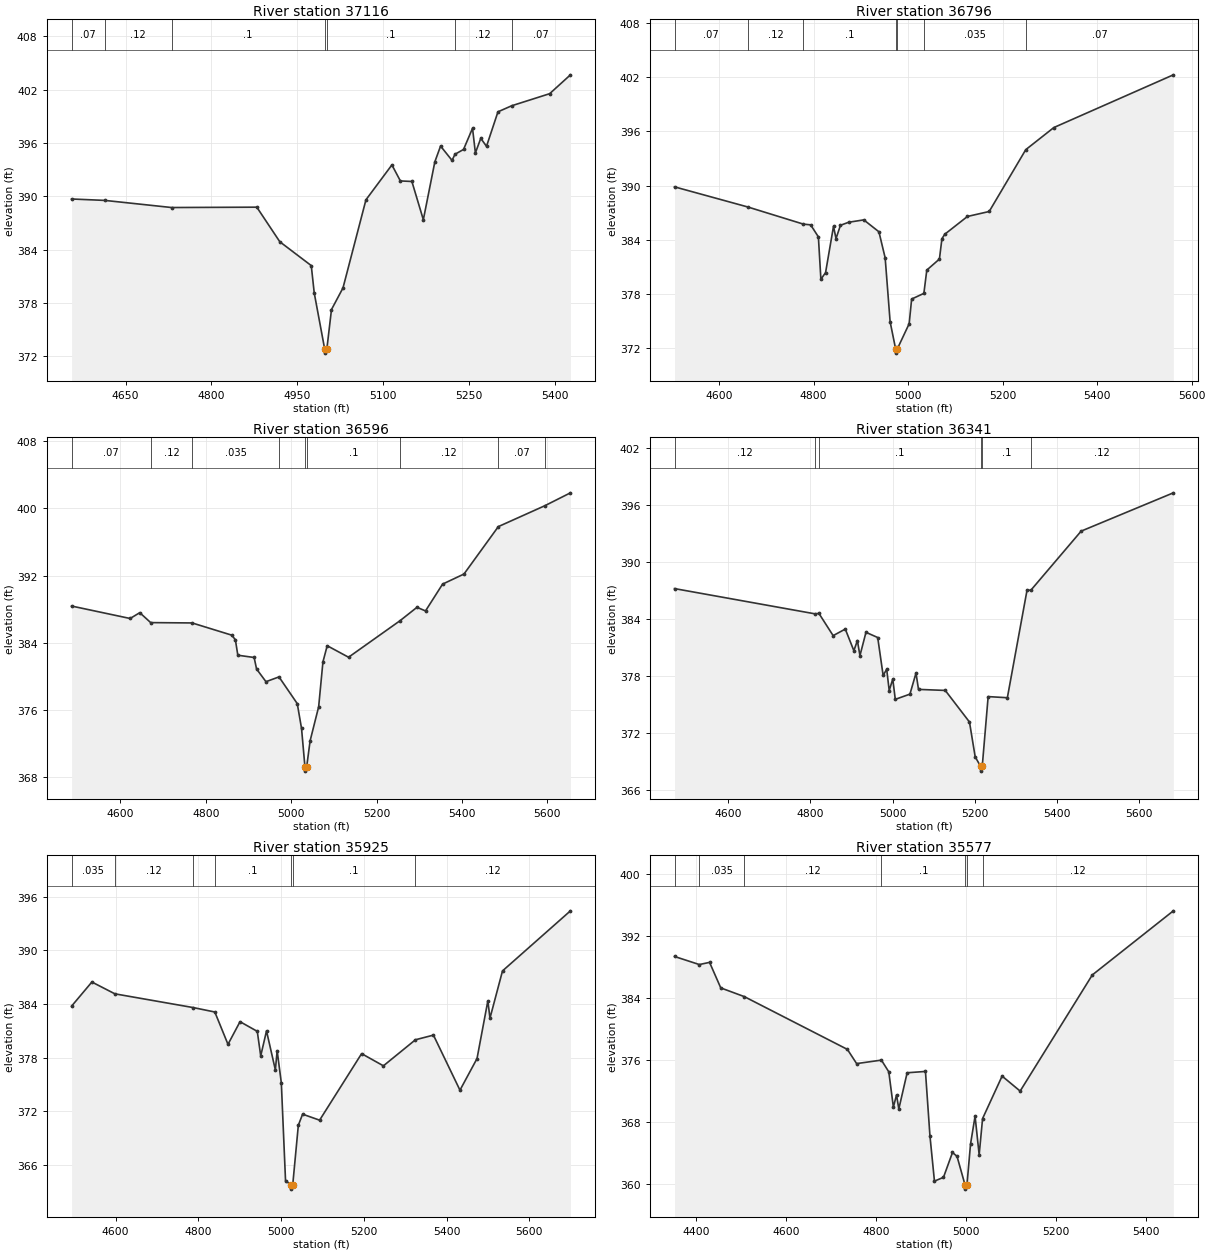
Type RM Length L Ch R = 1 ,37116   ,320,320,320
BEGIN DESCRIPTION:
XS7927
END DESCRIPTION:
XS GIS Cut Line= 3
      2534823.09     13750986.88      2534763.75      13751311.5
      2534802.06     13751851.24
#Sta/Elev= 30
  4555.8  389.69    4614  389.53  4730.4  388.73  4879.2  388.77  4919.4  384.88
  4974.3   382.2  4979.5  379.12  4997.6  372.86  4997.8  372.36  5001.6  372.86
  5009.6  377.26  5029.7  379.69  5069.8   389.6  5115.1  393.52  5129.9  391.72
    5150  391.66    5170  387.36  5190.1  393.87  5200.1  395.64  5220.1  394.03
  5225.3  394.72  5240.2  395.26  5255.9  397.64  5260.9  394.87  5270.3  396.51
  5280.3  395.61  5300.3  399.49  5324.2  400.17  5390.6  401.53  5426.9  403.65
#Mann= 7 ,-1 , 0
  4555.8     .07       0    4614     .12       0  4730.4      .1       0
  4997.6     .05       0  5001.6      .1       0  5225.3     .12       0
  5324.2     .07       0
Bank Sta=4997.6,5001.6
XS Rating Curve= 0 ,0
Exp/Cntr=0.3,0.1

Type RM Length L Ch R = 1 ,36796   ,200,200,200
BEGIN DESCRIPTION:
H21532
END DESCRIPTION:
XS GIS Cut Line= 3
      2534703.91     13750830.96      2534512.93     13751421.28
      2534482.55     13751855.27
#Sta/Elev= 30
  4505.8  389.86  4660.9  387.63  4778.5  385.73  4793.8  385.65  4810.2  384.32
  4815.5  379.62  4825.4  380.36  4842.2  385.49  4847.5  384.13  4856.9   385.6
  4874.3  385.94  4906.3   386.2  4938.3  384.88  4951.5  381.99    4962  374.91
  4973.5  371.94  4973.8  371.44  4977.5  371.94  5002.3   374.7  5007.5  377.43
  5033.4  378.06  5039.6  380.64  5066.3  381.86  5071.6  384.11  5077.6  384.61
  5125.6  386.58  5171.6  387.13    5249  393.98  5308.4  396.43  5561.3  402.27
#Mann= 7 ,-1 , 0
  4505.8     .07       0  4660.9     .12       0  4778.5      .1       0
  4973.5     .05       0  4977.5      .1       0  5033.4    .035       0
    5249     .07       0
Bank Sta=4973.5,4977.5
XS Rating Curve= 0 ,0
Exp/Cntr=0.3,0.1

Type RM Length L Ch R = 1 ,36596   ,255,255,255
BEGIN DESCRIPTION:
XS7928
END DESCRIPTION:
XS GIS Cut Line= 3
      2534641.58      13750704.1      2534411.19     13751136.97
      2534383.26     13751814.13
#Sta/Elev= 30
  4485.9  388.38  4622.9   386.9  4645.5  387.59  4671.1  386.41  4768.1  386.37
  4860.7  384.92  4869.4  384.37  4875.1  382.53  4913.3  382.26    4919  380.89
    4941  379.38  4971.5  379.95  5014.3  376.77  5024.3  373.82  5032.3  369.24
  5032.6  368.74  5036.3  369.24  5044.4  372.35  5064.4   376.4  5074.4  381.73
  5084.4  383.66  5134.4  382.29  5254.8  386.63  5294.6  388.23  5314.6   387.8
  5354.6  390.99  5404.7  392.19  5485.1  397.83  5593.8  400.31    5654  401.85
#Mann= 9 ,-1 , 0
  4485.9     .07       0  4671.1     .12       0  4768.1    .035       0
  4971.5      .1       0  5032.3     .05       0  5036.3      .1       0
  5254.8     .12       0  5485.1     .07       0  5593.8     .12       0
Bank Sta=5032.3,5036.3
XS Rating Curve= 0 ,0
Exp/Cntr=0.3,0.1

Type RM Length L Ch R = 1 ,36341   ,416,416,416
BEGIN DESCRIPTION:
XS7929
END DESCRIPTION:
XS GIS Cut Line= 3
      2534550.84     13750560.96      2534135.42     13751147.44
      2534292.52     13751618.74
#Sta/Elev= 30
  4468.7   387.2  4810.7  384.54  4820.6  384.58  4855.2  382.24  4884.8  382.93
  4905.7  380.65  4914.3  381.72  4920.5  380.13  4935.2  382.59  4963.8  382.04
    4977  378.05  4985.7  378.69  4991.8  376.45  5000.5  377.66  5006.6  375.52
  5042.3  376.07  5057.1  378.29  5063.2  376.57  5128.4  376.46  5187.4  373.13
  5201.3  369.46  5214.5  368.45  5214.7  367.95  5218.5  368.45  5232.9  375.81
  5279.7  375.69  5327.8  387.07  5336.6  387.01  5459.5  393.26  5684.2   397.3
#Mann= 6 ,-1 , 0
  4468.7     .12       0  4810.7    .035       0  4820.6      .1       0
  5214.5     .05       0  5218.5      .1       0  5336.6     .12       0
Bank Sta=5214.5,5218.5
XS Rating Curve= 0 ,0
Exp/Cntr=0.3,0.1

Type RM Length L Ch R = 1 ,35925   ,348,348,348
BEGIN DESCRIPTION:
XS7930
END DESCRIPTION:
XS GIS Cut Line= 3
      2534268.06     13750369.01      2533967.86     13750766.95
      2533803.79     13751454.67
#Sta/Elev= 30
  4493.7  383.76  4542.7  386.45  4598.3  385.13  4788.2  383.59  4839.8   383.1
  4871.6  379.49  4900.7  382.02  4942.4  380.94  4950.7   378.2  4964.7  380.99
  4986.1  376.63  4990.4  378.78  5000.5  375.19  5010.7  364.23  5024.1  363.82
  5024.4  363.32  5028.1  363.82  5041.6  370.45  5051.9  371.69    5093  371.02
  5194.5  378.45  5247.2  377.09  5324.6     380  5368.1  380.52  5432.2  374.37
  5473.4   377.9  5499.6  384.35  5504.7  382.41    5535  387.69  5699.2   394.4
#Mann= 7 ,-1 , 0
  4493.7    .035       0  4598.3     .12       0  4788.2    .035       0
  4839.8      .1       0  5024.1     .05       0  5028.1      .1       0
  5324.6     .12       0
Bank Sta=5024.1,5028.1
XS Rating Curve= 0 ,0
Exp/Cntr=0.3,0.1

Type RM Length L Ch R = 1 ,35577   ,356,356,356
BEGIN DESCRIPTION:
XS7931
END DESCRIPTION:
XS GIS Cut Line= 3
      2533810.78     13750288.71      2533699.08     13750826.29
      2533660.68     13751384.81
#Sta/Elev= 30
  4351.4  389.35  4406.5  388.31  4429.3  388.59  4454.2   385.3  4506.5  384.18
  4735.7  377.38  4756.2  375.55  4811.3     376  4827.7  374.49  4837.9  369.95
  4844.9  371.51    4850  369.71  4868.5  374.37  4909.2  374.54  4919.2  366.24
  4929.2  360.41  4949.3   360.9  4969.3   364.1  4979.4   363.6  4997.4  359.88
  4997.7  359.38  5001.4  359.88  5009.4  365.18  5019.5  368.77  5028.6  363.81
  5036.2  368.47  5079.6  373.94  5119.7  372.01  5280.1  386.97  5460.3  395.23
#Mann= 7 ,-1 , 0
  4351.4     .12       0  4406.5    .035       0  4506.5     .12       0
  4811.3      .1       0  4997.4     .05       0  5001.4      .1       0
  5036.2     .12       0
Bank Sta=4997.4,5001.4
XS Rating Curve= 0 ,0
Exp/Cntr=0.3,0.1

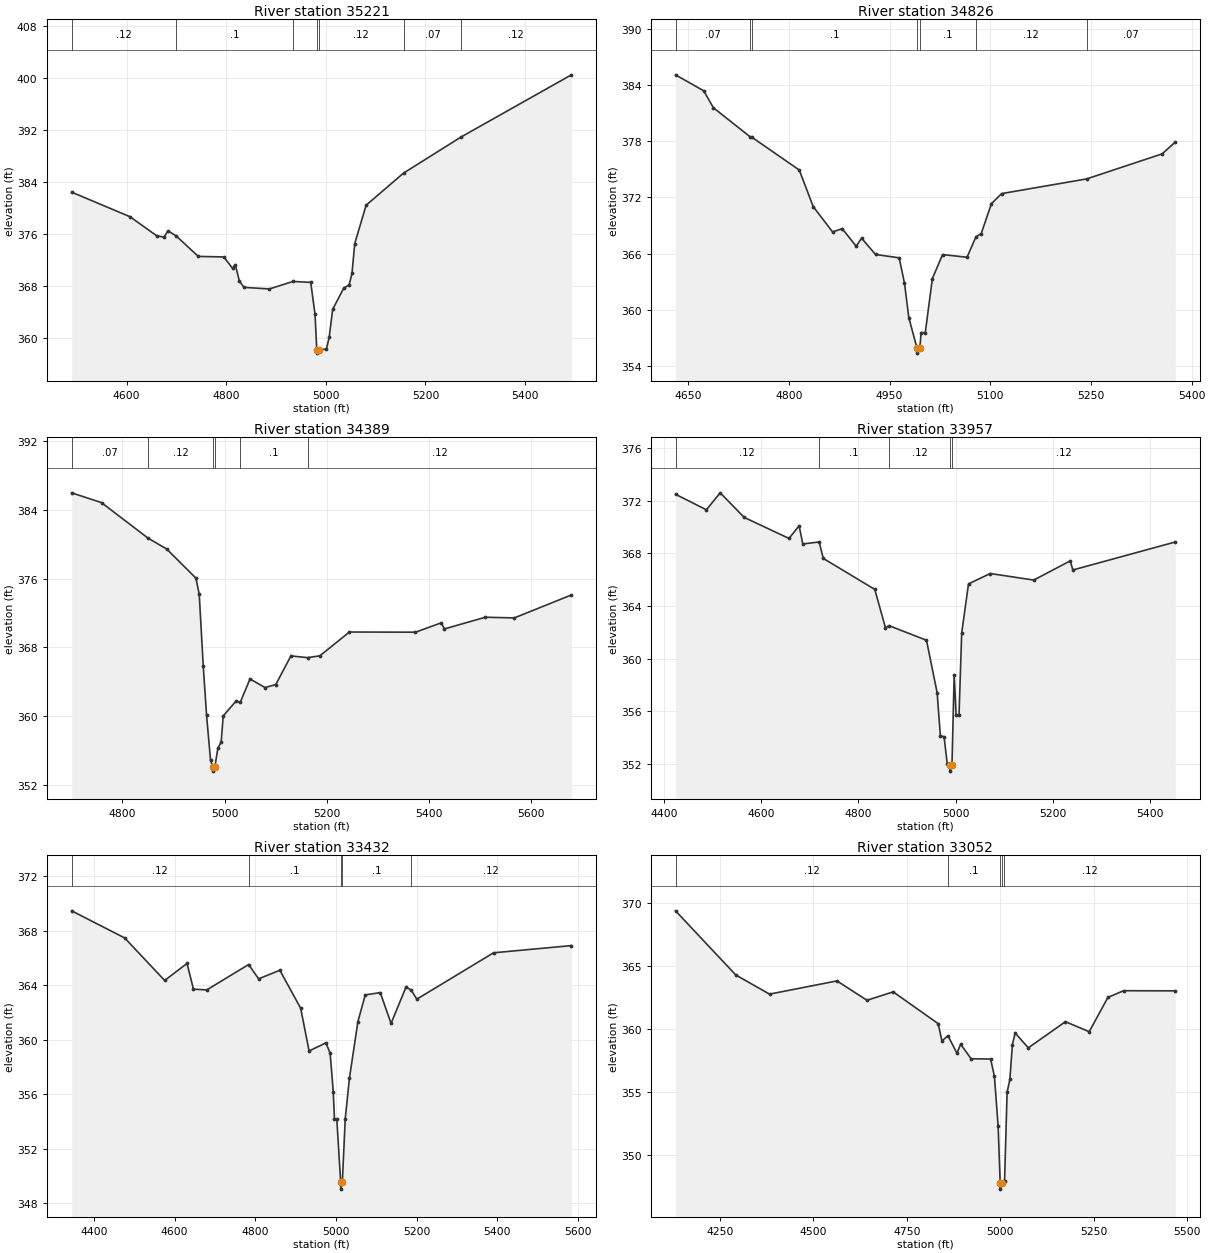
Type RM Length L Ch R = 1 ,35221   ,395,395,395
BEGIN DESCRIPTION:
XS7932
END DESCRIPTION:
XS GIS Cut Line= 3
      2533587.39     13750459.72      2533332.55     13751007.81
      2533304.62     13751405.79
#Sta/Elev= 30
  4489.6   382.5  4606.6  378.73  4660.8  375.77  4675.3   375.6  4682.9  376.55
  4699.2  375.79  4743.9  372.62  4795.2  372.54  4812.6  370.79  4818.1  371.36
  4826.3  368.85  4835.5  367.86  4886.8  367.62  4933.9  368.77  4969.6  368.63
  4978.3  363.71  4981.8  358.25  4982.1  357.75  4985.8  358.25  5001.2  358.38
  5006.7   360.2  5013.7  364.48  5035.8  367.73  5046.8  368.25  5052.5  370.01
    5058   374.6  5080.9   380.5    5156  385.43  5271.7  390.99    5493  400.54
#Mann= 7 ,-1 , 0
  4489.6     .12       0  4699.2      .1       0  4933.9     .12       0
  4981.8     .05       0  4985.8     .12       0    5156     .07       0
  5271.7     .12       0
Bank Sta=4981.8,4985.8
XS Rating Curve= 0 ,0
Exp/Cntr=0.3,0.1

Type RM Length L Ch R = 1 ,34826   ,437,437,437
BEGIN DESCRIPTION:
VANHAM CREEK 57.0
END DESCRIPTION:
XS GIS Cut Line= 3
      2533356.71     13750337.78        2533125.       13750625.
      2532923.05     13750941.41
#Sta/Elev= 30
  4631.2  385.11  4673.2   383.4  4687.6  381.59  4742.2  378.49  4744.9  378.44
  4815.5  374.93  4836.3  371.02  4865.1  368.31  4879.5  368.66  4900.3  366.78
  4908.3  367.64  4929.1   365.9  4964.3  365.54  4972.2  362.85  4978.7  359.14
    4991  355.85  4991.2  355.35  4995.1  355.85    4997  357.54  5003.2  357.54
  5013.8  363.33    5029  365.89  5065.4   365.6  5078.7  367.79  5086.5  368.13
  5101.8  371.34    5117  372.41  5243.6  373.98  5356.1  376.66  5375.6  377.92
#Mann= 7 ,-1 , 0
  4631.2     .07       0  4742.2     .12       0  4744.9      .1       0
    4991     .05       0  4995.1      .1       0  5078.7     .12       0
  5243.6     .07       0
Bank Sta=4991,4995.1
XS Rating Curve= 0 ,0
Exp/Cntr=0.3,0.1

Type RM Length L Ch R = 1 ,34389   ,432,432,432
BEGIN DESCRIPTION:
VANHAM CREEK 56.0
END DESCRIPTION:
XS GIS Cut Line= 3
      2533256.46     13750133.83        2533025.       13750325.
      2532635.57     13750881.35
#Sta/Elev= 30
  4700.4  385.99  4758.9  384.85  4850.1  380.72  4886.6  379.46  4943.9  376.07
  4950.4  374.19  4958.3  365.84  4964.8   360.1  4972.6  354.89    4977  354.12
  4977.3  353.62  4981.1  354.12  4986.9  356.29  4993.4  356.99  4997.4  360.04
  5022.8  361.79  5030.8  361.62  5049.9  364.34  5079.5  363.34  5100.4  363.69
  5130.1  367.02  5162.6  366.82  5186.7  367.03  5244.7   369.8  5374.2  369.78
  5424.8  370.87  5430.9  370.16  5511.1  371.52  5567.8  371.44  5679.7  374.11
#Mann= 6 ,-1 , 0
  4700.4     .07       0  4850.1     .12       0    4977     .05       0
  4981.1     .12       0  5030.8      .1       0  5162.6     .12       0
Bank Sta=4977,4981.1
XS Rating Curve= 0 ,0
Exp/Cntr=0.3,0.1

Type RM Length L Ch R = 1 ,33957   ,525,525,525
BEGIN DESCRIPTION:
VANHAM CREEK 55.0
END DESCRIPTION:
XS GIS Cut Line= 3
      2533065.88     13749946.65        2532625.       13750325.
      2532424.04     13750725.55
#Sta/Elev= 30
  4423.3   372.5  4486.8  371.32  4515.3  372.61  4564.7  370.74  4656.9  369.14
  4677.8   370.1  4685.4  368.72  4719.1  368.87  4727.5  367.62  4833.6  365.26
  4855.6  362.34    4863   362.5  4940.1  361.39    4962   357.4  4968.6  354.14
  4976.3  354.04  4982.9  351.96  4988.5  351.93  4988.7  351.43  4992.6  351.93
  4997.1  358.77    5001  355.72  5007.1  355.72  5012.6  361.95  5026.6  365.68
  5071.4  366.47  5160.9  365.97    5236  367.43  5241.6  366.74  5452.4  368.87
#Mann= 5 ,-1 , 0
  4423.3     .12       0  4719.1      .1       0    4863     .12       0
  4988.5     .05       0  4992.6     .12       0
Bank Sta=4988.5,4992.6
XS Rating Curve= 0 ,0
Exp/Cntr=0.3,0.1

Type RM Length L Ch R = 1 ,33432   ,380,380,380
BEGIN DESCRIPTION:
VANHAM CREEK 54.0
END DESCRIPTION:
XS GIS Cut Line= 3
       2533029.1     13749913.22      2532403.97     13750100.43
      2532223.45     13750658.71
#Sta/Elev= 30
  4344.5  369.45    4476  367.46  4575.2  364.34  4630.6  365.59  4646.6   363.7
  4679.7  363.65  4783.4  365.51  4808.1  364.46  4860.8  365.09  4912.5   362.3
  4933.3  359.17  4975.1  359.76  4985.5  359.01  4993.2  356.19  4996.3  354.14
  5002.1  354.14  5011.7  349.53    5012  349.03  5015.8  349.53  5022.9  354.18
  5033.4  357.18  5054.4  361.32  5072.6  363.28  5109.8  363.45  5136.6  361.19
  5173.9  363.87  5186.8  363.62  5200.6  362.97  5390.7  366.37  5583.8   366.9
#Mann= 5 ,-1 , 0
  4344.5     .12       0  4783.4      .1       0  5011.7     .05       0
  5015.8      .1       0  5186.8     .12       0
Bank Sta=5011.7,5015.8
XS Rating Curve= 0 ,0
Exp/Cntr=0.3,0.1

Type RM Length L Ch R = 1 ,33052   ,465,465,465
BEGIN DESCRIPTION:
VANHAM CREEK 53.0
END DESCRIPTION:
XS GIS Cut Line= 3
      2533045.78     13749879.79        2532175.       13749825.
      2531862.44     13750167.26
#Sta/Elev= 30
  4131.6  369.38  4292.7  364.28  4382.9  362.76  4563.2  363.81  4643.4  362.27
  4713.5  362.94  4833.8  360.41  4843.8  359.03  4859.8  359.46  4883.9  358.06
  4893.9  358.78  4921.7  357.62    4974   357.6  4984.1  356.22  4994.1  352.25
  4999.5  347.76  4999.8  347.26  5003.7  347.76  5010.1  347.85  5011.2  347.89
    5018  354.95  5025.4  355.98  5032.2  358.75  5039.6  359.67  5074.7  358.49
    5174  360.57  5237.5  359.77  5287.5   362.5  5329.4  363.03  5467.6  363.02
#Mann= 5 ,-1 , 0
  4131.6     .12       0  4859.8      .1       0  4999.5     .05       0
  5003.7      .1       0  5010.1     .12       0
Bank Sta=4999.5,5003.7
XS Rating Curve= 0 ,0
Exp/Cntr=0.3,0.1

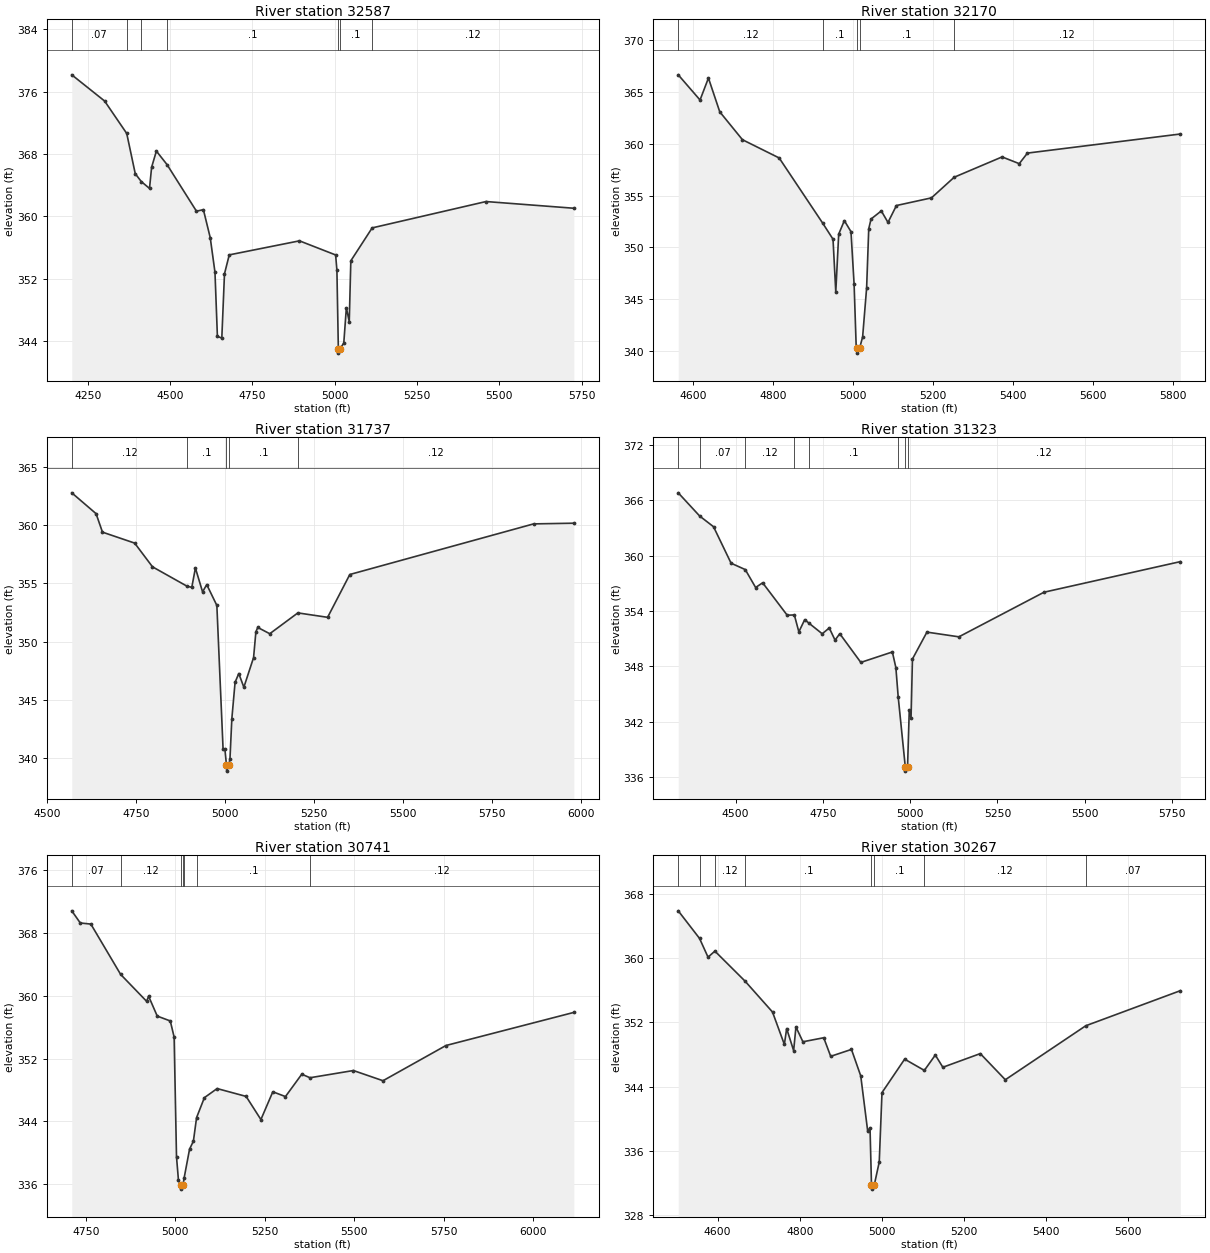
Type RM Length L Ch R = 1 ,32587   ,417,417,417
BEGIN DESCRIPTION:
VANHAM CREEK 52.0
END DESCRIPTION:
XS GIS Cut Line= 4
      2532668.07     13748896.96        2532175.       13749525.
      2532140.62     13749553.51      2531689.72     13750065.68
#Sta/Elev= 30
  4201.1  378.15  4300.9  374.79  4368.1  370.63    4394  365.47  4412.4  364.46
  4437.3  363.58  4443.7   366.3  4458.2  368.37  4490.5  366.64    4580  360.66
    4601  360.86  4621.8  357.27  4636.2  352.84  4643.6   344.6    4657   344.4
  4665.1  352.63  4679.6  355.06  4892.9  356.86  5002.8  355.05  5006.7  353.08
  5011.1  342.96  5011.4  342.46  5015.3  342.96  5027.6  343.75  5035.4  348.28
  5044.2  346.51    5049   354.3  5113.8  358.52  5459.8   361.9  5726.6  361.04
#Mann= 7 ,-1 , 0
  4201.1     .07       0  4368.1    .035       0  4412.4     .07       0
  4490.5      .1       0  5011.1     .05       0  5015.3      .1       0
  5113.8     .12       0
Bank Sta=5011.1,5015.3
XS Rating Curve= 0 ,0
Exp/Cntr=0.3,0.1

Type RM Length L Ch R = 1 ,32170   ,433,433,433
BEGIN DESCRIPTION:
VANHAM CREEK 51.0
END DESCRIPTION:
XS GIS Cut Line= 3
       2532285.3     13748878.48        2531975.       13749175.
      2531708.64     13749956.67
#Sta/Elev= 30
  4563.8  366.65  4618.3  364.22  4639.3  366.34  4667.6  363.08  4724.3  360.39
  4816.1  358.63  4924.9  352.34  4950.7  350.79  4957.6   345.7  4964.9  351.28
    4979  352.58  4995.6  351.52  5003.4  346.45  5008.7  340.34    5011   340.3
  5011.5   339.8  5017.3   340.3  5024.7  341.36  5034.7  346.09    5040   351.8
  5045.8  352.74  5071.4  353.52  5088.1  352.41  5109.2  354.04  5196.8  354.78
  5253.6  356.77  5373.3  358.73  5416.2  358.08  5436.7   359.1  5818.8  360.94
#Mann= 5 ,-1 , 0
  4563.8     .12       0  4924.9      .1       0    5011     .05       0
  5017.3      .1       0  5253.6     .12       0
Bank Sta=5011,5017.3
XS Rating Curve= 0 ,0
Exp/Cntr=0.3,0.1

Type RM Length L Ch R = 1 ,31737   ,414,414,414
BEGIN DESCRIPTION:
VANHAM CREEK 50.0
END DESCRIPTION:
XS GIS Cut Line= 4
      2531583.68     13748599.15        2531625.       13749025.
        2531725.       13749375.       2531628.4     13749986.77
#Sta/Elev= 30
  4568.8  362.78  4637.1  360.99  4655.1   359.4  4745.5  358.46  4795.7  356.42
    4893  354.75  4906.2  354.66  4916.3  356.32  4936.4  354.27  4948.2  354.89
  4976.6   353.1  4994.1  340.75  4999.2  340.75  5003.7  339.36  5004.2  338.86
  5010.3  339.36  5013.5  339.93  5018.7  343.36  5027.8  346.49  5038.2  347.25
  5052.5  346.07  5079.8  348.62  5086.3  350.83  5091.5  351.21  5125.3  350.67
  5204.3  352.46  5287.9  352.08  5350.3  355.76  5866.8  360.11    5980  360.17
#Mann= 5 ,-1 , 0
  4568.8     .12       0    4893      .1       0  5003.7     .05       0
  5010.3      .1       0  5204.3     .12       0
Bank Sta=5003.7,5010.3
XS Rating Curve= 0 ,0
Exp/Cntr=0.3,0.1

Type RM Length L Ch R = 1 ,31323   ,582,582,582
BEGIN DESCRIPTION:
VANHAM CREEK 49.0
END DESCRIPTION:
XS GIS Cut Line= 4
      2531307.92      13748564.3      2531370.75     13749234.51
        2531425.       13749475.      2531484.65     13749990.08
#Sta/Elev= 30
  4335.6   366.8  4397.2  364.28  4436.7  363.13    4487  359.18  4527.6  358.49
  4557.3  356.55  4577.4  357.06  4647.7  353.55  4668.2  353.58  4681.1  351.75
  4697.9  353.07    4711  352.66  4748.1  351.54  4768.2  352.17  4784.8  350.85
  4798.3  351.55  4858.6  348.44    4949  349.57    4959  347.88  4965.6  344.74
  4985.9  337.17  4986.4  336.67  4992.5  337.17  4997.4  343.26  5002.5  342.44
  5006.5  348.81    5048  351.72  5139.5  351.21  5383.4  356.04  5773.8  359.35
#Mann= 8 ,-1 , 0
  4335.6     .12       0  4397.2     .07       0  4527.6     .12       0
  4668.2     .07       0    4711      .1       0  4965.6     .12       0
  4985.9     .05       0  4992.5     .12       0
Bank Sta=4985.9,4992.5
XS Rating Curve= 0 ,0
Exp/Cntr=0.3,0.1

Type RM Length L Ch R = 1 ,30741   ,474,474,474
BEGIN DESCRIPTION:
VANHAM CREEK 48.0
END DESCRIPTION:
XS GIS Cut Line= 4
      2530920.45     13748609.67      2531070.55     13748983.18
        2531225.       13749575.      2531297.46      13749956.7
#Sta/Elev= 30
  4711.1  370.83  4734.9  369.28  4764.4  369.14  4847.7  362.72  4920.3  359.29
  4925.7  359.95  4949.9  357.41  4986.3  356.79  4997.1  354.73  5003.7  339.47
  5009.1  336.52  5015.3  335.85  5015.8  335.35  5021.9  335.85  5024.9  336.74
  5040.2  340.45  5050.9  341.46  5059.8  344.47  5081.6  347.01  5117.2  348.17
  5198.2  347.17  5239.5  344.22  5272.8  347.76  5308.1  347.15  5353.7     350
  5376.7  349.55  5497.9  350.47  5580.6  349.17  5756.5  353.66  6113.8  357.88
#Mann= 7 ,-1 , 0
  4711.1     .07       0  4847.7     .12       0  5015.3     .05       0
  5021.9     .12       0  5024.9     .07       0  5059.8      .1       0
  5376.7     .12       0
Bank Sta=5015.3,5021.9
XS Rating Curve= 0 ,0
Exp/Cntr=0.3,0.1

Type RM Length L Ch R = 1 ,30267   ,356,356,356
BEGIN DESCRIPTION:
VANHAM CREEK 47.0
END DESCRIPTION:
XS GIS Cut Line= 4
      2530536.48      13748728.4      2530773.83     13749217.06
      2530958.84     13749716.24       2531010.2     13749854.81
#Sta/Elev= 30
  4503.9  365.87  4555.8  362.44  4576.5  360.11  4593.2  360.86  4666.7  357.13
  4733.6  353.29  4762.5  349.26  4768.1  351.23  4785.1  348.49  4790.7  351.43
  4807.7  349.59  4858.4  350.09  4875.4  347.78    4926  348.64  4948.6  345.35
  4965.6  338.46  4971.2  338.91  4974.8  331.77  4975.3  331.27  4981.5  331.77
  4993.7  334.64  5000.4  343.27  5055.6  347.43  5103.6  346.03  5130.3  347.94
  5148.7  346.42  5239.9  348.12  5300.9  344.87  5496.9  351.58  5727.3  355.94
#Mann= 8 ,-1 , 0
  4503.9     .12       0  4555.8     .07       0  4593.2     .12       0
  4666.7      .1       0  4974.8     .05       0  4981.5      .1       0
  5103.6     .12       0  5496.9     .07       0
Bank Sta=4974.8,4981.5
XS Rating Curve= 0 ,0
Exp/Cntr=0.3,0.1

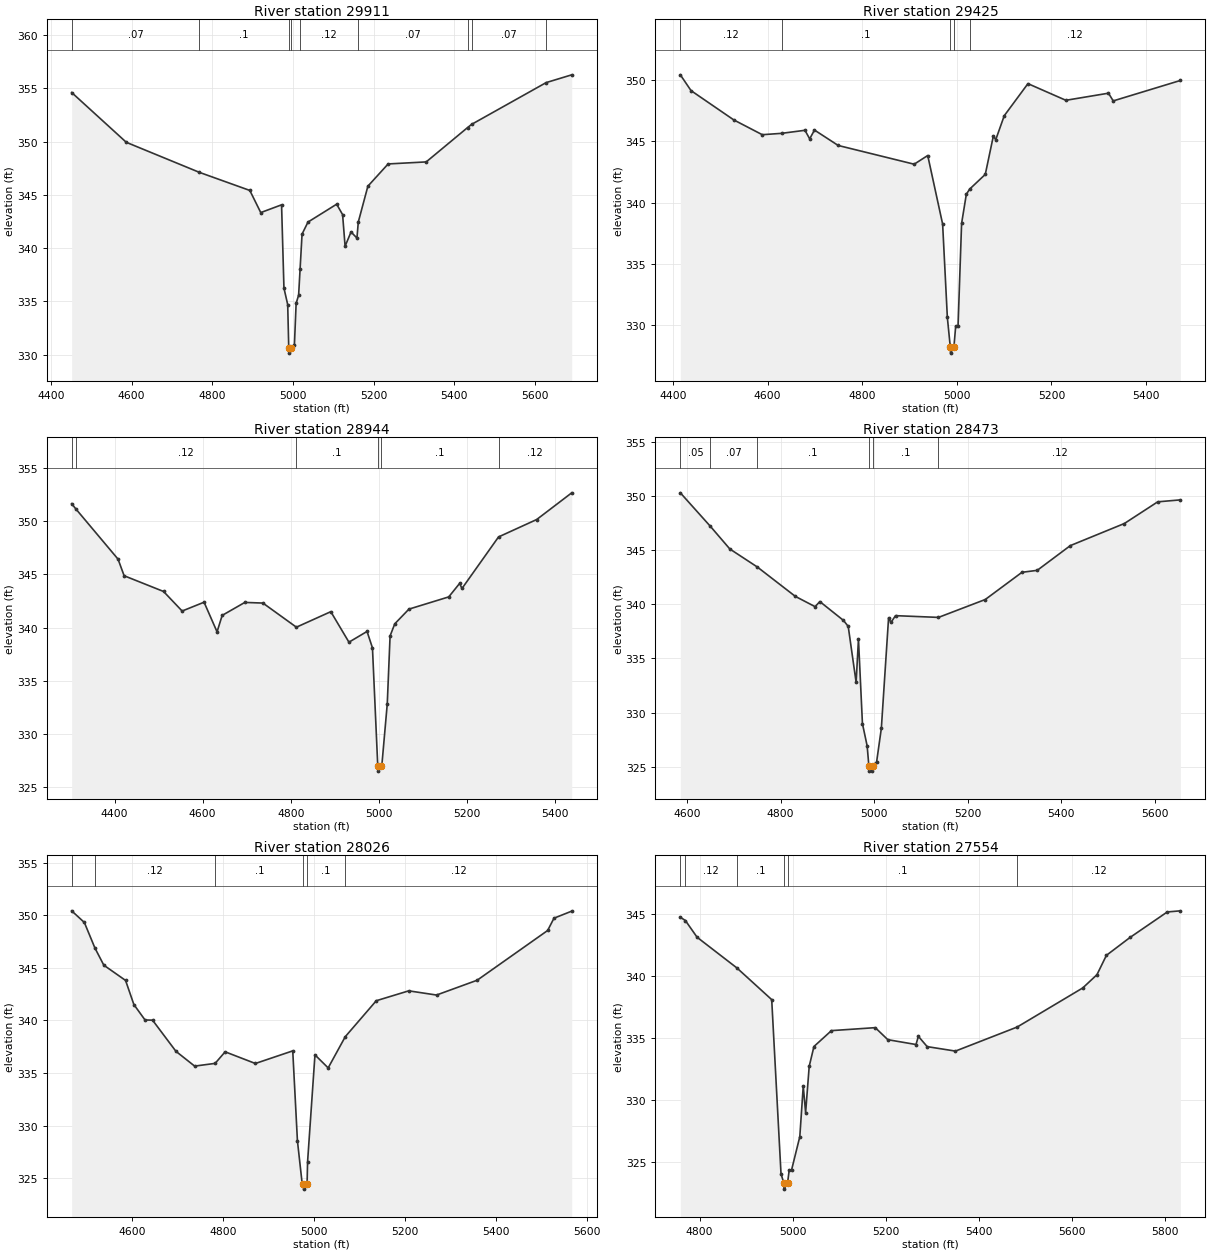
Type RM Length L Ch R = 1 ,29911   ,486,486,486
BEGIN DESCRIPTION:
VANHAM CREEK 46.0
END DESCRIPTION:
XS GIS Cut Line= 4
       2530229.3     13748962.27        2530525.       13749425.
      2530927.43     13749716.24      2531084.51     13749829.91
#Sta/Elev= 30
  4451.5  354.61    4587  349.93  4768.1  347.11  4893.2  345.41  4920.3  343.33
  4971.9  344.06  4977.8  336.24  4987.1  334.69  4989.7  330.63  4990.2  330.13
  4996.4  330.63  5003.7  330.85    5008   334.8  5014.2  335.58  5017.8  338.01
  5022.7  341.31  5037.4  342.44  5108.5  344.12  5123.2  343.14  5129.4  340.17
  5144.1  341.51  5158.8  340.94  5162.1  342.44  5185.9  345.81  5236.1   347.9
  5330.5  348.09  5432.9  351.31  5443.2  351.62  5627.9  355.54  5691.3  356.27
#Mann= 9 ,-1 , 0
  4451.5     .07       0  4768.1      .1       0  4989.7     .05       0
  4996.4      .1       0  5017.8     .12       0  5162.1     .07       0
  5432.9     .12       0  5443.2     .07       0  5627.9     .12       0
Bank Sta=4989.7,4996.4
XS Rating Curve= 0 ,0
Exp/Cntr=0.3,0.1

Type RM Length L Ch R = 1 ,29425   ,481,481,481
BEGIN DESCRIPTION:
VANHAM CREEK 45.0
END DESCRIPTION:
XS GIS Cut Line= 3
      2530124.55     13749042.49        2530175.       13749625.
      2530204.85     13750096.77
#Sta/Elev= 30
  4415.4  350.43    4438  349.14  4528.3  346.75  4588.6  345.54  4629.3  345.65
  4678.9   345.9  4688.9   345.2    4699  345.92  4749.2  344.66  4909.8  343.13
  4938.5  343.84    4970  338.24    4980  330.61  4986.2   328.2  4986.7   327.7
  4993.9   328.2  4997.6   329.9  5002.6   329.9  5010.1  338.29  5020.1  340.67
    5027  341.09  5060.2   342.3  5077.3  345.44  5082.3  345.13  5100.3  347.09
  5150.4  349.71  5230.6  348.35  5320.7  348.93  5330.7   348.3  5472.8  349.97
#Mann= 5 ,-1 , 0
  4415.4     .12       0  4629.3      .1       0  4986.2     .05       0
  4993.9      .1       0    5027     .12       0
Bank Sta=4986.2,4993.9
XS Rating Curve= 0 ,0
Exp/Cntr=0.3,0.1

Type RM Length L Ch R = 1 ,28944   ,471,471,471
BEGIN DESCRIPTION:
VANHAM CREEK 44.0
END DESCRIPTION:
XS GIS Cut Line= 3
      2529887.18     13749042.55        2529725.       13749725.
      2529570.06     13750130.23
#Sta/Elev= 30
  4302.7  351.65  4311.9  351.17    4408  346.43  4421.8  344.87  4511.3  343.39
  4553.5  341.55  4603.3  342.38  4632.8  339.59  4644.4  341.14  4695.8  342.36
  4736.9   342.3  4812.9  340.03    4891  341.49  4932.2  338.62  4973.3  339.63
  4985.6  338.08  4997.6  326.99  4998.1  326.49  5005.5  326.99  5006.8  326.99
  5019.2  332.82  5025.6  339.21  5036.3  340.35  5068.4  341.73  5158.8  342.88
  5183.5  344.15  5188.8  343.67  5271.8  348.52  5358.5  350.16    5438  352.67
#Mann= 6 ,-1 , 0
  4302.7     .07       0  4311.9     .12       0  4812.9      .1       0
  4997.6     .05       0  5005.5      .1       0  5271.8     .12       0
Bank Sta=4997.6,5005.5
XS Rating Curve= 0 ,0
Exp/Cntr=0.3,0.1

Type RM Length L Ch R = 1 ,28473   ,447,447,447
BEGIN DESCRIPTION:
VANHAM CREEK 43.0
END DESCRIPTION:
XS GIS Cut Line= 3
      2529311.22     13749070.46        2529375.       13749475.
      2529283.29     13750128.15
#Sta/Elev= 30
  4585.6  350.27    4650  347.17  4691.4  345.09  4750.1  343.43  4831.4  340.72
  4873.7  339.77  4883.8  340.24  4934.4   338.5  4944.5  337.95  4961.4  332.79
  4966.4  336.77  4974.9  328.98    4985  326.92  4988.6   325.1  4989.1   324.6
  4996.1   324.6  4996.6   325.1  5005.2  325.45  5015.3  328.54  5030.8  338.75
  5035.8  338.31  5045.6  338.94  5137.5  338.78  5237.5  340.43    5316  342.94
  5348.6  343.12  5419.3   345.4  5534.9  347.44  5606.2  349.44  5654.7  349.62
#Mann= 6 ,-1 , 0
  4585.6     .05       0    4650     .07       0  4750.1      .1       0
  4988.6     .05       0  4996.6      .1       0  5137.5     .12       0
Bank Sta=4988.6,4996.6
XS Rating Curve= 0 ,0
Exp/Cntr=0.3,0.1

Type RM Length L Ch R = 1 ,28026   ,472,472,472
BEGIN DESCRIPTION:
VANHAM CREEK 42.0
END DESCRIPTION:
XS GIS Cut Line= 3
      2528853.93     13749101.88        2528975.       13749625.
      2529077.34     13750177.05
#Sta/Elev= 30
  4467.2  350.42  4495.1  349.31  4518.2  346.89  4537.8  345.25  4585.6   343.8
  4603.8  341.51  4628.3  340.04  4644.9  340.02  4696.2  337.06  4737.3  335.65
  4782.3  335.91  4804.3  337.01  4870.7   335.9  4952.8   337.1  4963.1  328.54
  4973.4  324.51  4976.2  324.45  4976.7  323.95  4984.3  324.45  4985.4  326.56
  5001.6  336.72  5030.6  335.48  5068.2  338.45  5136.3  341.87  5207.6  342.81
  5268.6  342.41  5357.9  343.82  5512.7  348.55  5526.6  349.72  5565.6  350.39
#Mann= 6 ,-1 , 0
  4467.2     .05       0  4518.2     .12       0  4782.3      .1       0
  4976.2     .05       0  4984.3      .1       0  5068.2     .12       0
Bank Sta=4976.2,4984.3
XS Rating Curve= 0 ,0
Exp/Cntr=0.3,0.1

Type RM Length L Ch R = 1 ,27554   ,474,474,474
BEGIN DESCRIPTION:
VANHAM CREEK 41.0
END DESCRIPTION:
XS GIS Cut Line= 3
      2528592.12     13749189.14        2528575.       13749425.
      2528713.98     13750251.92
#Sta/Elev= 30
  4758.8  344.72  4769.6  344.46  4794.8  343.11  4880.2  340.64  4955.2  338.08
  4975.2  324.03  4981.2   323.3  4981.7   322.8  4989.3   323.3  4992.8  324.33
  4997.8  324.33  5015.6  327.03    5023  331.11  5028.1  328.97  5035.8   332.7
    5046   334.3  5083.6  335.58  5177.8  335.82  5204.8  334.85  5265.4  334.46
  5270.5  335.12  5289.4  334.29  5350.2  333.93  5482.9  335.87  5623.8  339.02
  5654.4  340.09  5674.7  341.65  5725.4  343.09  5805.6  345.15  5833.8  345.24
#Mann= 6 ,-1 , 0
  4758.8     .05       0  4769.6     .12       0  4880.2      .1       0
  4981.2     .05       0  4989.3      .1       0  5482.9     .12       0
Bank Sta=4981.2,4989.3
XS Rating Curve= 0 ,0
Exp/Cntr=0.3,0.1