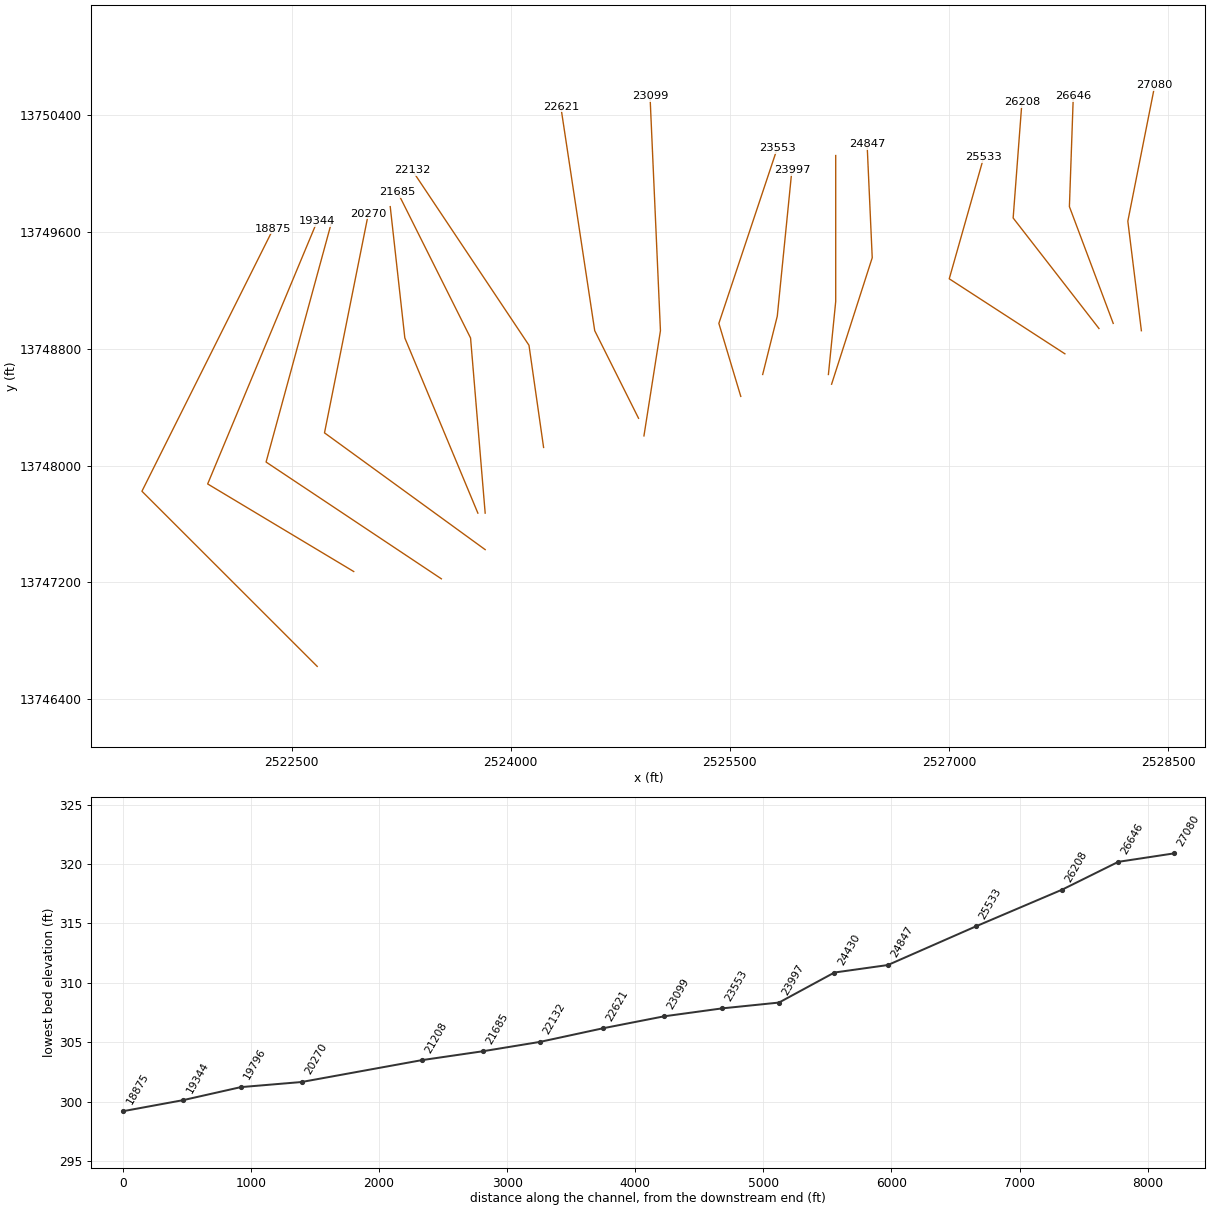
HEC-RAS study VANHAM CREEK.prj: VANHAM CREEK Base Level Engineering

--- VANHAM CREEK.g01 (geometry) --- (continued)

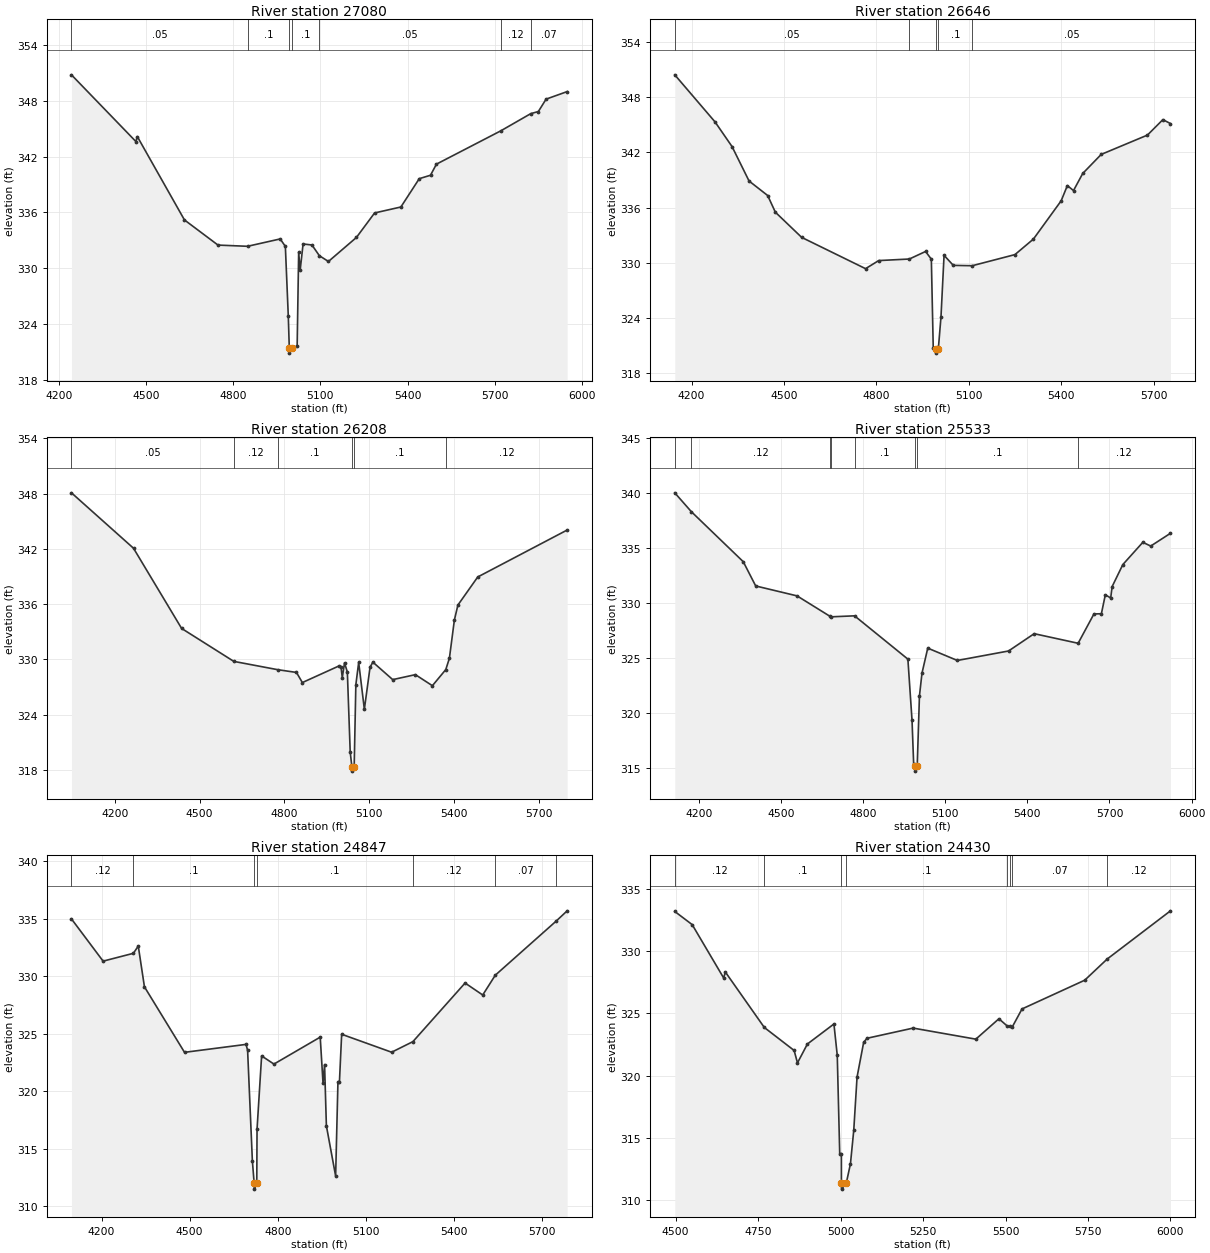
Type RM Length L Ch R = 1 ,27080   ,434,434,434
BEGIN DESCRIPTION:
VANHAM CREEK 40.0
END DESCRIPTION:
XS GIS Cut Line= 3
      2528317.77     13748924.73        2528225.       13749675.
      2528409.48     13750606.12
#Sta/Elev= 30
  4243.7  350.78  4465.3  343.62  4470.3  344.15  4632.4   335.2  4747.8   332.5
  4849.5  332.37  4961.7  333.16  4979.5  332.36  4989.6  324.87  4993.1   321.4
  4993.6   320.9  5001.3   321.4  5020.1  321.68  5025.3  331.74  5030.4   329.8
  5040.5  332.62    5071  332.51  5096.5  331.36  5127.7  330.74    5224  333.32
  5286.5  335.95  5376.9  336.59  5440.1  339.63  5478.8     340  5499.2  341.19
  5720.8  344.77  5823.5  346.61  5849.8  346.84  5876.4  348.17  5948.9  348.98
#Mann= 7 ,-1 , 0
  4243.7     .05       0  4849.5      .1       0  4993.1     .05       0
  5001.3      .1       0  5096.5     .05       0  5720.8     .12       0
  5823.5     .07       0
Bank Sta=4993.1,5001.3
XS Rating Curve= 0 ,0
Exp/Cntr=0.3,0.1

Type RM Length L Ch R = 1 ,26646   ,438,438,438
BEGIN DESCRIPTION:
VANHAM CREEK 39.0
END DESCRIPTION:
XS GIS Cut Line= 3
        2528125.     13748974.99        2527825.       13749775.
      2527851.58     13750529.72
#Sta/Elev= 30
  4145.5  350.44  4276.3  345.32  4331.5  342.64  4386.7   338.9  4447.2  337.32
  4472.1  335.51  4557.6  332.77    4765  329.37  4807.7  330.25  4907.2  330.42
  4959.9  331.24  4978.6   330.4  4984.8  320.72  4993.1  320.69  4993.6  320.19
  5001.4  320.69  5009.9  324.12  5019.9  330.82  5049.9  329.73  5111.2  329.69
  5250.1   330.9  5310.1  332.59  5400.2  336.75  5420.2   338.4  5440.2  337.86
  5470.2  339.72  5530.2  341.79  5680.3  343.89  5730.4  345.57  5755.1  345.14
#Mann= 5 ,-1 , 0
  4145.5     .05       0  4907.2      .1       0  4993.1     .05       0
  5001.4      .1       0  5111.2     .05       0
Bank Sta=4993.1,5001.4
XS Rating Curve= 0 ,0
Exp/Cntr=0.3,0.1

Type RM Length L Ch R = 1 ,26208   ,675,675,675
BEGIN DESCRIPTION:
VANHAM CREEK 38.0
END DESCRIPTION:
XS GIS Cut Line= 3
      2528027.37     13748940.04      2527439.83      13749697.2
      2527499.96     13750490.54
#Sta/Elev= 30
  4046.5  348.08  4266.1  342.06  4436.3  333.35    4621  329.77  4776.2  328.87
  4842.7  328.57  4863.5  327.47    4992  329.26  5000.2  329.19  5004.8  328.01
  5012.7  329.61  5022.7  328.62  5032.8  319.95  5038.6  318.35  5039.1  317.85
  5046.9  318.35  5052.8  327.24  5062.8  329.66  5082.9  324.57    5103  329.13
    5113  329.69  5183.2  327.79  5263.4  328.33  5323.6  327.13    5371  328.88
  5383.8  330.11  5401.4  334.26  5413.9  335.89  5484.1  338.94  5800.5  344.04
#Mann= 6 ,-1 , 0
  4046.5     .05       0    4621     .12       0  4776.2      .1       0
  5038.6     .05       0  5046.9      .1       0    5371     .12       0
Bank Sta=5038.6,5046.9
XS Rating Curve= 0 ,0
Exp/Cntr=0.3,0.1

Type RM Length L Ch R = 1 ,25533   ,686,686,686
BEGIN DESCRIPTION:
VANHAM CREEK 37.0
END DESCRIPTION:
XS GIS Cut Line= 3
      2527794.03     13748766.63      2527002.33     13749280.54
      2527238.44     13750113.87
#Sta/Elev= 30
  4112.7     340  4173.2  338.29  4362.8  333.75  4408.2  331.55  4559.2  330.65
  4679.2   328.8    4684  328.75  4769.1  328.84  4963.9  324.91    4979  319.36
    4985  315.36  4989.6  315.25  4990.1  314.75    4998  315.25  5006.1  321.57
  5015.3  323.63  5036.4  325.91  5144.4  324.79  5331.4  325.65    5425  327.22
  5585.5  326.35  5643.2  329.01  5670.4  329.03  5684.8  330.75  5704.4  330.46
  5709.6  331.49  5748.7  333.49  5821.7  335.51  5850.5  335.17  5922.7  336.33
#Mann= 8 ,-1 , 0
  4112.7     .05       0  4173.2     .12       0  4679.2     .07       0
    4684     .12       0  4769.1      .1       0  4989.6     .05       0
    4998      .1       0  5585.5     .12       0
Bank Sta=4989.6,4998
XS Rating Curve= 0 ,0
Exp/Cntr=0.3,0.1

Type RM Length L Ch R = 1 ,24847   ,417,417,417
BEGIN DESCRIPTION:
VANHAM CREEK 36.0
END DESCRIPTION:
XS GIS Cut Line= 3
      2526196.77     13748558.29        2526475.       13749425.
      2526439.92     13750202.33
#Sta/Elev= 30
  4097.5  334.97  4205.3   331.3  4308.4  331.98  4325.1  332.61  4346.1  329.07
  4482.6  323.38  4692.2  324.07  4697.5  323.55  4713.7  313.97  4719.8     312
  4720.3   311.5  4728.7     312  4729.6  316.69  4745.2  323.07  4787.2  322.36
  4944.8   324.7  4954.4  320.69  4959.6  322.32  4965.8     317  4997.3  312.64
  5005.2  320.83  5010.3  320.83  5017.8  324.95    5188  323.39  5260.5  324.31
  5438.2   329.4  5498.3  328.36  5541.1  330.08  5747.2  334.75  5785.9  335.67
#Mann= 7 ,-1 , 0
  4097.5     .12       0  4308.4      .1       0  4719.8     .05       0
  4728.7      .1       0  5260.5     .12       0  5541.1     .07       0
  5747.2     .12       0
Bank Sta=4719.8,4728.7
XS Rating Curve= 0 ,0
Exp/Cntr=0.3,0.1

Type RM Length L Ch R = 1 ,24430   ,433,433,433
BEGIN DESCRIPTION:
VANHAM CREEK 35.0
END DESCRIPTION:
XS GIS Cut Line= 3
        2526175.     13748624.99        2526225.       13749125.
        2526225.       13750125.
#Sta/Elev= 30
  4497.5   333.2  4550.3  332.14  4645.7  327.85  4650.8  328.33  4768.9  323.87
  4859.3  322.02  4869.4  321.02  4899.5  322.54  4979.9  324.15    4990  321.63
  4997.5   313.7  5002.5   313.7  5002.6  311.37  5003.1  310.87  5017.5  311.37
    5030  312.91    5040   315.6    5050  319.88    5070  322.67    5080     323
    5220  323.82    5410  322.93    5480  324.57  5505.9  323.97  5512.7  323.96
  5520.6  323.92    5550  325.36    5740  327.67    5808  329.37    6000  333.25
#Mann= 8 ,-1 , 0
  4497.5     .12       0  4768.9      .1       0  5002.6     .05       0
  5017.5      .1       0  5505.9     .07       0  5512.7     .12       0
  5520.6     .07       0    5808     .12       0
Bank Sta=5002.6,5017.5
XS Rating Curve= 0 ,0
Exp/Cntr=0.3,0.1

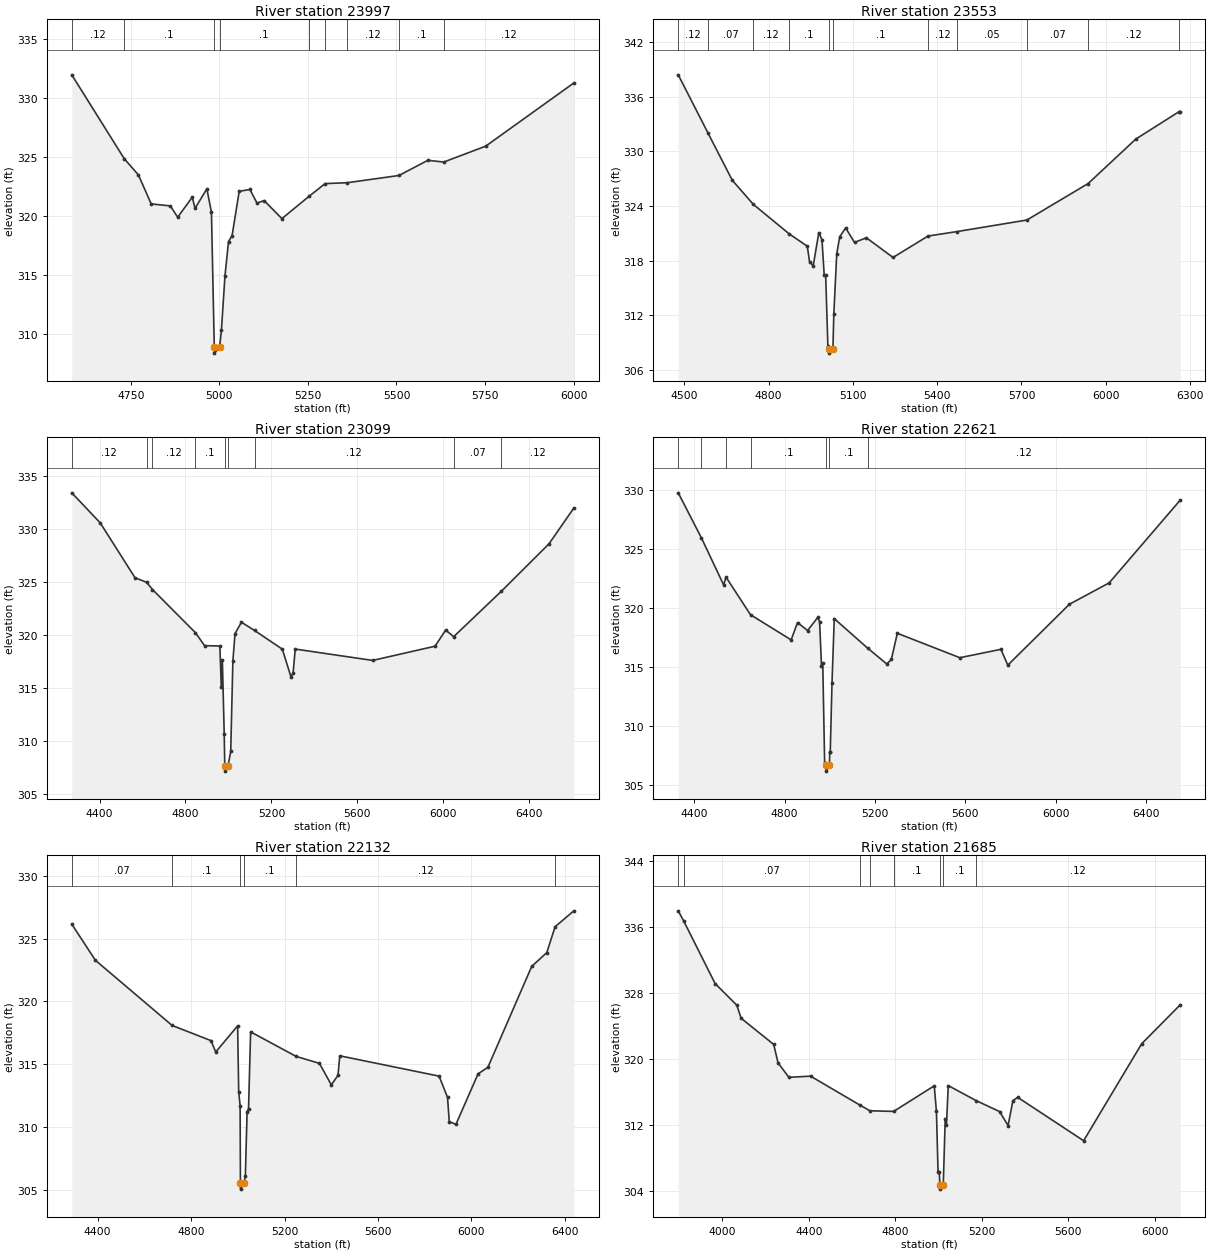
Type RM Length L Ch R = 1 ,23997   ,444,444,444
BEGIN DESCRIPTION:
VANHAM CREEK 34.0
END DESCRIPTION:
XS GIS Cut Line= 3
      2525724.99     13748624.97        2525825.       13749025.
        2525925.     13750024.97
#Sta/Elev= 30
  4583.4  331.95  4731.4  324.84  4771.5  323.46  4807.6     321  4861.7  320.83
  4882.4  319.87  4923.6  321.57  4931.3  320.62  4964.8  322.28  4977.7  320.29
  4985.7  308.84  4986.2  308.34  5000.6  308.84  5005.8  310.26  5015.8  314.87
  5025.9  317.81  5035.9   318.3    5056  322.06  5086.2  322.23  5106.3  321.07
  5126.4  321.28  5176.6  319.75  5252.6  321.63  5298.5  322.72  5361.7   322.8
    5507  323.41  5588.7   324.7  5633.4  324.55    5752   325.9  6000.7  331.26
#Mann= 9 ,-1 , 0
  4583.4     .12       0  4731.4      .1       0  4985.7     .05       0
  5000.6      .1       0  5252.6     .12       0  5298.5      .1       0
  5361.7     .12       0    5507      .1       0  5633.4     .12       0
Bank Sta=4985.7,5000.6
XS Rating Curve= 0 ,0
Exp/Cntr=0.3,0.1

Type RM Length L Ch R = 1 ,23553   ,454,454,454
BEGIN DESCRIPTION:
VANHAM CREEK 33.0
END DESCRIPTION:
XS GIS Cut Line= 3
      2525575.01     13748474.95        2525425.       13748975.
      2525825.01     13750175.02
#Sta/Elev= 30
  4478.4  338.42  4585.1  331.98  4670.7  326.84    4746  324.18  4873.4  320.95
  4937.8  319.59  4945.7   317.9  4958.7  317.43  4978.7  321.08    4990  320.31
  4997.9  316.45  5003.1  316.45    5011  308.67  5014.1  308.35  5014.6  307.85
    5029  308.35  5032.1   312.1  5042.6  318.77  5053.2  320.64  5074.2   321.6
  5105.9  320.01    5148  320.52  5242.9  318.36  5367.4  320.71  5472.2  321.21
  5719.3  322.47  5937.4  326.48  6107.3  331.37  6261.8  334.39  6265.4  334.38
#Mann= 11 ,-1 , 0
  4478.4     .12       0  4585.1     .07       0    4746     .12       0
  4873.4      .1       0  5014.1     .05       0    5029      .1       0
  5367.4     .12       0  5472.2     .05       0  5719.3     .07       0
  5937.4     .12       0  6261.8     .07       0
Bank Sta=5014.1,5029
XS Rating Curve= 0 ,0
Exp/Cntr=0.3,0.1

Type RM Length L Ch R = 1 ,23099   ,478,478,478
BEGIN DESCRIPTION:
VANHAM CREEK 32.0
END DESCRIPTION:
XS GIS Cut Line= 3
      2524912.06     13748204.15        2525025.       13748925.
      2524953.74     13750530.27
#Sta/Elev= 30
  4270.8   333.4  4403.2  330.57  4565.2   325.4  4619.2  324.97  4646.4  324.29
  4845.5  320.24  4889.1     319    4960  318.97  4966.6  315.11  4971.6  317.64
  4980.2  310.71  4982.8  307.68  4983.3  307.18  4997.9  307.68  5010.5  309.03
  5020.5  317.54  5030.5  320.14  5060.5  321.21  5121.4  320.43  5250.7  318.67
  5290.7  316.07  5300.7  316.42  5310.8  318.68  5671.1  317.61  5961.4  318.95
  6010.8  320.47  6048.2  319.85  6269.7  324.12  6491.9   328.6  6607.3  331.97
#Mann= 9 ,-1 , 0
  4270.8     .12       0  4619.2     .07       0  4646.4     .12       0
  4845.5      .1       0  4982.8     .05       0  4997.9      .1       0
  5121.4     .12       0  6048.2     .07       0  6269.7     .12       0
Bank Sta=4982.8,4997.9
XS Rating Curve= 0 ,0
Exp/Cntr=0.3,0.1

Type RM Length L Ch R = 1 ,22621   ,489,489,489
BEGIN DESCRIPTION:
VANHAM CREEK 31.0
END DESCRIPTION:
XS GIS Cut Line= 3
      2524875.01     13748324.98        2524575.       13748925.
      2524342.69     13750460.58
#Sta/Elev= 30
  4328.8  329.75  4431.8  325.92  4530.1  321.94  4540.4  322.61  4648.9  319.42
  4829.1  317.29  4857.1  318.76  4901.8  318.08  4946.5  319.19  4954.9  318.84
  4963.3  315.11  4968.9  315.36  4977.3   306.9  4983.7  306.67  4984.2  306.17
  4998.8  306.67  4999.6  307.82  5002.2  307.82  5009.8   313.6  5019.9  319.09
  5167.2   316.6  5252.5  315.25  5272.7  315.63  5299.2  317.85  5576.1  315.78
  5758.2  316.49  5788.5  315.15  6061.6  320.31  6237.5  322.12  6552.7  329.14
#Mann= 7 ,-1 , 0
  4328.8     .12       0  4431.8    .035       0  4540.4     .12       0
  4648.9      .1       0  4983.7     .05       0  4998.8      .1       0
  5167.2     .12       0
Bank Sta=4983.7,4998.8
XS Rating Curve= 0 ,0
Exp/Cntr=0.3,0.1

Type RM Length L Ch R = 1 ,22132   ,447,447,447
BEGIN DESCRIPTION:
VANHAM CREEK 30.0
END DESCRIPTION:
XS GIS Cut Line= 3
        2524225.     13748125.03        2524125.       13748825.
        2523325.       13750025.
#Sta/Elev= 30
  4289.3  326.16  4390.3  323.28  4718.9  318.08  4885.3  316.87  4905.5  315.96
  4999.4  318.05  5003.9  312.78  5009.9  311.69  5011.3  305.53  5011.8  305.03
  5026.6  305.53  5032.4  306.09  5039.9   311.2    5046  311.44    5055  317.57
  5249.9  315.61  5349.4  315.06  5400.5  313.34    5429  314.11  5436.6  315.66
  5861.7  314.04  5897.8  312.35  5905.3  310.42  5933.8  310.19  6028.5  314.22
  6070.5  314.74  6258.3  322.79  6322.9  323.89  6358.3  325.95  6438.6  327.22
#Mann= 6 ,-1 , 0
  4289.3     .07       0  4718.9      .1       0  5011.3     .05       0
  5026.6      .1       0  5249.9     .12       0  6358.3     .07       0
Bank Sta=5011.3,5026.6
XS Rating Curve= 0 ,0
Exp/Cntr=0.3,0.1

Type RM Length L Ch R = 1 ,21685   ,477,477,477
BEGIN DESCRIPTION:
VANHAM CREEK 29.0
END DESCRIPTION:
XS GIS Cut Line= 3
        2523825.     13747674.96        2523725.       13748875.
      2523225.02     13749874.97
#Sta/Elev= 30
  3796.2  337.94  3821.1  336.73  3966.8  329.13  4067.2  326.51  4087.2  324.93
  4237.8  321.76  4257.8  319.53    4308  317.78  4408.4  317.92  4638.1  314.39
  4682.7  313.73  4792.5  313.65  4980.3  316.75  4990.4  313.65  4997.9  306.36
  5003.2  306.36  5006.7  304.74  5007.2  304.24    5022  304.74  5031.1  312.77
  5036.7  311.97  5045.1  316.78  5173.8  314.96  5282.7  313.63  5321.8  311.94
  5344.2  314.96  5366.6  315.35  5671.2   310.1  5939.6  321.84  6118.4  326.57
#Mann= 8 ,-1 , 0
  3796.2    .035       0  3821.1     .07       0  4638.1     .12       0
  4682.7     .07       0  4792.5      .1       0  5006.7     .05       0
    5022      .1       0  5173.8     .12       0
Bank Sta=5006.7,5022
XS Rating Curve= 0 ,0
Exp/Cntr=0.3,0.1

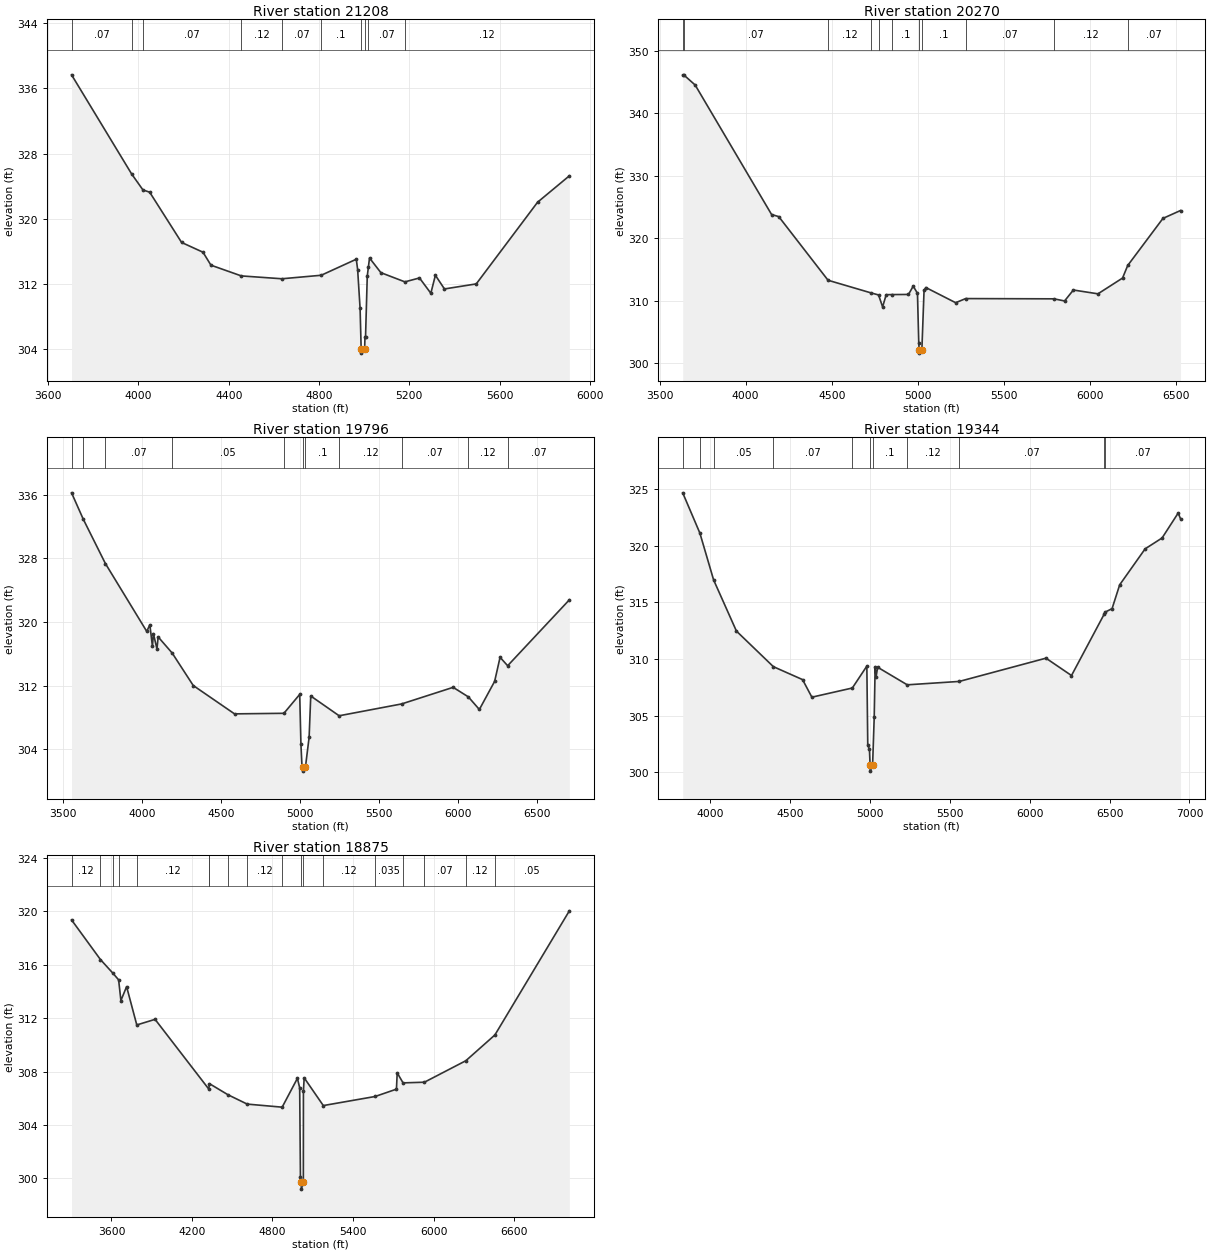
Type RM Length L Ch R = 1 ,21208   ,938,938,938
BEGIN DESCRIPTION:
VANHAM CREEK 28.0
END DESCRIPTION:
XS GIS Cut Line= 3
        2523775.       13747675.        2523275.       13748875.
        2523175.     13749774.97
#Sta/Elev= 30
  3703.6  337.66  3969.5   325.5  4019.8  323.53  4049.7  323.25  4191.1  317.08
  4285.9  315.88  4321.1  314.29  4455.8  312.97  4635.5  312.62  4809.6  313.05
  4965.1  315.02  4971.1  313.74  4981.9  308.99  4986.7  303.99  4987.2  303.49
    5002  303.99  5003.6  305.51  5006.1  305.51  5013.7  312.94  5018.6  314.03
  5023.7  315.17    5074  313.37  5180.5  312.24  5245.1  312.72  5295.4  310.84
  5315.5  313.05  5355.7  311.37  5496.6  311.99  5768.3  322.02  5909.1  325.26
#Mann= 10 ,-1 , 0
  3703.6     .07       0  3969.5     .12       0  4019.8     .07       0
  4455.8     .12       0  4635.5     .07       0  4809.6      .1       0
  4986.7     .05       0    5002      .1       0  5018.6     .07       0
  5180.5     .12       0
Bank Sta=4986.7,5002
XS Rating Curve= 0 ,0
Exp/Cntr=0.3,0.1

Type RM Length L Ch R = 1 ,20270   ,474,474,474
BEGIN DESCRIPTION:
VANHAM CREEK 27.0
END DESCRIPTION:
XS GIS Cut Line= 3
      2523825.02     13747424.99        2522725.       13748225.
        2523025.     13749725.02
#Sta/Elev= 30
  3634.6  346.08  3640.1  346.14  3706.9  344.51  4150.5  323.81  4192.2  323.47
  4478.3   313.3    4729  311.27  4771.5  310.95    4795  309.04  4815.9  310.99
  4847.3  311.01  4945.3  311.03  4972.7  312.36  4997.3  311.22    5005  303.21
  5007.5  302.15    5008  301.65  5022.9  302.15  5035.6  311.67  5045.8  312.14
  5219.1  309.71  5277.2  310.37  5789.5  310.33  5851.4  309.99  5902.4  311.74
  6045.2  311.13  6187.9  313.65  6217.9  315.66  6422.5  323.19  6524.5  324.45
#Mann= 11 ,-1 , 0
  3634.6    .035       0  3640.1     .07       0  4478.3     .12       0
    4729      .1       0  4771.5     .05       0  4847.3      .1       0
  5007.5     .05       0  5022.9      .1       0  5277.2     .07       0
  5789.5     .12       0  6217.9     .07       0
Bank Sta=5007.5,5022.9
XS Rating Curve= 0 ,0
Exp/Cntr=0.3,0.1

Type RM Length L Ch R = 1 ,19796   ,452,452,452
BEGIN DESCRIPTION:
VANHAM CREEK 26.0
END DESCRIPTION:
XS GIS Cut Line= 3
      2523524.96     13747225.02        2522325.       13748025.
      2522774.99     13749674.96
#Sta/Elev= 30
  3552.7  336.26  3626.8  332.94  3766.9  327.36  4028.9  318.81  4048.4  319.65
  4064.9  316.95    4071  318.53  4093.5   316.6    4101  318.12  4189.8  316.09
  4323.3     312  4584.7  308.43  4897.4   308.5  4997.5  310.88  5005.2  304.58
  5012.2  301.72  5018.2  301.72  5018.7  301.22  5033.7  301.72  5057.1  305.48
  5067.4  310.68  5247.2  308.19  5642.9  309.68  5969.2  311.77  6065.3  310.57
  6135.1  308.98  6231.8  312.52  6266.3  315.55  6314.3  314.49  6705.1  322.79
#Mann= 11 ,-1 , 0
  3552.7     .07       0  3626.8     .12       0  3766.9     .07       0
  4189.8     .05       0  4897.4      .1       0  5018.2     .05       0
  5033.7      .1       0  5247.2     .12       0  5642.9     .07       0
  6065.3     .12       0  6314.3     .07       0
Bank Sta=5018.2,5033.7
XS Rating Curve= 0 ,0
Exp/Cntr=0.3,0.1

Type RM Length L Ch R = 1 ,19344   ,469,469,469
BEGIN DESCRIPTION:
VANHAM CREEK 25.0
END DESCRIPTION:
XS GIS Cut Line= 3
      2522924.99     13747275.01        2521925.       13747875.
      2522675.01     13749675.02
#Sta/Elev= 30
  3827.9  324.66  3935.3  321.11  4021.3  316.98  4164.1  312.47  4395.5  309.33
  4578.1  308.19  4636.4  306.64  4889.7  307.45  4980.5  309.38  4986.3  302.41
  4996.8  302.03    5001  300.62  5001.5  300.12  5016.5  300.62  5026.6  304.86
  5032.5  309.33    5038  308.41  5048.2  309.28  5233.4  307.73  5559.4  308.03
  6101.8  310.08  6261.6  308.55  6465.4  313.94  6472.1  314.14  6515.6  314.45
  6563.3  316.55  6722.5  319.72  6828.7  320.68  6929.5  322.88  6944.1  322.37
#Mann= 11 ,-1 , 0
  3827.9     .05       0  3935.3     .07       0  4021.3     .05       0
  4395.5     .07       0  4889.7      .1       0    5001     .05       0
  5016.5      .1       0  5233.4     .12       0  5559.4     .07       0
  6465.4     .12       0  6472.1     .07       0
Bank Sta=5001,5016.5
XS Rating Curve= 0 ,0
Exp/Cntr=0.3,0.1

Type RM Length L Ch R = 1 ,18875   ,482,482,482
BEGIN DESCRIPTION:
VANHAM CREEK 24.0
END DESCRIPTION:
XS GIS Cut Line= 3
      2522675.02     13746624.98        2521475.       13747825.
      2522374.98     13749624.96
#Sta/Elev= 30
  3302.9  319.36  3518.2  316.39  3608.9  315.39  3653.6  314.87  3670.6  313.32
  3713.1  314.36    3789  311.49  3925.2  311.91  4325.2  306.69  4330.6  307.09
  4468.5  306.26  4611.8  305.56  4872.3  305.33  4985.8  307.49  5002.8  306.78
  5008.4   300.1  5014.6  299.69  5015.1  299.19  5030.1  299.69  5030.7  306.52
  5036.3  307.53  5178.8  305.45  5564.7  306.13  5723.9  306.68  5729.5   307.9
  5773.2  307.15  5932.3   307.2    6241  308.81  6457.5  310.74  7012.4  320.04
#Mann= 18 ,-1 , 0
  3302.9     .12       0  3518.2     .07       0  3608.9     .12       0
  3653.6    .035       0    3789     .12       0  4325.2     .07       0
  4330.6     .12       0  4468.5    .035       0  4611.8     .12       0
  4872.3      .1       0  5014.6     .05       0  5030.1      .1       0
  5178.8     .12       0  5564.7    .035       0  5773.2     .12       0
  5932.3     .07       0    6241     .12       0  6457.5     .05       0
Bank Sta=5014.6,5030.1
XS Rating Curve= 0 ,0
Exp/Cntr=0.3,0.1