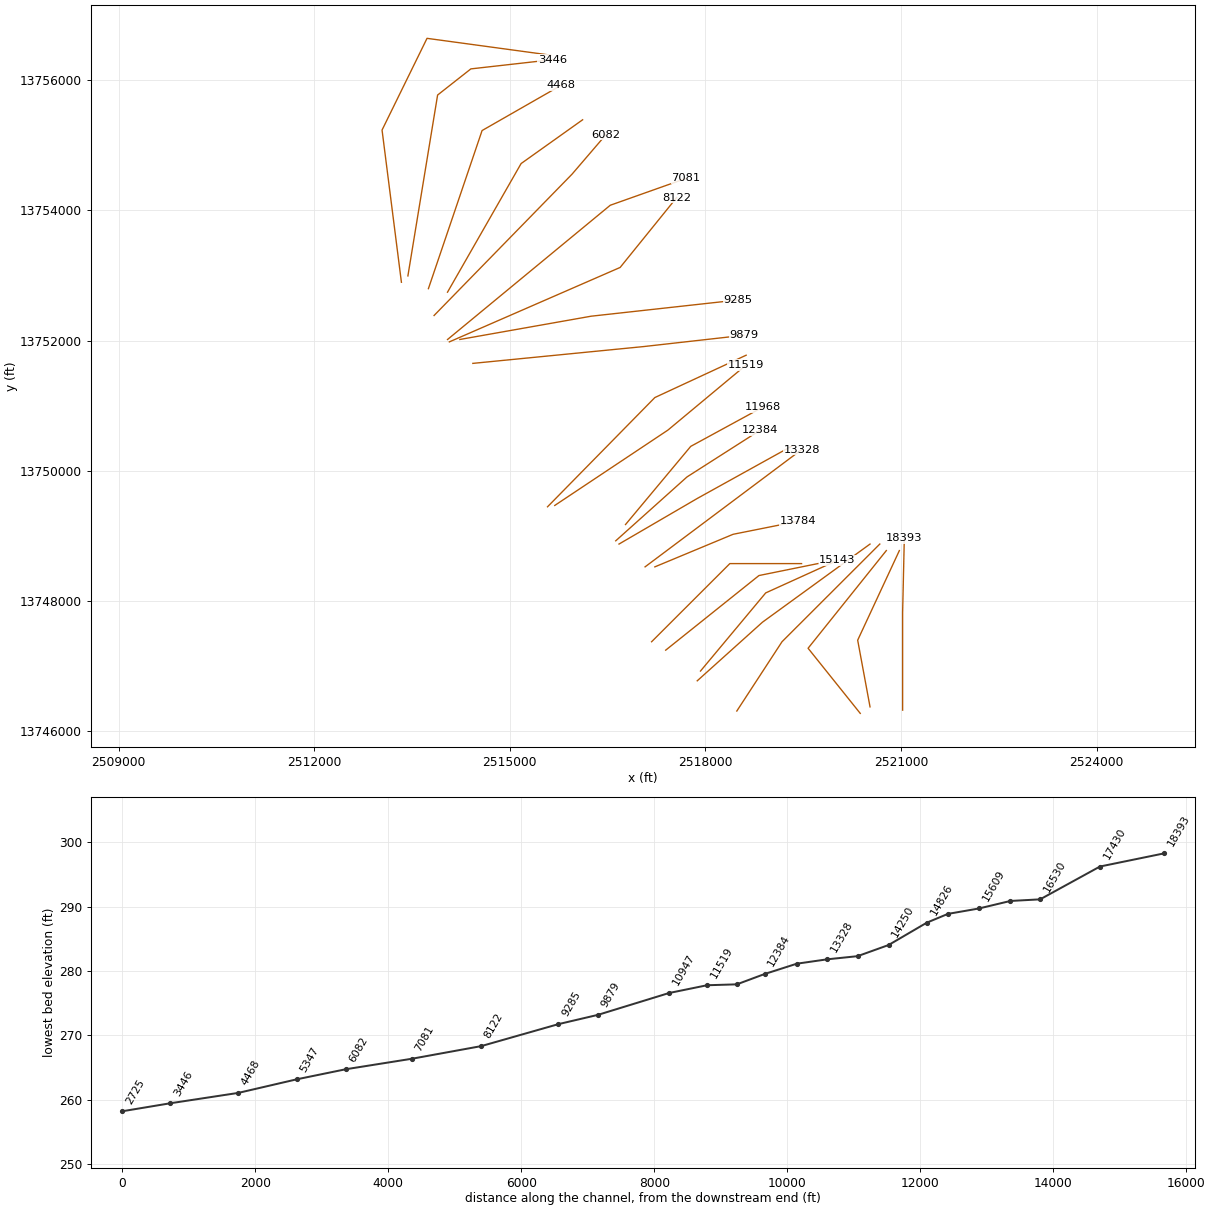
HEC-RAS study VANHAM CREEK.prj: VANHAM CREEK Base Level Engineering

--- VANHAM CREEK.g01 (geometry) --- (continued)

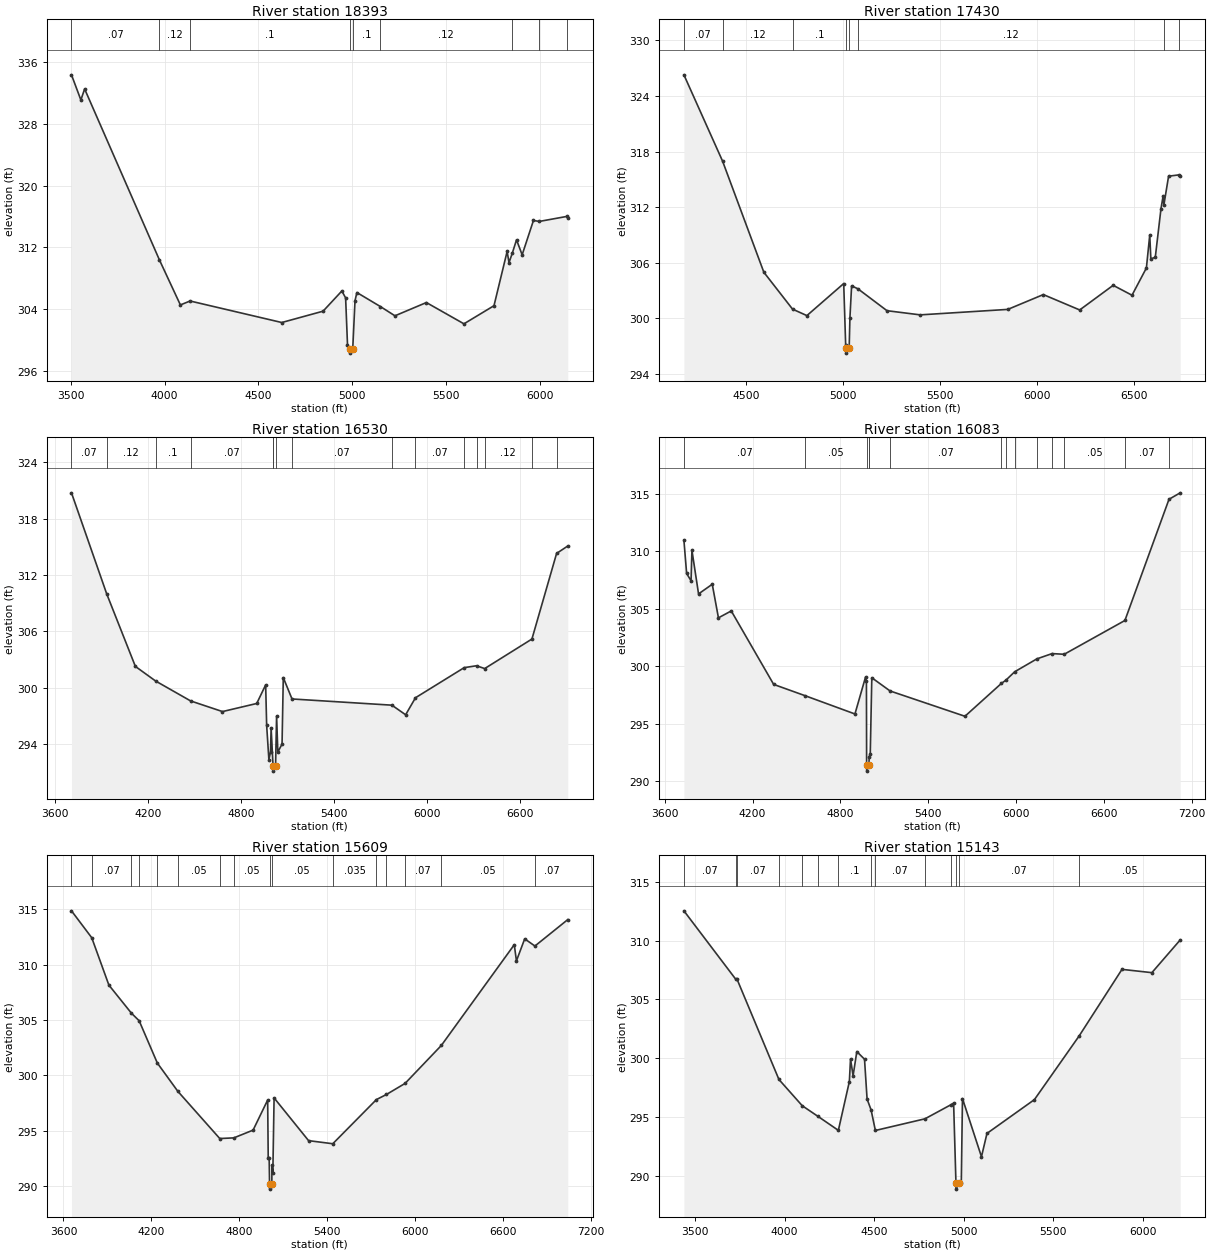
Type RM Length L Ch R = 1 ,18393   ,963,963,963
BEGIN DESCRIPTION:
VANHAM CREEK 23.0
END DESCRIPTION:
XS GIS Cut Line= 3
        2521025.     13746324.98        2521025.       13747825.
      2521050.94     13748967.99
#Sta/Elev= 30
  3504.5  334.38  3554.5  331.12  3574.5  332.55  3973.2  310.36  4084.5  304.54
  4136.2  305.05  4624.5  302.26  4844.5  303.73  4944.5  306.35  4964.5  305.45
  4974.5   299.4  4986.8  298.79  4987.3  298.29  5002.3  298.79  5014.5  305.09
  5024.5  306.15  5149.7  304.33  5227.2  303.13  5394.6  304.85  5594.7  302.09
  5754.7  304.44  5824.7  311.48  5834.7  310.02  5851.6  311.21  5874.7  312.98
  5904.7  311.04  5964.8  315.49  5996.3  315.37  6140.9  316.01  6147.8  315.86
#Mann= 9 ,-1 , 0
  3504.5     .07       0  3973.2     .12       0  4136.2      .1       0
  4986.8     .05       0  5002.3      .1       0  5149.7     .12       0
  5851.6     .07       0  5996.3     .05       0  6140.9     .07       0
Bank Sta=4986.8,5002.3
XS Rating Curve= 0 ,0
Exp/Cntr=0.3,0.1

Type RM Length L Ch R = 1 ,17430   ,900,900,900
BEGIN DESCRIPTION:
VANHAM CREEK 22.0
END DESCRIPTION:
XS GIS Cut Line= 3
      2520525.01     13746374.97      2520335.67     13747398.59
      2520974.99     13748774.97
#Sta/Elev= 30
  4181.5  326.29  4380.9  316.97  4593.6  304.98  4741.5     301  4815.5   300.3
  5005.3  303.76  5015.4  297.13  5017.9  296.75  5018.4  296.25  5033.4  296.75
  5037.3  300.05    5046  303.51  5078.8  303.19  5228.4  300.83  5399.7  300.38
  5851.2  300.97  6034.4  302.57  6221.9  300.91  6394.4  303.57  6491.5   302.5
  6565.7  305.44    6583     309  6588.6  306.43  6611.5  306.59  6640.9  311.84
  6651.7  313.19  6655.9  312.25  6680.1  315.35  6733.5  315.49  6740.1  315.39
#Mann= 8 ,-1 , 0
  4181.5     .07       0  4380.9     .12       0  4741.5      .1       0
  5017.9     .05       0  5033.4      .1       0  5078.8     .12       0
  6655.9     .07       0  6733.5     .05       0
Bank Sta=5017.9,5033.4
XS Rating Curve= 0 ,0
Exp/Cntr=0.3,0.1

Type RM Length L Ch R = 1 ,16530   ,447,447,447
BEGIN DESCRIPTION:
VANHAM CREEK 21.0
END DESCRIPTION:
XS GIS Cut Line= 3
      2520375.01     13746274.98        2519575.       13747275.
      2520775.01     13748775.01
#Sta/Elev= 30
  3707.7  320.73  3934.9  309.99  4119.9  302.28  4250.2  300.73  4476.4  298.61
  4681.8  297.48  4902.7  298.34  4960.3  300.32  4966.7  296.01  4981.1  292.37
  4991.5  293.18  4995.5  295.72  5007.7  291.79  5008.6  291.65  5009.1  291.15
  5024.1  291.65  5030.8     297  5038.8  293.17    5066  294.03    5074  301.09
  5130.3  298.82  5774.6  298.16  5863.2  297.14  5926.8  298.95    6241  302.15
  6320.5  302.35  6373.1  302.05  6677.9  305.19    6837  314.29  6909.3  315.08
#Mann= 15 ,-1 , 0
  3707.7     .07       0  3934.9     .12       0  4250.2      .1       0
  4476.4     .07       0  5007.7     .12       0  5008.6     .05       0
  5024.1     .12       0  5130.3     .07       0  5774.6    .035       0
  5926.8     .07       0    6241     .12       0  6320.5     .05       0
  6373.1     .12       0  6677.9     .07       0    6837     .05       0
Bank Sta=5008.6,5024.1
XS Rating Curve= 0 ,0
Exp/Cntr=0.3,0.1

Type RM Length L Ch R = 1 ,16083   ,474,474,474
BEGIN DESCRIPTION:
VANHAM CREEK 20.0
END DESCRIPTION:
XS GIS Cut Line= 3
      2518482.02     13746311.11        2519175.       13747375.
        2520675.       13748875.
#Sta/Elev= 30
  3730.7  310.99  3749.3  308.09  3779.5  307.45  3785.5   310.1  3830.8  306.31
  3924.4  307.15  3966.6  304.23  4054.2  304.83    4344  298.44  4560.7  297.45
  4899.3  295.87  4971.7  299.08  4977.7  298.71  4979.1   291.4  4979.6   290.9
  4994.6   291.4  4996.8  292.17  5003.9  292.38  5014.5  299.02  5139.4  297.87
  5650.9  295.67  5900.1  298.53  5930.7  298.81  5990.7  299.54  6142.1  300.66
  6246.1  301.12    6329  301.06  6743.8     304    7045  314.54  7121.7   315.1
#Mann= 14 ,-1 , 0
  3730.7     .07       0  4560.7     .05       0  4979.1     .05       0
  4994.6     .05       0  4996.8     .12       0  5139.4     .07       0
  5900.1     .05       0  5930.7     .07       0  5990.7     .05       0
  6142.1    .035       0  6246.1     .07       0    6329     .05       0
  6743.8     .07       0    7045     .05       0
Bank Sta=4979.1,4994.6
XS Rating Curve= 0 ,0
Exp/Cntr=0.3,0.1

Type RM Length L Ch R = 1 ,15609   ,466,466,466
BEGIN DESCRIPTION:
VANHAM CREEK 19.0
END DESCRIPTION:
XS GIS Cut Line= 3
      2517875.03     13746775.03        2518875.       13747675.
      2520524.97     13748874.98
#Sta/Elev= 30
  3654.8  314.87    3793  312.44    3910  308.16  4063.9  305.62  4116.4  304.94
  4240.4  301.12    4380  298.57  4666.3   294.3  4762.3  294.36  4893.6  295.06
    4993  297.78  4996.8  292.57  5003.2  292.57  5005.9  290.23  5006.4  289.73
  5021.4  290.23  5022.1  291.88  5028.3  291.17  5036.8  297.97  5272.1  294.11
  5437.2  293.83  5734.9  297.82  5803.3  298.28  5930.3  299.28  6177.7  302.71
  6675.2  311.81  6689.9  310.35  6746.3  312.34    6816  311.69  7040.3  314.08
#Mann= 16 ,-1 , 0
  3654.8     .12       0    3793     .07       0  4063.9     .05       0
  4116.4     .07       0  4240.4    .035       0    4380     .05       0
  4666.3     .07       0  4762.3     .05       0  5005.9     .05       0
  5021.4     .05       0  5437.2    .035       0  5734.9     .07       0
  5803.3     .05       0  5930.3     .07       0  6177.7     .05       0
    6816     .07       0
Bank Sta=5005.9,5021.4
XS Rating Curve= 0 ,0
Exp/Cntr=0.3,0.1

Type RM Length L Ch R = 1 ,15143   ,317,317,317
BEGIN DESCRIPTION:
VANHAM CREEK 18.0
END DESCRIPTION:
XS GIS Cut Line= 3
      2517925.03     13746925.03        2518925.       13748125.
      2520024.99       13748625.
#Sta/Elev= 30
  3437.5  312.52  3725.9  306.73  3733.6  306.73  3967.9   298.2  4098.1  295.97
  4184.6  295.08  4299.6  293.88    4361  298.02  4367.5  299.94  4381.8  298.52
  4402.7  300.57  4445.6  299.92  4459.9  296.54  4482.2  295.62  4506.2  293.87
    4783  294.86  4928.5  296.06  4942.9  296.19    4956  289.39  4956.5  288.89
  4971.5  289.39  4985.8   289.4  4992.3  296.58  5098.4  291.64  5129.1  293.62
  5393.9  296.49  5643.3  301.89  5882.7  307.55  6049.6  307.27  6207.8  310.05
#Mann= 14 ,-1 , 0
  3437.5     .07       0  3725.9     .05       0  3733.6     .07       0
  3967.9    .035       0  4098.1     .07       0  4184.6     .05       0
  4299.6      .1       0  4482.2     .05       0  4506.2     .07       0
    4783     .05       0  4928.5     .07       0    4956     .05       0
  4971.5     .07       0  5643.3     .05       0
Bank Sta=4956,4971.5
XS Rating Curve= 0 ,0
Exp/Cntr=0.3,0.1

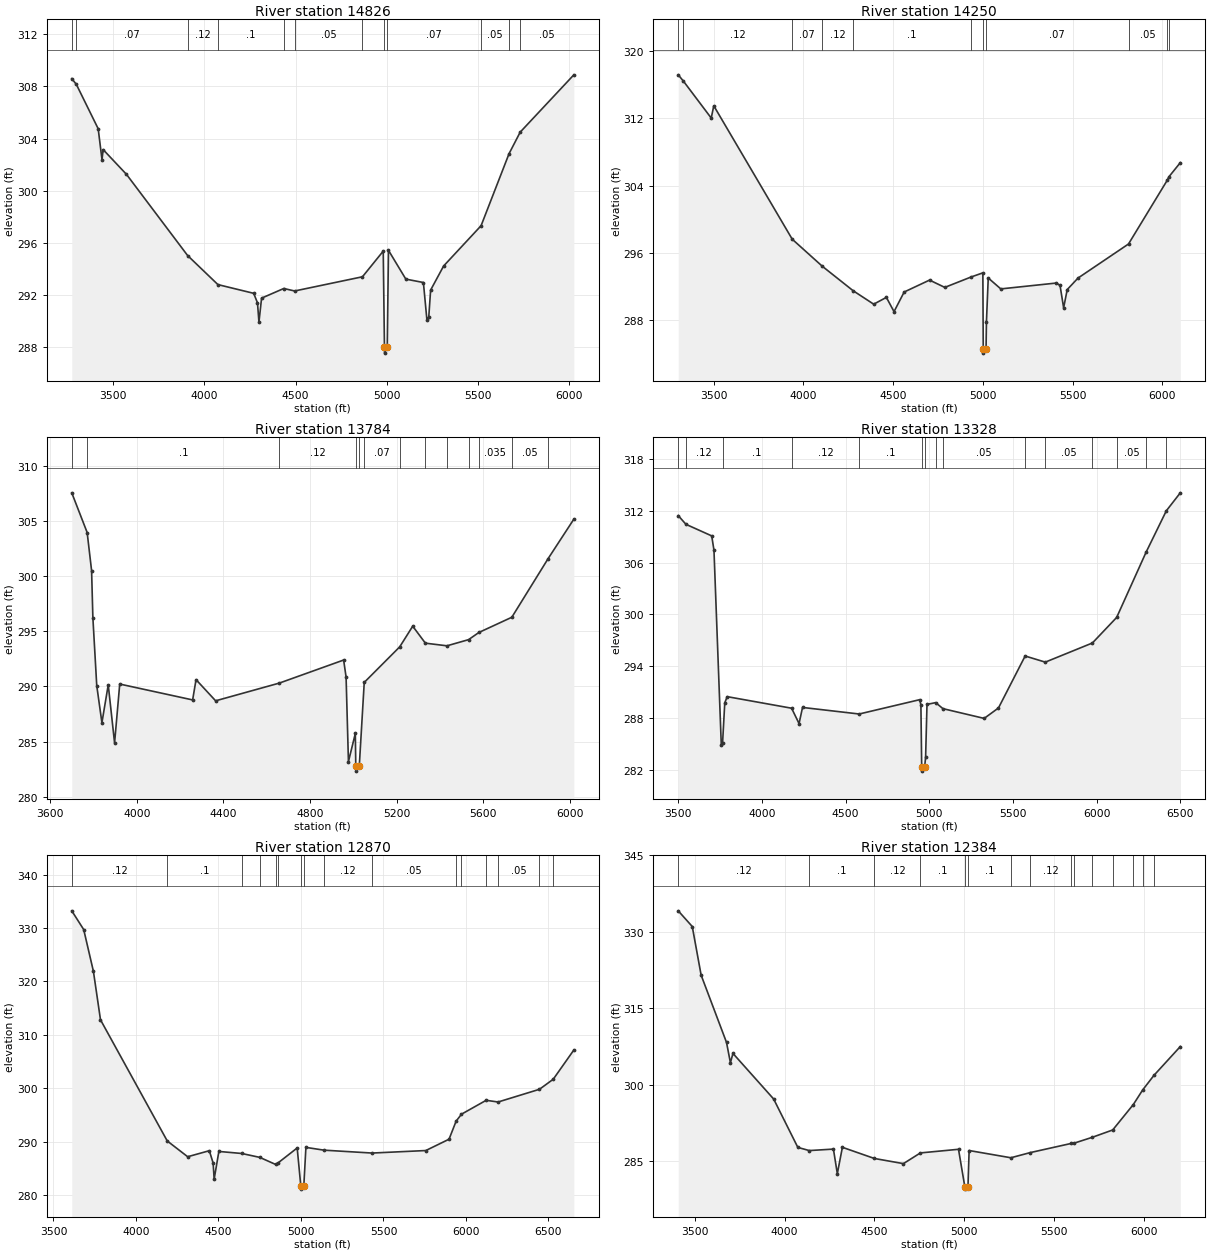
Type RM Length L Ch R = 1 ,14826   ,576,576,576
BEGIN DESCRIPTION:
VANHAM CREEK 17.0
END DESCRIPTION:
XS GIS Cut Line= 3
      2517391.26     13747245.84      2518821.78     13748391.65
      2519725.03     13748575.01
#Sta/Elev= 30
  3272.1   308.6  3297.1  308.16  3417.1  304.75  3437.9  302.38  3444.3  303.15
  3572.3  301.25  3907.7  295.02  4073.9  292.79  4270.2  292.12    4291  291.39
    4299  289.91  4313.4  291.75  4435.2  292.49    4495   292.3  4866.9  293.39
  4980.9  295.36  4987.5  288.03    4988  287.53    5003  288.03  5009.6  295.42
  5104.9  293.21  5201.2  292.95  5220.5  290.08  5230.7  290.31  5240.9  292.37
  5312.3  294.22  5517.7  297.31  5671.2  302.84  5732.2  304.49  6026.6  308.89
#Mann= 12 ,-1 , 0
  3272.1     .12       0  3297.1     .07       0  3907.7     .12       0
  4073.9      .1       0  4435.2     .07       0    4495     .05       0
  4866.9     .07       0  4987.5     .05       0    5003     .07       0
  5517.7     .05       0  5671.2     .07       0  5732.2     .05       0
Bank Sta=4987.5,5003
XS Rating Curve= 0 ,0
Exp/Cntr=0.3,0.1

Type RM Length L Ch R = 1 ,14250   ,466,466,466
BEGIN DESCRIPTION:
VANHAM CREEK 16.0
END DESCRIPTION:
XS GIS Cut Line= 3
      2517175.01     13747375.01        2518375.       13748575.
      2519474.95       13748575.
#Sta/Elev= 30
    3303   317.2  3331.8  316.45  3486.8  312.05    3501  313.51    3938  297.62
    4106  294.39  4276.9  291.49  4391.9  289.88  4462.6  290.69  4505.1  288.99
  4561.6  291.33  4703.1  292.75  4787.9  291.88  4935.8  293.13    5000  293.61
  5002.2  284.55  5002.7  284.05  5017.8  284.55    5020   287.8    5030     293
    5100   291.7    5410   292.4    5430  292.11    5450  289.45    5470  291.62
    5530  292.99  5811.4  297.05  6027.2  304.64  6036.7  305.06    6100  306.74
#Mann= 11 ,-1 , 0
    3303     .07       0  3331.8     .12       0    3938     .07       0
    4106     .12       0  4276.9      .1       0  4935.8     .07       0
  5002.2     .05       0  5017.8     .07       0  5811.4     .05       0
  6027.2     .07       0  6036.7     .05       0
Bank Sta=5002.2,5017.8
XS Rating Curve= 0 ,0
Exp/Cntr=0.3,0.1

Type RM Length L Ch R = 1 ,13784   ,456,456,456
BEGIN DESCRIPTION:
VANHAM CREEK 15.0
END DESCRIPTION:
XS GIS Cut Line= 3
      2517224.96     13748524.98        2518425.       13749025.
      2519425.05     13749225.01
#Sta/Elev= 30
  3699.5  307.57  3770.6  303.97  3791.1  300.51    3797  296.25  3814.9  290.08
  3838.8  286.71    3868  290.15  3897.3  284.88  3921.1  290.22    4258  288.78
  4273.7  290.62  4364.2   288.7    4659  290.31  4955.7   292.4    4967  290.86
  4977.9  283.18  5009.7  285.74  5011.8  282.82  5012.3  282.32  5028.1  282.82
  5050.9  290.37    5215   293.6  5274.9  295.47  5333.4  293.93  5433.2  293.69
  5533.1  294.25  5580.6   294.9  5732.8  296.28  5900.8  301.61  6019.4  305.18
#Mann= 13 ,-1 , 0
  3699.5     .07       0  3770.6      .1       0    4659     .12       0
  5011.8     .05       0  5028.1     .12       0  5050.9     .07       0
    5215     .12       0  5333.4     .07       0  5433.2    .035       0
  5533.1     .05       0  5580.6    .035       0  5732.8     .05       0
  5900.8     .07       0
Bank Sta=5011.8,5028.1
XS Rating Curve= 0 ,0
Exp/Cntr=0.3,0.1

Type RM Length L Ch R = 1 ,13328   ,458,458,458
BEGIN DESCRIPTION:
VANHAM CREEK 14.0
END DESCRIPTION:
XS GIS Cut Line= 3
      2517075.02     13748525.01        2518275.       13749425.
      2519475.02     13750325.01
#Sta/Elev= 30
    3500  311.44  3546.2  310.43    3700  309.09  3713.5  307.44  3757.3  284.85
  3764.8  285.06  3778.1  289.75  3792.7  290.46  4177.4  289.12  4221.9  287.34
  4242.7  289.21  4581.2  288.45  4942.7  290.11    4950  289.51  4954.7  282.33
  4955.2  281.83  4972.4  282.33  4978.1  283.44  4986.4  289.56  5038.2  289.77
  5081.7  289.07  5328.1  287.94  5413.5  289.15  5572.8  295.17  5693.3  294.46
  5974.8  296.68  6119.7  299.64    6296  307.22  6416.5     312    6500  314.08
#Mann= 15 ,-1 , 0
    3500     .07       0  3546.2     .12       0  3764.8      .1       0
  4177.4     .12       0  4581.2      .1       0  4954.7     .05       0
  4972.4      .1       0  5038.2     .12       0  5081.7     .05       0
  5572.8    .035       0  5693.3     .05       0  5974.8     .07       0
  6119.7     .05       0    6296    .035       0  6416.5     .05       0
Bank Sta=4954.7,4972.4
XS Rating Curve= 0 ,0
Exp/Cntr=0.3,0.1

Type RM Length L Ch R = 1 ,12870   ,486,486,486
BEGIN DESCRIPTION:
VANHAM CREEK 13.0
END DESCRIPTION:
XS GIS Cut Line= 3
      2516674.97     13748874.98        2517875.       13749575.
      2519320.87     13750377.25
#Sta/Elev= 30
    3611  333.22  3683.4  329.71  3742.1  321.91  3785.1  312.83  4189.7  290.16
  4313.5  287.21  4444.6  288.34  4467.7  286.04  4473.9  283.02  4502.5   288.2
  4641.1  287.82  4750.4  287.09  4846.3  285.77  4862.6  286.09  4977.1  288.85
  4999.4  281.65  4999.9  281.15  5017.1  281.65    5030  288.96  5139.6  288.44
  5431.3   287.9  5756.7  288.37  5897.4  290.49  5940.2  293.86  5972.8  295.17
  6122.5  297.77  6194.6  297.45  6445.4  299.83  6528.9  301.71  6653.8  307.18
#Mann= 16 ,-1 , 0
    3611     .12       0  4189.7      .1       0  4641.1     .07       0
  4750.4     .12       0  4846.3     .07       0  4862.6      .1       0
  4999.4     .05       0  5017.1      .1       0  5139.6     .12       0
  5431.3     .05       0  5940.2    .035       0  5972.8     .05       0
  6122.5     .07       0  6194.6     .05       0  6445.4     .07       0
  6528.9     .05       0
Bank Sta=4999.4,5017.1
XS Rating Curve= 0 ,0
Exp/Cntr=0.3,0.1

Type RM Length L Ch R = 1 ,12384   ,416,416,416
BEGIN DESCRIPTION:
VANHAM CREEK 12.0
END DESCRIPTION:
XS GIS Cut Line= 3
      2516624.99     13748924.99      2517717.61     13749905.54
      2518835.02      13750620.4
#Sta/Elev= 30
    3408  334.11  3486.1  331.03  3535.5  321.49  3676.7  308.31  3698.4  304.33
  3712.6  306.15  3939.1  297.21  4073.7  287.72  4137.5   287.1  4271.8  287.39
  4293.5  282.57  4321.7  287.74  4499.8  285.55  4661.3  284.54  4755.9  286.64
    4968  287.35    5003  280.04  5003.5  279.54  5020.7  280.04  5027.1  287.11
  5259.5  285.69    5367   286.7  5596.7  288.51  5611.3  288.55  5711.5  289.69
  5826.3  291.14  5941.1  296.13  5993.4     299  6055.9  301.85  6202.6   307.5
#Mann= 15 ,-1 , 0
    3408     .12       0  4137.5      .1       0  4499.8     .12       0
  4755.9      .1       0    5003     .05       0  5020.7      .1       0
  5259.5     .15       0    5367     .12       0  5596.7     .05       0
  5611.3     .07       0  5711.5     .05       0  5826.3    .035       0
  5941.1     .07       0  5993.4    .035       0  6055.9     .07       0
Bank Sta=5003,5020.7
XS Rating Curve= 0 ,0
Exp/Cntr=0.3,0.1

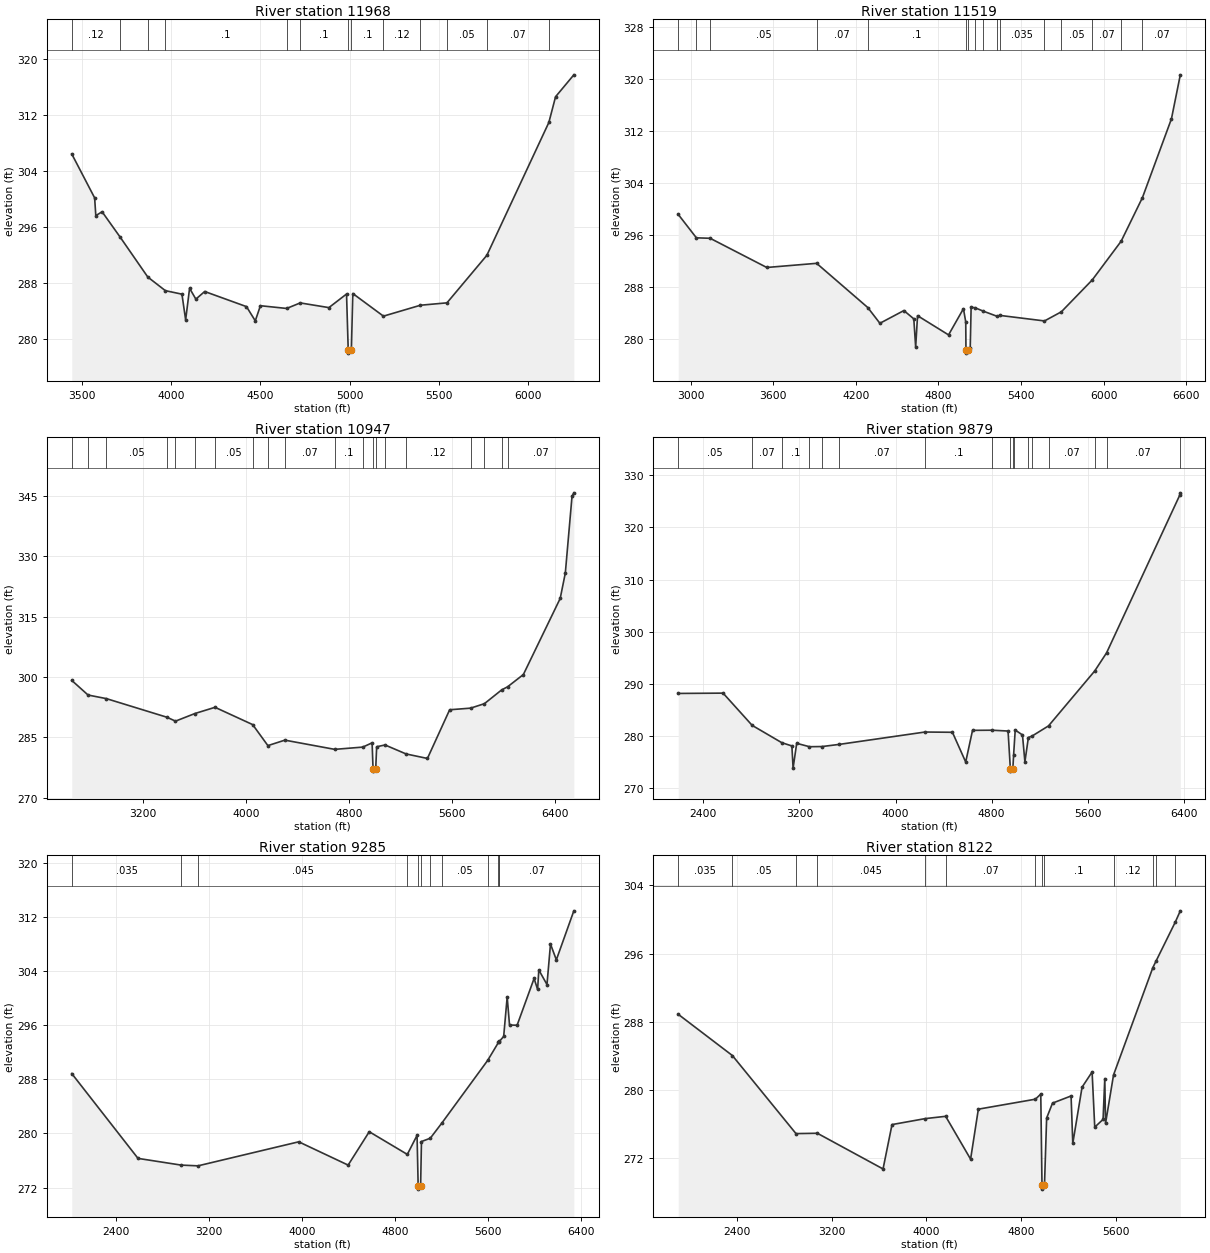
Type RM Length L Ch R = 1 ,11968   ,449,449,449
BEGIN DESCRIPTION:
VANHAM CREEK 11.0
END DESCRIPTION:
XS GIS Cut Line= 3
      2516774.98     13749174.98        2517775.       13750375.
      2518875.02     13750975.01
#Sta/Elev= 30
  3442.4  306.38  3570.6  300.11  3577.2  297.57  3612.3  298.13  3714.4  294.48
  3868.8   288.8  3967.2  286.86  4060.1  286.36  4080.9  282.69    4103   287.2
  4138.2  285.65  4187.7  286.74    4422  284.58  4471.4  282.55  4500.1  284.71
  4647.3  284.32  4723.3  285.11  4884.1  284.44    4983  286.38  4992.4  278.44
  4992.9  277.94  5010.1  278.44  5018.2  286.45  5189.9  283.22  5397.6  284.78
  5546.1  285.12  5769.8  291.91  6117.4  310.88    6155  314.55  6257.5  317.68
#Mann= 13 ,-1 , 0
  3442.4     .12       0  3714.4     .07       0  3868.8     .12       0
  3967.2      .1       0  4647.3     .07       0  4723.3      .1       0
  4992.4     .05       0  5010.1      .1       0  5189.9     .12       0
  5397.6     .07       0  5546.1     .05       0  5769.8     .07       0
  6117.4    .035       0
Bank Sta=4992.4,5010.1
XS Rating Curve= 0 ,0
Exp/Cntr=0.3,0.1

Type RM Length L Ch R = 1 ,11519   ,572,572,572
BEGIN DESCRIPTION:
VANHAM CREEK 10.0
END DESCRIPTION:
XS GIS Cut Line= 3
      2515689.86     13749468.05        2517425.       13750625.
      2518624.98     13751624.98
#Sta/Elev= 30
  2910.1  299.18  3041.9  295.57  3141.9   295.5  3553.3     291  3915.4  291.64
  4286.9  284.83  4375.1   282.4  4549.4  284.36  4621.5  283.08    4635  278.73
  4648.6  283.57  4873.9  280.61  4982.1  284.65  4998.8   282.6  5000.4   278.3
  5000.9   277.8  5018.1   278.3  5031.4  278.64  5037.9  284.87    5068  284.78
  5126.1  284.27  5227.2  283.47  5244.4  283.62  5570.9  282.76  5693.5  284.17
  5918.3  289.09  6127.9  295.05  6282.7  301.78  6493.2  313.91  6557.6  320.69
#Mann= 16 ,-1 , 0
  2910.1     .07       0  3041.9    .035       0  3141.9     .05       0
  3915.4     .07       0  4286.9      .1       0  5000.4     .05       0
  5018.1      .1       0    5068     .15       0  5126.1    .035       0
  5227.2     .15       0  5244.4    .035       0  5570.9     .07       0
  5693.5     .05       0  5918.3     .07       0  6127.9     .05       0
  6282.7     .07       0
Bank Sta=5000.4,5018.1
XS Rating Curve= 0 ,0
Exp/Cntr=0.3,0.1

Type RM Length L Ch R = 1 ,10947   ,1068,1068,1068
BEGIN DESCRIPTION:
VANHAM CREEK 9.0
END DESCRIPTION:
XS GIS Cut Line= 3
      2515578.71     13749447.19        2517225.       13751125.
      2518624.97     13751774.99
#Sta/Elev= 30
  2649.4  299.13  2775.8   295.5  2917.7  294.61  3387.7  289.98  3453.9  289.01
  3604.9  290.91  3760.5  292.45  4052.4  288.15  4170.5  282.93    4302  284.29
  4688.6     282  4906.1  282.56  4978.8  283.62  4986.2  277.09  4986.7  276.59
  5006.7  277.09  5014.2  282.65  5079.3  283.09  5242.3  280.86  5407.9  279.74
  5580.3  291.84  5742.6  292.24  5849.7  293.35  5983.4  296.77  6029.8  297.55
  6151.9  300.59  6437.7  319.51  6477.4  325.82  6529.3  344.87  6543.5  345.75
#Mann= 20 ,-1 , 0
  2649.4     .07       0  2775.8    .035       0  2917.7     .05       0
  3387.7    .035       0  3453.9     .05       0  3604.9    .035       0
  3760.5     .05       0  4052.4     .05       0  4170.5      .1       0
    4302     .07       0  4688.6      .1       0  4906.1     .12       0
  4986.2     .05       0  5006.7      .1       0  5079.3    .035       0
  5242.3     .12       0  5742.6     .07       0  5849.7     .07       0
  5983.4     .05       0  6029.8     .07       0
Bank Sta=4986.2,5006.7
XS Rating Curve= 0 ,0
Exp/Cntr=0.3,0.1

Type RM Length L Ch R = 1 ,9879    ,594,594,594
BEGIN DESCRIPTION:
VANHAM CREEK 8.0
END DESCRIPTION:
XS GIS Cut Line= 3
      2514433.54     13751649.59      2517050.51     13751907.49
      2518590.61     13752081.02
#Sta/Elev= 30
  2191.4  288.12  2564.7  288.18  2806.7  281.99  3053.6  278.66  3137.4  278.04
  3147.5  273.79  3177.6  278.54  3283.7  277.89  3388.3  277.92  3533.4  278.34
  4244.9  280.71  4473.9  280.66  4584.4  274.95  4641.2  281.03  4802.5  281.06
    4937   280.9    4956   273.7  4956.5   273.2    4977   273.7  4983.4  276.38
  4996.6  281.09    5057  280.15  5077.2  274.98  5106.1  279.65  5137.7  279.95
  5273.9  281.89  5658.5  292.44  5757.2  295.92  6368.2   326.3  6370.9  326.65
#Mann= 17 ,-1 , 0
  2191.4     .05       0  2806.7     .07       0  3053.6      .1       0
  3283.7     .07       0  3388.3     .05       0  3533.4     .07       0
  4244.9      .1       0  4802.5     .12       0    4956     .05       0
    4977     .12       0  4983.4      .1       0  5106.1     .12       0
  5137.7      .1       0  5273.9     .07       0  5658.5    .035       0
  5757.2     .07       0  6368.2    .035       0
Bank Sta=4956,4977
XS Rating Curve= 0 ,0
Exp/Cntr=0.3,0.1

Type RM Length L Ch R = 1 ,9285    ,1163,1163,1163
BEGIN DESCRIPTION:
VANHAM CREEK 7.0
END DESCRIPTION:
XS GIS Cut Line= 3
       2514234.4     13752016.79      2516247.56     13752374.07
      2518504.48     13752623.63
#Sta/Elev= 30
  2022.6  288.83    2592   276.3  2962.5  275.31  3107.6   275.2  3973.2  278.75
  4397.9  275.31  4579.4  280.24  4906.6  276.89  4990.3   279.7  4999.8  272.26
  5000.3  271.76  5020.9  272.26  5028.2  278.79  5104.1  279.28    5206  281.58
  5597.9  290.79  5690.2  293.44  5696.6  293.53  5698.4   293.6  5734.8  294.31
  5764.9  300.15  5785.1     296  5850.2  295.97  5996.3  302.88  6026.5  301.25
  6036.7  304.14    6107  301.98  6137.2  307.96  6187.5  305.63  6337.9  312.87
#Mann= 12 ,-1 , 0
  2022.6    .035       0  2962.5     .12       0  3107.6    .045       0
  4906.6     .07       0  4999.8     .05       0  5020.9     .07       0
  5104.1     .07       0    5206     .05       0  5597.9    .035       0
  5690.2     .05       0  5696.6    .035       0  5698.4     .07       0
Bank Sta=4999.8,5020.9
XS Rating Curve= 0 ,0
Exp/Cntr=0.3,0.1

Type RM Length L Ch R = 1 ,8122    ,1041,1041,1041
BEGIN DESCRIPTION:
VANHAM CREEK 6.0
END DESCRIPTION:
XS GIS Cut Line= 3
      2514072.56     13751979.44      2516692.44     13753122.77
      2517560.24     13754196.67
#Sta/Elev= 30
  1904.2  288.87  2361.1  284.03  2898.3  274.86  3078.8   274.9  3633.5  270.71
  3709.2  275.92  3989.3  276.62    4162  276.89  4372.7  271.86  4438.2  277.73
  4919.8   278.9  4965.2   279.5  4975.5  268.84    4976  268.34  4996.6  268.84
  5014.8  276.69  5064.4  278.44  5221.1  279.28  5235.5  273.71  5313.8  280.31
  5398.6   282.1  5420.9  275.62  5491.3  276.53  5505.7  281.32  5512.1  276.06
  5579.6  281.75  5911.7  294.36  5938.5  295.12  6101.4  299.71  6143.4  301.02
#Mann= 13 ,-1 , 0
  1904.2    .035       0  2361.1     .05       0  2898.3     .12       0
  3078.8    .045       0  3989.3     .12       0    4162     .07       0
  4919.8      .1       0  4975.5     .05       0  4996.6      .1       0
  5579.6     .12       0  5911.7     .07       0  5938.5     .12       0
  6101.4     .07       0
Bank Sta=4975.5,4996.6
XS Rating Curve= 0 ,0
Exp/Cntr=0.3,0.1

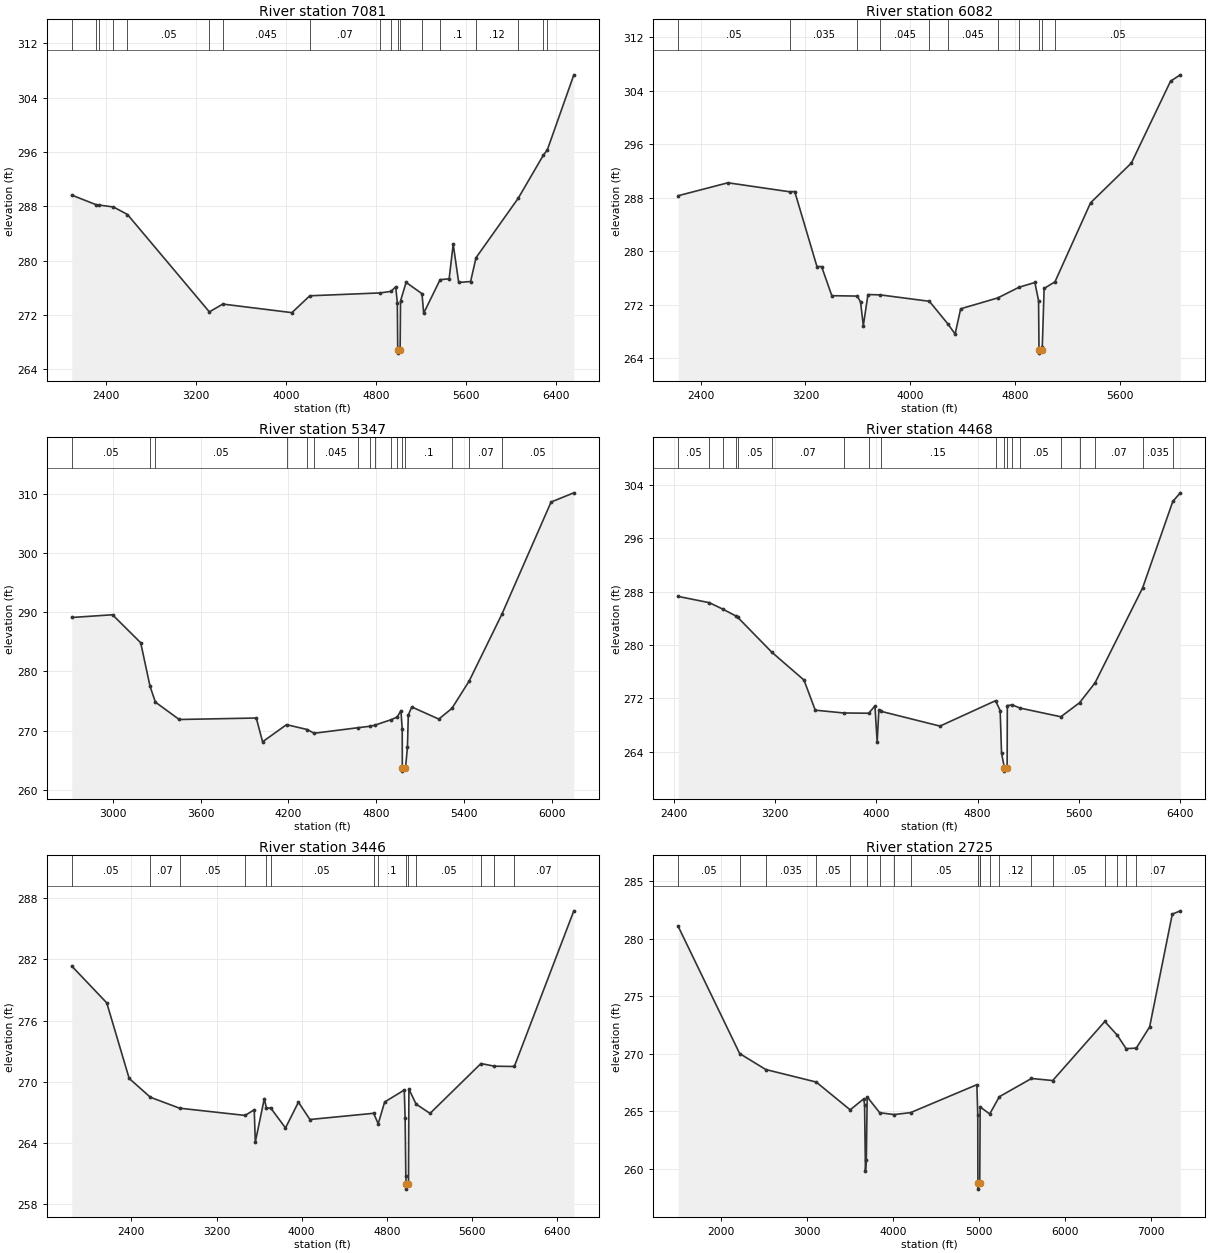
Type RM Length L Ch R = 1 ,7081    ,999,999,999
BEGIN DESCRIPTION:
VANHAM CREEK 5.0
END DESCRIPTION:
XS GIS Cut Line= 3
      2514044.87       13752016.      2516540.53     13754077.63
      2517700.76     13754489.67
#Sta/Elev= 30
  2094.8  289.64    2312  288.22  2332.9  288.18  2465.8  287.89  2590.7  286.78
  3319.4  272.45  3438.9   273.6  4054.1  272.34  4213.2  274.82  4837.2  275.24
  4936.6  275.47  4977.7  276.15  4992.1   273.8  4995.7  266.88  4996.2  266.38
    5017  266.88  5020.7  274.07  5070.2  276.79  5211.6  275.13  5226.6  272.26
    5373  277.19  5453.3  277.32  5489.4  282.42  5538.2  276.78  5644.4  276.92
  5692.4  280.42  6068.2  289.18  6292.2  295.53  6326.4  296.26  6563.1  307.34
#Mann= 18 ,-1 , 0
  2094.8    .035       0    2312     .07       0  2332.9     .05       0
  2465.8    .035       0  2590.7     .05       0  3319.4     .12       0
  3438.9    .045       0  4213.2     .07       0  4837.2     .12       0
  4936.6      .1       0  4995.7     .05       0    5017      .1       0
  5211.6     .12       0    5373      .1       0  5692.4     .12       0
  6068.2     .07       0  6292.2     .12       0  6326.4     .07       0
Bank Sta=4995.7,5017
XS Rating Curve= 0 ,0
Exp/Cntr=0.3,0.1

Type RM Length L Ch R = 1 ,6082    ,735,735,735
BEGIN DESCRIPTION:
VANHAM CREEK 4.0
END DESCRIPTION:
XS GIS Cut Line= 3
      2513838.71     13752384.92      2515954.59     13754555.06
       2516474.3     13755161.39
#Sta/Elev= 30
  2229.7  288.28  2608.9  290.21  3081.1  288.86  3118.2   288.9  3287.9  277.68
  3323.2  277.68  3401.1  273.33  3595.2  273.27  3620.3  272.39  3641.4  268.85
  3676.8   273.5  3770.1  273.45  4145.3  272.49  4286.7   269.1  4341.5   267.6
  4383.9  271.37  4666.4  272.99  4828.9  274.59  4949.8   275.3  4978.1  272.58
  4981.4  265.24  4981.9  264.74  5002.9  265.24  5006.3  265.63  5020.5  274.41
  5103.1   275.4  5374.5  287.21  5686.2  293.17  5984.7   305.4  6059.2  306.35
#Mann= 11 ,-1 , 0
  2229.7     .05       0  3081.1    .035       0  3595.2      .1       0
  3770.1    .045       0  4145.3    .035       0  4286.7    .045       0
  4666.4    .035       0  4828.9      .1       0  4981.4     .05       0
  5002.9      .1       0  5103.1     .05       0
Bank Sta=4981.4,5002.9
XS Rating Curve= 0 ,0
Exp/Cntr=0.3,0.1

Type RM Length L Ch R = 1 ,5347    ,879,879,879
BEGIN DESCRIPTION:
VANHAM CREEK 3.0
END DESCRIPTION:
XS GIS Cut Line= 3
      2514044.88     13752743.02      2515173.34     13754717.82
      2516116.96     13755390.29
#Sta/Elev= 30
  2719.5   289.1  2998.2  289.56  3190.8  284.84  3254.8  277.48  3291.4  274.82
  3454.3  271.89  3981.2  272.14  4024.4  268.13    4188  271.02  4329.5   270.2
  4377.1  269.57  4675.2   270.5  4755.4  270.74  4790.5  270.92  4905.7  271.88
  4944.5  272.31  4970.3  273.37  4979.2  270.27  4979.9  263.68  4980.4  263.18
  5001.4  263.68  5014.7  267.17  5020.8  272.64  5044.2  274.01  5229.3  271.96
  5318.6  273.76  5437.1  278.39  5660.8  289.66    5997  308.58  6152.7  310.13
#Mann= 16 ,-1 , 0
  2719.5     .05       0  3254.8     .07       0  3291.4     .05       0
    4188    .045       0  4329.5     .05       0  4377.1    .045       0
  4675.2      .1       0  4755.4    .045       0  4790.5      .1       0
  4905.7     .07       0  4944.5      .1       0  4979.9     .05       0
  5001.4      .1       0  5318.6    .035       0  5437.1     .07       0
  5660.8     .05       0
Bank Sta=4979.9,5001.4
XS Rating Curve= 0 ,0
Exp/Cntr=0.3,0.1

Type RM Length L Ch R = 1 ,4468    ,1022,1022,1022
BEGIN DESCRIPTION:
VANHAM CREEK 2.0
END DESCRIPTION:
XS GIS Cut Line= 3
       2513751.9     13752797.25        2514575.       13755225.
      2515790.95     13755921.74
#Sta/Elev= 30
  2436.5  287.29  2682.4  286.35  2786.7   285.4  2891.7  284.36  2907.8  284.13
  3174.9  278.93  3429.6  274.74  3518.5  270.22  3741.7   269.8  3941.1  269.76
  3989.7  270.86  4007.4  265.47  4021.1   270.3  4034.8  270.06  4503.7  267.83
  4942.2  271.64  4978.9  270.16  4989.6  263.77  5012.3  261.57  5012.8  261.07
  5033.8  261.57  5035.2  270.91  5074.8  271.01  5136.7  270.53  5458.1  269.23
    5606  271.34  5728.1  274.32  6103.7  288.57  6342.3  301.56  6401.4  302.84
#Mann= 19 ,-1 , 0
  2436.5     .05       0  2682.4     .07       0  2786.7     .05       0
  2891.7     .07       0  2907.8     .05       0  3174.9     .07       0
  3741.7     .05       0  3941.1      .1       0  4034.8     .15       0
  4942.2      .1       0  5012.3     .05       0  5033.8      .1       0
  5074.8     .07       0  5136.7     .05       0  5458.1     .07       0
    5606     .12       0  5728.1     .07       0  6103.7    .035       0
  6342.3     .07       0
Bank Sta=5012.3,5033.8
XS Rating Curve= 0 ,0
Exp/Cntr=0.3,0.1

Type RM Length L Ch R = 1 ,3446    ,721,721,721
BEGIN DESCRIPTION:
VANHAM CREEK 1.0
END DESCRIPTION:
XS GIS Cut Line= 4
      2513437.23     13752992.57      2513892.96     13755770.34
      2514402.94     13756171.81      2515650.35     13756312.82
#Sta/Elev= 30
  1839.4  281.34  2168.3  277.73  2378.9  270.32  2578.6  268.47  2852.4   267.4
  3469.2  266.69  3554.5  267.25  3564.6  264.08  3649.2  268.34  3669.7  267.38
    3708  267.44  3848.3  265.46  3969.9  267.99  4078.2  266.29  4677.1   266.9
  4719.7  265.87  4780.4  268.01  4964.8  269.18  4972.9  266.43  4979.3  260.78
    4983  259.96  4983.5  259.46  5004.5  259.96  5008.2  269.27  5076.1   267.8
    5207  266.89  5685.6  271.78  5811.7  271.52  5999.2  271.49  6558.7  286.76
#Mann= 14 ,-1 , 0
  1839.4     .05       0  2578.6     .07       0  2852.4     .05       0
  3469.2      .1       0  3669.7     .15       0    3708     .05       0
  4677.1    .035       0  4719.7      .1       0    4983     .05       0
  5004.5      .1       0  5076.1     .05       0  5685.6     .07       0
  5811.7     .12       0  5999.2     .07       0
Bank Sta=4983,5004.5
XS Rating Curve= 0 ,0
Exp/Cntr=0.3,0.1

Type RM Length L Ch R = 1 ,2725    ,0,0,0
BEGIN DESCRIPTION:
H21531
END DESCRIPTION:
XS GIS Cut Line= 4
      2513337.91     13752895.14      2513040.92     13755232.73
       2513730.7     13756641.03      2515627.61     13756382.36
#Sta/Elev= 30
  1503.2  281.08  2217.5  270.02  2520.8  268.63  3107.8  267.54  3502.9  265.12
  3660.3  266.08  3670.3  265.58  3680.4  259.82  3690.5  260.73  3700.6  266.25
  3845.8  264.87  4014.3  264.71  4205.8  264.88  4976.3  267.31  4986.8  264.64
    4988  258.72  4988.5  258.22  5009.6  258.72  5014.7  265.37  5125.8  264.76
    5237  266.26  5611.2  267.85    5858  267.67  6464.1  272.81  6608.8  271.62
  6711.7  270.45  6830.2  270.49  6985.5  272.34  7248.7  282.15  7342.2  282.44
#Mann= 20 ,-1 , 0
  1503.2     .05       0  2217.5     .07       0  2520.8    .035       0
  3107.8     .05       0  3502.9    .035       0  3700.6    .035       0
  3845.8    .035       0  4014.3     .05       0  4205.8     .05       0
    4988     .05       0  5009.6      .1       0  5014.7     .12       0
  5125.8     .07       0    5237     .12       0  5611.2     .07       0
    5858     .05       0  6464.1     .05       0  6608.8     .07       0
  6711.7     .12       0  6830.2     .07       0
Bank Sta=4988,5009.6
XS Rating Curve= 0 ,0
Exp/Cntr=0.3,0.1

Chan Stop Cuts=-1
Use User Specified Reach Order=0
Composite Channel Slope=5