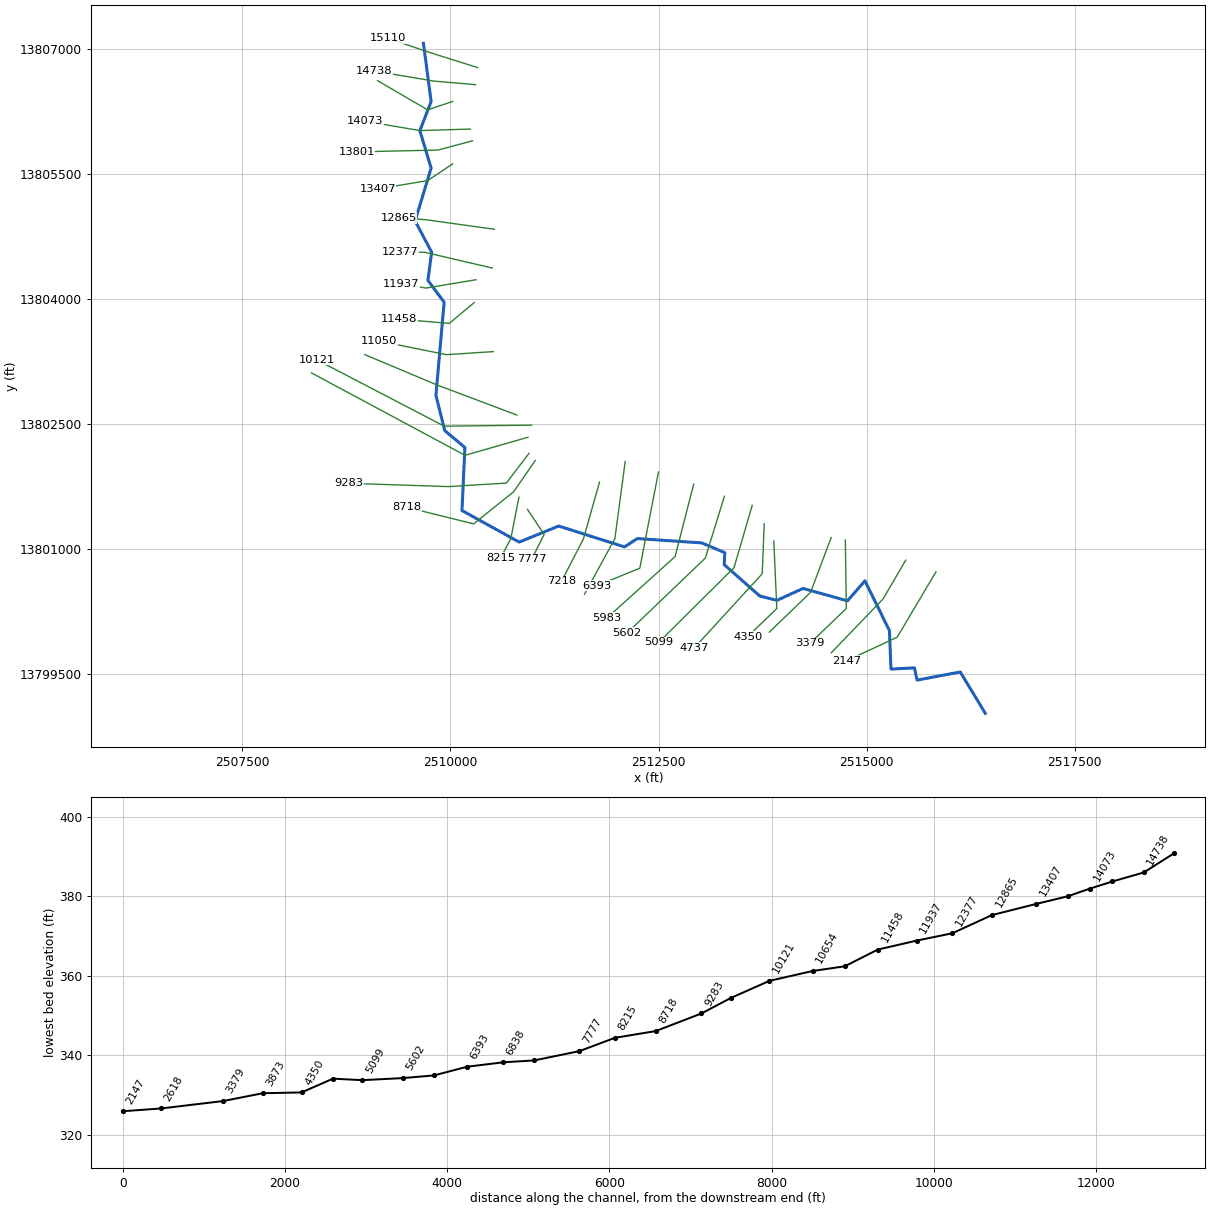
--- WAELDER BRANCH.prj (project) ---

Proj Title=WAELDER BRANCH Base Level Engineering
Current Plan=p01
Default Exp/Contr=0.3,0.1
English Units
Geom File=g01
Flow File=f01
Plan File=p01
BEGIN DESCRIPTION:
WAELDER BRANCH
END DESCRIPTION:

--- WAELDER BRANCH.p01 (plan) ---

Plan Title=Multiple Run
Short Identifier=Multiple
Geom File=g01
Flow File=f01
Subcritical Flow
K Sum by GR= 0
Std Step Tol= 0.01
Critical Tol= 0.01
Num of Std Step Trials= 20
Max Error Tol= 0.3
Flow Tol Ratio= 0.001
Split Flow NTrial= 30
Split Flow Tol= 0.02
Split Flow Ratio= 0.02
Log Output Level= 0
Friction Slope Method= 1
Unsteady Friction Slope Method= 2
Unsteady Bridges Friction Slope Method= 1
Parabolic Critical Depth
Global Vel Dist=  1 , 1 , 1
Global Log Level= 0
CheckData=True
Encroach Param= -1, 0, 0, 0
BEGIN DESCRIPTION:
Multiple Run
END DESCRIPTION:

--- WAELDER BRANCH.f01 (steady flow) ---

Flow Title=Multiple
Number of Profiles=7
Profile Names=10-year,25-year,50-year,1pct_min,100-year,1pct_plu,500-year
River Rch & RM= WAELDER BRANCH,Reach-1,15110
     361     556     724     458     913    1823    1437
River Rch & RM= WAELDER BRANCH,Reach-1,11937
     705    1133    1517     984    1964    3919    3257
River Rch & RM= WAELDER BRANCH,Reach-1,6838
     916    1485    2002    1305    2604    5195    4361
Boundary for River Rch & Prof#=WAELDER BRANCH,Reach-1,1
Up Type=0
Dn Type=3
Dn Slope=0.005
Boundary for River Rch & Prof#=WAELDER BRANCH,Reach-1,2
Up Type=0
Dn Type=3
Dn Slope=0.005
Boundary for River Rch & Prof#=WAELDER BRANCH,Reach-1,3
Up Type=0
Dn Type=3
Dn Slope=0.005
Boundary for River Rch & Prof#=WAELDER BRANCH,Reach-1,4
Up Type=0
Dn Type=3
Dn Slope=0.005
Boundary for River Rch & Prof#=WAELDER BRANCH,Reach-1,5
Up Type=0
Dn Type=3
Dn Slope=0.005
Boundary for River Rch & Prof#=WAELDER BRANCH,Reach-1,6
Up Type=0
Dn Type=3
Dn Slope=0.005
Boundary for River Rch & Prof#=WAELDER BRANCH,Reach-1,7
Up Type=0
Dn Type=3
Dn Slope=0.005

--- WAELDER BRANCH.g01 (geometry) ---

Geom Title=Existing Conditions

River Reach=WAELDER BRANCH,Reach-1
Reach XY= 30
      2509675.00     13807075.00      2509767.44     13806375.00
      2509632.30     13806024.92      2509767.44     13805575.00
      2509575.10     13804940.40      2509774.06     13804564.52
      2509728.54     13804226.46      2509923.80     13803964.50
      2509825.07     13802845.03      2509930.52     13802422.56
      2510172.95     13802219.16      2510138.11     13801461.76
      2510824.99     13801082.53      2511299.96     13801275.49
      2512090.36     13801024.90      2512244.98     13801125.04
      2513019.06     13801072.74      2513295.68     13800955.38
      2513288.40     13800811.27      2513714.88     13800435.35
      2513921.70     13800383.08      2514235.05     13800525.80
      2514769.15     13800376.55      2514978.35     13800617.42
      2515273.02     13800019.33      2515291.43     13799557.31
      2515573.98     13799571.40      2515604.24     13799424.43
      2516123.61     13799521.97      2516425.00     13799025.00

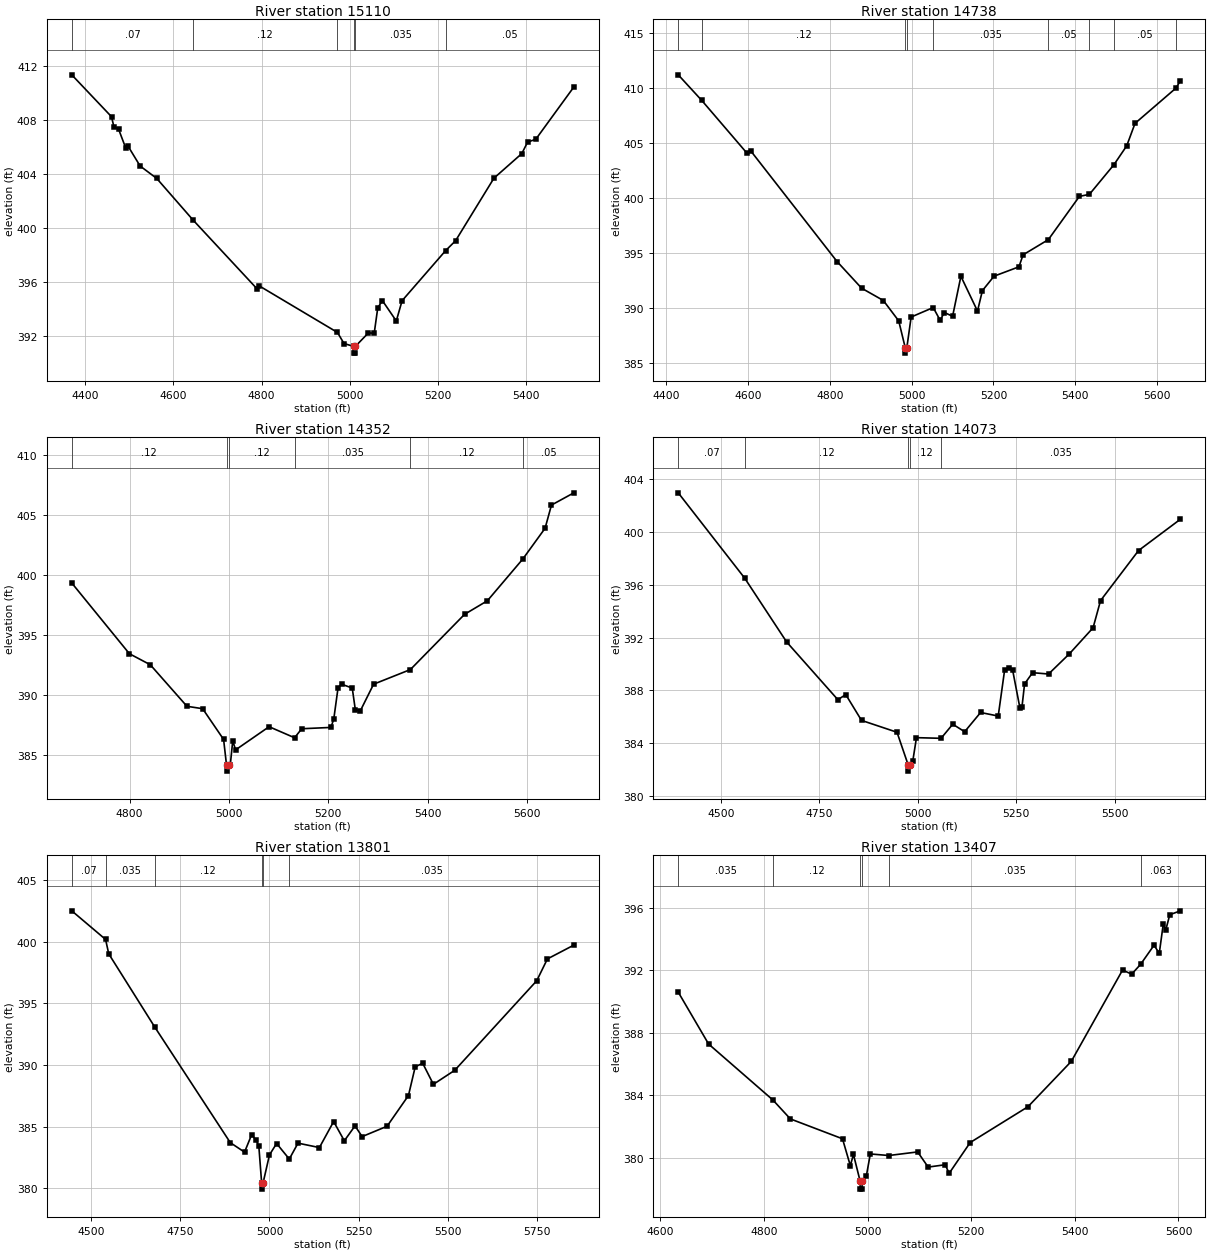
Type RM Length L Ch R = 1,15110,372,372,372
BEGIN DESCRIPTION:
XS7940
END DESCRIPTION:
XS GIS Cut Line= 3
      2510326.11     13806783.10      2509823.93     13806940.40
      2509243.09     13807134.02
#Sta/Elev= 30
  4369.4  411.32  4459.5  408.22  4464.9  407.48  4475.4  407.31  4492.0  405.88
  4497.2  406.03  4524.4  404.57  4562.1  403.65  4644.2  400.58  4789.2  395.49
  4794.4  395.70  4971.9  392.25  4986.7  391.43  5008.5  391.22  5008.7  390.72
  5012.2  390.72  5012.5  391.22  5042.1  392.22  5055.2  392.19  5063.2  394.06
  5073.7  394.61  5105.3  393.10  5118.4  394.60  5217.2  398.31  5239.7  399.04
  5326.7  403.67  5389.9  405.49  5403.0  406.34  5421.6  406.55  5507.9  410.42
#Mann=6,-1,0
  4369.4    0.07       0  4644.2    0.12       0  4971.9   0.035       0
  5008.5   0.035       0  5012.5   0.035       0  5217.2    0.05       0
Bank Sta=5008.5,5012.5
Exp/Cntr=0.3,0.1

Type RM Length L Ch R = 1,14738,386,386,386
BEGIN DESCRIPTION:
WAELDER BRANCH 24.0
END DESCRIPTION:
XS GIS Cut Line= 3
      2510301.92     13806577.38      2509805.77     13806619.73
      2509085.72     13806740.75
#Sta/Elev= 30
  4429.0  411.20  4486.4  408.88  4596.5  404.11  4606.6  404.28  4817.5  394.24
  4877.5  391.82  4930.7  390.70  4968.3  388.85  4984.2  386.42  4984.5  385.92
  4988.2  386.42  4998.7  389.20  5052.7  390.06  5069.7  388.90  5079.8  389.61
  5100.1  389.27  5120.4  392.90  5161.0  389.74  5173.0  391.60  5201.5  392.91
  5262.4  393.76  5272.5  394.85  5334.3  396.23  5410.3  400.16  5434.7  400.34
  5495.0  403.05  5526.0  404.75  5546.3  406.79  5646.6  410.00  5657.1  410.66
#Mann=9,-1,0
  4429.0    0.07       0  4486.4    0.12       0  4984.2    0.05       0
  4988.2    0.12       0  5052.7   0.035       0  5334.3    0.05       0
  5434.7    0.12       0  5495.0    0.05       0  5646.6   0.035       0
Bank Sta=4984.2,4988.2
Exp/Cntr=0.3,0.1

Type RM Length L Ch R = 1,14352,279,279,279
BEGIN DESCRIPTION:
WAELDER BRANCH 23.0
END DESCRIPTION:
XS GIS Cut Line= 3
      2510025.02     13806375.01      2509725.00     13806275.00
      2509124.98     13806625.01
#Sta/Elev= 30
  4683.4  399.33  4799.4  393.44  4841.5  392.52  4915.3  389.06  4946.9  388.86
  4989.1  386.30  4995.0  384.16  4995.3  383.66  4999.0  384.16  5002.5  384.16
  5007.5  386.18  5013.3  385.43  5080.7  387.36  5132.0  386.44  5146.4  387.19
  5205.1  387.30  5210.9  387.99  5219.6  390.62  5226.6  390.90  5248.1  390.58
  5254.3  388.78  5263.9  388.64  5291.1  390.90  5365.2  392.12  5474.3  396.72
  5520.2  397.85  5591.6  401.33  5636.4  403.89  5649.2  405.82  5694.3  406.84
#Mann=6,-1,0
  4683.4    0.12       0  4995.0    0.05       0  4999.0    0.12       0
  5132.0   0.035       0  5365.2    0.12       0  5591.6    0.05       0
Bank Sta=4995,4999
Exp/Cntr=0.3,0.1

Type RM Length L Ch R = 1,14073,272,272,272
BEGIN DESCRIPTION:
H21539
END DESCRIPTION:
XS GIS Cut Line= 3
      2510240.03     13806044.11      2509631.10     13806026.09
      2508975.34     13806137.79
#Sta/Elev= 30
  4392.2  402.98  4561.0  396.50  4667.4  391.66  4797.4  387.28  4817.4  387.67
  4857.4  385.71  4947.5  384.81  4975.5  382.36  4975.7  381.86  4979.5  382.36
  4987.5  382.62  4996.9  384.40  5059.3  384.35  5089.0  385.42  5119.2  384.85
  5159.7  386.31  5204.4  386.04  5220.6  389.52  5230.8  389.67  5240.9  389.54
  5259.5  386.65  5264.6  386.71  5271.3  388.48  5291.6  389.33  5332.2  389.23
  5385.0  390.76  5445.2  392.74  5464.1  394.80  5560.6  398.60  5666.6  400.97
#Mann=5,-1,0
  4392.2    0.07       0  4561.0    0.12       0  4975.5    0.05       0
  4979.5    0.12       0  5059.3   0.035       0
Bank Sta=4975.5,4979.5
Exp/Cntr=0.3,0.1

Type RM Length L Ch R = 1,13801,394,394,394
BEGIN DESCRIPTION:
WAELDER BRANCH 22.0
END DESCRIPTION:
XS GIS Cut Line= 3
      2510265.21     13805903.57      2509850.89     13805791.89
      2508870.84     13805770.27
#Sta/Elev= 30
  4445.0  402.50  4539.9  400.18  4548.8  399.01  4677.6  393.09  4890.0  383.70
  4930.0  382.93  4950.0  384.35  4962.3  383.90  4970.0  383.45  4978.0  380.43
  4978.3  379.93  4982.0  380.43  5000.0  382.71  5020.0  383.63  5055.6  382.37
  5080.1  383.66  5140.1  383.30  5180.1  385.41  5210.1  383.85  5240.1  385.06
  5260.1  384.19  5330.1  385.03  5390.1  387.52  5409.1  389.85  5430.1  390.14
  5460.1  388.43  5520.2  389.57  5750.2  396.83  5780.2  398.60  5854.4  399.72
#Mann=6,-1,0
  4445.0    0.07       0  4539.9   0.035       0  4677.6    0.12       0
  4978.0    0.05       0  4982.0    0.12       0  5055.6   0.035       0
Bank Sta=4978,4982
Exp/Cntr=0.3,0.1

Type RM Length L Ch R = 1,13407,542,542,542
BEGIN DESCRIPTION:
WAELDER BRANCH 21.0
END DESCRIPTION:
XS GIS Cut Line= 3
      2510025.03     13805625.02      2509725.00     13805425.00
      2509124.97     13805325.00
#Sta/Elev= 30
  4634.6  390.59  4693.2  387.27  4817.3  383.69  4851.0  382.48  4951.6  381.21
  4966.7  379.49  4972.7  380.21  4985.7  378.49  4985.9  377.99  4989.4  377.99
  4989.7  378.49  4997.7  378.85  5005.3  380.24  5040.9  380.14  5096.6  380.37
  5116.9  379.40  5149.8  379.55  5157.4  379.00  5198.0  380.97  5309.5  383.26
  5393.1  386.16  5492.0  392.00  5509.7  391.74  5526.9  392.37  5552.8  393.59
  5562.9  393.07  5570.5  394.92  5575.6  394.59  5583.2  395.54  5603.5  395.79
#Mann=6,-1,0
  4634.6   0.035       0  4817.3    0.12       0  4985.7    0.05       0
  4989.7    0.12       0  5040.9   0.035       0  5526.9   0.063       0
Bank Sta=4985.7,4989.7
Exp/Cntr=0.3,0.1

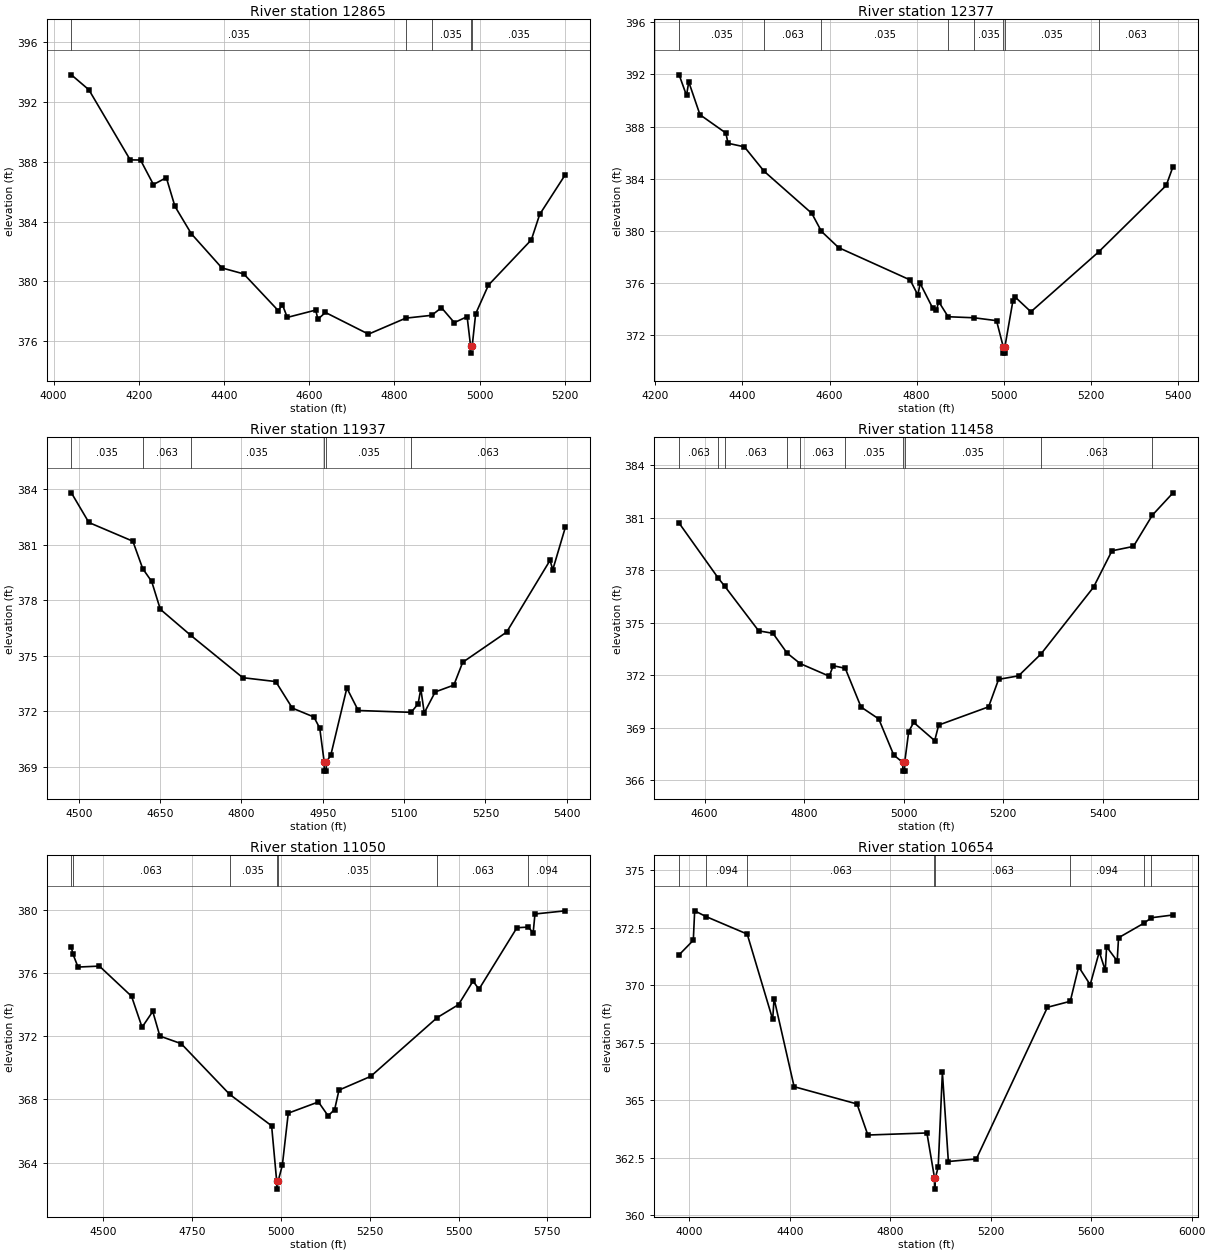
Type RM Length L Ch R = 1,12865,488,488,488
BEGIN DESCRIPTION:
WAELDER BRANCH 20.0
END DESCRIPTION:
XS GIS Cut Line= 3
      2510525.76     13804840.89      2509696.87     13804955.85
      2509374.96     13804975.00
#Sta/Elev= 30
  4041.7  393.82  4082.8  392.82  4179.8  388.13  4204.0  388.12  4234.3  386.48
  4264.6  386.94  4284.8  385.02  4323.2  383.19  4395.0  380.90  4446.3  380.50
  4527.1  378.05  4537.2  378.43  4548.5  377.59  4615.2  378.08  4620.3  377.47
  4638.1  377.92  4739.1  376.47  4826.5  377.54  4887.4  377.73  4910.4  378.24
  4940.5  377.24  4970.6  377.64  4978.6  375.70  4978.8  375.20  4982.6  375.70
  4990.6  377.83  5020.6  379.75  5121.3  382.78  5140.9  384.48  5201.0  387.14
#Mann=5,-1,0
  4041.7   0.035       0  4826.5   0.063       0  4887.4   0.035       0
  4978.6   0.035       0  4982.6   0.035       0
Bank Sta=4978.6,4982.6
Exp/Cntr=0.3,0.1

Type RM Length L Ch R = 1,12377,440,440,440
BEGIN DESCRIPTION:
WAELDER BRANCH 19.0
END DESCRIPTION:
XS GIS Cut Line= 3
      2510501.62     13804374.99      2509688.70     13804564.50
      2509389.31     13804564.50
#Sta/Elev= 30
  4254.6  391.97  4271.6  390.39  4276.7  391.43  4302.5  388.91  4361.8  387.51
  4367.0  386.72  4404.4  386.45  4449.6  384.58  4559.2  381.35  4581.3  379.97
  4620.8  378.72  4785.1  376.24  4802.8  375.08  4808.0  375.98  4836.4  374.11
  4845.4  373.90  4850.5  374.58  4872.3  373.42  4932.1  373.34  4983.4  373.12
  4998.7  371.13  4998.9  370.63  5002.4  370.63  5002.7  371.13  5020.8  374.60
  5025.9  374.94  5062.3  373.80  5217.8  378.39  5373.0  383.49  5388.7  384.94
#Mann=8,-1,0
  4254.6   0.035       0  4449.6   0.063       0  4581.3   0.035       0
  4872.3   0.063       0  4932.1   0.035       0  4998.7   0.035       0
  5002.7   0.035       0  5217.8   0.063       0
Bank Sta=4998.7,5002.7
Exp/Cntr=0.3,0.1

Type RM Length L Ch R = 1,11937,479,479,479
BEGIN DESCRIPTION:
WAELDER BRANCH 18.0
END DESCRIPTION:
XS GIS Cut Line= 3
      2510306.82     13804234.24      2509706.85     13804134.24
      2509408.41     13804183.98
#Sta/Elev= 30
  4486.4  383.79  4518.7  382.19  4599.8  381.18  4618.0  379.70  4634.5  379.01
  4650.4  377.51  4706.3  376.11  4802.5  373.82  4863.3  373.61  4893.8  372.18
  4933.6  371.70  4944.4  371.10  4952.6  369.28  4952.8  368.78  4956.3  368.78
  4956.6  369.28  4964.7  369.63  4994.4  373.26  5015.4  372.05  5113.0  371.95
  5125.8  372.41  5130.8  373.22  5137.1  371.92  5157.3  373.05  5191.7  373.42
  5208.0  374.65  5289.1  376.28  5369.1  380.15  5374.1  379.64  5397.2  381.92
#Mann=6,-1,0
  4486.4   0.035       0  4618.0   0.063       0  4706.3   0.035       0
  4952.6   0.035       0  4956.6   0.035       0  5113.0   0.063       0
Bank Sta=4952.6,4956.6
Exp/Cntr=0.3,0.1

Type RM Length L Ch R = 1,11458,408,408,408
BEGIN DESCRIPTION:
WAELDER BRANCH 17.0
END DESCRIPTION:
XS GIS Cut Line= 3
      2510285.51     13803960.05      2509985.50     13803710.04
      2509385.71     13803760.02
#Sta/Elev= 30
  4548.9  380.69  4627.8  377.54  4640.5  377.09  4708.7  374.54  4737.4  374.40
  4765.8  373.27  4792.2  372.67  4850.6  371.95  4858.4  372.55  4882.7  372.40
  4914.4  370.19  4950.0  369.51  4980.1  367.45  4998.1  367.03  4998.4  366.53
  5001.9  366.53  5002.1  367.03  5010.2  368.79  5020.2  369.31  5062.4  368.27
  5070.4  369.16  5170.7  370.20  5190.8  371.77  5230.9  371.97  5276.0  373.22
  5381.5  377.03  5418.6  379.11  5461.7  379.36  5499.9  381.15  5541.3  382.42
#Mann=10,-1,0
  4548.9   0.063       0  4627.8   0.035       0  4640.5   0.063       0
  4765.8   0.035       0  4792.2   0.063       0  4882.7   0.035       0
  4998.1   0.035       0  5002.1   0.035       0  5276.0   0.063       0
  5499.9   0.035       0
Bank Sta=4998.1,5002.1
Exp/Cntr=0.3,0.1

Type RM Length L Ch R = 1,11050,396,396,396
BEGIN DESCRIPTION:
WAELDER BRANCH 16.0
END DESCRIPTION:
XS GIS Cut Line= 3
      2510513.70     13803370.62      2509950.99     13803334.32
      2509140.26     13803497.67
#Sta/Elev= 30
  4409.8  377.62  4414.2  377.21  4428.5  376.38  4488.7  376.44  4579.3  374.53
  4608.9  372.57  4639.0  373.57  4659.0  372.01  4719.1  371.53  4855.6  368.32
  4973.7  366.33  4988.0  362.82  4988.2  362.32  4992.0  362.82  5003.9  363.83
  5020.6  367.13  5105.5  367.84  5132.8  366.96  5151.2  367.36  5163.4  368.59
  5252.8  369.46  5440.0  373.18  5500.0  374.00  5540.8  375.49  5557.7  374.98
  5664.5  378.87  5696.7  378.91  5710.2  378.54  5715.3  379.74  5800.7  379.94
#Mann=7,-1,0
  4409.8   0.035       0  4414.2   0.063       0  4855.6   0.035       0
  4988.0   0.035       0  4992.0   0.035       0  5440.0   0.063       0
  5696.7   0.094       0
Bank Sta=4988,4992
Exp/Cntr=0.3,0.1

Type RM Length L Ch R = 1,10654,533,533,533
BEGIN DESCRIPTION:
WAELDER BRANCH 15.0
END DESCRIPTION:
XS GIS Cut Line= 3
      2510798.10     13802608.24      2509836.03     13802971.29
      2508970.79     13803334.33
#Sta/Elev= 30
  3959.3  371.32  4015.8  371.95  4021.2  373.23  4066.5  372.98  4230.4  372.22
  4331.9  368.51  4337.3  369.42  4417.2  365.59  4667.5  364.84  4710.8  363.49
  4945.9  363.58  4976.0  361.64  4976.2  361.14  4980.0  361.64  4990.9  362.11
  5007.5  366.21  5031.3  362.34  5142.6  362.45  5425.8  369.04  5516.7  369.30
  5550.0  370.80  5596.0  370.02  5632.2  371.45  5656.0  370.64  5661.4  371.67
  5703.5  371.05  5708.9  372.06  5809.5  372.69  5839.8  372.93  5925.9  373.05
#Mann=8,-1,0
  3959.3   0.063       0  4066.5   0.094       0  4230.4   0.063       0
  4976.0    0.05       0  4980.0   0.063       0  5516.7   0.094       0
  5809.5   0.063       0  5839.8     0.1       0
Bank Sta=4976,4980
Exp/Cntr=0.3,0.1

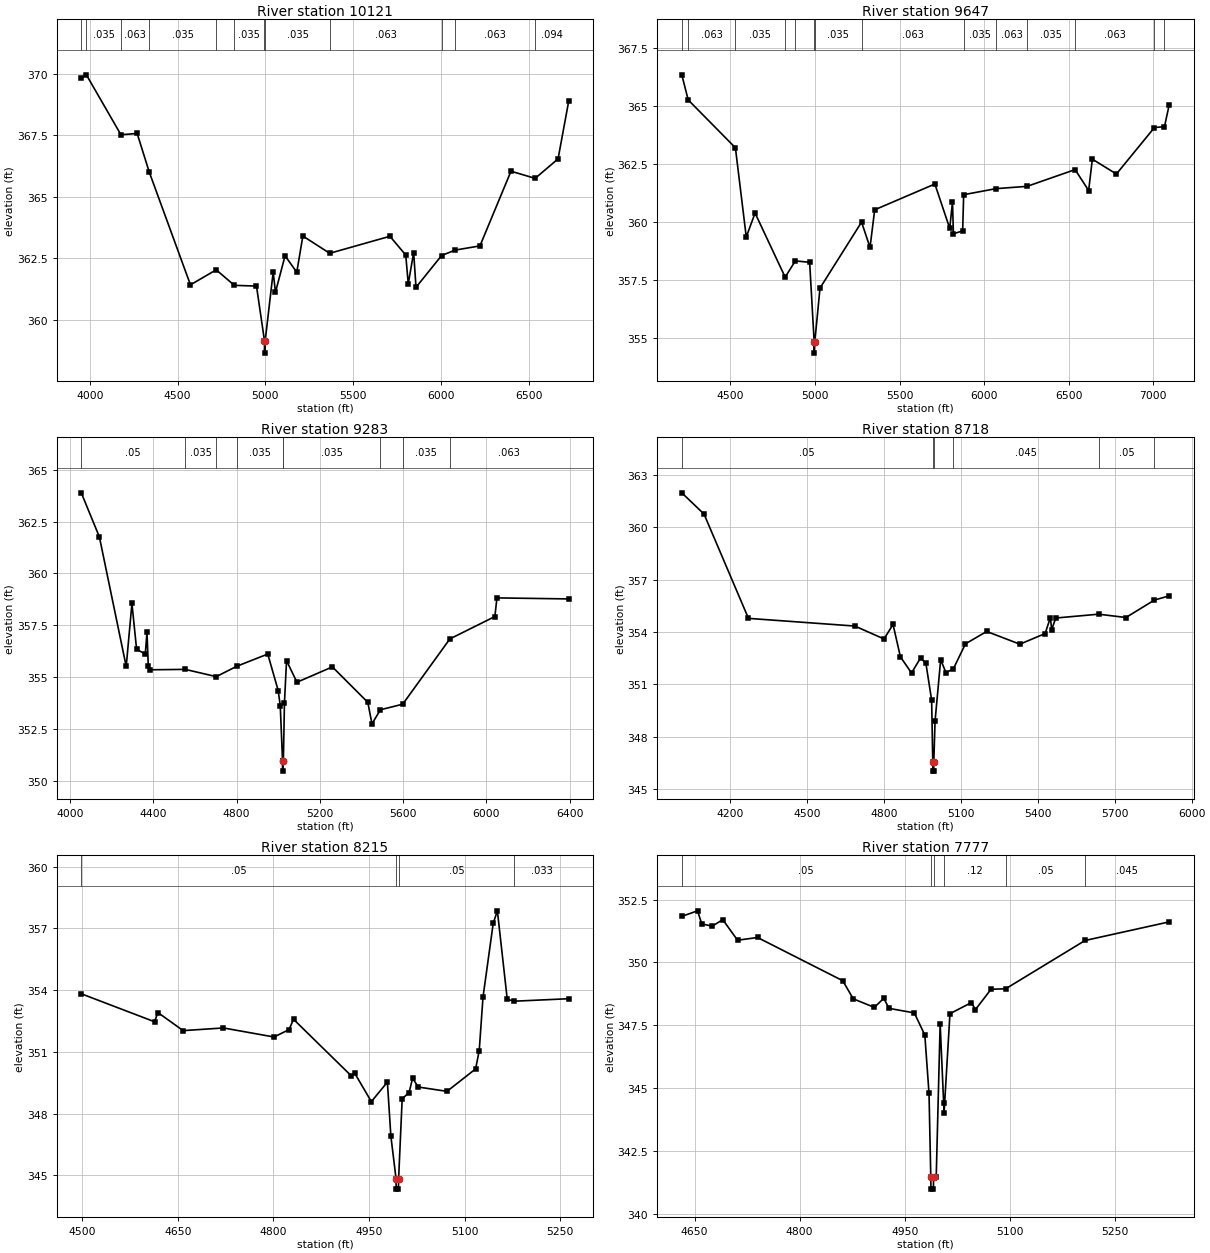
Type RM Length L Ch R = 1,10121,474,474,474
BEGIN DESCRIPTION:
WAELDER BRANCH 14.0
END DESCRIPTION:
XS GIS Cut Line= 3
      2510973.47     13802487.25      2509925.00     13802475.00
      2508391.58     13803273.27
#Sta/Elev= 30
  3951.4  369.83  3980.4  369.95  4177.3  367.52  4269.9  367.57  4338.5  366.01
  4573.5  361.43  4720.4  362.04  4823.4  361.41  4949.9  361.38  4995.4  359.16
  4995.7  358.66  4999.4  359.16  5045.0  361.95  5058.0  361.13  5112.7  362.61
  5179.4  361.94  5214.1  363.41  5367.2  362.71  5710.2  363.40  5800.4  362.64
  5814.7  361.47  5845.5  362.74  5858.9  361.33  6004.9  362.62  6082.1  362.84
  6223.3  363.01  6400.2  366.04  6537.8  365.75  6668.5  366.54  6728.7  368.87
#Mann=12,-1,0
  3951.4   0.063       0  3980.4   0.035       0  4177.3   0.063       0
  4338.5   0.035       0  4720.4   0.063       0  4823.4   0.035       0
  4995.4   0.035       0  4999.4   0.035       0  5367.2   0.063       0
  6004.9   0.035       0  6082.1   0.063       0  6537.8   0.094       0
Bank Sta=4995.4,4999.4
Exp/Cntr=0.3,0.1

Type RM Length L Ch R = 1,9647,364,364,364
BEGIN DESCRIPTION:
WAELDER BRANCH 13.0
END DESCRIPTION:
XS GIS Cut Line= 3
      2510931.16     13802342.04      2510175.00     13802125.00
      2508330.33     13803114.72
#Sta/Elev= 30
  4213.4  366.35  4251.1  365.27  4530.2  363.21  4594.3  359.37  4646.4  360.40
  4824.1  357.64  4884.5  358.34  4968.9  358.28  4995.5  354.87  4995.7  354.37
  4999.5  354.87  5030.1  357.17  5275.7  360.01  5325.7  358.92  5353.3  360.54
  5709.0  361.65  5796.7  359.74  5813.0  360.87  5818.6  359.51  5873.1  359.63
  5879.1  361.19  6069.9  361.45  6254.4  361.55  6537.5  362.27  6617.7  361.37
  6639.6  362.72  6781.8  362.08  7006.4  364.08  7065.9  364.12  7093.5  365.05
#Mann=14,-1,0
  4213.4   0.035       0  4251.1   0.063       0  4530.2   0.035       0
  4824.1   0.063       0  4884.5   0.035       0  4995.5   0.035       0
  4999.5   0.035       0  5275.7   0.063       0  5879.1   0.035       0
  6069.9   0.063       0  6254.4   0.035       0  6537.5   0.063       0
  7006.4   0.094       0  7065.9   0.063       0
Bank Sta=4995.5,4999.5
Exp/Cntr=0.3,0.1

Type RM Length L Ch R = 1,9283,565,565,565
BEGIN DESCRIPTION:
XS7939
END DESCRIPTION:
XS GIS Cut Line= 4
      2510943.29     13802148.46      2510670.99     13801791.45
      2509975.19     13801749.09      2508780.75     13801788.74
#Sta/Elev= 30
  4054.1  363.89  4141.1  361.76  4269.9  355.51  4297.4  358.55  4319.8  356.34
  4361.5  356.11  4369.7  357.15  4376.0  355.53  4384.2  355.35  4553.5  355.37
  4702.5  355.02  4801.0  355.52  4949.9  356.11  5000.0  354.35  5010.0  353.61
  5020.9  350.96  5021.1  350.46  5024.9  350.96  5030.1  353.76  5040.1  355.79
  5090.2  354.75  5260.4  355.49  5430.5  353.78  5450.5  352.74  5490.9  353.42
  5598.2  353.69  5824.7  356.84  6040.9  357.92  6050.9  358.82  6395.3  358.77
#Mann=9,-1,0
  4054.1    0.05       0  4553.5   0.035       0  4702.5    0.05       0
  4801.0   0.035       0  5020.9   0.035       0  5024.9   0.035       0
  5490.9   0.063       0  5598.2   0.035       0  5824.7   0.063       0
Bank Sta=5020.9,5024.9
Exp/Cntr=0.3,0.1

Type RM Length L Ch R = 1,8718,503,503,503
BEGIN DESCRIPTION:
WAELDER BRANCH 12.0
END DESCRIPTION:
XS GIS Cut Line= 4
      2511018.35     13802062.62      2510759.10     13801687.59
      2510277.71     13801301.36      2509476.17     13801500.48
#Sta/Elev= 30
  4013.3  361.98  4100.0  360.76  4273.0  354.78  4687.5  354.34  4801.2  353.60
  4836.4  354.43  4865.2  352.57  4908.4  351.65  4943.6  352.51  4964.4  352.21
  4986.8  350.09  4991.2  346.52  4991.5  346.02  4995.0  346.02  4995.2  346.52
  5000.1  348.89  5022.0  352.41  5042.8  351.66  5071.9  351.90  5118.6  353.32
  5201.3  354.03  5330.5  353.30  5429.2  353.91  5449.4  354.83  5454.5  354.13
  5470.4  354.80  5637.3  355.02  5743.9  354.83  5854.8  355.83  5912.3  356.07
#Mann=6,-1,0
  4013.3    0.05       0  4991.2    0.05       0  4995.2    0.05       0
  5071.9   0.045       0  5637.3    0.05       0  5854.8   0.035       0
Bank Sta=4991.2,4995.2
Exp/Cntr=0.3,0.1

Type RM Length L Ch R = 1,8215,438,438,438
BEGIN DESCRIPTION:
WAELDER BRANCH 11.0
END DESCRIPTION:
XS GIS Cut Line= 3
      2510822.26     13801622.06      2510725.00     13801125.00
      2510604.44     13800895.98
#Sta/Elev= 30
  4498.2  353.82  4613.3  352.46  4618.4  352.91  4658.2  352.03  4721.4  352.16
  4800.9  351.72  4824.4  352.08  4831.5  352.58  4922.3  349.83  4927.4  349.97
  4953.7  348.58  4978.9  349.53  4984.3  346.92  4992.5  344.83  4992.7  344.33
  4996.2  344.33  4996.5  344.83  5002.1  348.72  5012.9  349.02  5018.5  349.72
  5027.3  349.29  5072.5  349.08  5117.4  350.17  5123.1  351.06  5129.0  353.65
  5145.1  357.25  5151.6  357.85  5167.1  353.55  5178.1  353.46  5263.5  353.58
#Mann=4,-1,0
  4498.2    0.05       0  4992.5    0.05       0  4996.5    0.05       0
  5178.1   0.033       0
Bank Sta=4992.5,4996.5
Exp/Cntr=0.3,0.1

Type RM Length L Ch R = 1,7777,559,559,559
BEGIN DESCRIPTION:
WAELDER BRANCH 10.0
END DESCRIPTION:
XS GIS Cut Line= 3
      2510925.02     13801474.96      2511125.00     13801175.00
      2510975.01     13800875.02
#Sta/Elev= 30
  4631.7  351.83  4654.2  352.05  4660.2  351.53  4675.2  351.44  4690.2  351.70
  4711.3  350.88  4739.8  350.99  4861.5  349.27  4876.5  348.55  4906.6  348.21
  4920.1  348.57  4927.6  348.17  4963.7  347.99  4978.7  347.11  4984.7  344.79
  4987.2  341.48  4987.5  340.98  4991.0  340.98  4991.2  341.48  4995.0  341.48
  5000.6  347.56  5005.6  344.40  5006.2  344.02  5014.6  347.96  5045.3  348.40
  5050.9  348.12  5073.3  348.93  5094.2  348.95  5207.5  350.87  5327.6  351.61
#Mann=6,-1,0
  4631.7    0.05       0  4987.2    0.05       0  4991.2    0.05       0
  5005.6    0.12       0  5094.2    0.05       0  5207.5   0.045       0
Bank Sta=4987.2,4991.2
Exp/Cntr=0.3,0.1

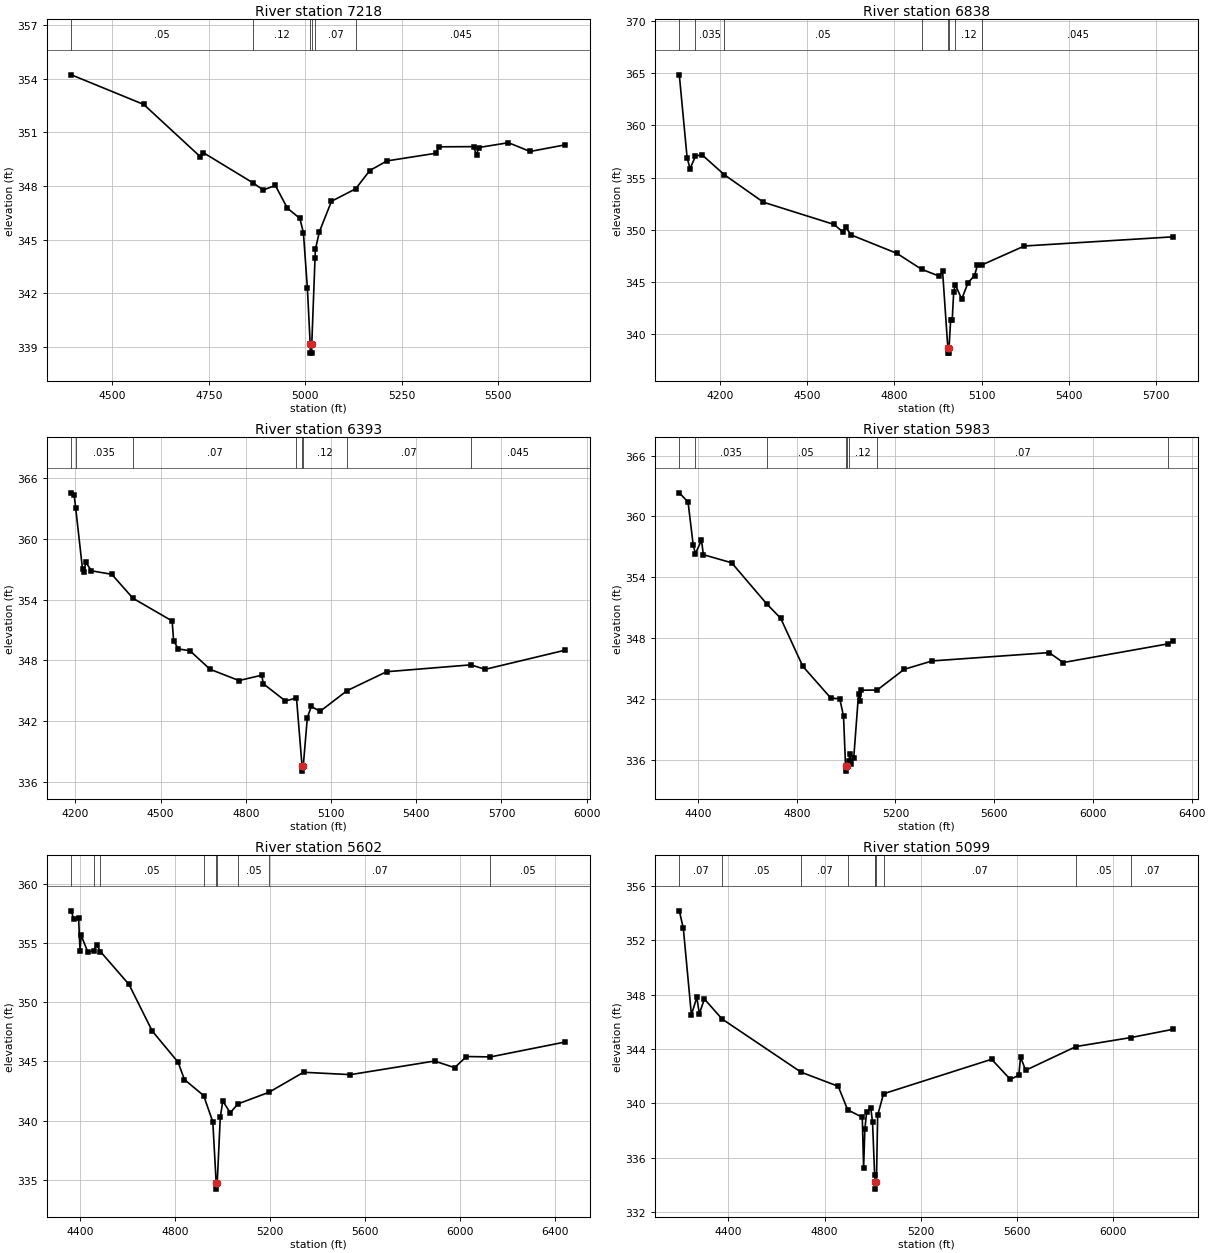
Type RM Length L Ch R = 1,7218,380,380,380
BEGIN DESCRIPTION:
WAELDER BRANCH 9.0
END DESCRIPTION:
XS GIS Cut Line= 3
      2511790.32     13801803.51      2511596.72     13801119.84
      2511335.41     13800614.11
#Sta/Elev= 30
  4393.9  354.22  4581.6  352.56  4727.8  349.64  4735.3  349.87  4864.7  348.17
  4891.2  347.77  4922.4  348.03  4953.6  346.76  4986.1  346.18  4995.2  345.38
  5005.6  342.26  5012.8  339.14  5013.1  338.64  5016.7  338.64  5016.9  339.14
  5025.4  343.98  5026.3  344.45  5036.7  345.44  5067.9  347.14  5130.7  347.84
  5167.2  348.86  5211.5  349.40  5338.8  349.83  5346.3  350.19  5436.3  350.20
  5443.9  349.72  5449.5  350.15  5526.4  350.42  5582.7  349.93  5673.7  350.30
#Mann=6,-1,0
  4393.9    0.05       0  4864.7    0.12       0  5012.8    0.05       0
  5016.9    0.12       0  5025.4    0.07       0  5130.7   0.045       0
Bank Sta=5012.8,5016.9
Exp/Cntr=0.3,0.1

Type RM Length L Ch R = 1,6838,445,445,445
BEGIN DESCRIPTION:
WAELDER BRANCH 8.0
END DESCRIPTION:
XS GIS Cut Line= 3
      2512098.91     13802051.61      2511975.00     13801125.00
      2511609.63     13800456.26
#Sta/Elev= 30
  4060.8  364.85  4087.6  356.91  4097.7  355.85  4116.4  357.05  4138.1  357.20
  4216.1  355.26  4349.6  352.64  4592.1  350.51  4622.4  349.80  4632.5  350.23
  4651.9  349.49  4808.0  347.74  4893.2  346.21  4954.1  345.55  4965.4  346.02
  4983.5  338.67  4983.8  338.17  4987.4  338.17  4987.6  338.67  4993.1  341.33
  4998.5  341.33  5003.7  344.06  5009.1  344.73  5031.2  343.35  5053.1  344.93
  5075.4  345.61  5085.3  346.62  5102.5  346.65  5246.4  348.44  5757.7  349.32
#Mann=8,-1,0
  4060.8    0.07       0  4116.4   0.035       0  4216.1    0.05       0
  4893.2    0.07       0  4983.5    0.05       0  4987.6    0.07       0
  5009.1    0.12       0  5102.5   0.045       0
Bank Sta=4983.5,4987.6
Exp/Cntr=0.3,0.1

Type RM Length L Ch R = 1,6393,410,410,410
BEGIN DESCRIPTION:
XS7938
END DESCRIPTION:
XS GIS Cut Line= 3
      2512498.24     13801924.57      2512274.37     13800768.91
      2511754.05     13800557.16
#Sta/Elev= 30
  4185.6  364.53  4195.4  364.29  4201.0  362.99  4224.9  356.99  4230.0  356.70
  4236.1  357.68  4256.5  356.83  4327.8  356.49  4402.6  354.12  4540.5  351.88
  4545.6  349.94  4562.0  349.12  4602.8  348.95  4674.1  347.11  4775.9  346.00
  4856.1  346.53  4861.2  345.69  4938.9  343.99  4978.3  344.27  4997.9  337.56
  4998.2  337.06  5002.1  337.56  5016.5  342.35  5030.6  343.44  5061.2  342.96
  5156.2  345.00  5295.4  346.87  5591.9  347.55  5642.8  347.11  5924.5  349.00
#Mann=8,-1,0
  4185.6    0.12       0  4201.0   0.035       0  4402.6    0.07       0
  4978.3    0.12       0  4997.9    0.05       0  5002.1    0.12       0
  5156.2    0.07       0  5591.9   0.045       0
Bank Sta=4997.9,5002.1
Exp/Cntr=0.3,0.1

Type RM Length L Ch R = 1,5983,381,381,381
BEGIN DESCRIPTION:
XS7937
END DESCRIPTION:
XS GIS Cut Line= 3
      2512921.77     13801779.35      2512697.90     13800908.08
      2511879.74     13800171.13
#Sta/Elev= 30
  4324.4  362.32  4359.9  361.41  4380.5  357.21  4389.8  356.33  4414.3  357.65
  4421.8  356.22  4536.5  355.42  4678.4  351.37  4735.0  349.95  4824.5  345.22
  4938.7  342.06  4974.3  342.02  4989.7  340.30  4997.9  335.37  4998.2  334.87
  5002.2  335.37  5011.3  335.87  5015.1  336.55  5020.7  335.54  5031.0  336.15
  5050.6  342.51  5055.8  341.75  5062.0  342.85  5126.2  342.87  5235.3  344.91
  5348.9  345.74  5822.8  346.56  5879.6  345.58  6303.4  347.42  6325.1  347.73
#Mann=8,-1,0
  4324.4    0.07       0  4389.8   0.035       0  4678.4    0.05       0
  4997.9    0.05       0  5002.2    0.05       0  5011.3    0.12       0
  5126.2    0.07       0  6303.4    0.05       0
Bank Sta=4997.9,5002.2
Exp/Cntr=0.3,0.1

Type RM Length L Ch R = 1,5602,503,503,503
BEGIN DESCRIPTION:
XS7936
END DESCRIPTION:
XS GIS Cut Line= 3
      2513290.86     13801634.15      2513060.93     13800889.92
      2512120.88     13799990.73
#Sta/Elev= 30
  4362.4  357.73  4372.0  357.01  4392.9  357.15  4398.7  354.35  4403.9  355.65
  4431.3  354.26  4455.7  354.35  4469.2  354.86  4485.0  354.28  4605.0  351.51
  4702.9  347.57  4811.6  344.94  4838.7  343.46  4919.6  342.11  4958.1  339.88
  4972.3  334.70  4972.6  334.20  4976.6  334.70  4989.5  340.26  5000.0  341.65
  5031.4  340.66  5064.5  341.41  5194.8  342.39  5340.1  344.08  5537.9  343.88
  5891.7  345.03  5976.6  344.47  6026.0  345.41  6127.5  345.38  6442.2  346.64
#Mann=9,-1,0
  4362.4    0.05       0  4455.7    0.07       0  4485.0    0.05       0
  4919.6    0.12       0  4972.3    0.05       0  4976.6    0.12       0
  5064.5    0.05       0  5194.8    0.07       0  6127.5    0.05       0
Bank Sta=4972.3,4976.6
Exp/Cntr=0.3,0.1

Type RM Length L Ch R = 1,5099,362,362,362
BEGIN DESCRIPTION:
WAELDER BRANCH 7.0
END DESCRIPTION:
XS GIS Cut Line= 3
      2513625.00     13801524.99      2513405.81     13800774.97
      2512503.34     13799879.55
#Sta/Elev= 30
  4196.1  354.17  4212.8  352.89  4246.3  346.52  4269.0  347.79  4279.4  346.59
  4300.3  347.68  4373.6  346.21  4702.4  342.29  4856.6  341.25  4895.9  339.52
  4956.6  338.97  4962.2  335.25  4967.4  338.09  4974.9  339.39  4992.2  339.63
  4999.3  338.61  5007.9  334.75  5011.2  334.18  5011.5  333.68  5015.5  334.18
  5020.5  339.11  5044.9  340.70  5494.2  343.24  5572.0  341.76  5607.4  342.07
  5614.4  343.40  5635.7  342.43  5845.4  344.18  6073.3  344.84  6248.8  345.45
#Mann=10,-1,0
  4196.1    0.07       0  4373.6    0.05       0  4702.4    0.07       0
  4895.9    0.12       0  5007.9    0.05       0  5011.2    0.05       0
  5015.5    0.05       0  5044.9    0.07       0  5845.4    0.05       0
  6073.3    0.07       0
Bank Sta=5011.2,5015.5
Exp/Cntr=0.3,0.1

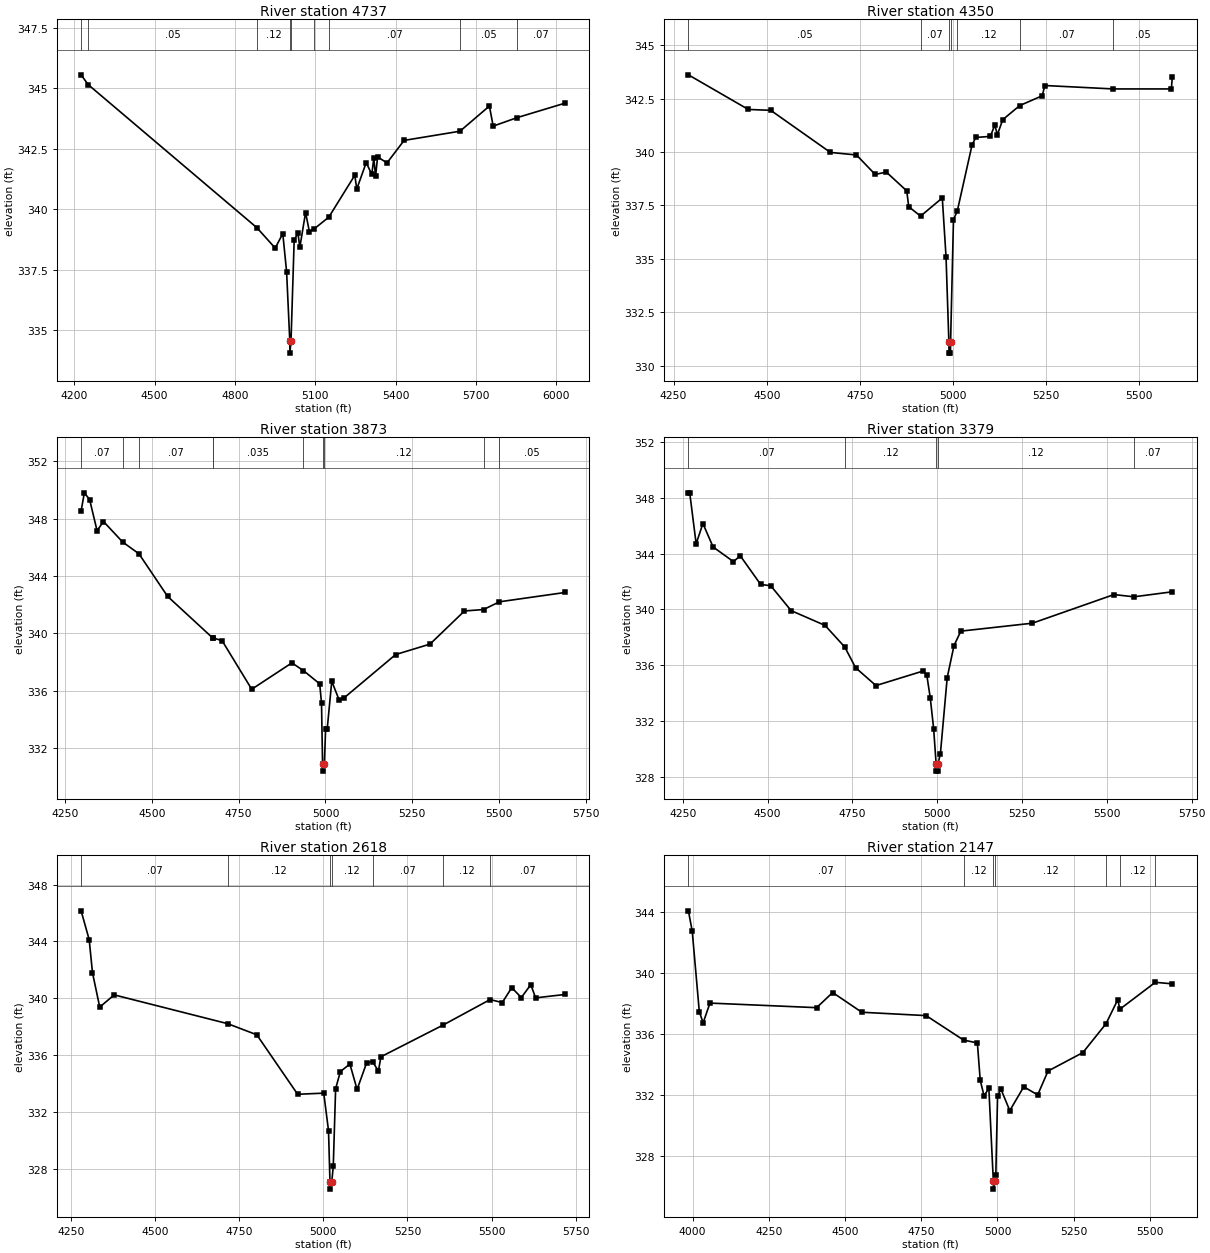
Type RM Length L Ch R = 1,4737,387,387,387
BEGIN DESCRIPTION:
XS7935
END DESCRIPTION:
XS GIS Cut Line= 3
      2513768.84     13801301.37      2513744.64     13800702.36
      2512929.02     13799811.68
#Sta/Elev= 30
  4225.9  345.55  4251.8  345.15  4882.5  339.23  4950.7  338.39  4979.0  338.99
  4993.2  337.42  5005.2  334.55  5005.5  334.05  5009.7  334.55  5021.6  338.74
  5035.8  339.00  5042.6  338.42  5064.1  339.86  5078.3  339.07  5096.9  339.19
  5150.9  339.67  5247.9  341.40  5255.3  340.83  5290.4  341.92  5311.4  341.44
  5318.8  342.10  5325.6  341.36  5333.0  342.16  5368.1  341.91  5432.0  342.84
  5640.7  343.22  5750.5  344.26  5764.7  343.43  5853.6  343.78  6033.1  344.38
#Mann=9,-1,0
  4225.9    0.07       0  4251.8    0.05       0  4882.5    0.12       0
  5005.2    0.05       0  5009.7    0.12       0  5096.9    0.05       0
  5150.9    0.07       0  5640.7    0.05       0  5853.6    0.07       0
Bank Sta=5005.2,5009.7
Exp/Cntr=0.3,0.1

Type RM Length L Ch R = 1,4350,477,477,477
BEGIN DESCRIPTION:
XS7934
END DESCRIPTION:
XS GIS Cut Line= 3
      2513883.80     13801095.68      2513920.10     13800284.88
      2513569.62     13799946.48
#Sta/Elev= 30
  4289.8  343.61  4450.6  341.99  4510.7  341.95  4670.9  339.98  4740.9  339.86
  4791.0  338.95  4821.0  339.06  4875.8  338.18  4881.1  337.44  4912.9  337.00
  4971.2  337.85  4981.2  335.10  4988.9  331.09  4989.2  330.59  4993.1  330.59
  4993.4  331.09  5001.2  336.84  5011.3  337.23  5051.2  340.34  5061.2  340.68
  5100.3  340.73  5111.9  341.26  5119.1  340.81  5133.3  341.51  5178.8  342.17
  5239.3  342.63  5246.5  343.11  5430.0  342.95  5585.8  342.95  5588.6  343.51
#Mann=7,-1,0
  4289.8    0.05       0  4912.9    0.07       0  4988.9    0.05       0
  4993.4    0.07       0  5011.3    0.12       0  5178.8    0.07       0
  5430.0    0.05       0
Bank Sta=4988.9,4993.4
Exp/Cntr=0.3,0.1

Type RM Length L Ch R = 1,3873,494,494,494
BEGIN DESCRIPTION:
WAELDER BRANCH 6.0
END DESCRIPTION:
XS GIS Cut Line= 3
      2514573.54     13801137.97      2514325.48     13800478.49
      2513829.65     13800000.80
#Sta/Elev= 30
  4296.6  348.54  4305.9  349.80  4321.1  349.33  4342.5  347.16  4361.0  347.80
  4416.1  346.37  4463.0  345.55  4545.5  342.58  4675.7  339.67  4676.4  339.68
  4702.4  339.49  4787.7  336.10  4903.3  337.94  4936.6  337.40  4983.3  336.48
  4988.6  335.15  4991.6  330.89  4992.0  330.39  4996.8  330.89  5000.4  333.33
  5005.0  333.33  5018.1  336.66  5039.4  335.35  5053.6  335.50  5202.0  338.52
  5301.0  339.25  5400.1  341.56  5455.1  341.66  5500.8  342.20  5689.7  342.85
#Mann=10,-1,0
  4296.6    0.07       0  4416.1   0.035       0  4463.0    0.07       0
  4675.7    0.12       0  4676.4   0.035       0  4936.6    0.12       0
  4991.6    0.05       0  4996.8    0.12       0  5455.1    0.07       0
  5500.8    0.05       0
Bank Sta=4991.6,4996.8
Exp/Cntr=0.3,0.1

Type RM Length L Ch R = 1,3379,761,761,761
BEGIN DESCRIPTION:
WAELDER BRANCH 5.0
END DESCRIPTION:
XS GIS Cut Line= 3
      2514742.97     13801107.76      2514755.07     13800284.88
      2514319.40     13799867.36
#Sta/Elev= 30
  4266.7  348.35  4270.6  348.35  4289.5  344.70  4309.5  346.15  4339.5  344.47
  4399.5  343.42  4419.5  343.84  4479.5  341.79  4509.5  341.69  4569.5  339.91
  4669.5  338.85  4727.6  337.30  4759.5  335.82  4819.5  334.54  4959.5  335.59
  4969.5  335.27  4979.5  333.67  4989.5  331.46  4996.9  328.91  4997.3  328.41
  5001.7  328.41  5002.1  328.91  5009.5  329.67  5029.5  335.11  5049.5  337.40
  5069.6  338.44  5280.7  339.01  5521.0  341.06  5580.1  340.90  5693.1  341.26
#Mann=5,-1,0
  4266.7    0.07       0  4727.6    0.12       0  4996.9    0.05       0
  5002.1    0.12       0  5580.1    0.07       0
Bank Sta=4996.9,5002.1
Exp/Cntr=0.3,0.1

Type RM Length L Ch R = 1,2618,471,471,471
BEGIN DESCRIPTION:
WAELDER BRANCH 4.0
END DESCRIPTION:
XS GIS Cut Line= 3
      2515469.04     13800865.75      2515196.75     13800399.84
      2514573.53     13799752.41
#Sta/Elev= 30
  4280.1  346.16  4304.1  344.13  4313.9  341.80  4335.4  339.38  4378.4  340.24
  4716.0  338.21  4802.2  337.43  4923.6  333.24  5001.2  333.32  5015.4  330.67
  5019.7  327.06  5020.1  326.56  5025.0  327.06  5029.5  328.17  5036.5  333.63
  5050.6  334.84  5078.9  335.37  5100.3  333.58  5128.6  335.45  5146.3  335.53
  5163.8  334.88  5171.0  335.88  5355.5  338.11  5495.6  339.91  5531.7  339.70
  5560.0  340.75  5588.3  340.05  5616.6  340.96  5630.8  340.03  5718.4  340.27
#Mann=7,-1,0
  4280.1    0.07       0  4716.0    0.12       0  5019.7    0.05       0
  5025.0    0.12       0  5146.3    0.07       0  5355.5    0.12       0
  5495.6    0.07       0
Bank Sta=5019.7,5025
Exp/Cntr=0.3,0.1

Type RM Length L Ch R = 1,2147,723,723,723
BEGIN DESCRIPTION:
WAELDER BRANCH 3.0
END DESCRIPTION:
XS GIS Cut Line= 3
      2515832.19     13800725.81      2515366.17     13799940.00
      2514755.10     13799655.64
#Sta/Elev= 30
  3986.1  344.08  3998.7  342.74  4021.9  337.47  4034.5  336.75  4056.8  338.04
  4406.7  337.74  4459.4  338.73  4554.9  337.44  4766.0  337.22  4888.7  335.62
  4934.1  335.43  4943.4  332.99  4956.1  331.96  4971.7  332.47  4986.5  326.36
  4986.9  325.86  4991.8  326.36  4994.6  326.80  5000.3  331.96  5011.3  332.41
  5040.4  331.00  5086.2  332.56  5131.9  332.03  5165.8  333.59  5280.2  334.80
  5356.1  336.69  5394.6  338.26  5401.5  337.64  5517.9  339.40  5573.7  339.30
#Mann=7,-1,0
  3986.1    0.07       0  4888.7    0.12       0  4986.5    0.05       0
  4991.8    0.12       0  5356.1    0.07       0  5401.5    0.12       0
  5517.9    0.07       0
Bank Sta=4986.5,4991.8
Exp/Cntr=0.3,0.1