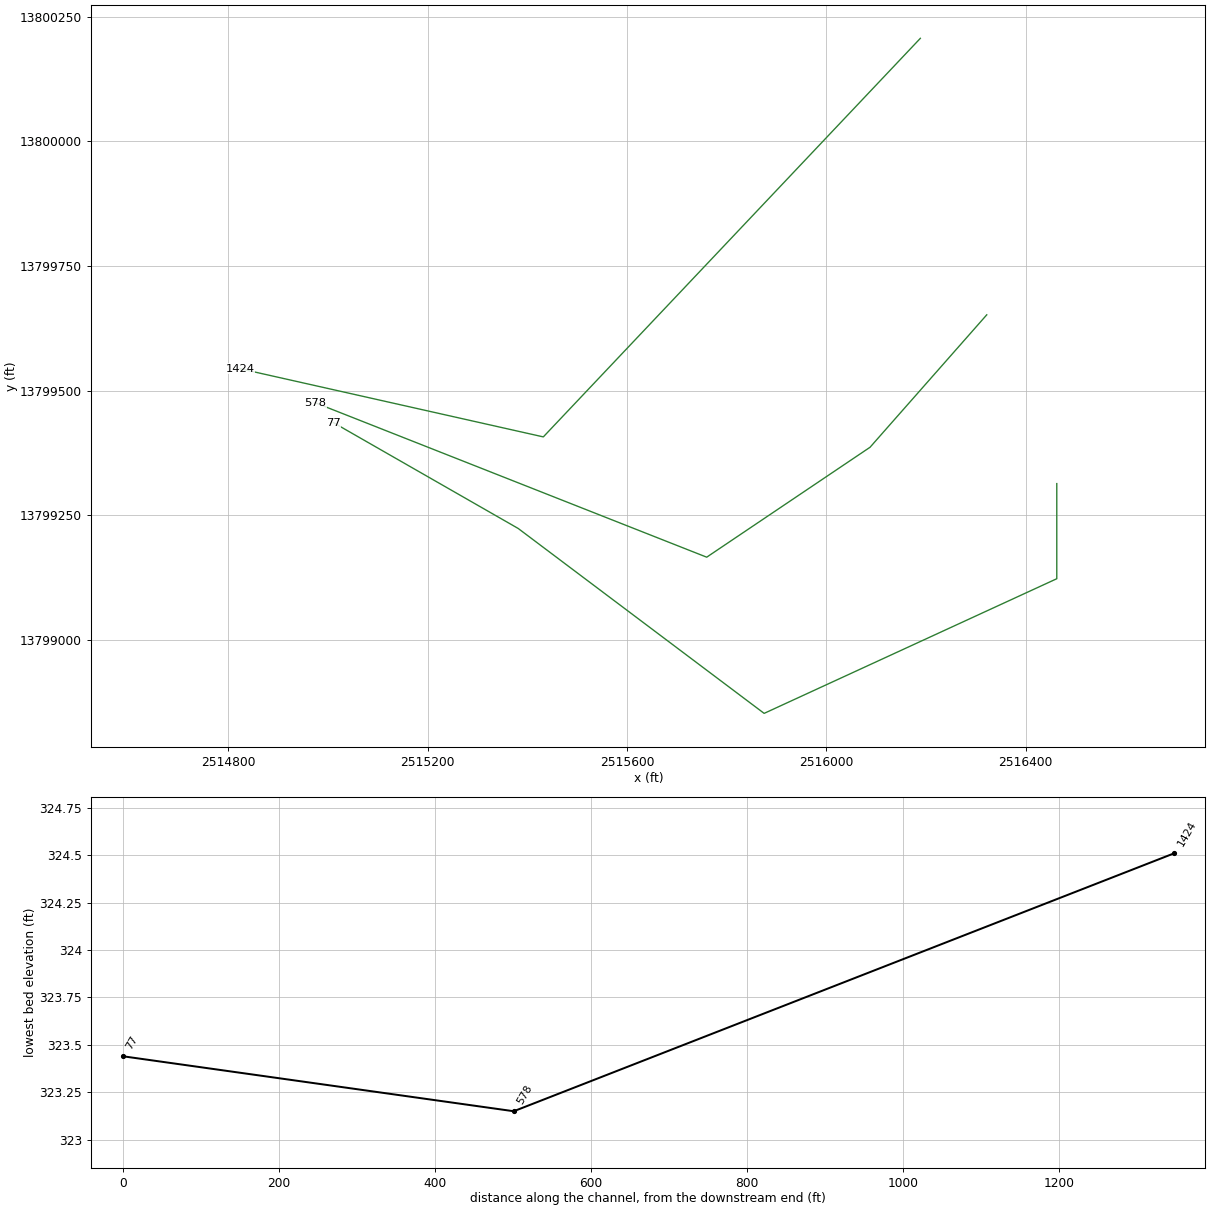
HEC-RAS study WAELDER BRANCH.prj: WAELDER BRANCH Base Level Engineering

--- WAELDER BRANCH.g01 (geometry) --- (continued)

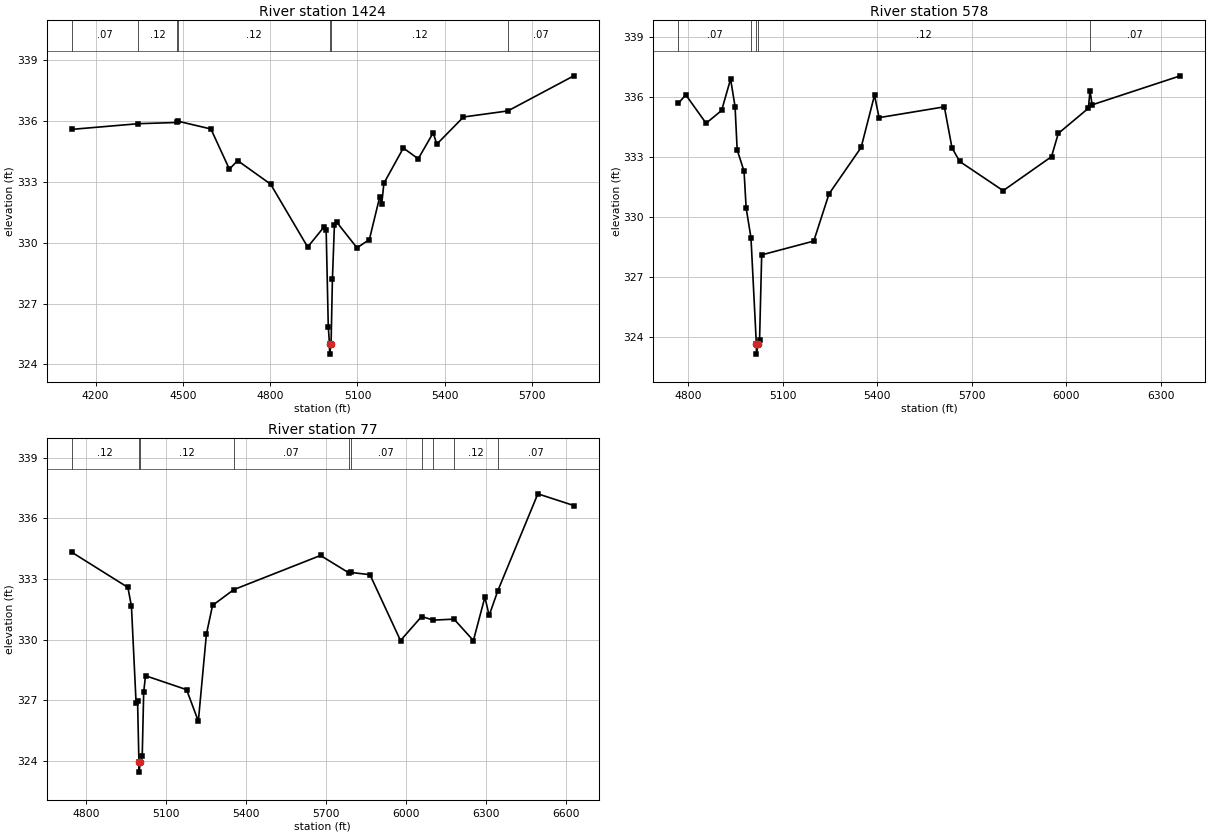
Type RM Length L Ch R = 1,1424,846,846,846
BEGIN DESCRIPTION:
WAELDER BRANCH 2.0
END DESCRIPTION:
XS GIS Cut Line= 3
      2516188.91     13800206.94      2515432.23     13799407.03
      2514823.33     13799543.94
#Sta/Elev= 30
  4118.2  335.59  4346.8  335.87  4479.2  335.93  4483.9  335.99  4596.3  335.61
  4659.8  333.63  4688.1  334.05  4801.4  332.89  4928.8  329.79  4985.5  330.79
  4992.3  330.63  4999.6  325.87  5003.8  325.01  5004.2  324.51  5009.2  325.01
  5013.8  328.20  5020.7  330.88  5027.9  331.03  5098.3  329.75  5140.8  330.16
  5176.4  332.26  5183.3  331.91  5190.6  332.93  5257.5  334.67  5308.7  334.14
  5360.0  335.42  5372.5  334.86  5464.2  336.20  5616.7  336.50  5843.4  338.23
#Mann=7,-1,0
  4118.2    0.07       0  4346.8    0.12       0  4479.2    0.07       0
  4483.9    0.12       0  5003.8    0.05       0  5009.2    0.12       0
  5616.7    0.07       0
Bank Sta=5003.8,5009.2
Exp/Cntr=0.3,0.1

Type RM Length L Ch R = 1,578,501,501,501
BEGIN DESCRIPTION:
WAELDER BRANCH 1.0
END DESCRIPTION:
XS GIS Cut Line= 4
      2516322.22     13799652.05      2516088.01     13799386.26
      2515760.13     13799165.62      2514974.61     13799475.50
#Sta/Elev= 30
  4768.6  335.68  4792.5  336.11  4857.0  334.69  4906.4  335.33  4934.8  336.90
  4949.0  335.52  4955.7  333.36  4977.5  332.29  4984.2  330.45  4999.5  328.97
  5016.6  323.65  5017.0  323.15  5022.0  323.65  5026.8  323.87  5033.5  328.11
  5198.8  328.80  5247.3  331.16  5349.2  333.48  5391.7  336.09  5406.2  334.97
  5613.4  335.51  5637.7  333.46  5662.1  332.78  5800.1  331.32  5953.6  333.02
  5975.1  334.18  6070.7  335.44  6075.8  336.31  6082.6  335.61  6362.5  337.06
#Mann=5,-1,0
  4768.6    0.07       0  4999.5    0.12       0  5016.6    0.05       0
  5022.0    0.12       0  6075.8    0.07       0
Bank Sta=5016.6,5022
Exp/Cntr=0.3,0.1

Type RM Length L Ch R = 1,77,0,0,0
BEGIN DESCRIPTION:
XS7933
END DESCRIPTION:
XS GIS Cut Line= 5
      2516462.75     13799313.30      2516462.75     13799122.38
      2515875.43     13798852.14      2515381.79     13799223.27
      2515010.68     13799435.84
#Sta/Elev= 30
  4745.2  334.32  4955.7  332.58  4969.0  331.64  4986.4  326.85  4991.9  326.95
  4997.0  323.94  4997.4  323.44  5002.4  323.94  5009.4  324.23  5014.9  327.40
  5021.7  328.21  5175.7  327.52  5219.8  325.96  5250.1  330.27  5273.1  331.69
  5352.8  332.47  5678.0  334.16  5782.9  333.31  5791.3  333.32  5863.3  333.21
  5977.9  329.95  6057.0  331.14  6101.6  330.96  6178.6  331.01  6251.2  329.95
  6294.4  332.10  6310.2  331.19  6343.0  332.42  6492.9  337.21  6627.9  336.63
#Mann=10,-1,0
  4745.2    0.12       0  4997.0    0.05       0  5002.4    0.12       0
  5352.8    0.07       0  5782.9    0.12       0  5791.3    0.07       0
  6057.0    0.12       0  6101.6    0.07       0  6178.6    0.12       0
  6343.0    0.07       0
Bank Sta=4997,5002.4
Exp/Cntr=0.3,0.1

Chan Stop Cuts=-1