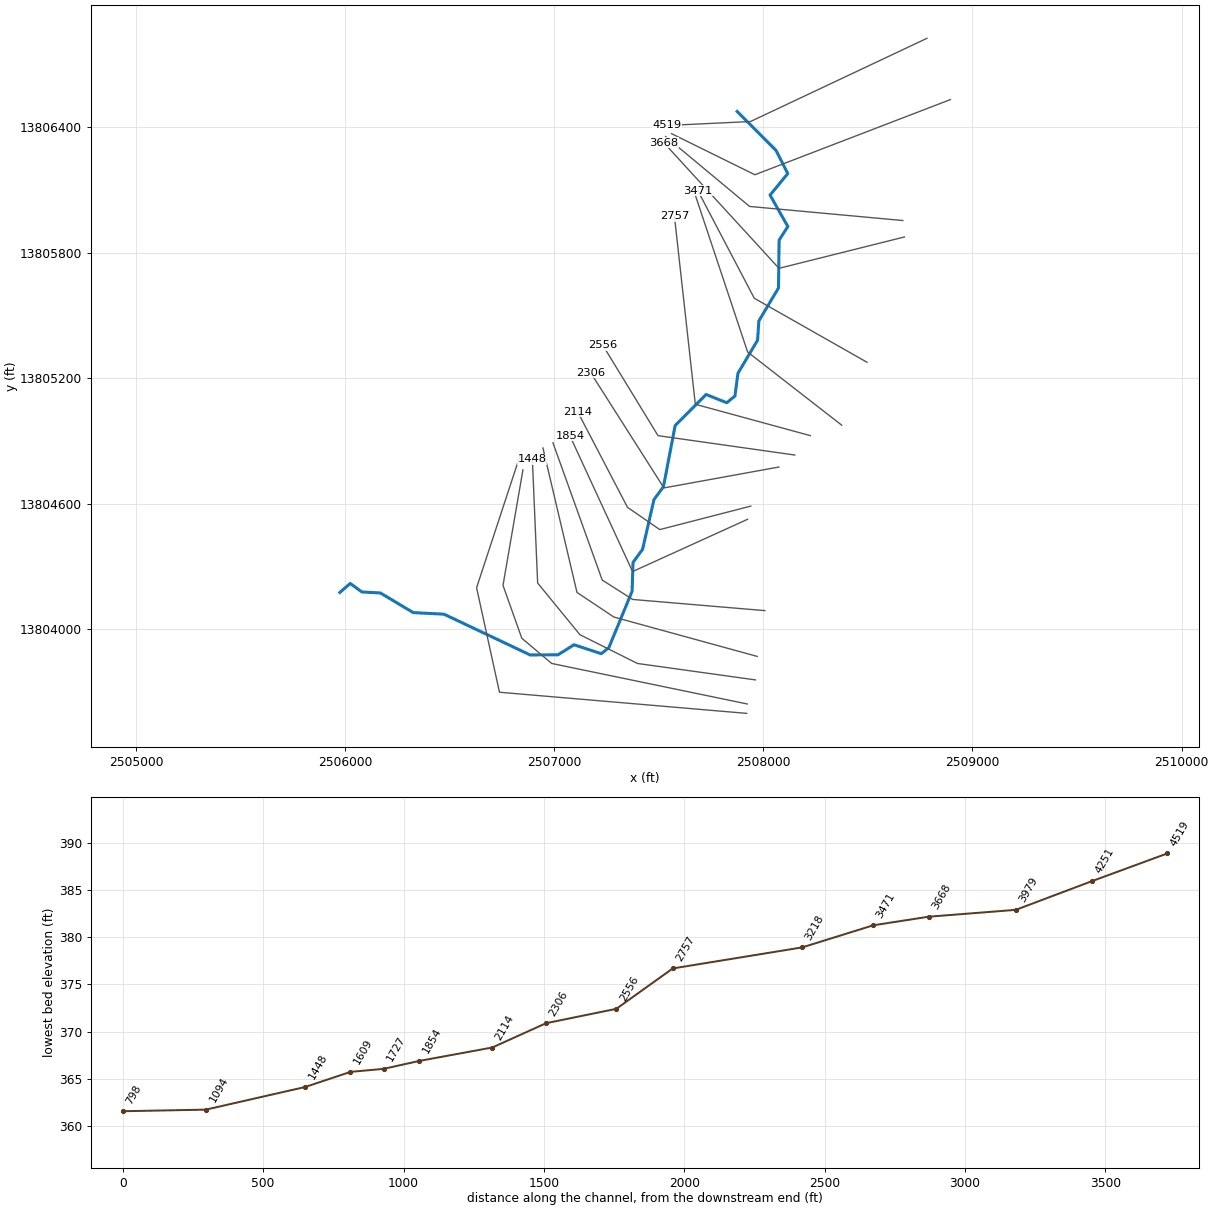
--- WEST DRAIN.prj (project) ---

Proj Title=WEST DRAIN Base Level Engineering
Current Plan=p01
Default Exp/Contr=0.3,0.1
English Units
Geom File=g01
Flow File=f01
Plan File=p01
BEGIN DESCRIPTION:
WEST DRAIN
END DESCRIPTION:

--- WEST DRAIN.p01 (plan) ---

Plan Title=Multiple Run
Short Identifier=Multiple
Geom File=g01
Flow File=f01
Subcritical Flow
K Sum by GR= 0
Std Step Tol= 0.01
Critical Tol= 0.01
Num of Std Step Trials= 20
Max Error Tol= 0.3
Flow Tol Ratio= 0.001
Split Flow NTrial= 30
Split Flow Tol= 0.02
Split Flow Ratio= 0.02
Log Output Level= 0
Friction Slope Method= 1
Unsteady Friction Slope Method= 2
Unsteady Bridges Friction Slope Method= 1
Parabolic Critical Depth
Global Vel Dist=  1 , 1 , 1
Global Log Level= 0
CheckData=True
Encroach Param= -1, 0, 0, 0
BEGIN DESCRIPTION:
Multiple Run
END DESCRIPTION:

--- WEST DRAIN.f01 (steady flow) ---

Flow Title=Multiple
Number of Profiles=7
Profile Names=10-year,25-year,50-year,1pct_min,100-year,1pct_plu,500-year
River Rch & RM= WEST DRAIN,Reach-1,4519
     282     428     552     347     692    1380    1070
Boundary for River Rch & Prof#=WEST DRAIN,Reach-1,1
Up Type=0
Dn Type=3
Dn Slope=0.005
Boundary for River Rch & Prof#=WEST DRAIN,Reach-1,2
Up Type=0
Dn Type=3
Dn Slope=0.005
Boundary for River Rch & Prof#=WEST DRAIN,Reach-1,3
Up Type=0
Dn Type=3
Dn Slope=0.005
Boundary for River Rch & Prof#=WEST DRAIN,Reach-1,4
Up Type=0
Dn Type=3
Dn Slope=0.005
Boundary for River Rch & Prof#=WEST DRAIN,Reach-1,5
Up Type=0
Dn Type=3
Dn Slope=0.005
Boundary for River Rch & Prof#=WEST DRAIN,Reach-1,6
Up Type=0
Dn Type=3
Dn Slope=0.005
Boundary for River Rch & Prof#=WEST DRAIN,Reach-1,7
Up Type=0
Dn Type=3
Dn Slope=0.005

--- WEST DRAIN.g01 (geometry) ---

Geom Title=Existing Conditions

River Reach=WEST DRAIN,Reach-1
Reach XY= 30
      2507875.00     13806475.00      2508061.40     13806288.21
      2508117.15     13806178.23      2508032.31     13806075.09
      2508117.47     13805925.01      2508075.66     13805859.84
      2508072.76     13805630.93      2507978.83     13805473.42
      2507972.67     13805380.97      2507878.83     13805223.41
      2507864.49     13805114.48      2507825.33     13805082.25
      2507726.65     13805121.84      2507578.61     13804973.50
      2507522.73     13804680.94      2507477.36     13804619.02
      2507422.64     13804380.98      2507377.27     13804319.06
      2507372.73     13804180.94      2507261.39     13803910.97
      2507225.31     13803882.23      2507095.10     13803925.09
      2507019.06     13803877.25      2506885.50     13803876.19
      2506473.44     13804071.24      2506326.56     13804078.76
      2506169.03     13804172.67      2506080.88     13804177.46
      2506024.86     13804218.10      2505975.00     13804175.00

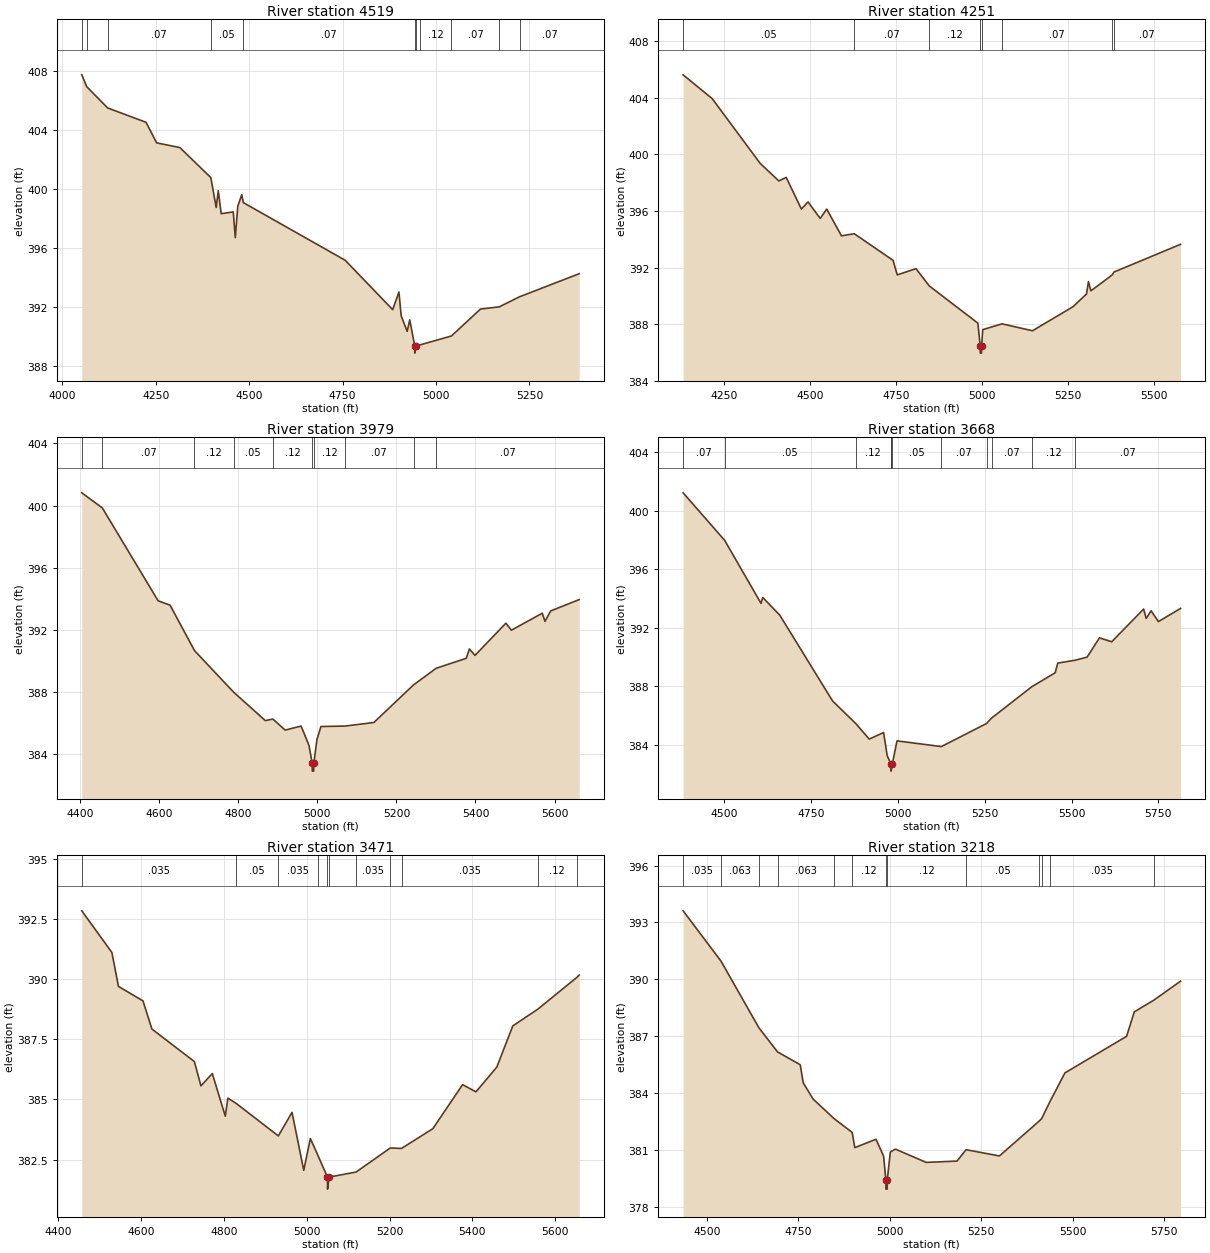
Type RM Length L Ch R = 1,4519,268,268,268
BEGIN DESCRIPTION:
WEST DRAIN 8.0
END DESCRIPTION:
XS GIS Cut Line= 3
      2508782.42     13806824.74      2507938.73     13806426.90
      2507541.16     13806408.10
#Sta/Elev= 30
  4052.3  407.71  4065.5  406.91  4121.5  405.47  4224.2  404.50  4252.5  403.11
  4314.8  402.79  4397.5  400.76  4411.9  398.74  4417.5  399.87  4425.3  398.32
  4457.5  398.44  4463.0  396.70  4469.6  398.81  4480.3  399.61  4484.4  399.07
  4757.0  395.17  4884.1  391.83  4900.8  393.02  4906.9  391.40  4922.9  390.36
  4929.7  391.14  4943.0  389.39  4943.2  388.89  4947.0  389.39  4956.3  389.44
  5041.3  390.05  5119.0  391.87  5169.3  392.02  5223.5  392.70  5383.1  394.26
#Mann=11,-1,0
  4052.3   0.035       0  4065.5    0.05       0  4121.5    0.07       0
  4397.5    0.05       0  4484.4    0.07       0  4943.0    0.05       0
  4947.0    0.07       0  4956.3    0.12       0  5041.3    0.07       0
  5169.3   0.035       0  5223.5    0.07       0
Bank Sta=4943,4947
Exp/Cntr=0.3,0.1

Type RM Length L Ch R = 1,4251,272,272,272
BEGIN DESCRIPTION:
H21638
END DESCRIPTION:
XS GIS Cut Line= 3
      2508894.71     13806531.87      2507959.84     13806172.52
      2507561.20     13806369.03
#Sta/Elev= 30
  4130.6  405.63  4215.0  403.95  4354.3  399.38  4408.8  398.13  4430.3  398.38
  4474.4  396.14  4493.7  396.65  4529.0  395.48  4548.1  396.14  4591.0  394.25
  4628.0  394.40  4740.9  392.52  4753.0  391.49  4807.7  391.93  4845.7  390.72
  4987.4  388.08  4994.3  386.46  4994.5  385.96  4998.0  385.96  4998.3  386.46
  5001.6  387.62  5057.6  388.03  5146.1  387.54  5264.0  389.24  5303.3  390.14
  5308.9  391.02  5315.9  390.36  5378.1  391.49  5383.0  391.69  5576.6  393.65
#Mann=8,-1,0
  4130.6    0.05       0  4628.0    0.07       0  4845.7    0.12       0
  4994.3    0.05       0  4998.3    0.12       0  5057.6    0.07       0
  5378.1   0.035       0  5383.0    0.07       0
Bank Sta=4994.3,4998.3
Exp/Cntr=0.3,0.1

Type RM Length L Ch R = 1,3979,311,311,311
BEGIN DESCRIPTION:
H21637
END DESCRIPTION:
XS GIS Cut Line= 3
      2508667.33     13805953.54      2507934.57     13806020.92
      2507533.14     13806354.98
#Sta/Elev= 30
  4404.3  400.82  4456.2  399.85  4597.4  393.87  4627.6  393.59  4689.3  390.67
  4788.4  387.99  4868.6  386.16  4887.6  386.26  4918.8  385.55  4959.0  385.81
  4979.0  384.56  4987.1  383.41  4987.3  382.91  4990.8  382.91  4991.1  383.41
  4999.1  384.94  5009.2  385.78  5070.1  385.81  5143.1  386.04  5243.4  388.46
  5300.7  389.53  5376.7  390.17  5384.6  390.77  5398.9  390.36  5477.0  392.43
  5490.9  391.98  5568.9  393.07  5575.9  392.55  5590.3  393.22  5662.4  393.95
#Mann=10,-1,0
  4404.3    0.05       0  4456.2    0.07       0  4689.3    0.12       0
  4788.4    0.05       0  4887.6    0.12       0  4987.1    0.05       0
  4991.1    0.12       0  5070.1    0.07       0  5243.4    0.12       0
  5300.7    0.07       0
Bank Sta=4987.1,4991.1
Exp/Cntr=0.3,0.1

Type RM Length L Ch R = 1,3668,197,197,197
BEGIN DESCRIPTION:
WEST DRAIN 7.0
END DESCRIPTION:
XS GIS Cut Line= 3
      2508675.02     13805875.00      2508075.00     13805725.00
      2507525.02     13806324.98
#Sta/Elev= 30
  4381.6  401.22  4501.2  397.97  4605.8  393.66  4611.0  394.06  4659.9  392.85
  4812.0  386.98  4878.5  385.44  4917.6  384.37  4958.9  384.82  4969.2  383.25
  4979.3  382.69  4980.0  382.68  4980.3  382.18  4984.0  382.68  4997.5  384.25
  5125.3  383.86  5255.4  385.44  5269.9  385.81  5385.5  387.95  5453.0  388.91
  5460.4  389.57  5511.0  389.77  5544.9  389.98  5580.6  391.30  5615.8  391.03
  5707.7  393.27  5715.1  392.63  5729.2  393.15  5750.2  392.41  5814.0  393.31
#Mann=11,-1,0
  4381.6    0.07       0  4501.2    0.05       0  4878.5    0.12       0
  4979.3    0.05       0  4980.0    0.05       0  4984.0    0.05       0
  5125.3    0.07       0  5255.4    0.12       0  5269.9    0.07       0
  5385.5    0.12       0  5511.0    0.07       0
Bank Sta=4980,4984
Exp/Cntr=0.3,0.1

Type RM Length L Ch R = 1,3471,253,253,253
BEGIN DESCRIPTION:
H21636
END DESCRIPTION:
XS GIS Cut Line= 3
      2508496.06     13805275.82      2507957.03     13805581.83
      2507687.51     13806095.60
#Sta/Elev= 30
  4457.6  392.83  4530.2  391.10  4546.1  389.69  4605.2  389.09  4626.8  387.92
  4729.2  386.57  4745.1  385.56  4772.5  386.07  4803.8  384.30  4810.0  385.05
  4830.1  384.83  4931.8  383.48  4964.8  384.46  4993.1  382.05  5009.0  383.37
  5026.3  382.71  5050.2  381.77  5050.5  381.27  5054.2  381.77  5119.4  381.98
  5201.9  382.98  5228.9  382.96  5304.5  383.78  5376.3  385.61  5408.5  385.31
  5458.9  386.34  5497.4  388.05  5557.4  388.74  5652.3  390.07  5657.6  390.16
#Mann=11,-1,0
  4457.6   0.035       0  4830.1    0.05       0  4931.8   0.035       0
  5026.3    0.05       0  5050.2   0.035       0  5054.2    0.05       0
  5119.4   0.035       0  5201.9    0.05       0  5228.9   0.035       0
  5557.4    0.12       0  5652.3    0.07       0
Bank Sta=5050.2,5054.2
Exp/Cntr=0.3,0.1

Type RM Length L Ch R = 1,3218,461,461,461
BEGIN DESCRIPTION:
WEST DRAIN 6.0
END DESCRIPTION:
XS GIS Cut Line= 3
      2508375.00     13804975.00      2507925.00     13805325.00
      2507674.99     13806075.04
#Sta/Elev= 30
  4434.7  393.61  4538.2  390.96  4642.0  387.44  4692.9  386.17  4755.0  385.49
  4763.2  384.54  4790.3  383.68  4847.6  382.65  4897.2  381.92  4904.3  381.12
  4962.3  381.56  4983.1  380.67  4989.2  379.43  4989.5  378.93  4993.0  378.93
  4993.2  379.43  5001.6  380.89  5015.3  381.04  5099.7  380.34  5184.0  380.41
  5208.6  381.01  5299.9  380.68  5409.4  382.53  5415.5  382.65  5438.6  383.56
  5479.1  385.06  5647.8  386.99  5668.9  388.28  5722.5  388.90  5795.4  389.90
#Mann=13,-1,0
  4434.7   0.035       0  4538.2   0.063       0  4642.0   0.035       0
  4692.9   0.063       0  4847.6   0.035       0  4897.2    0.12       0
  4989.2    0.05       0  4993.2    0.12       0  5208.6    0.05       0
  5409.4    0.12       0  5415.5    0.07       0  5438.6   0.035       0
  5722.5    0.12       0
Bank Sta=4989.2,4993.2
Exp/Cntr=0.3,0.1

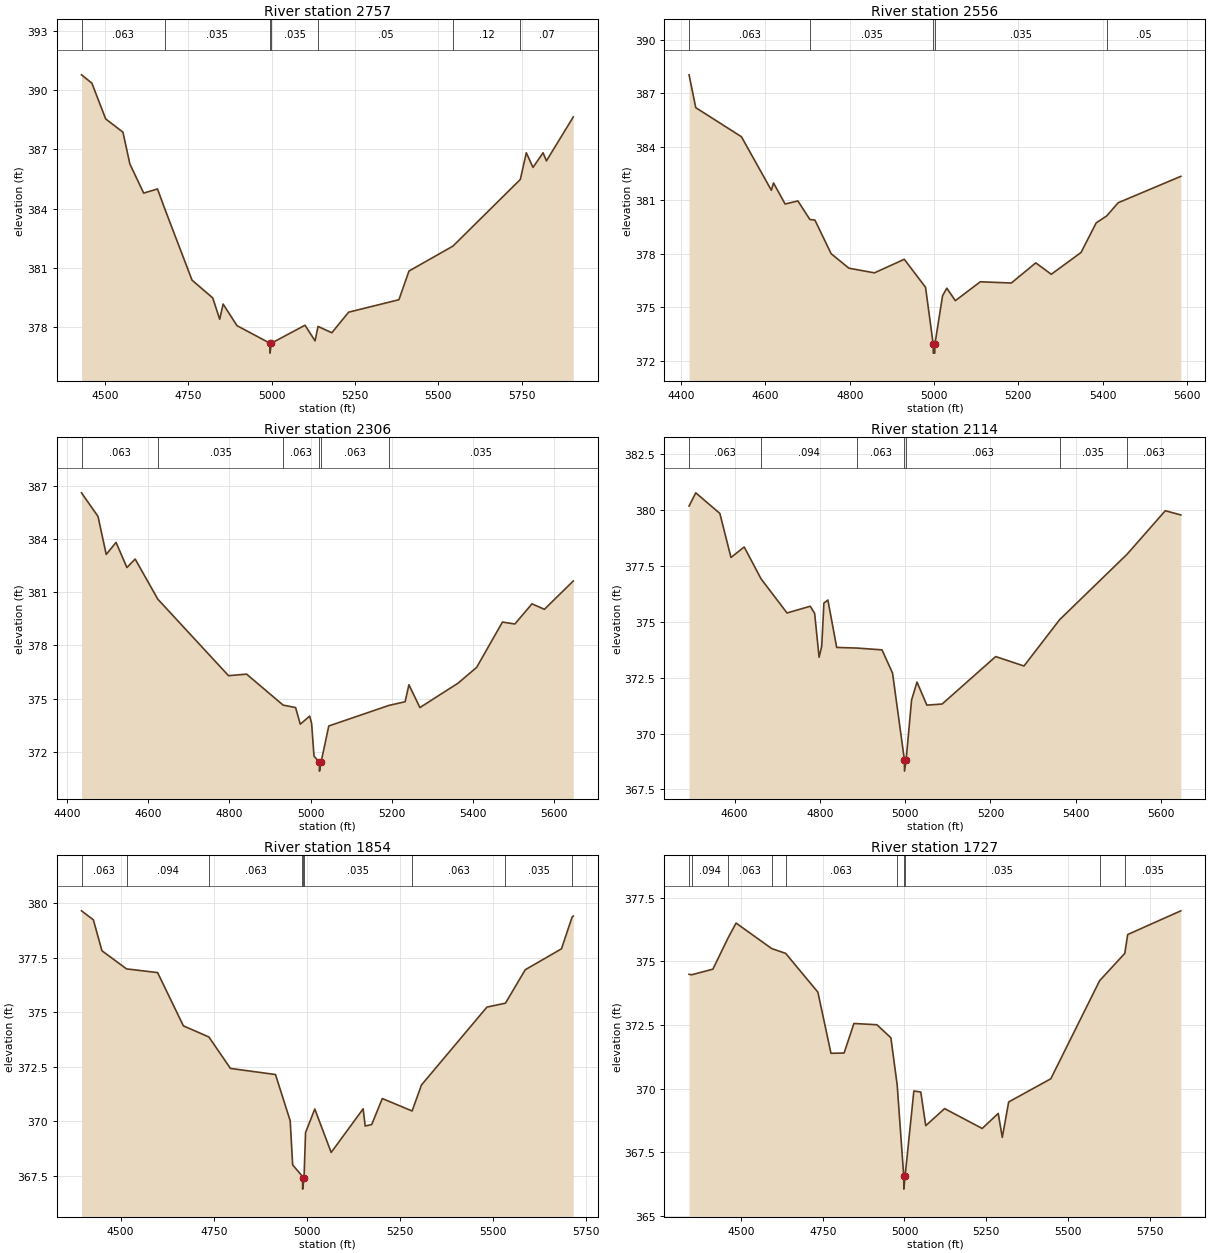
Type RM Length L Ch R = 1,2757,201,201,201
BEGIN DESCRIPTION:
WEST DRAIN 5.0
END DESCRIPTION:
XS GIS Cut Line= 3
      2508225.05     13804924.99      2507675.00     13805075.00
      2507575.00     13805975.03
#Sta/Elev= 30
  4429.5  390.77  4460.6  390.35  4502.1  388.54  4553.9  387.87  4574.7  386.26
  4616.1  384.79  4657.6  385.00  4679.3  384.00  4761.2  380.39  4823.4  379.49
  4844.2  378.41  4854.5  379.18  4896.0  378.09  4995.0  377.20  4995.3  376.70
  4999.0  377.20  5100.2  378.11  5130.4  377.32  5139.3  378.05  5180.7  377.73
  5231.1  378.77  5382.0  379.40  5412.2  380.85  5544.1  382.11  5746.3  385.48
  5764.3  386.83  5784.4  386.09  5814.6  386.83  5824.7  386.42  5905.2  388.64
#Mann=7,-1,0
  4429.5   0.063       0  4679.3   0.035       0  4995.0   0.035       0
  4999.0   0.035       0  5139.3    0.05       0  5544.1    0.12       0
  5746.3    0.07       0
Bank Sta=4995,4999
Exp/Cntr=0.3,0.1

Type RM Length L Ch R = 1,2556,250,250,250
BEGIN DESCRIPTION:
H21635
END DESCRIPTION:
XS GIS Cut Line= 3
      2508150.74     13804832.24      2507496.61     13804924.88
      2507232.70     13805357.24
#Sta/Elev= 30
  4418.6  388.02  4434.5  386.18  4542.9  384.55  4613.9  381.55  4619.0  381.96
  4646.6  380.78  4676.9  380.95  4705.4  379.91  4717.3  379.88  4755.9  377.99
  4798.1  377.18  4858.7  376.92  4929.4  377.68  4979.9  376.11  4998.1  372.92
  4998.3  372.42  5001.8  372.42  5002.1  372.92  5020.3  375.64  5030.4  376.06
  5050.6  375.36  5109.9  376.42  5183.5  376.35  5241.5  377.48  5278.3  376.84
  5348.9  378.06  5384.9  379.72  5409.8  380.11  5437.1  380.85  5585.8  382.33
#Mann=5,-1,0
  4418.6   0.063       0  4705.4   0.035       0  4998.1   0.035       0
  5002.1   0.035       0  5409.8    0.05       0
Bank Sta=4998.1,5002.1
Exp/Cntr=0.3,0.1

Type RM Length L Ch R = 1,2306,192,192,192
BEGIN DESCRIPTION:
WEST DRAIN 4.0
END DESCRIPTION:
XS GIS Cut Line= 3
      2508074.96     13804774.99      2507525.00     13804675.00
      2507175.00     13805225.00
#Sta/Elev= 30
  4435.8  386.62  4476.4  385.29  4496.7  383.14  4520.9  383.82  4547.6  382.40
  4567.9  382.88  4623.8  380.61  4797.9  376.29  4842.3  376.38  4932.2  374.63
  4963.0  374.49  4974.5  373.55  4997.7  374.01  5002.4  373.60  5008.3  371.75
  5021.6  371.40  5021.8  370.90  5025.6  371.40  5044.7  373.45  5192.5  374.61
  5232.7  374.82  5242.0  375.78  5269.1  374.49  5363.1  375.87  5408.8  376.76
  5472.3  379.32  5502.8  379.21  5545.1  380.35  5575.6  380.04  5646.7  381.64
#Mann=6,-1,0
  4435.8   0.063       0  4623.8   0.035       0  4932.2   0.063       0
  5021.6    0.05       0  5025.6   0.063       0  5192.5   0.035       0
Bank Sta=5021.6,5025.6
Exp/Cntr=0.3,0.1

Type RM Length L Ch R = 1,2114,260,260,260
BEGIN DESCRIPTION:
H21634
END DESCRIPTION:
XS GIS Cut Line= 4
      2507940.20     13804587.99      2507505.03     13804475.69
      2507350.62     13804582.37      2507111.99     13805039.98
#Sta/Elev= 30
  4493.3  380.17  4509.0  380.76  4565.5  379.84  4591.6  377.87  4622.6  378.34
  4662.0  376.92  4723.0  375.39  4777.5  375.69  4787.8  375.37  4798.2  373.41
  4804.4  373.90  4809.5  375.83  4818.8  375.97  4839.5  373.85  4887.9  373.82
  4945.8  373.74  4970.5  372.70  4998.3  368.82  4998.5  368.32  5002.3  368.82
  5015.1  371.50  5027.8  372.30  5051.0  371.27  5086.8  371.32  5212.3  373.44
  5278.7  373.02  5362.3  375.09  5520.7  378.02  5610.1  379.96  5646.5  379.77
#Mann=7,-1,0
  4493.3   0.063       0  4662.0   0.094       0  4887.9   0.063       0
  4998.3    0.05       0  5002.3   0.063       0  5362.3   0.035       0
  5520.7   0.063       0
Bank Sta=4998.3,5002.3
Exp/Cntr=0.3,0.1

Type RM Length L Ch R = 1,1854,127,127,127
BEGIN DESCRIPTION:
WEST DRAIN 3.0
END DESCRIPTION:
XS GIS Cut Line= 3
      2507924.98     13804524.99      2507375.00     13804275.00
      2507075.01     13804924.98
#Sta/Elev= 30
  4395.1  379.65  4426.9  379.24  4450.0  377.82  4516.0  376.99  4599.4  376.82
  4668.6  374.38  4737.1  373.87  4794.9  372.43  4915.8  372.15  4955.3  370.03
  4961.9  368.01  4987.9  367.49  4988.4  367.40  4988.7  366.90  4992.4  367.40
  4996.5  369.49  5021.3  370.57  5065.3  368.58  5151.1  370.58  5156.6  369.79
  5174.1  369.86  5202.5  371.05  5282.5  370.48  5307.6  371.67  5483.4  375.24
  5533.1  375.42  5586.2  376.95  5683.5  377.91  5712.1  379.37  5715.1  379.41
#Mann=9,-1,0
  4395.1   0.063       0  4516.0   0.094       0  4737.1   0.063       0
  4987.9   0.035       0  4988.4   0.035       0  4992.4   0.035       0
  5282.5   0.063       0  5533.1   0.035       0  5712.1   0.063       0
Bank Sta=4988.4,4992.4
Exp/Cntr=0.3,0.1

Type RM Length L Ch R = 1,1727,118,118,118
BEGIN DESCRIPTION:
H21633
END DESCRIPTION:
XS GIS Cut Line= 4
      2508007.56     13804088.26      2507375.88     13804141.60
      2507229.90     13804234.25      2506994.28     13804890.61
#Sta/Elev= 30
  4341.1  374.49  4348.9  374.47  4413.9  374.69  4460.6  375.92  4484.9  376.50
  4593.7  375.50  4636.6  375.31  4735.1  373.79  4775.2  371.39  4815.3  371.40
  4845.4  372.56  4915.7  372.51  4958.4  372.00  4977.7  370.15  4997.8  366.56
  4998.0  366.06  5001.8  366.56  5028.7  369.91  5049.9  369.87  5065.1  368.55
  5122.7  369.22  5237.7  368.44  5286.8  369.03  5299.2  368.09  5318.7  369.48
  5447.6  370.39  5597.0  374.24  5673.9  375.31  5682.8  376.05  5845.3  376.98
#Mann=10,-1,0
  4341.1   0.063       0  4348.9   0.094       0  4460.6   0.063       0
  4593.7   0.094       0  4636.6   0.063       0  4977.7   0.035       0
  4997.8   0.035       0  5001.8   0.035       0  5597.0   0.063       0
  5673.9   0.035       0
Bank Sta=4997.8,5001.8
Exp/Cntr=0.3,0.1

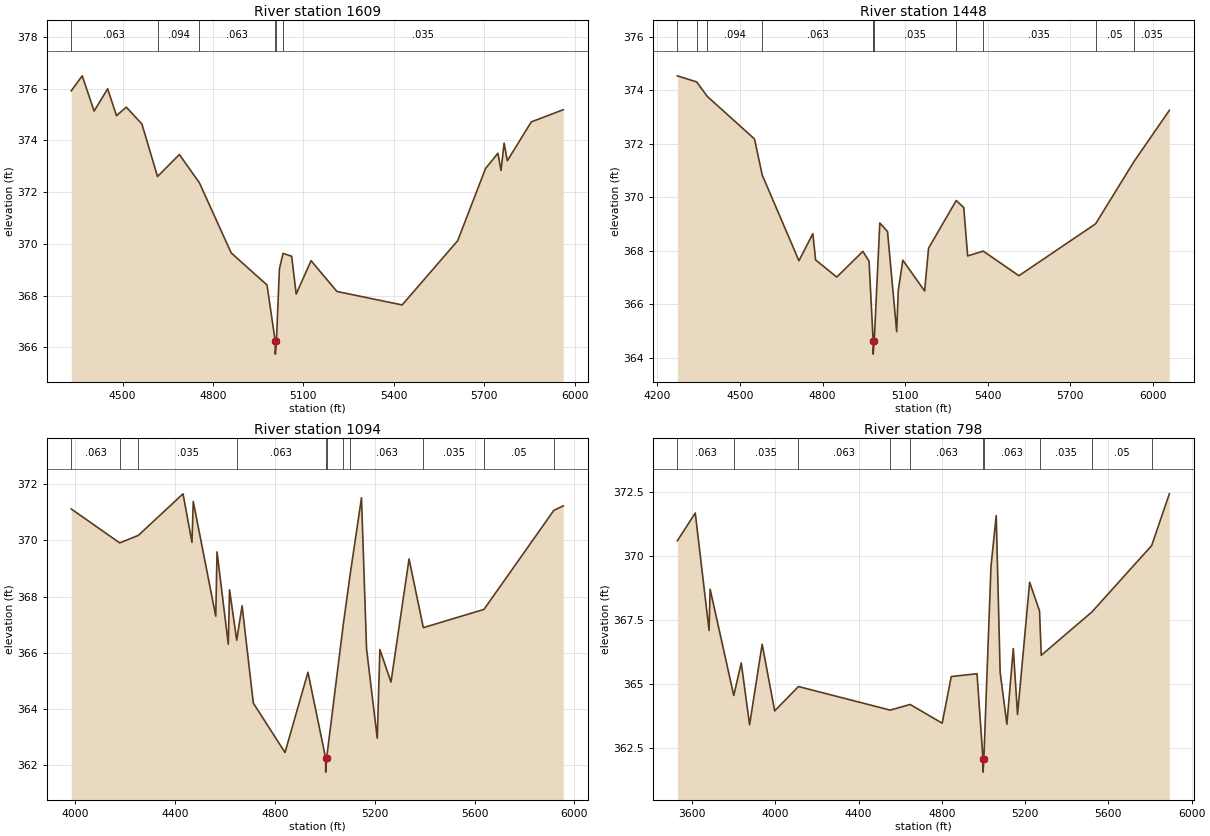
Type RM Length L Ch R = 1,1609,161,161,161
BEGIN DESCRIPTION:
H21632
END DESCRIPTION:
XS GIS Cut Line= 4
      2507971.03     13803869.28      2507286.05     13804057.38
      2507109.17     13804175.29      2506946.34     13804865.94
#Sta/Elev= 30
  4329.9  375.91  4366.2  376.49  4405.8  375.13  4450.7  375.99  4479.9  374.95
  4512.4  375.28  4564.3  374.63  4616.1  372.60  4688.7  373.45  4755.0  372.36
  4860.6  369.65  4979.5  368.41  5006.7  366.24  5007.0  365.74  5010.7  366.24
  5020.6  369.03  5032.6  369.63  5061.3  369.52  5076.3  368.06  5125.6  369.35
  5211.5  368.16  5427.9  367.64  5612.1  370.12  5704.6  372.91  5745.7  373.50
  5756.0  372.83  5766.2  373.89  5776.9  373.21  5856.4  374.71  5962.4  375.18
#Mann=6,-1,0
  4329.9   0.063       0  4616.1   0.094       0  4755.0   0.063       0
  5006.7    0.05       0  5010.7   0.063       0  5032.6   0.035       0
Bank Sta=5006.7,5010.7
Exp/Cntr=0.3,0.1

Type RM Length L Ch R = 1,1448,354,354,354
BEGIN DESCRIPTION:
H21631
END DESCRIPTION:
XS GIS Cut Line= 5
      2507962.61     13803756.98      2507398.34     13803835.59
      2507123.21     13803973.15      2506921.07     13804220.21
      2506895.86     13804811.34
#Sta/Elev= 30
  4272.5  374.54  4342.9  374.31  4381.2  373.77  4552.8  372.18  4580.9  370.83
  4714.3  367.63  4764.8  368.64  4774.9  367.66  4851.8  367.02  4946.8  367.98
  4969.2  367.61  4983.5  364.75  4984.0  364.64  4984.2  364.14  4988.0  364.64
  5008.3  369.04  5036.3  368.72  5069.6  364.98  5075.4  366.52  5091.9  367.65
  5171.1  366.50  5185.5  368.10  5286.0  369.88  5313.3  369.62  5327.6  367.81
  5384.1  367.99  5513.9  367.07  5792.7  369.01  5931.7  371.33  6060.7  373.25
#Mann=11,-1,0
  4272.5   0.094       0  4342.9   0.063       0  4381.2   0.094       0
  4580.9   0.063       0  4983.5   0.035       0  4984.0   0.035       0
  4988.0   0.035       0  5286.0   0.063       0  5384.1   0.035       0
  5792.7    0.05       0  5931.7   0.035       0
Bank Sta=4984,4988
Exp/Cntr=0.3,0.1

Type RM Length L Ch R = 1,1094,296,296,296
BEGIN DESCRIPTION:
H21630
END DESCRIPTION:
XS GIS Cut Line= 5
      2507923.30     13803641.88      2506988.45     13803835.59
      2506845.27     13803956.31      2506755.43     13804208.98
      2506850.72     13804761.07
#Sta/Elev= 30
  3984.8  371.12  4179.0  369.91  4253.6  370.18  4432.4  371.66  4468.3  369.93
  4473.4  371.39  4563.5  367.30  4568.6  369.59  4613.7  366.30  4618.8  368.24
  4647.4  366.44  4669.0  367.67  4714.0  364.20  4840.9  362.44  4932.8  365.30
  5003.6  362.24  5003.9  361.74  5007.6  362.24  5073.4  366.94  5099.6  368.65
  5147.2  371.52  5167.5  366.13  5210.3  362.95  5220.9  366.11  5265.3  364.95
  5337.7  369.34  5394.9  366.89  5637.7  367.54  5917.5  371.07  5955.2  371.23
#Mann=11,-1,0
  3984.8   0.063       0  4179.0   0.094       0  4253.6   0.035       0
  4647.4   0.063       0  5003.6    0.05       0  5007.6   0.063       0
  5073.4   0.035       0  5099.6   0.063       0  5394.9   0.035       0
  5637.7    0.05       0  5917.5   0.035       0
Bank Sta=5003.6,5007.6
Exp/Cntr=0.3,0.1

Type RM Length L Ch R = 1,798,0,0,0
BEGIN DESCRIPTION:
H21629
END DESCRIPTION:
XS GIS Cut Line= 4
      2507920.58     13803596.95      2506738.59     13803698.02
      2506629.10     13804197.75      2506836.84     13804829.38
#Sta/Elev= 30
  3530.1  370.60  3616.0  371.68  3682.3  367.10  3687.3  368.71  3800.9  364.56
  3836.8  365.83  3876.9  363.42  3937.2  366.56  3997.4  363.96  4111.6  364.91
  4552.1  363.99  4648.0  364.21  4801.8  363.48  4845.6  365.30  4969.2  365.41
  4997.9  362.07  4998.2  361.57  5001.9  362.07  5036.3  369.60  5061.4  371.58
  5080.2  365.47  5112.6  363.44  5143.3  366.39  5163.7  363.82  5221.9  368.98
  5269.4  367.86  5277.7  366.13  5520.9  367.82  5807.9  370.41  5892.9  372.43
#Mann=10,-1,0
  3530.1   0.063       0  3800.9   0.035       0  4111.6   0.063       0
  4552.1   0.035       0  4648.0   0.063       0  4997.9    0.05       0
  5001.9   0.063       0  5269.4   0.035       0  5520.9    0.05       0
  5807.9   0.035       0
Bank Sta=4997.9,5001.9
Exp/Cntr=0.3,0.1

Chan Stop Cuts=-1