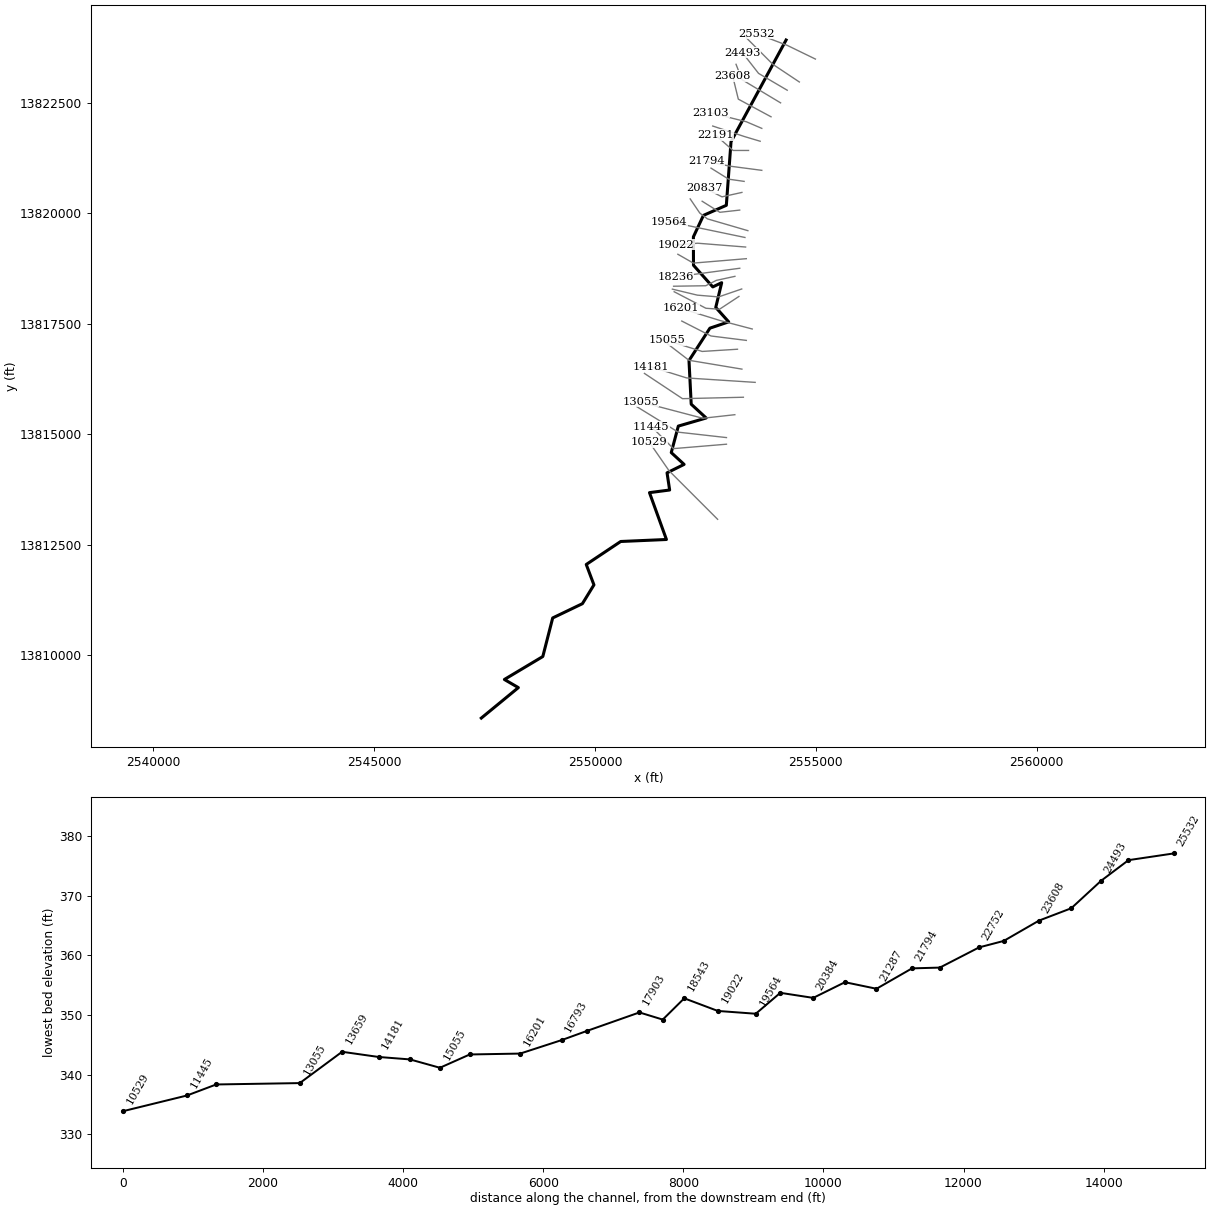
--- West Brook Creek.prj (project) ---

Proj Title=West Brook Creek Base Level Engineering
Current Plan=p01
Default Exp/Contr=0.3,0.1
English Units
Geom File=g01
Flow File=f01
Plan File=p01
Y Axis Title=Elevation
X Axis Title(PF)=Main Channel Distance
X Axis Title(XS)=Station
BEGIN DESCRIPTION:
West Brook Creek
END DESCRIPTION:
DSS Export Rating Curves= 0
DSS Export Rating Curve Sorted= 0
DSS Export Volume Flow Curves= 0
DXF OffsetX= 0
DXF OffsetY= 0
DXF ScaleX= 1
DXF ScaleY= 10

--- West Brook Creek.p01 (plan) ---

Plan Title=Multiple Run
Short Identifier=Multiple
Geom File=g01
Flow File=f01
Subcritical Flow
K Sum by GR= 0
Std Step Tol= 0.01
Critical Tol= 0.01
Num of Std Step Trials= 20
Max Error Tol= 0.3
Flow Tol Ratio= 0.001
Split Flow NTrial= 30
Split Flow Tol= 0.02
Split Flow Ratio= 0.02
Log Output Level= 0
Friction Slope Method= 1
Unsteady Friction Slope Method= 2
Unsteady Bridges Friction Slope Method= 1
Parabolic Critical Depth
Global Vel Dist=  1 , 1 , 1
Global Log Level= 0
CheckData=True
Encroach Param= -1, 0, 0, 0
BEGIN DESCRIPTION:
Multiple Run
END DESCRIPTION:

--- West Brook Creek.f01 (steady flow) ---

Flow Title=Multiple
Number of Profiles=7
Profile Names=10-year,25-year,50-year,1pct_min,100-year,1pct_plu,500-year
River Rch & RM= West Brook Creek,Reach-1,25532
     529     829    1093     699    1394    2782    2242
River Rch & RM= West Brook Creek,Reach-1,23103
    1108    1806    2443    1596    3185    6355    5361
River Rch & RM= West Brook Creek,Reach-1,16201
    1417    2337    3186    2097    4183    8347    7143
River Rch & RM= West Brook Creek,Reach-1,15055
    1536    2526    3435    2254    4497    8973    7631
River Rch & RM= West Brook Creek,Reach-1,7786
    1934    3208    4389    2894    5775   11522    9904
River Rch & RM= West Brook Creek,Reach-1,3630
    2073    3445    4719    3115    6215   12400   10678
Boundary for River Rch & Prof#=West Brook Creek,Reach-1,1
Up Type=0
Dn Type=3
Dn Slope=0.005
Boundary for River Rch & Prof#=West Brook Creek,Reach-1,2
Up Type=0
Dn Type=3
Dn Slope=0.005
Boundary for River Rch & Prof#=West Brook Creek,Reach-1,3
Up Type=0
Dn Type=3
Dn Slope=0.005
Boundary for River Rch & Prof#=West Brook Creek,Reach-1,4
Up Type=0
Dn Type=3
Dn Slope=0.005
Boundary for River Rch & Prof#=West Brook Creek,Reach-1,5
Up Type=0
Dn Type=3
Dn Slope=0.005
Boundary for River Rch & Prof#=West Brook Creek,Reach-1,6
Up Type=0
Dn Type=3
Dn Slope=0.005
Boundary for River Rch & Prof#=West Brook Creek,Reach-1,7
Up Type=0
Dn Type=3
Dn Slope=0.005

--- West Brook Creek.g01 (geometry) ---

Geom Title=Existing Conditions
Program Version=4.10

River Reach=West Brook Creek,Reach-1
Reach XY= 30
        2554325.       13823925.      2553078.37     13821623.72
      2552972.35     13820183.49      2552453.94      13819955.4
      2552226.49     13819469.16      2552228.53     13818826.47
      2552664.98     13818335.94      2552867.19     13818431.85
      2552732.85     13817871.77      2553025.33     13817544.86
      2552600.57     13817402.14      2552126.96     13816669.12
      2552177.06     13815680.85      2552516.22      13815368.2
      2551885.34     13815185.24      2551725.55     13814585.64
      2552016.19     13814318.01      2551630.06     13814127.29
      2551688.74      13813738.2      2551232.48     13813678.62
      2551616.17     13812617.96      2550580.93     13812572.76
      2549800.98     13812052.33      2549975.11     13811590.35
      2549714.04       13811165.      2549041.49     13810842.05
      2548817.66     13809968.61      2547947.54     13809448.83
      2548264.19     13809264.85        2547425.       13808575.

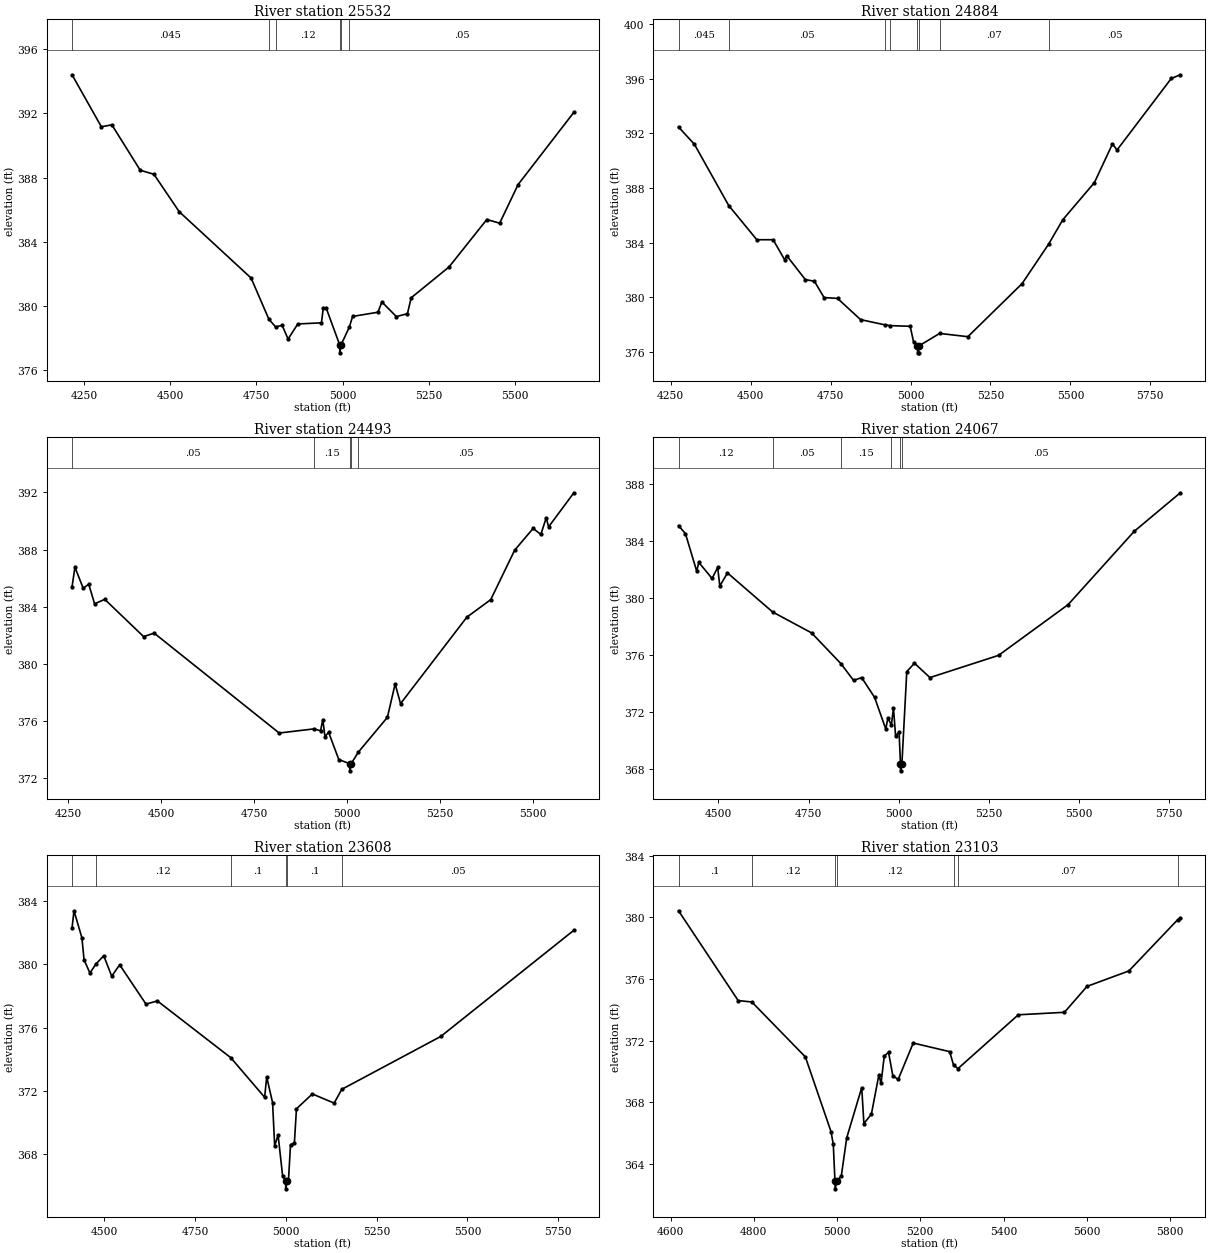
Type RM Length L Ch R = 1 ,25532   ,648,648,648
BEGIN DESCRIPTION:
West Brook Creek 38.0
END DESCRIPTION:
XS GIS Cut Line= 3
      2554988.81     13823494.06      2554347.08     13823805.75
      2553653.99     13824069.79
#Sta/Elev= 30
  4215.7  394.41  4300.6  391.17  4331.1  391.29  4413.4  388.46    4453  388.21
  4526.3  385.88  4734.9  381.74  4786.5  379.17  4805.8   378.7  4825.1  378.79
  4842.1  377.94  4870.2  378.88  4938.9  378.95  4944.2  379.88  4952.8  379.86
  4991.7  377.58    4992  377.08  4995.7  377.58  5019.8  378.69  5029.2  379.35
  5102.6  379.61  5114.1  380.25  5156.1  379.34  5188.2  379.52    5199  380.51
  5308.7  382.43  5418.4  385.39  5455.7  385.16  5509.2  387.57  5670.8  392.07
#Mann= 6 ,-1 , 0
  4215.7    .045       0  4786.5     .05       0  4805.8     .12       0
  4991.7     .05       0  4995.7     .12       0  5019.8     .05       0
Bank Sta=4991.7,4995.7
XS Rating Curve= 0 ,0
Exp/Cntr=0.3,0.1

Type RM Length L Ch R = 1 ,24884   ,391,391,391
BEGIN DESCRIPTION:
West Brook Creek 37.0
END DESCRIPTION:
XS GIS Cut Line= 3
      2554625.03     13822974.98        2554025.       13823375.
      2553424.98     13823975.02
#Sta/Elev= 30
  4274.2  392.46  4323.8   391.2  4431.2  386.72  4519.1  384.22  4570.2  384.22
  4606.2  382.75  4612.3  383.06  4670.8  381.31  4699.4  381.18  4729.4  379.99
  4771.5  379.93  4843.6  378.38    4919     378  4936.5  377.94  4998.9  377.89
  5009.5  376.74  5021.6  376.45  5021.9  375.95  5025.4  375.95  5025.6  376.45
  5091.1  377.37  5179.2  377.13  5348.9  381.01  5431.7  383.89  5476.2  385.68
  5575.2   388.4  5631.7  391.23  5645.9  390.78  5815.6  396.01  5843.9  396.28
#Mann= 8 ,-1 , 0
  4274.2    .045       0  4431.2     .05       0    4919     .07       0
  4936.5     .05       0  5021.6     .05       0  5025.6     .05       0
  5091.1     .07       0  5431.7     .05       0
Bank Sta=5021.6,5025.6
XS Rating Curve= 0 ,0
Exp/Cntr=0.3,0.1

Type RM Length L Ch R = 1 ,24493   ,426,426,426
BEGIN DESCRIPTION:
H21580
END DESCRIPTION:
XS GIS Cut Line= 3
      2554350.75     13822788.51      2553701.68     13823169.88
      2553334.96     13823639.29
#Sta/Elev= 30
  4260.7   385.4  4268.4  386.76  4290.6  385.29  4305.5  385.57  4321.2   384.2
  4348.6  384.51  4452.9   381.9  4481.4  382.14  4817.3  375.14  4910.3  375.43
  4928.5   375.3  4934.5  376.08  4940.3  374.89  4950.2  375.19  4977.5  373.28
  5006.7  372.99    5007  372.49  5010.7  372.99    5030   373.8  5108.1  376.24
  5128.9  378.58  5143.4   377.2  5321.6  383.26  5385.8  384.49    5450  387.95
  5499.7  389.48  5520.5  389.06    5535  390.23  5541.3  389.59  5609.2  391.98
#Mann= 5 ,-1 , 0
  4260.7     .05       0  4910.3     .15       0  5006.7     .05       0
  5010.7     .15       0    5030     .05       0
Bank Sta=5006.7,5010.7
XS Rating Curve= 0 ,0
Exp/Cntr=0.3,0.1

Type RM Length L Ch R = 1 ,24067   ,459,459,459
BEGIN DESCRIPTION:
H21579
END DESCRIPTION:
XS GIS Cut Line= 3
      2554200.44     13822502.46      2553327.64     13823026.87
      2553191.95     13823375.25
#Sta/Elev= 30
  4389.3   385.1  4408.5  384.54  4439.6  381.91  4445.5  382.52  4482.4  381.39
  4497.9  382.17  4503.8  380.86  4525.1  381.78  4650.2  379.04  4758.3  377.57
  4840.1   375.4  4874.9  374.23  4897.3  374.43  4933.2  373.04  4964.2  370.82
  4970.1  371.58  4979.8  371.11  4985.6  372.29  4991.4  370.35  5001.2  370.59
    5005  368.38  5005.2  367.88    5009  368.38  5022.5  374.85  5043.9  375.44
  5086.7  374.43  5277.1  375.99  5469.9  379.55  5653.4   384.7  5781.4  387.41
#Mann= 6 ,-1 , 0
  4389.3     .12       0  4650.2     .05       0  4840.1     .15       0
  4979.8     .05       0    5005     .05       0    5009     .05       0
Bank Sta=5005,5009
XS Rating Curve= 0 ,0
Exp/Cntr=0.3,0.1

Type RM Length L Ch R = 1 ,23608   ,505,505,505
BEGIN DESCRIPTION:
H21578
END DESCRIPTION:
XS GIS Cut Line= 3
      2553984.02     13822187.12      2553243.29     13822586.82
       2553115.1     13823110.57
#Sta/Elev= 30
  4411.8   382.3  4417.1  383.37  4438.9  381.66  4444.8  380.28  4460.9  379.44
  4477.4  380.01    4499  380.53  4520.9  379.24  4542.8  379.96  4615.2  377.48
  4646.6  377.68  4848.4   374.1  4941.7   371.6  4947.4  372.88  4963.6  371.26
  4969.3  368.54  4978.8  369.21  4991.2  366.64  4999.6  366.32  4999.8  365.82
  5003.6  366.32  5007.4  366.39    5013  368.61  5023.6  368.71  5029.3  370.87
    5073  371.81    5133  371.23    5154   372.1  5426.6  375.44  5792.7  382.14
#Mann= 6 ,-1 , 0
  4411.8     .07       0  4477.4     .12       0  4848.4      .1       0
  4999.6     .05       0  5003.6      .1       0    5154     .05       0
Bank Sta=4999.6,5003.6
XS Rating Curve= 0 ,0
Exp/Cntr=0.3,0.1

Type RM Length L Ch R = 1 ,23103   ,351,351,351
BEGIN DESCRIPTION:
West Brook Creek 33.0
END DESCRIPTION:
XS GIS Cut Line= 3
      2553775.04     13821924.98        2553425.       13822075.
      2552624.96     13822275.01
#Sta/Elev= 30
  4619.2  380.42  4762.5   374.6  4795.3  374.51  4923.9  370.95  4985.5  366.11
    4991  365.28    4995   362.9  4995.4   362.4  4999.6   362.9  5010.3  363.24
  5023.2   365.7  5059.3  368.96  5064.5  366.63  5082.5  367.24  5100.5  369.78
  5105.7  369.23  5113.4     371  5123.7  371.25    5134  369.73  5146.9  369.49
    5183  371.85  5270.6  371.29  5279.8  370.43  5290.4  370.19  5435.5  373.68
  5546.3  373.84  5600.5  375.52    5701  376.52  5818.7  379.85  5824.7  379.94
#Mann= 7 ,-1 , 0
  4619.2      .1       0  4795.3     .12       0    4995     .05       0
  4999.6     .12       0  5279.8      .1       0  5290.4     .07       0
  5818.7     .05       0
Bank Sta=4995,4999.6
XS Rating Curve= 0 ,0
Exp/Cntr=0.3,0.1

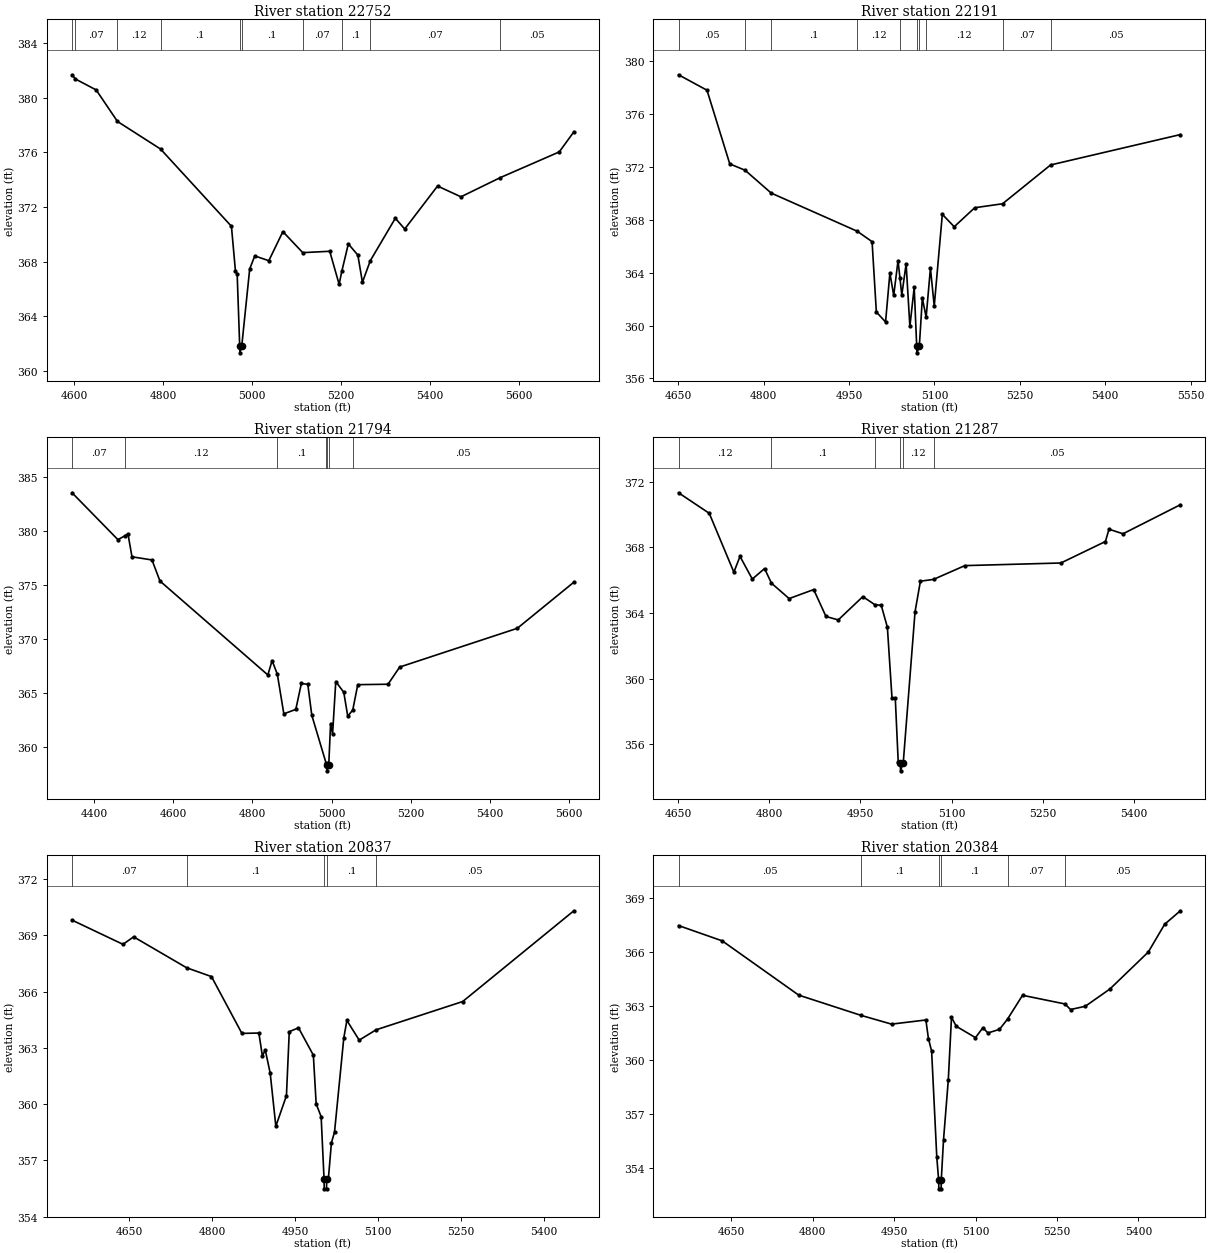
Type RM Length L Ch R = 1 ,22752   ,561,561,561
BEGIN DESCRIPTION:
West Brook Creek 32.0
END DESCRIPTION:
XS GIS Cut Line= 3
      2553738.35     13821633.38      2553382.64     13821739.73
       2552663.9     13821978.09
#Sta/Elev= 30
  4595.4  381.69  4602.9  381.38  4649.6  380.58  4697.5  378.27  4794.4  376.25
  4953.8  370.59  4962.8  367.32  4966.7  367.09  4972.4  361.82  4972.8  361.32
    4977  361.82  4994.9  367.47  5006.3  368.42  5037.9  368.07  5069.5   370.2
  5114.2  368.66  5174.9  368.76    5196  366.34    5202  367.29  5216.7   369.3
  5238.1  368.48  5248.4  366.49  5266.1  368.07  5322.4  371.18  5343.5  370.39
  5417.4  373.54  5469.9  372.75  5558.7  374.16  5691.1  376.04  5723.9  377.51
#Mann= 10 ,-1 , 0
  4595.4     .05       0  4602.9     .07       0  4697.5     .12       0
  4794.4      .1       0  4972.4     .05       0    4977      .1       0
  5114.2     .07       0    5202      .1       0  5266.1     .07       0
  5558.7     .05       0
Bank Sta=4972.4,4977
XS Rating Curve= 0 ,0
Exp/Cntr=0.3,0.1

Type RM Length L Ch R = 1 ,22191   ,397,397,397
BEGIN DESCRIPTION:
West Brook Creek 31.0
END DESCRIPTION:
XS GIS Cut Line= 3
      2553474.97       13821425.        2553125.       13821425.
      2552724.98     13821775.02
#Sta/Elev= 30
  4650.4  378.99  4700.4  377.82  4740.4  372.24  4767.3  371.76  4813.2  370.03
  4964.3  367.14  4990.4  366.35  4997.9  361.02  5014.1  360.27  5021.7  363.98
  5028.4  362.28    5036  364.92  5039.3  363.62  5042.6  362.31  5050.2  364.67
  5056.8  359.93  5064.4  362.89  5068.8  358.43  5069.1  357.93  5073.4  358.43
  5078.7  362.07  5085.4  360.63  5092.9  364.34  5099.6  361.47  5113.8  368.42
  5134.7  367.48  5170.7  368.92  5219.6  369.22    5304  372.16  5531.9  374.46
#Mann= 10 ,-1 , 0
  4650.4     .05       0  4767.3     .12       0  4813.2      .1       0
  4964.3     .12       0  5039.3      .1       0  5068.8     .05       0
  5073.4      .1       0  5085.4     .12       0  5219.6     .07       0
    5304     .05       0
Bank Sta=5068.8,5073.4
XS Rating Curve= 0 ,0
Exp/Cntr=0.3,0.1

Type RM Length L Ch R = 1 ,21794   ,507,507,507
BEGIN DESCRIPTION:
West Brook Creek 30.0
END DESCRIPTION:
XS GIS Cut Line= 3
      2553774.95     13820975.01      2553059.94     13821068.66
      2552525.03     13821174.99
#Sta/Elev= 30
  4344.9  383.55  4460.6  379.21  4478.9  379.58    4486  379.74  4496.1  377.62
  4546.6  377.33  4566.7  375.38    4839  366.68  4849.8  368.01    4863  366.74
  4879.4  363.08  4909.6  363.49  4923.6  365.89  4939.9  365.81    4950  362.94
  4985.7  358.55    4988   358.3  4988.3   357.8  4992.7   358.3  4997.4  362.18
  5002.4  361.21  5010.5  366.07  5030.7  365.07  5040.7  362.86  5053.3  363.43
    5066  365.78  5142.4  365.82  5171.7  367.41  5468.7     371  5611.4  375.27
#Mann= 7 ,-1 , 0
  4344.9     .07       0  4478.9     .12       0    4863      .1       0
  4985.7     .12       0    4988     .05       0  4992.7     .12       0
  5053.3     .05       0
Bank Sta=4988,4992.7
XS Rating Curve= 0 ,0
Exp/Cntr=0.3,0.1

Type RM Length L Ch R = 1 ,21287   ,450,450,450
BEGIN DESCRIPTION:
West Brook Creek 29.0
END DESCRIPTION:
XS GIS Cut Line= 3
      2553375.04     13820724.99        2553025.       13820775.
      2552624.99       13821025.
#Sta/Elev= 30
  4650.9  371.33  4701.4  370.08  4741.9  366.49    4752  367.45  4772.2  366.07
  4792.4  366.71  4803.7  365.82  4832.8  364.88  4873.2  365.43  4893.4  363.79
  4913.6  363.58    4954     365  4973.7  364.51  4984.3  364.47  4994.4  363.13
    5002   358.8  5007.4   358.8  5012.2  354.93  5015.7  354.88    5016  354.38
  5020.5  354.88  5039.9  364.08  5048.7  365.94  5070.3  366.05  5121.8  366.89
  5279.8  367.05    5353  368.36  5358.9  369.11  5381.9  368.83  5476.2   370.6
#Mann= 6 ,-1 , 0
  4650.9     .12       0  4803.7      .1       0  4973.7     .12       0
  5015.7     .05       0  5020.5     .12       0  5070.3     .05       0
Bank Sta=5015.7,5020.5
XS Rating Curve= 0 ,0
Exp/Cntr=0.3,0.1

Type RM Length L Ch R = 1 ,20837   ,453,453,453
BEGIN DESCRIPTION:
West Brook Creek 28.0
END DESCRIPTION:
XS GIS Cut Line= 3
      2553325.04     13820475.01        2552875.       13820375.
      2552475.03     13820574.99
#Sta/Elev= 30
  4546.7  369.81  4638.9  368.52  4658.1  368.92  4754.1  367.27    4799   366.8
  4854.1  363.77  4884.8  363.79  4891.2  362.56  4896.3  362.89  4905.3  361.65
  4915.5  358.82  4934.7  360.45  4939.8  363.86  4956.5  364.07  4983.4  362.61
  4988.5  360.01  4997.5  359.33  5002.8  355.98  5003.1  355.48  5007.2  355.48
  5007.6  355.98  5010.5  355.98  5016.1  357.94  5021.7   358.5  5038.5  363.53
  5044.1  364.46  5066.4  363.41  5096.8  363.96  5253.7  365.47  5454.9  370.31
#Mann= 5 ,-1 , 0
  4546.7     .07       0  4754.1      .1       0  5002.8     .05       0
  5007.6      .1       0  5096.8     .05       0
Bank Sta=5002.8,5007.6
XS Rating Curve= 0 ,0
Exp/Cntr=0.3,0.1

Type RM Length L Ch R = 1 ,20384   ,470,470,470
BEGIN DESCRIPTION:
West Brook Creek 27.0
END DESCRIPTION:
XS GIS Cut Line= 3
      2553275.01       13820075.        2552825.       13820025.
      2552424.99     13820275.01
#Sta/Elev= 30
  4552.6  367.46  4633.1  366.61    4774   363.6  4888.4  362.48    4945  361.99
  5008.3  362.22    5013  361.19  5018.9  360.49  5028.4  354.61  5031.8  353.35
  5032.2  352.85  5036.4  352.85  5036.7  353.35  5040.8  355.57  5049.6  358.89
  5055.5  362.37  5064.3  361.87  5099.7  361.24  5113.3  361.79  5122.7   361.5
  5143.9   361.7  5158.8  362.27  5186.4  363.59  5264.4  363.11  5274.8   362.8
    5302  362.98  5347.4  363.94  5418.1  365.99  5448.2  367.53  5477.1  368.28
#Mann= 6 ,-1 , 0
  4552.6     .05       0  4888.4      .1       0  5031.8     .05       0
  5036.7      .1       0  5158.8     .07       0  5264.4     .05       0
Bank Sta=5031.8,5036.7
XS Rating Curve= 0 ,0
Exp/Cntr=0.3,0.1

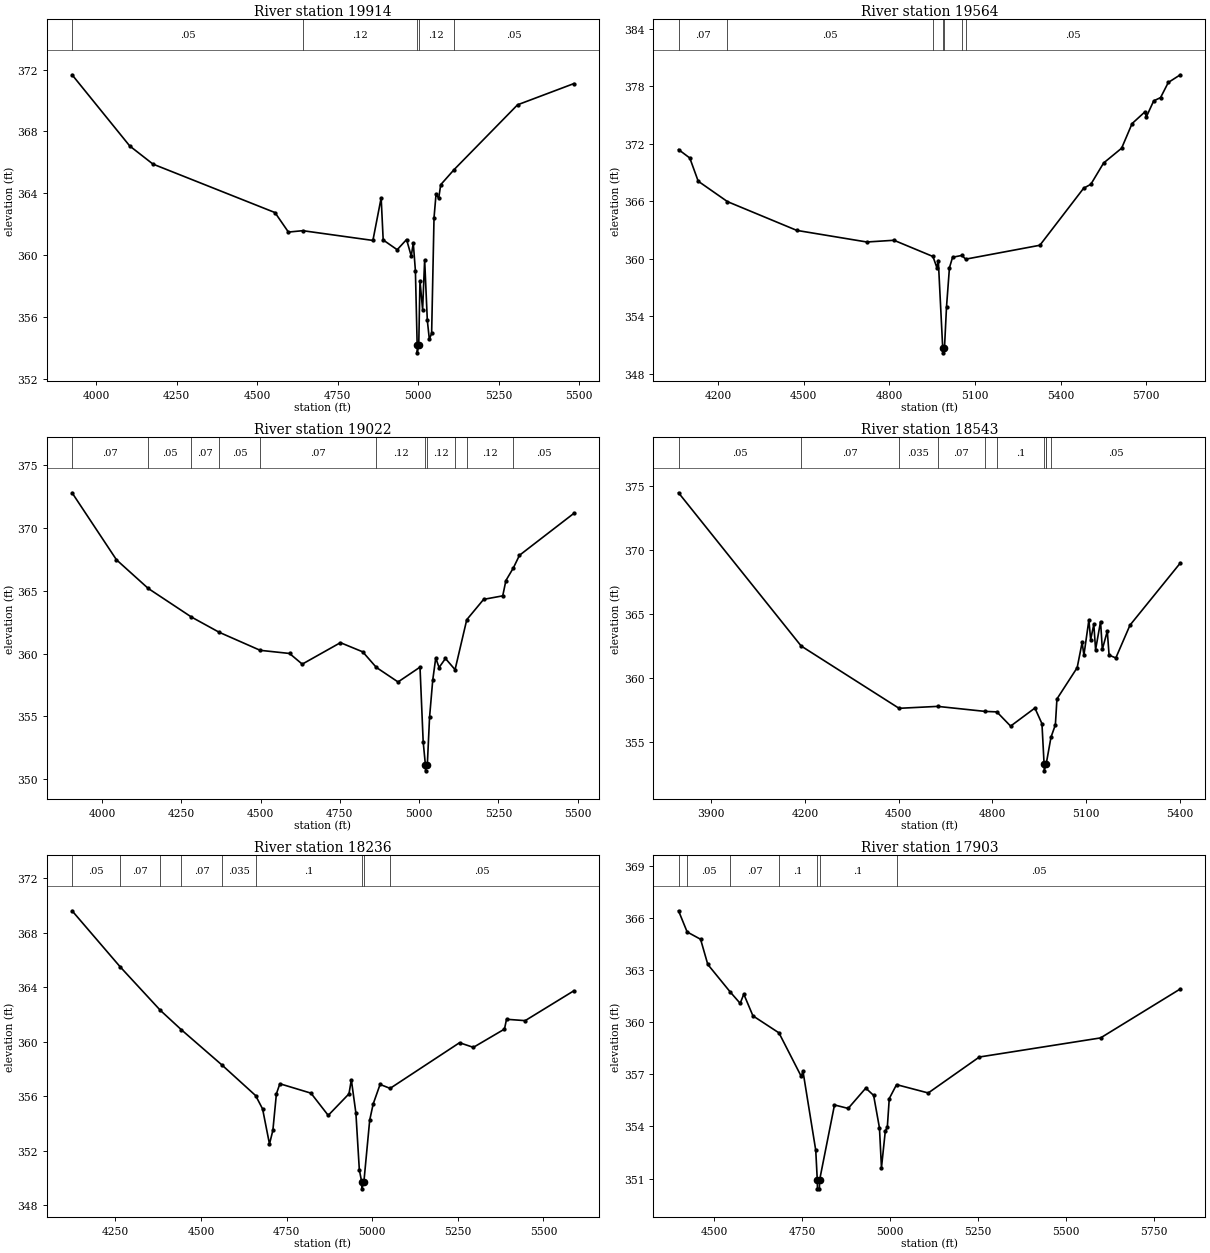
Type RM Length L Ch R = 1 ,19914   ,350,350,350
BEGIN DESCRIPTION:
H21577
END DESCRIPTION:
XS GIS Cut Line= 4
      2553459.68     13819609.16      2552542.88     13819876.86
      2552370.53     13820008.88      2552154.15     13820327.94
#Sta/Elev= 30
  3925.4  371.66  4104.5  367.06  4176.6  365.89  4555.3  362.76    4597   361.5
  4641.6  361.59  4859.3  360.96  4884.9  363.71  4891.2  360.99  4934.7  360.36
  4963.8  361.02  4978.3  359.95  4984.6  360.79  4991.2  359.01  4996.7   354.2
    4997   353.7  5001.6   354.2  5005.4  358.36  5013.6  356.49  5019.9  359.71
  5028.2   355.8  5034.5  354.57  5041.6  354.96    5049  362.42  5055.3  363.96
  5063.5  363.68  5069.8  364.56  5111.1  365.53  5308.3  369.72  5483.1  371.09
#Mann= 5 ,-1 , 0
  3925.4     .05       0  4641.6     .12       0  4996.7     .05       0
  5001.6     .12       0  5111.1     .05       0
Bank Sta=4996.7,5001.6
XS Rating Curve= 0 ,0
Exp/Cntr=0.3,0.1

Type RM Length L Ch R = 1 ,19564   ,542,542,542
BEGIN DESCRIPTION:
H21576
END DESCRIPTION:
XS GIS Cut Line= 3
      2553393.62     13819455.15      2552249.52     13819693.51
      2551673.76     13819814.53
#Sta/Elev= 30
  4062.1  371.39  4101.5  370.51    4131  368.09  4233.5  365.96  4476.2  362.96
  4721.4  361.75  4816.4  361.93  4952.9  360.24  4966.5  359.09  4971.7  359.82
  4987.1  350.69  4987.6  350.19  4993.3  350.69  5000.4  354.98  5010.7  359.07
  5021.7  360.16  5054.1  360.35  5067.5  359.96  5327.3  361.41  5480.6  367.36
  5505.8  367.77  5550.5  369.99  5613.5  371.53  5650.2   374.1    5695  375.32
  5700.1   374.8  5725.9  376.47  5749.9  376.81    5777  378.39  5819.1  379.19
#Mann= 7 ,-1 , 0
  4062.1     .07       0  4233.5     .05       0  4952.9     .12       0
  4987.1     .05       0  4993.3     .12       0  5054.1     .07       0
  5067.5     .05       0
Bank Sta=4987.1,4993.3
XS Rating Curve= 0 ,0
Exp/Cntr=0.3,0.1

Type RM Length L Ch R = 1 ,19022   ,479,479,479
BEGIN DESCRIPTION:
West Brook Creek 24.0
END DESCRIPTION:
XS GIS Cut Line= 3
      2553408.31     13819238.79        2552325.       13819325.
      2551831.44     13819286.46
#Sta/Elev= 30
  3905.8  372.81  4045.8  367.47  4145.9  365.19  4282.2  362.91  4369.4   361.7
  4498.8  360.26  4591.3  360.01  4631.4  359.16  4751.8  360.87    4822  360.14
  4864.9   358.9  4933.4  357.74  5002.6  358.92  5012.6  352.98  5019.5  351.16
    5020  350.66  5025.7  351.16  5032.7  354.92  5042.7  357.88  5052.2  359.65
  5062.7  358.89  5082.8  359.61  5113.1  358.72    5150   362.7  5203.2  364.32
  5263.4   364.6  5273.4  365.82    5297  366.83  5316.1  367.83  5487.6  371.17
#Mann= 11 ,-1 , 0
  3905.8     .07       0  4145.9     .05       0  4282.2     .07       0
  4369.4     .05       0  4498.8     .07       0  4864.9     .12       0
  5019.5     .05       0  5025.7     .12       0  5113.1     .05       0
    5150     .12       0    5297     .05       0
Bank Sta=5019.5,5025.7
XS Rating Curve= 0 ,0
Exp/Cntr=0.3,0.1

Type RM Length L Ch R = 1 ,18543   ,307,307,307
BEGIN DESCRIPTION:
West Brook Creek 23.0
END DESCRIPTION:
XS GIS Cut Line= 3
      2553424.95       13818975.        2552225.       13818875.
      2551875.02     13819074.99
#Sta/Elev= 30
  3795.3  374.48  4188.2  362.52  4501.6  357.66  4625.1  357.81  4776.6  357.42
  4814.8  357.38  4858.9  356.27  4936.7  357.68  4959.3  356.46  4966.2  353.28
  4966.7  352.78  4972.5  353.28  4972.7  353.29  4988.3  355.41  5002.3  356.37
  5007.3  358.39  5072.1  360.83    5088   362.8  5093.7  361.81  5109.6  364.55
  5115.3  363.02  5125.4  364.21  5131.1  362.24    5147  364.43  5152.7  362.26
  5168.6  363.68  5174.3  361.81  5195.9  361.59  5241.3  364.15  5402.5     369
#Mann= 10 ,-1 , 0
  3795.3     .05       0  4188.2     .07       0  4501.6    .035       0
  4625.1     .07       0  4776.6     .12       0  4814.8      .1       0
  4966.2     .05       0  4972.5      .1       0  4972.7     .12       0
  4988.3     .05       0
Bank Sta=4966.2,4972.5
XS Rating Curve= 0 ,0
Exp/Cntr=0.3,0.1

Type RM Length L Ch R = 1 ,18236   ,333,333,333
BEGIN DESCRIPTION:
H21575
END DESCRIPTION:
XS GIS Cut Line= 2
      2553276.34     13818758.41      2551824.19     13818564.06
#Sta/Elev= 30
  4123.6  369.61  4263.6  365.51  4381.6   362.3  4442.8  360.88  4560.6  358.31
  4659.6  356.05  4679.9  355.07    4700   352.5  4709.9   353.5  4720.2  356.18
  4730.3  356.92  4821.1  356.23  4871.5   354.6  4932.1  356.18    4939  357.21
  4952.3  354.77  4962.3  350.62  4969.2  349.71  4969.7  349.21  4975.6  349.71
  4992.6  354.25  5002.7  355.43  5022.9  356.87  5052.2  356.58  5254.9  359.93
  5295.3  359.59  5386.1  360.93  5392.1  361.65  5446.6  361.55  5588.7  363.74
#Mann= 9 ,-1 , 0
  4123.6     .05       0  4263.6     .07       0  4381.6     .05       0
  4442.8     .07       0  4560.6    .035       0  4659.6      .1       0
  4969.2     .05       0  4975.6      .1       0  5052.2     .05       0
Bank Sta=4969.2,4975.6
XS Rating Curve= 0 ,0
Exp/Cntr=0.3,0.1

Type RM Length L Ch R = 1 ,17903   ,749,749,749
BEGIN DESCRIPTION:
H21574
END DESCRIPTION:
XS GIS Cut Line= 4
      2553166.32     13818575.06      2552744.57     13818483.38
      2552506.21     13818362.36      2551778.21     13818351.39
#Sta/Elev= 30
  4398.5  366.42    4423   365.2  4461.2  364.78  4481.7  363.33  4546.1  361.73
  4573.8  361.09  4584.1  361.62  4610.1  360.37  4684.1  359.39  4747.3  356.89
  4752.4  357.18  4788.7  352.63  4793.1  350.91  4793.6  350.41  4799.1  350.41
  4799.6  350.91    4842  355.24  4880.9  355.04    4931  356.21  4953.3  355.79
  4969.9  353.92  4975.6  351.63  4986.6  353.75  4992.2  353.95  4997.8  355.61
  5018.5  356.41  5108.6  355.93  5253.9     358  5598.7   359.1  5825.5  361.92
#Mann= 7 ,-1 , 0
  4398.5     .07       0    4423     .05       0  4546.1     .07       0
  4684.1      .1       0  4793.1     .05       0  4799.6      .1       0
  5018.5     .05       0
Bank Sta=4793.1,4799.6
XS Rating Curve= 0 ,0
Exp/Cntr=0.3,0.1

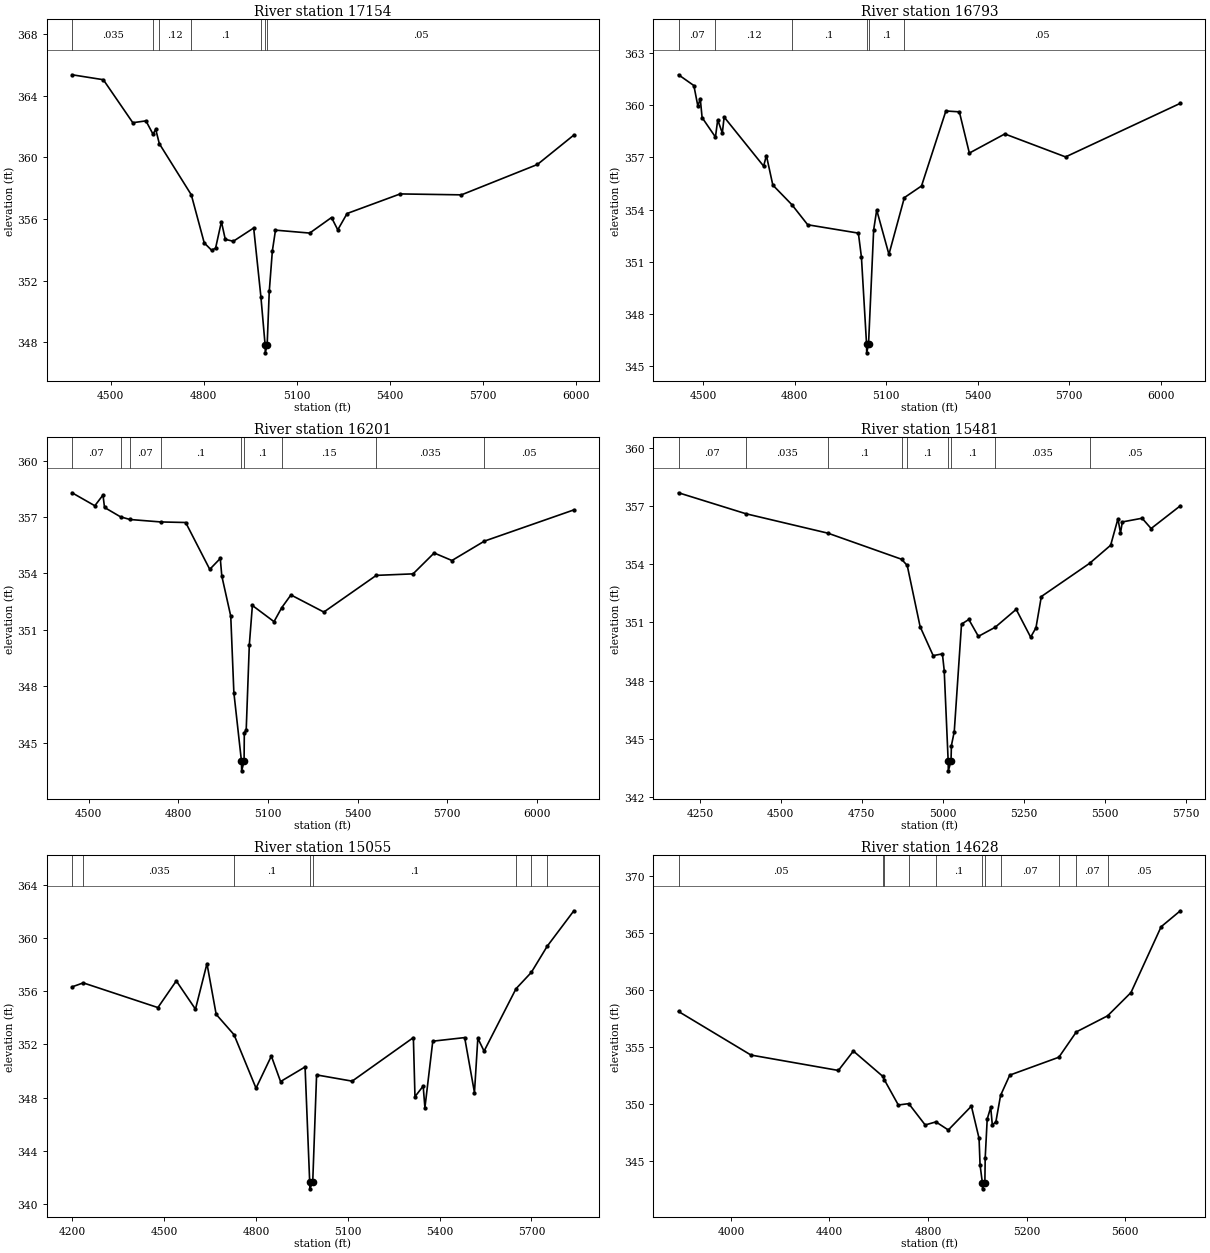
Type RM Length L Ch R = 1 ,17154   ,361,361,361
BEGIN DESCRIPTION:
H21573
END DESCRIPTION:
XS GIS Cut Line= 4
      2553320.27     13818289.01      2552795.91     13818109.34
      2552315.53     13818149.67      2551750.76     13818285.36
#Sta/Elev= 30
  4375.3  365.35    4476  365.03  4571.1  362.24  4613.4  362.36  4636.1   361.5
  4644.9  361.81  4656.5  360.88  4759.6  357.56  4801.3  354.44  4824.8  353.97
  4837.8   354.1  4856.6  355.82  4869.1  354.67  4895.1  354.55  4960.6  355.41
  4983.8  350.96  4997.5  347.81    4998  347.31    5004  347.81  5010.8  351.29
  5020.8  353.92  5030.9  355.27  5141.2  355.08  5211.5  356.09  5231.6  355.29
  5261.7  356.35  5432.8  357.62  5630.2  357.56    5875  359.53  5992.5  361.44
#Mann= 7 ,-1 , 0
  4375.3    .035       0  4636.1     .07       0  4656.5     .12       0
  4759.6      .1       0  4983.8     .05       0  4997.5     .05       0
    5004     .05       0
Bank Sta=4997.5,5004
XS Rating Curve= 0 ,0
Exp/Cntr=0.3,0.1

Type RM Length L Ch R = 1 ,16793   ,592,592,592
BEGIN DESCRIPTION:
H21572
END DESCRIPTION:
XS GIS Cut Line= 4
      2553257.93     13818120.31      2552817.91     13817830.64
      2552509.88     13817852.64      2551791.11      13818226.7
#Sta/Elev= 30
  4418.7  361.75    4469  361.13  4482.1  359.95    4490  360.38    4496  359.29
  4539.8  358.17  4547.2  359.16  4562.3   358.4  4568.3  359.32  4697.8   356.5
  4706.9  357.11    4728  355.41  4790.7  354.28  4842.4  353.13  5008.6  352.65
  5018.6  351.27  5035.4  346.27  5035.9  345.77  5041.9  346.27  5058.7  352.83
  5068.7  353.98  5108.8  351.43  5159.4  354.69  5215.7  355.36  5295.6  359.67
  5339.8  359.62  5372.6  357.25  5488.9  358.35  5688.2  357.03  6064.6  360.11
#Mann= 6 ,-1 , 0
  4418.7     .07       0  4539.8     .12       0  4790.7      .1       0
  5035.4     .05       0  5041.9      .1       0  5159.4     .05       0
Bank Sta=5035.4,5041.9
XS Rating Curve= 0 ,0
Exp/Cntr=0.3,0.1

Type RM Length L Ch R = 1 ,16201   ,720,720,720
BEGIN DESCRIPTION:
H21571
END DESCRIPTION:
XS GIS Cut Line= 3
      2553558.66     13817383.26      2552821.58     13817577.61
       2551945.2     13817848.96
#Sta/Elev= 30
  4443.9  358.29  4520.1   357.6  4547.4  358.17  4552.5  357.51  4606.3  357.01
  4637.8  356.87  4740.4  356.74  4824.2  356.71  4904.8  354.22    4940   354.8
  4945.1  353.87  4975.1  351.73  4985.5  347.67    5011  344.01  5011.5  343.51
  5019.7  344.01  5020.5  345.54  5026.8  345.68  5037.2   350.2  5047.5   352.3
  5119.9  351.44    5146  352.19  5176.5  352.86  5286.7  351.95  5462.2   353.9
  5585.4  353.98  5655.9  355.09  5715.5  354.69  5824.1  355.72  6123.6  357.38
#Mann= 9 ,-1 , 0
  4443.9     .07       0  4606.3    .035       0  4637.8     .07       0
  4740.4      .1       0    5011     .05       0  5019.7      .1       0
    5146     .15       0  5462.2    .035       0  5824.1     .05       0
Bank Sta=5011,5019.7
XS Rating Curve= 0 ,0
Exp/Cntr=0.3,0.1

Type RM Length L Ch R = 1 ,15481   ,426,426,426
BEGIN DESCRIPTION:
West Brook Creek 19.0
END DESCRIPTION:
XS GIS Cut Line= 3
      2553425.03       13817125.        2552625.       13817225.
      2551963.48     13817562.95
#Sta/Elev= 30
  4184.1  357.67  4392.3  356.59  4645.5  355.59  4872.5  354.25  4890.1  353.93
  4929.9  350.78  4970.2  349.29  4998.7  349.38  5004.3  348.52  5016.5  343.86
    5017  343.36  5025.3  343.86  5026.5  344.66  5035.3  345.38  5057.7  350.91
  5080.2  351.15  5109.8  350.28  5161.7  350.75  5226.5  351.67  5271.1  350.24
  5287.5  350.72  5304.1  352.33  5453.2  354.04  5518.1  354.97  5540.6  356.33
  5548.5   355.6  5554.2  356.17  5615.2  356.36    5643  355.83  5733.2     357
#Mann= 9 ,-1 , 0
  4184.1     .07       0  4392.3    .035       0  4645.5      .1       0
  4872.5     .12       0  4890.1      .1       0  5016.5     .05       0
  5025.3      .1       0  5161.7    .035       0  5453.2     .05       0
Bank Sta=5016.5,5025.3
XS Rating Curve= 0 ,0
Exp/Cntr=0.3,0.1

Type RM Length L Ch R = 1 ,15055   ,427,427,427
BEGIN DESCRIPTION:
West Brook Creek 18.0
END DESCRIPTION:
XS GIS Cut Line= 3
      2553224.96       13816925.        2552425.       13816875.
      2551624.97     13817125.01
#Sta/Elev= 30
  4198.8  356.34  4235.4  356.64  4479.3  354.78  4539.4  356.79    4602  354.66
  4639.6  358.09  4669.7  354.27    4728  352.74  4799.9  348.71    4850  351.13
  4880.1  349.21  4960.2  350.31  4975.3  341.63  4975.8  341.13  4985.2  341.63
  4997.8  349.71    5114  349.24  5314.1  352.52  5319.3  348.07  5346.1  348.87
  5351.8  347.24  5377.5  352.25  5481.7  352.52  5513.7  348.38  5524.7  352.47
  5545.1   351.5  5649.5   356.2  5699.5  357.43  5751.4   359.4  5838.5  362.07
#Mann= 8 ,-1 , 0
  4198.8     .07       0  4235.4    .035       0    4728      .1       0
  4975.3     .05       0  4985.2      .1       0  5649.5     .07       0
  5699.5      .1       0  5751.4     .05       0
Bank Sta=4975.3,4985.2
XS Rating Curve= 0 ,0
Exp/Cntr=0.3,0.1

Type RM Length L Ch R = 1 ,14628   ,447,447,447
BEGIN DESCRIPTION:
West Brook Creek 17.0
END DESCRIPTION:
XS GIS Cut Line= 3
      2553324.97       13816475.        2552125.       13816675.
      2551474.99     13817175.01
#Sta/Elev= 30
  3787.4  358.08  4081.4  354.26  4436.2  352.91    4497  354.61    4616   352.4
  4622.5   352.1  4679.5  349.88  4721.8     350  4788.5  348.13    4832   348.4
  4882.3  347.69    4976  349.78  5007.1  346.96  5011.2  344.63  5020.7  343.03
  5021.2  342.53  5030.7  343.03    5032  345.22  5040.2  348.65  5054.4  349.67
    5061  348.12  5075.5  348.42  5094.4  350.72  5131.7   352.5  5331.1  354.07
  5401.9  356.29  5528.9   357.7  5623.7  359.74  5746.1  365.51    5824  366.91
#Mann= 11 ,-1 , 0
  3787.4     .05       0    4616     .07       0  4622.5      .1       0
  4721.8     .07       0    4832      .1       0  5020.7     .05       0
  5030.7      .1       0  5094.4     .07       0  5331.1      .1       0
  5401.9     .07       0  5528.9     .05       0
Bank Sta=5020.7,5030.7
XS Rating Curve= 0 ,0
Exp/Cntr=0.3,0.1

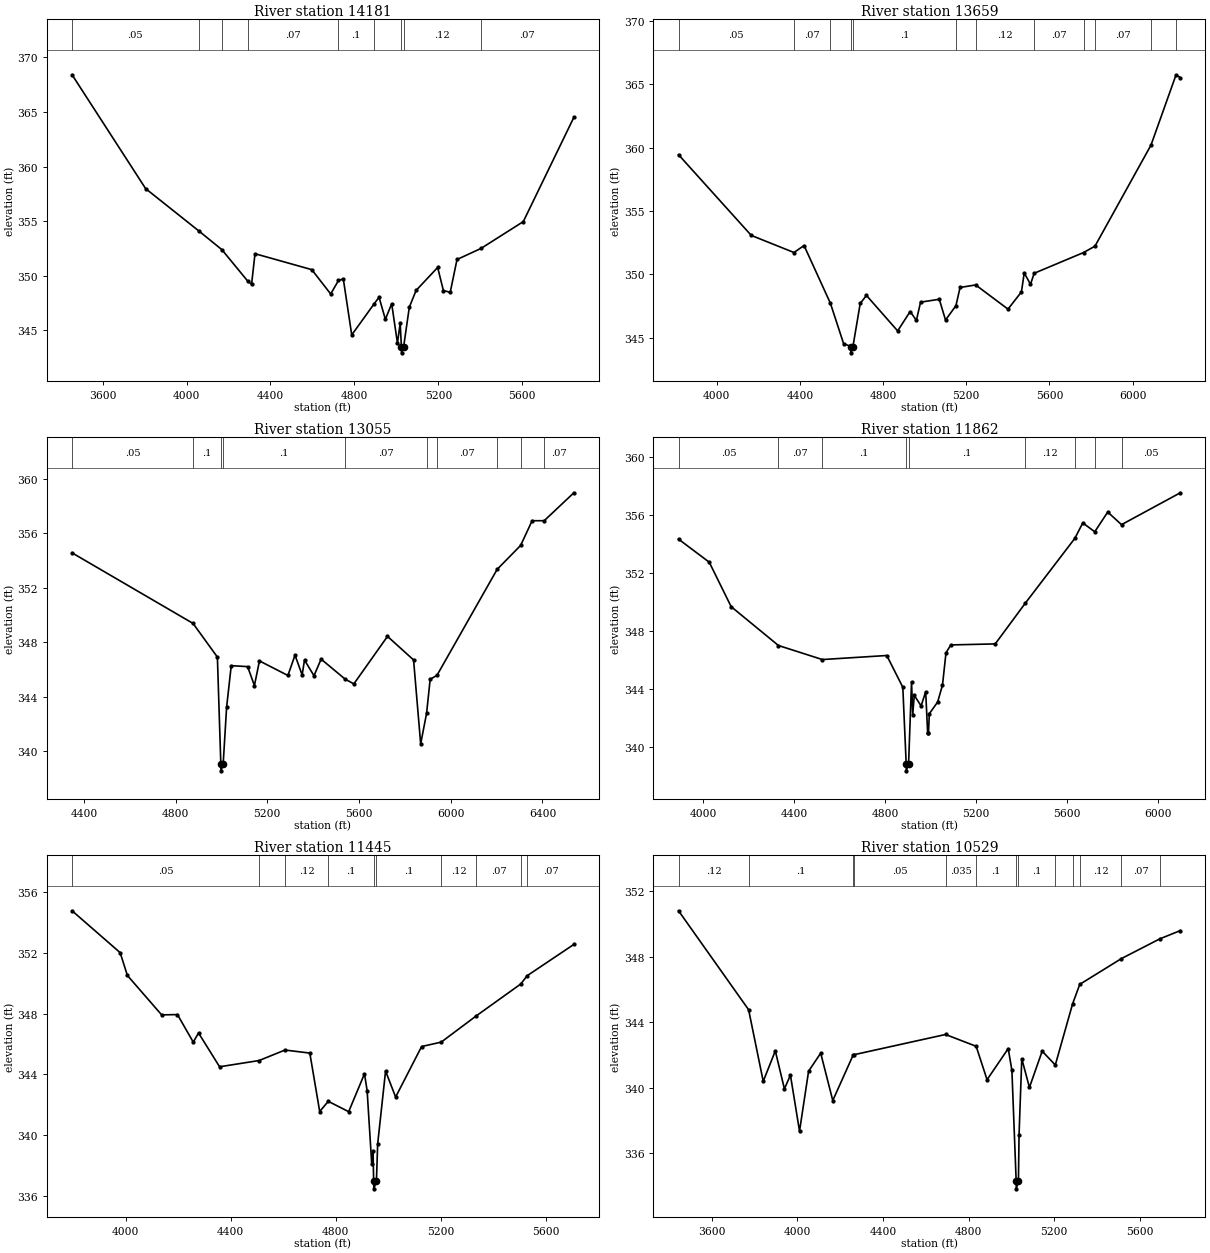
Type RM Length L Ch R = 1 ,14181   ,522,522,522
BEGIN DESCRIPTION:
West Brook Creek 16.0
END DESCRIPTION:
XS GIS Cut Line= 3
        2553625.       13816175.        2552075.       13816275.
      2551274.98     13816525.01
#Sta/Elev= 30
  3454.4  368.41  3805.1  357.98  4057.6  354.12  4168.4  352.39    4292   349.5
  4309.9  349.22  4326.2  352.02  4596.8  350.56    4687  348.33    4724  349.57
  4747.1  349.71  4787.2  344.58  4893.6  347.42  4917.4  348.03  4947.5  346.01
  4977.6  347.44  5005.1  343.83  5018.1  345.65  5024.1  343.44  5024.6  342.94
  5034.1  343.44  5061.6  347.12  5094.1  348.66  5196.7  350.76    5224  348.65
  5256.5  348.48  5288.9  351.49    5403   352.5  5604.8  354.96  5845.8  364.51
#Mann= 9 ,-1 , 0
  3454.4     .05       0  4057.6     .07       0  4168.4     .12       0
    4292     .07       0    4724      .1       0  4893.6     .12       0
  5024.1     .05       0  5034.1     .12       0    5403     .07       0
Bank Sta=5024.1,5034.1
XS Rating Curve= 0 ,0
Exp/Cntr=0.3,0.1

Type RM Length L Ch R = 1 ,13659   ,604,604,604
BEGIN DESCRIPTION:
H21570
END DESCRIPTION:
XS GIS Cut Line= 3
      2553358.35      13815838.2      2551979.51     13815805.95
      2551118.37     13816377.36
#Sta/Elev= 30
  3816.6  359.45  4166.3  353.08  4371.6  351.73  4420.1  352.28  4546.9  347.72
  4610.2  344.54  4645.1  344.31  4645.6  343.81  4655.2  344.31  4690.2  347.71
  4720.2  348.34  4870.2  345.54  4930.3  347.07  4960.3  346.37  4980.3  347.81
  5070.3  348.04  5100.3   346.4  5150.3  347.53  5170.3  348.97  5245.2  349.17
  5400.7  347.26  5465.3  348.62  5478.8  350.12  5508.9  349.22  5526.6  350.09
  5764.4  351.73  5818.9  352.23  6088.3  360.21  6208.8  365.76  6229.3  365.54
#Mann= 12 ,-1 , 0
  3816.6     .05       0  4371.6     .07       0  4546.9      .1       0
  4645.1     .05       0  4655.2      .1       0  5150.3     .07       0
  5245.2     .12       0  5526.6     .07       0  5764.4     .12       0
  5818.9     .07       0  6088.3    .035       0  6208.8     .12       0
Bank Sta=4645.1,4655.2
XS Rating Curve= 0 ,0
Exp/Cntr=0.3,0.1

Type RM Length L Ch R = 1 ,13055   ,1193,1193,1193
BEGIN DESCRIPTION:
West Brook Creek 15.0
END DESCRIPTION:
XS GIS Cut Line= 3
      2553164.82     13815443.09      2552439.13     13815362.46
      2551028.99     13815733.12
#Sta/Elev= 30
  4348.6  354.56  4876.2  349.38  4982.3  346.91  4997.3  339.06  4997.8  338.56
  5007.5  339.06  5022.5  343.23  5042.7  346.28  5114.1  346.21  5143.8  344.82
  5165.7  346.63  5289.8  345.56  5320.8  347.05  5351.9   345.6  5362.2  346.69
  5403.6  345.54  5434.6  346.76  5538.8   345.3  5577.3  344.94  5724.1  348.43
  5837.8   346.7  5868.8  340.54  5894.5  342.78  5910.2  345.28  5939.9  345.57
  6202.3  353.35  6304.9  355.11  6354.8  356.92  6407.5  356.92  6536.8  358.97
#Mann= 10 ,-1 , 0
  4348.6     .05       0  4876.2      .1       0  4997.3     .05       0
  5007.5      .1       0  5538.8     .07       0  5894.5     .12       0
  5939.9     .07       0  6202.3     .12       0  6304.9    .035       0
  6407.5     .07       0
Bank Sta=4997.3,5007.5
XS Rating Curve= 0 ,0
Exp/Cntr=0.3,0.1

Type RM Length L Ch R = 1 ,11862   ,417,417,417
BEGIN DESCRIPTION:
West Brook Creek 14.0
END DESCRIPTION:
XS GIS Cut Line= 3
        2552975.       13814925.      2551882.75     13815047.98
      2550939.66     13815628.34
#Sta/Elev= 30
  3891.7  354.32  4026.7  352.73  4123.1  349.66    4331  346.98  4524.1  346.01
  4807.4  346.29  4877.9   344.1  4892.7  338.83  4893.2  338.33  4903.3  338.83
  4916.3  344.48  4921.4  342.19  4928.2  343.54  4958.4  342.81  4978.5  343.79
  4987.2  340.92  4990.8  340.92  4994.4  342.27  5031.1  343.08  5052.4  344.25
  5067.8  346.48  5089.1  347.02  5284.3  347.09  5416.5   349.9  5634.6  354.38
  5669.2  355.44  5721.9  354.83  5778.9  356.19  5839.6  355.32  6098.2  357.52
#Mann= 9 ,-1 , 0
  3891.7     .05       0    4331     .07       0  4524.1      .1       0
  4892.7     .05       0  4903.3      .1       0  5416.5     .12       0
  5634.6     .07       0  5721.9    .035       0  5839.6     .05       0
Bank Sta=4892.7,4903.3
XS Rating Curve= 0 ,0
Exp/Cntr=0.3,0.1

Type RM Length L Ch R = 1 ,11445   ,916,916,916
BEGIN DESCRIPTION:
West Brook Creek 13.0
END DESCRIPTION:
XS GIS Cut Line= 3
      2552974.99       13814775.        2551775.       13814675.
      2551274.97     13815175.03
#Sta/Elev= 30
  3795.6  354.75  3978.7     352  4006.3   350.5  4136.8  347.91    4197  347.93
  4257.2  346.12  4277.3  346.72  4357.5   344.5  4507.9  344.91  4606.6   345.6
  4701.2   345.4  4738.8  341.56  4771.5  342.23  4849.2  341.55  4909.4  344.04
  4919.5  342.93    4937  338.11  4942.1  338.96  4944.3  336.98  4944.8  336.48
  4954.9  336.98  4959.6  339.43  4989.7  344.22    5028  342.51    5127  345.83
  5201.6  346.12  5335.6  347.85  5504.7  349.94  5528.8  350.48  5706.9  352.54
#Mann= 10 ,-1 , 0
  3795.6     .05       0  4507.9     .07       0  4606.6     .12       0
  4771.5      .1       0  4944.3     .05       0  4954.9      .1       0
  5201.6     .12       0  5335.6     .07       0  5504.7     .12       0
  5528.8     .07       0
Bank Sta=4944.3,4954.9
XS Rating Curve= 0 ,0
Exp/Cntr=0.3,0.1

Type RM Length L Ch R = 1 ,10529   ,455,455,455
BEGIN DESCRIPTION:
West Brook Creek 12.0
END DESCRIPTION:
XS GIS Cut Line= 3
      2552774.98     13813075.02        2551675.       13814175.
      2551224.99     13814825.02
#Sta/Elev= 30
  3444.1  350.81  3771.8  344.77  3840.1   340.4  3896.6  342.26  3939.1  339.94
  3967.3  340.78  4009.8  337.36  4052.2  341.02  4108.8  342.12  4165.3  339.23
  4259.7  341.98  4262.5  342.02  4692.4  343.26  4835.7  342.54  4886.6   340.5
  4985.6   342.4  5002.8  341.07  5022.7  334.34  5023.2  333.84  5033.4  334.34
  5036.2  337.13    5049  341.78  5084.8  340.03  5144.3  342.24  5205.8   341.4
  5286.6  345.13  5320.2  346.32  5514.6  347.89    5695   349.1  5790.3   349.6
#Mann= 13 ,-1 , 0
  3444.1     .12       0  3771.8      .1       0  4259.7     .07       0
  4262.5     .05       0  4692.4    .035       0  4835.7      .1       0
  5022.7     .05       0  5033.4      .1       0  5205.8     .07       0
  5286.6      .1       0  5320.2     .12       0  5514.6     .07       0
    5695    .035       0
Bank Sta=5022.7,5033.4
XS Rating Curve= 0 ,0
Exp/Cntr=0.3,0.1