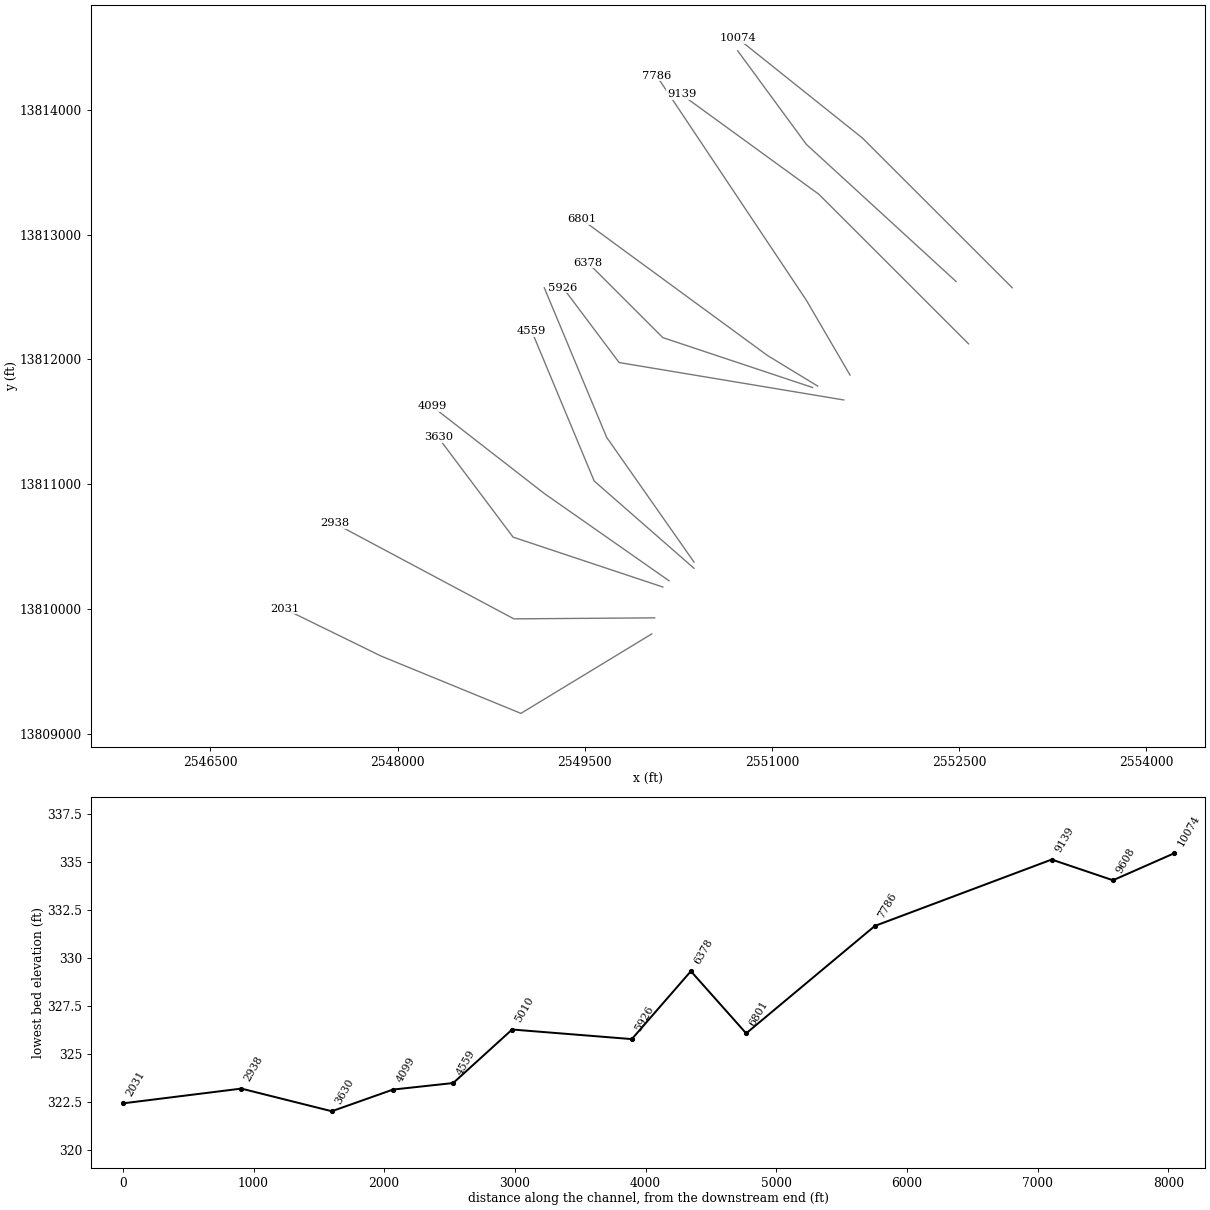
HEC-RAS study West Brook Creek.prj: West Brook Creek Base Level Engineering

--- West Brook Creek.g01 (geometry) --- (continued)

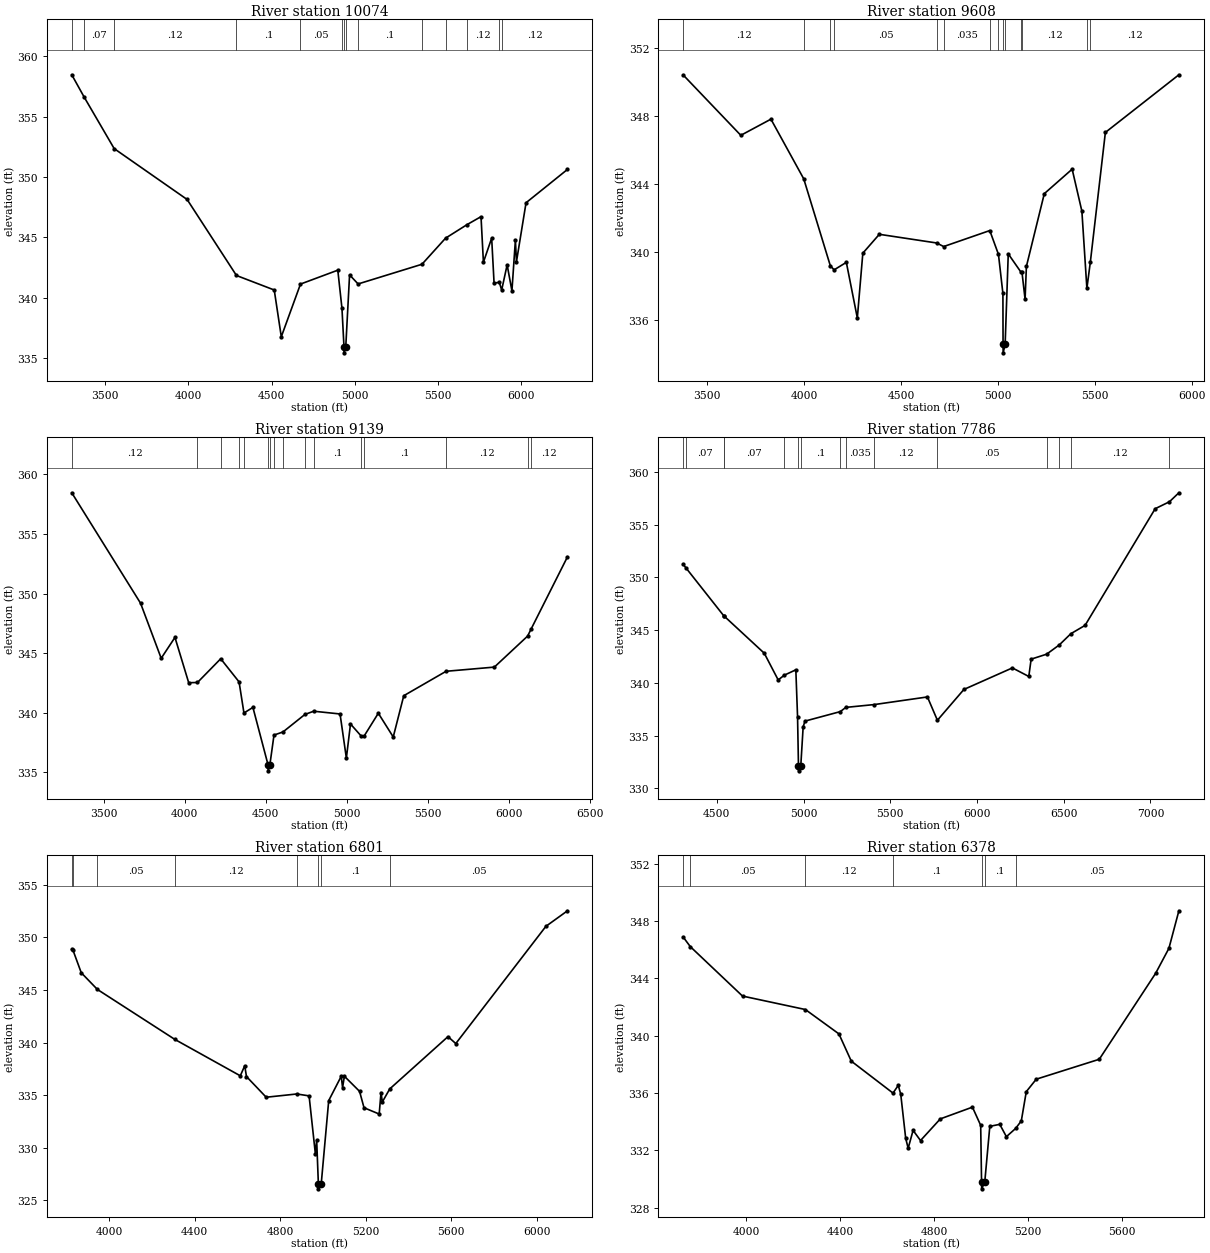
Type RM Length L Ch R = 1 ,10074   ,466,466,466
BEGIN DESCRIPTION:
West Brook Creek 11.0
END DESCRIPTION:
XS GIS Cut Line= 3
      2552924.97     13812575.03        2551725.       13813775.
      2550725.03     13814574.98
#Sta/Elev= 30
  3299.1  358.46  3373.7  356.61  3553.9  352.35    3992  348.14  4288.4  341.85
  4515.3  340.65  4557.7  336.78  4672.9  341.14  4897.1  342.29  4922.1  339.13
  4934.2  335.95  4934.7  335.45  4944.9  335.95  4967.8   341.9    5019  341.15
  5402.7  342.78  5544.4  344.94  5673.4  346.06  5757.3  346.72  5771.7  342.95
  5821.3  344.94  5835.7  341.23  5867.2  341.28  5881.4  340.65  5914.2  342.73
    5943  340.58  5963.8  344.78  5970.2  342.99  6027.8  347.87  6276.7  350.63
#Mann= 14 ,-1 , 0
  3299.1     .12       0  3373.7     .07       0  3553.9     .12       0
  4288.4      .1       0  4672.9     .05       0  4922.1    .035       0
  4934.2    .035       0  4944.9    .035       0    5019      .1       0
  5402.7     .07       0  5544.4    .035       0  5673.4     .12       0
  5867.2      .1       0  5881.4     .12       0
Bank Sta=4934.2,4944.9
XS Rating Curve= 0 ,0
Exp/Cntr=0.3,0.1

Type RM Length L Ch R = 1 ,9608    ,469,469,469
BEGIN DESCRIPTION:
West Brook Creek 10.0
END DESCRIPTION:
XS GIS Cut Line= 3
      2552475.01     13812624.99        2551275.       13813725.
      2550725.03     13814474.96
#Sta/Elev= 30
  3376.3  350.39  3673.8  346.84  3829.2  347.79  3998.5  344.28  4135.7  339.17
  4155.3  338.93  4218.3  339.37    4275   336.1  4303.4  339.91  4388.5  341.02
  4684.2  340.51  4720.6   340.3  4958.5  341.24  5003.2  339.84  5026.2  337.54
    5027  334.55  5027.5  334.05  5037.7  334.55  5053.8  339.87  5119.7  338.79
  5124.7  338.78  5140.6   337.2  5147.4  339.13  5239.8  343.41  5383.5  344.85
  5433.7  342.38  5459.5  337.84  5477.6  339.41  5554.9  347.01  5934.2   350.4
#Mann= 14 ,-1 , 0
  3376.3     .12       0  3998.5    .035       0  4135.7      .1       0
  4155.3     .05       0  4684.2      .1       0  4720.6    .035       0
  4958.5      .1       0  5003.2    .035       0    5027     .05       0
  5037.7    .035       0  5119.7      .1       0  5124.7     .12       0
  5459.5      .1       0  5477.6     .12       0
Bank Sta=5027,5037.7
XS Rating Curve= 0 ,0
Exp/Cntr=0.3,0.1

Type RM Length L Ch R = 1 ,9139    ,1353,1353,1353
BEGIN DESCRIPTION:
West Brook Creek 9.0
END DESCRIPTION:
XS GIS Cut Line= 3
      2552574.97     13812125.03        2551375.       13813325.
      2550274.97     13814125.02
#Sta/Elev= 30
  3303.2  358.45  3727.4  349.19  3854.7  344.57  3939.6  346.32  4024.4  342.52
  4078.5  342.54  4221.8  344.53    4335  342.59  4365.1  339.98  4420.4  340.45
  4513.8  335.63  4514.3  335.13  4524.9  335.63  4550.4  338.13  4605.7  338.39
  4741.1  339.86  4795.1  340.13  4957.8   339.9  4996.7   336.2  5022.2  339.06
  5089.3  338.03  5106.3  338.05  5193.8  339.96  5285.8  337.97  5350.7  341.43
  5611.9  343.48  5909.4  343.83  6114.4  346.43  6137.1  347.05  6360.4  353.08
#Mann= 16 ,-1 , 0
  3303.2     .12       0  4078.5    .035       0  4221.8      .1       0
    4335     .05       0  4365.1      .1       0  4513.8     .05       0
  4524.9      .1       0  4550.4     .05       0  4605.7      .1       0
  4741.1     .05       0  4795.1      .1       0  5089.3     .05       0
  5106.3      .1       0  5611.9     .12       0  6114.4     .07       0
  6137.1     .12       0
Bank Sta=4513.8,4524.9
XS Rating Curve= 0 ,0
Exp/Cntr=0.3,0.1

Type RM Length L Ch R = 1 ,7786    ,985,985,985
BEGIN DESCRIPTION:
West Brook Creek 8.0
END DESCRIPTION:
XS GIS Cut Line= 3
      2551625.02     13811874.97        2551275.       13812475.
      2550074.99     13814275.01
#Sta/Elev= 30
  4305.9  351.24  4321.7   350.9  4539.4  346.37  4542.7  346.32  4773.6  342.81
  4853.8  340.28    4889  340.73  4955.5  341.24  4965.4  336.81  4970.7  332.17
  4971.2  331.67  4984.1  332.17  4997.7  335.83  5008.1  336.38  5211.8  337.28
  5243.7  337.68  5408.8  337.95  5714.2  338.67  5771.7  336.46  5924.5  339.38
  6203.9  341.42  6298.6  340.61  6312.1  342.25  6401.4  342.72  6474.6   343.6
  6541.1  344.66  6623.1  345.45  7027.2   356.5  7109.5  357.16  7163.9  358.01
#Mann= 15 ,-1 , 0
  4305.9    .035       0  4321.7     .07       0  4539.4     .05       0
  4542.7     .07       0    4889      .1       0  4970.7     .05       0
  4984.1      .1       0  5211.8     .12       0  5243.7    .035       0
  5408.8     .12       0  5771.7     .05       0  6401.4     .07       0
  6474.6     .05       0  6541.1     .12       0  7109.5     .07       0
Bank Sta=4970.7,4984.1
XS Rating Curve= 0 ,0
Exp/Cntr=0.3,0.1

Type RM Length L Ch R = 1 ,6801    ,423,423,423
BEGIN DESCRIPTION:
West Brook Creek 7.0
END DESCRIPTION:
XS GIS Cut Line= 3
      2551366.62     13811786.06      2550963.96     13812031.37
      2549473.51     13813123.75
#Sta/Elev= 30
  3825.2  348.87  3830.7   348.8  3869.6  346.64  3945.2  345.05  4307.9  340.29
  4613.7  336.83  4634.5  337.79  4642.6  336.76  4734.9  334.79  4878.1   335.1
  4935.6  334.92  4964.9  329.42  4971.1   330.7    4979  326.57  4979.5  326.07
  4992.5  326.57  5027.4  334.47  5086.1  336.79  5092.3   335.7  5100.7  336.79
  5171.8  335.35  5192.6  333.79  5263.6  333.19  5272.1  335.24  5278.3  334.34
  5312.9  335.58  5585.5  340.56    5622   339.9  6043.6  351.06  6144.6  352.54
#Mann= 8 ,-1 , 0
  3825.2     .07       0  3830.7    .035       0  3945.2     .05       0
  4307.9     .12       0  4878.1      .1       0    4979     .05       0
  4992.5      .1       0  5312.9     .05       0
Bank Sta=4979,4992.5
XS Rating Curve= 0 ,0
Exp/Cntr=0.3,0.1

Type RM Length L Ch R = 1 ,6378    ,452,452,452
BEGIN DESCRIPTION:
West Brook Creek 6.0
END DESCRIPTION:
XS GIS Cut Line= 3
      2551325.03     13811774.99        2550125.       13812175.
      2549524.98     13812775.02
#Sta/Elev= 30
  3730.4  346.88  3760.8  346.21  3983.4  342.76  4251.5  341.82  4394.5  340.12
  4447.2  338.22  4625.1  335.99  4647.5  336.53    4658  335.92  4679.1  332.84
  4689.7  332.14  4710.7  333.39  4742.4  332.68  4826.7  334.19  4963.7  335.01
  4998.9  333.74  5002.6  329.81  5003.1  329.31  5016.4  329.81  5037.8  333.67
  5080.2  333.81  5108.5  332.95  5147.7  333.52  5172.1  334.05  5193.3  336.09
  5235.8  336.96  5504.5  338.35  5744.9  344.35  5801.4  346.09  5843.9  348.71
#Mann= 7 ,-1 , 0
  3730.4    .035       0  3760.8     .05       0  4251.5     .12       0
  4625.1      .1       0  5002.6     .05       0  5016.4      .1       0
  5147.7     .05       0
Bank Sta=5002.6,5016.4
XS Rating Curve= 0 ,0
Exp/Cntr=0.3,0.1

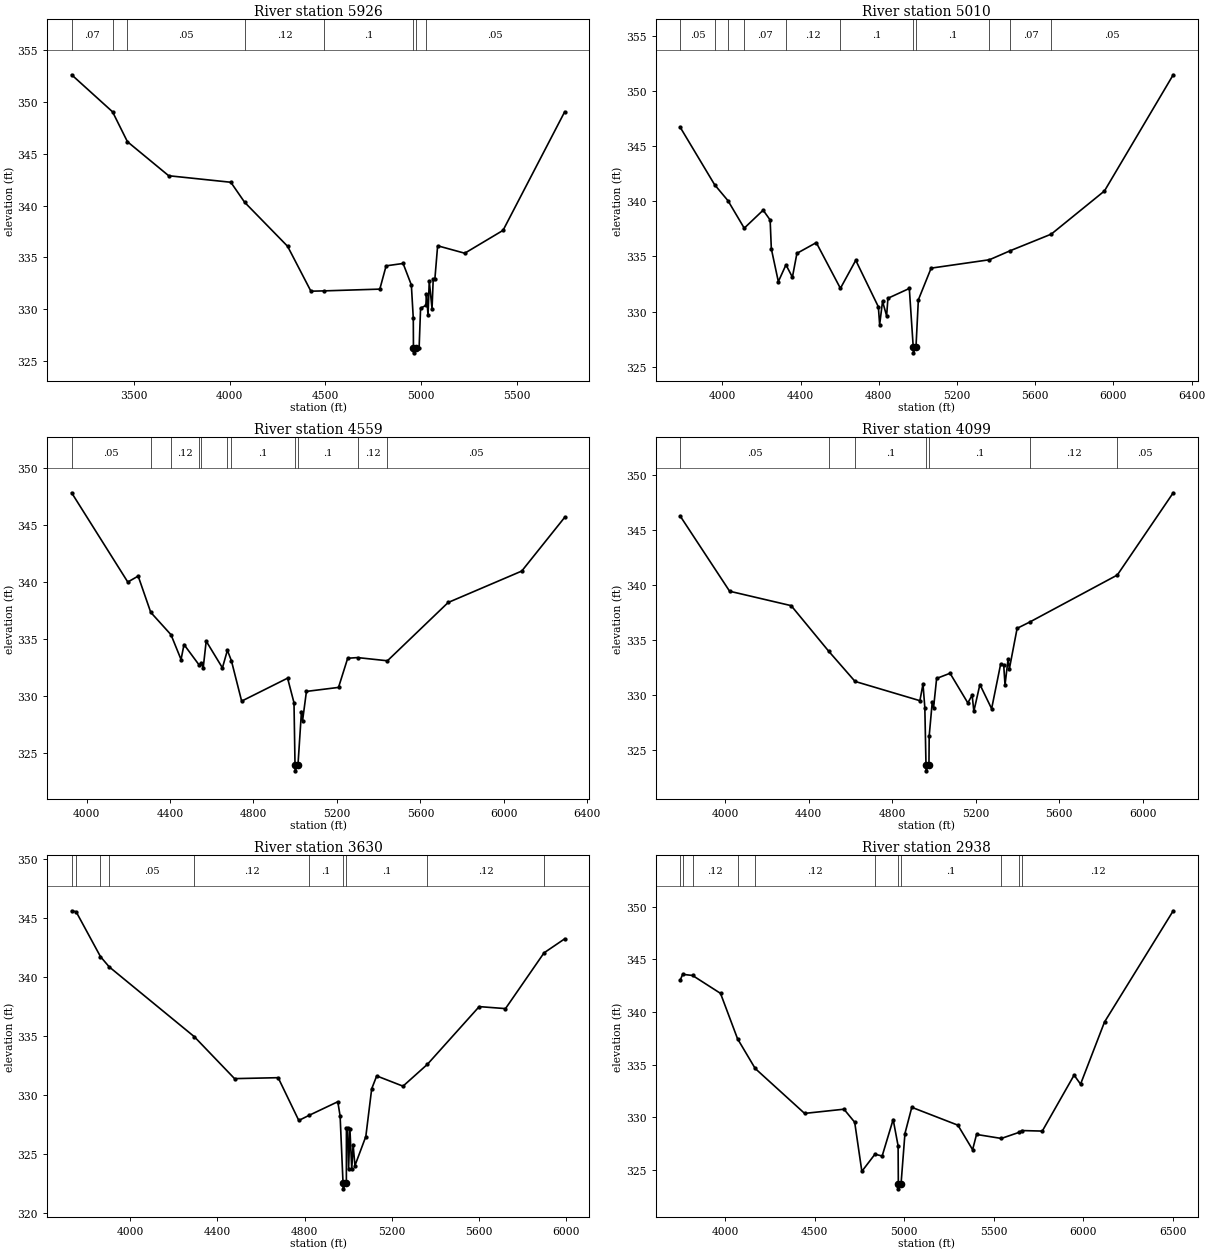
Type RM Length L Ch R = 1 ,5926    ,916,916,916
BEGIN DESCRIPTION:
West Brook Creek 5.0
END DESCRIPTION:
XS GIS Cut Line= 3
      2551574.97       13811675.        2549775.       13811975.
        2549325.       13812575.
#Sta/Elev= 30
  3174.5  352.65  3388.2  349.07  3465.9  346.18  3681.4  342.89  4005.8  342.26
  4078.1  340.32  4302.3  336.07    4424  331.73  4494.4  331.76  4783.9  331.93
  4816.8  334.18  4905.5  334.41  4948.6  332.33  4958.7   329.1  4959.5  326.27
    4960  325.77  4973.3  326.27  4989.2  326.27  4996.8  330.09  5024.4  330.35
  5027.4  331.48  5035.8  329.38    5042  332.73  5056.6  330.04  5062.8  332.92
  5071.2  332.86  5085.8  336.12  5227.4   335.4  5427.4  337.61  5749.3  349.07
#Mann= 8 ,-1 , 0
  3174.5     .07       0  3388.2    .035       0  3465.9     .05       0
  4078.1     .12       0  4494.4      .1       0  4959.5     .05       0
  4973.3      .1       0  5024.4     .05       0
Bank Sta=4959.5,4973.3
XS Rating Curve= 0 ,0
Exp/Cntr=0.3,0.1

Type RM Length L Ch R = 1 ,5010    ,451,451,451
BEGIN DESCRIPTION:
West Brook Creek 4.0
END DESCRIPTION:
XS GIS Cut Line= 3
      2550374.99     13810375.02        2549675.       13811375.
      2549175.01     13812574.97
#Sta/Elev= 30
  3784.9   346.7  3961.1  341.49  4029.2  340.05  4112.4  337.56  4209.1  339.19
  4244.8   338.3  4250.9  335.69  4286.7  332.72  4325.7  334.24  4358.6  333.12
  4381.7  335.28  4480.7  336.25    4604  332.11  4682.5  334.65    4798  330.44
  4804.6  328.82  4819.4  330.93  4840.3  329.62  4846.9  331.21  4956.3   332.1
  4976.4  326.77  4976.9  326.27  4990.3  326.77  5002.5  331.07  5067.8  333.94
  5365.9   334.7  5471.2  335.51    5682  337.02    5954  340.93  6305.5  351.45
#Mann= 11 ,-1 , 0
  3784.9     .05       0  3961.1    .035       0  4029.2     .05       0
  4112.4     .07       0  4325.7     .12       0    4604      .1       0
  4976.4     .05       0  4990.3      .1       0  5365.9     .05       0
  5471.2     .07       0    5682     .05       0
Bank Sta=4976.4,4990.3
XS Rating Curve= 0 ,0
Exp/Cntr=0.3,0.1

Type RM Length L Ch R = 1 ,4559    ,460,460,460
BEGIN DESCRIPTION:
West Brook Creek 3.0
END DESCRIPTION:
XS GIS Cut Line= 3
      2550374.98     13810325.01        2549575.       13811025.
        2549075.     13812225.01
#Sta/Elev= 30
  3928.4  347.81  4197.5     340  4247.3  340.52  4307.5  337.35  4404.6  335.39
  4452.8  333.22    4467  334.53  4540.7  332.71  4549.4   332.9  4559.1  332.51
  4573.3  334.83  4651.1  332.49  4674.9  334.03  4694.2  333.11  4743.2  329.58
  4963.4  331.59  4994.1  329.44    4999  323.98  4999.5  323.48  5013.1  323.98
  5029.9  328.67  5035.3  327.88  5053.7  330.43  5207.5  330.78  5251.4  333.33
  5298.6  333.39  5441.9  333.11  5732.9  338.21  6085.6  340.96  6291.4  345.66
#Mann= 11 ,-1 , 0
  3928.4     .05       0  4307.5     .07       0  4404.6     .12       0
  4540.7     .05       0  4549.4      .1       0  4674.9     .12       0
  4694.2      .1       0    4999     .05       0  5013.1      .1       0
  5298.6     .12       0  5441.9     .05       0
Bank Sta=4999,5013.1
XS Rating Curve= 0 ,0
Exp/Cntr=0.3,0.1

Type RM Length L Ch R = 1 ,4099    ,469,469,469
BEGIN DESCRIPTION:
West Brook Creek 2.0
END DESCRIPTION:
XS GIS Cut Line= 3
      2550174.97     13810225.02        2549175.       13810925.
        2548275.       13811625.
#Sta/Elev= 30
    3785  346.28  4021.7  339.45  4316.4  338.14  4495.8  334.01  4622.3  331.26
  4932.8  329.51  4947.6  331.02  4956.4  328.89    4962  323.64  4962.5  323.14
  4976.1  323.64  4977.3  326.31  4992.1  329.42  4998.2  328.86  5012.9  331.53
  5077.1     332  5162.2  329.31    5183  330.01  5191.1  328.55  5220.1  330.98
  5276.2  328.78  5319.6  332.85  5334.1  332.73  5340.4  330.94  5354.9  333.27
  5361.2   332.4  5398.3  336.08  5458.6  336.65    5878  340.92  6145.8  348.39
#Mann= 7 ,-1 , 0
    3785     .05       0  4495.8     .12       0  4622.3      .1       0
    4962     .05       0  4976.1      .1       0  5458.6     .12       0
    5878     .05       0
Bank Sta=4962,4976.1
XS Rating Curve= 0 ,0
Exp/Cntr=0.3,0.1

Type RM Length L Ch R = 1 ,3630    ,692,692,692
BEGIN DESCRIPTION:
West Brook Creek 1.0
END DESCRIPTION:
XS GIS Cut Line= 3
      2550124.98     13810175.01        2548925.       13810575.
        2548325.       13811375.
#Sta/Elev= 30
  3730.1   345.6  3750.7  345.52  3862.6  341.71  3902.8  340.84  4293.5  334.92
  4478.5  331.36  4678.8  331.44  4773.6  327.81  4820.3  328.24  4952.8   329.4
  4963.4  328.19  4976.8  322.51  4977.3  322.01  4992.1  322.51  4992.4  327.16
  4998.1  327.16  5002.3  323.67  5008.5  327.06  5016.9  323.69  5023.1  325.77
  5031.5  323.98  5081.5  326.45  5108.5   330.5  5131.5  331.59  5252.3  330.72
  5364.2  332.57  5602.3  337.47  5723.1   337.3  5900.1  342.03    5995  343.22
#Mann= 10 ,-1 , 0
  3730.1     .07       0  3750.7     .05       0  3862.6     .07       0
  3902.8     .05       0  4293.5     .12       0  4820.3      .1       0
  4976.8     .05       0  4992.1      .1       0  5364.2     .12       0
  5900.1     .05       0
Bank Sta=4976.8,4992.1
XS Rating Curve= 0 ,0
Exp/Cntr=0.3,0.1

Type RM Length L Ch R = 1 ,2938    ,907,907,907
BEGIN DESCRIPTION:
H21569
END DESCRIPTION:
XS GIS Cut Line= 3
      2550060.35     13809927.63      2548931.49     13809919.56
      2547496.21     13810685.59
#Sta/Elev= 30
  3747.5  343.02  3761.3  343.58  3816.8  343.47  3972.9  341.77  4068.2  337.45
  4166.7  334.63  4442.9  330.36  4662.9  330.76  4722.9  329.52  4762.9  324.85
    4836  326.48  4876.4  326.31  4937.9  329.78  4965.5  327.28  4966.8  323.69
  4967.3  323.19  4982.1  323.69  5003.8  328.45    5042  330.94  5299.8  329.24
  5381.9  326.91  5403.9  328.36  5542.4  327.98  5641.8  328.56  5657.3  328.73
  5771.4  328.68  5949.2     334  5985.3  333.14  6119.3  339.05  6503.3  349.62
#Mann= 11 ,-1 , 0
  3747.5     .05       0  3761.3     .07       0  3816.8     .12       0
  4068.2     .07       0  4166.7     .12       0    4836      .1       0
  4966.8     .05       0  4982.1      .1       0  5542.4     .12       0
  5641.8      .1       0  5657.3     .12       0
Bank Sta=4966.8,4982.1
XS Rating Curve= 0 ,0
Exp/Cntr=0.3,0.1

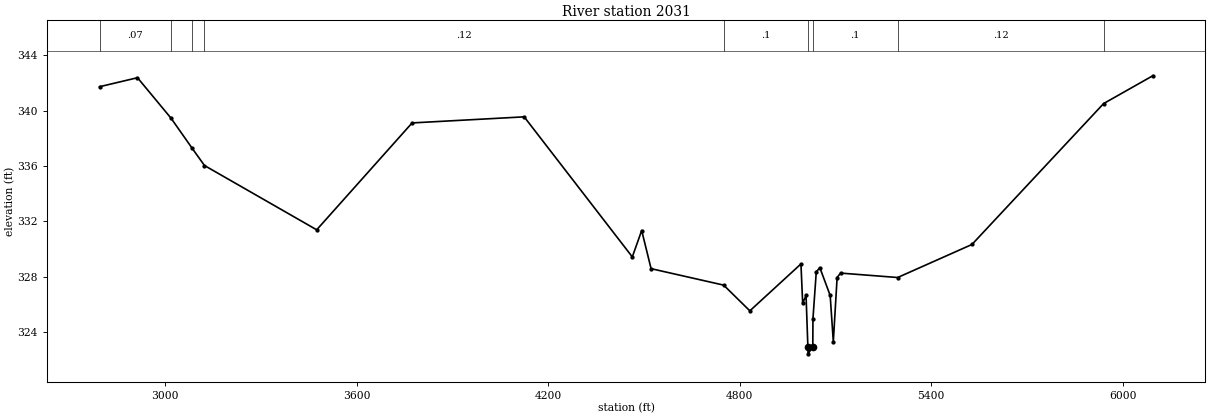
Type RM Length L Ch R = 1 ,2031    ,0,0,0
BEGIN DESCRIPTION:
H21568
END DESCRIPTION:
XS GIS Cut Line= 4
      2550036.22     13809798.62      2548987.94     13809161.59
       2547867.1     13809621.21      2547093.24     13810000.08
#Sta/Elev= 30
  2794.9  341.74  2913.5  342.39  3018.7  339.46  3084.7  337.29  3123.4  336.04
    3475  331.39  3773.9  339.12  4125.1  339.56  4463.9  329.43  4493.3  331.34
  4522.7  328.58  4750.1  327.39  4832.2  325.53  4992.3  328.92  4997.7  326.08
  5008.3  326.64    5014  322.92  5014.5  322.42  5029.4  322.92  5029.9  324.96
  5040.3  328.35  5051.5  328.65  5083.9  326.64  5093.7  323.29  5105.6  327.94
  5116.4  328.26  5295.3  327.94  5528.1  330.33  5940.6  340.52  6094.6  342.53
#Mann= 9 ,-1 , 0
  2794.9     .07       0  3018.7     .12       0  3084.7     .07       0
  3123.4     .12       0  4750.1      .1       0    5014     .05       0
  5029.4      .1       0  5295.3     .12       0  5940.6     .05       0
Bank Sta=5014,5029.4
XS Rating Curve= 0 ,0
Exp/Cntr=0.3,0.1

Chan Stop Cuts=-1
Use User Specified Reach Order=0
Composite Channel Slope=5