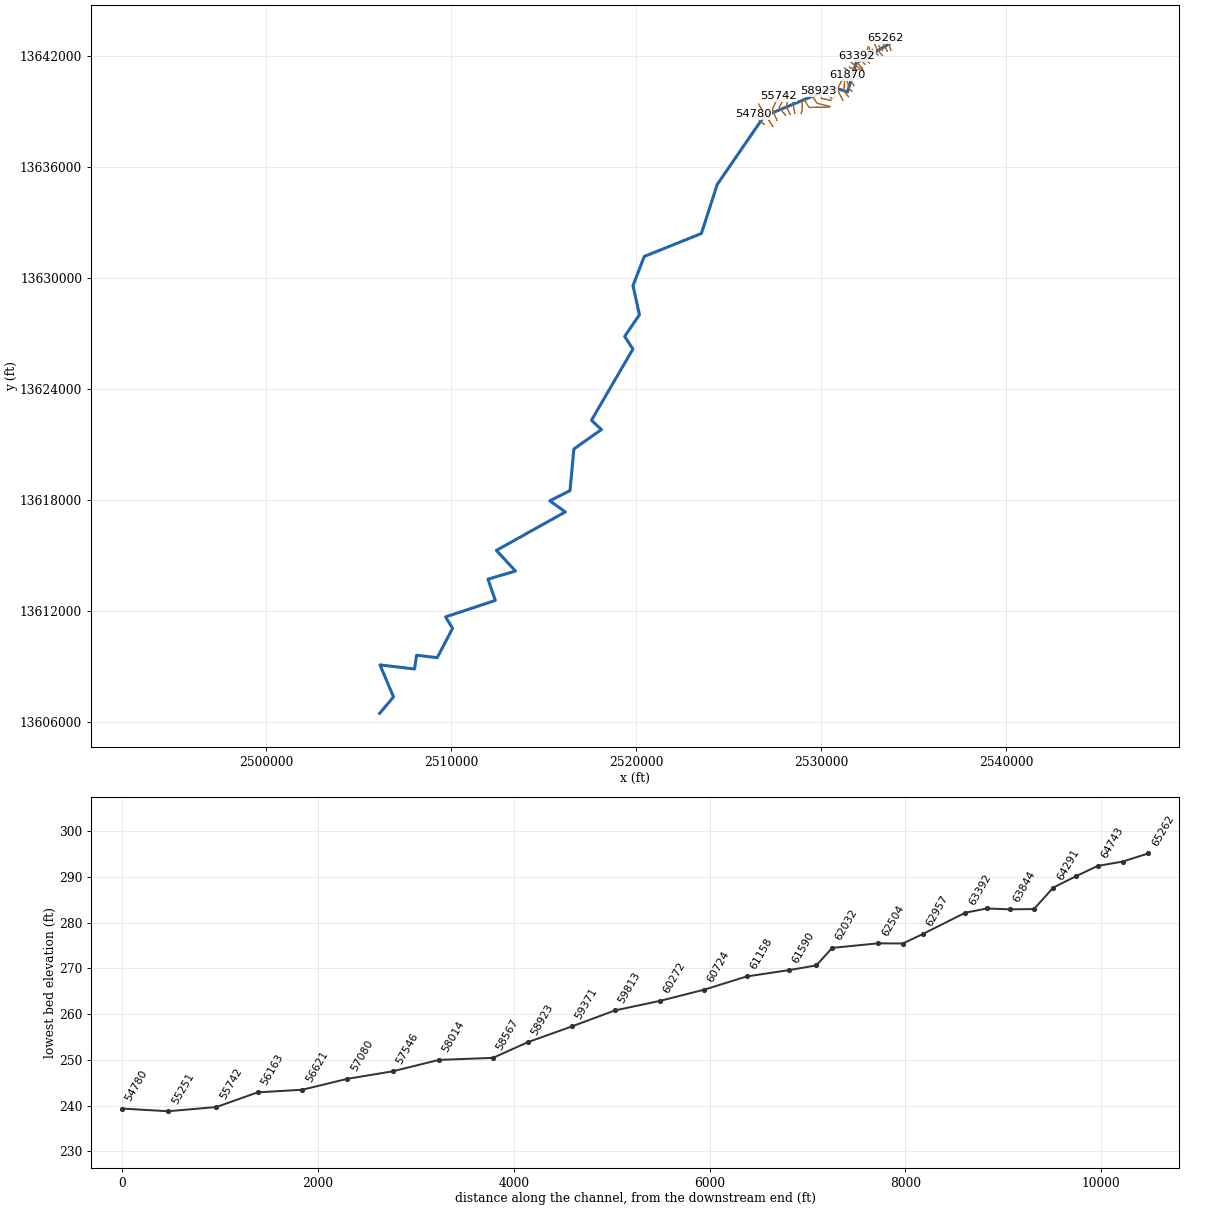
--- CUERO CREEK.prj (project) ---

Proj Title=CUERO CREEK Base Level Engineering
Current Plan=p01
Default Exp/Contr=0.3,0.1
English Units
Geom File=g01
Flow File=f01
Plan File=p01
Y Axis Title=Elevation
X Axis Title(PF)=Main Channel Distance
X Axis Title(XS)=Station
BEGIN DESCRIPTION:
CUERO CREEK
END DESCRIPTION:
DSS Export Rating Curves= 0
DSS Export Rating Curve Sorted= 0
DSS Export Volume Flow Curves= 0
DXF OffsetX= 0
DXF OffsetY= 0
DXF ScaleX= 1
DXF ScaleY= 10

--- CUERO CREEK.p01 (plan) ---

Plan Title=Multiple Run
Short Identifier=Multiple
Geom File=g01
Flow File=f01
Subcritical Flow
K Sum by GR= 0
Std Step Tol= 0.01
Critical Tol= 0.01
Num of Std Step Trials= 20
Max Error Tol= 0.3
Flow Tol Ratio= 0.001
Split Flow NTrial= 30
Split Flow Tol= 0.02
Split Flow Ratio= 0.02
Log Output Level= 0
Friction Slope Method= 1
Unsteady Friction Slope Method= 2
Unsteady Bridges Friction Slope Method= 1
Parabolic Critical Depth
Global Vel Dist=  1 , 1 , 1
Global Log Level= 0
CheckData=True
Encroach Param= -1, 0, 0, 0
BEGIN DESCRIPTION:
Multiple Run
END DESCRIPTION:

--- CUERO CREEK.f01 (steady flow) ---

Flow Title=Multiple
Program Version=4.10
Number of Profiles= 7
Profile Names=10-year,25-year,50-year,1pct_min,100-year,1pct_plu,500-year
River Rch & RM=CUERO CREEK,Reach-1         ,65262
     417     651     855     546    1089    2173    1746
River Rch & RM=CUERO CREEK,Reach-1         ,63844
     625     992    1318     848    1693    3377    2761
River Rch & RM=CUERO CREEK,Reach-1         ,59813
     906    1476    1998    1309    2611    5211    4416
River Rch & RM=CUERO CREEK,Reach-1         ,57546
    1376    2291    3147    2089    4168    8316    7239
River Rch & RM=CUERO CREEK,Reach-1         ,57080
    1352    2257    3103    2062    4115    8211    7166
River Rch & RM=CUERO CREEK,Reach-1         ,55251
    1587    2665    3678    2452    4893    9763    8578
River Rch & RM=CUERO CREEK,Reach-1         ,54311
    1904    3223    4472    2995    5976   11924   10575
River Rch & RM=CUERO CREEK,Reach-1         ,52050
    2098    3553    4931    3301    6586   13142   11644
River Rch & RM=CUERO CREEK,Reach-1         ,47475
    2039    3441    4763    3180    6346   12662   11161
River Rch & RM=CUERO CREEK,Reach-1         ,46964
    2974    5077    7083    4759    9496   18947   16915
River Rch & RM=CUERO CREEK,Reach-1         ,40575
    3068    5235    7299    4902    9780   19513   17397
River Rch & RM=CUERO CREEK,Reach-1         ,37041
    3054    5193    7224    4838    9654   19262   17083
River Rch & RM=CUERO CREEK,Reach-1         ,33129
    3013    5113    7101    4746    9470   18895   16695
River Rch & RM=CUERO CREEK,Reach-1         ,22303
    4637    7951   11122    7479   14922   29774   26619
Boundary for River Rch & Prof#=CUERO CREEK,Reach-1         , 1
Up Type= 0
Dn Type= 3
Dn Slope=0.0001
Boundary for River Rch & Prof#=CUERO CREEK,Reach-1         , 2
Up Type= 0
Dn Type= 3
Dn Slope=0.0001
Boundary for River Rch & Prof#=CUERO CREEK,Reach-1         , 3
Up Type= 0
Dn Type= 3
Dn Slope=0.0001
Boundary for River Rch & Prof#=CUERO CREEK,Reach-1         , 4
Up Type= 0
Dn Type= 3
Dn Slope=0.0001
Boundary for River Rch & Prof#=CUERO CREEK,Reach-1         , 5
Up Type= 0
Dn Type= 3
Dn Slope=0.0001
Boundary for River Rch & Prof#=CUERO CREEK,Reach-1         , 6
Up Type= 0
Dn Type= 3
Dn Slope=0.0001
Boundary for River Rch & Prof#=CUERO CREEK,Reach-1         , 7
Up Type= 0
Dn Type= 3
Dn Slope=0.0001
DSS Import GetInterval= 0
DSS Import GetPeak= 0
DSS Import FillOption= 0

--- CUERO CREEK.g01 (geometry) ---

Geom Title=Existing Conditions
Program Version=4.10

River Reach=CUERO CREEK     ,Reach-1
Reach XY= 30
        2533675.       13642675.      2531888.26     13641638.66
       2531427.3      13640080.8        2530675.       13640325.
      2526911.66     13638761.64      2524380.36      13635077.7
        2523525.       13632425.      2520435.77      13631184.7
      2519824.79     13629604.94      2520173.18     13628031.12
      2519375.09      13626859.6       2519821.9     13626176.65
      2517578.82     13622323.41      2518119.91      13621822.7
      2516628.44     13620773.78      2516419.55     13618522.54
      2515326.88     13617969.32       2516166.1     13617368.52
      2512438.37     13615288.32      2513470.04     13614172.46
      2511983.13     13613731.08      2512381.08     13612583.13
      2509691.64     13611691.68      2510067.49     13611071.85
      2509238.32     13609488.37      2508122.56     13609619.49
      2508009.84     13608875.34       2506144.4     13609095.66
      2506875.45     13607364.81        2506125.       13606475.

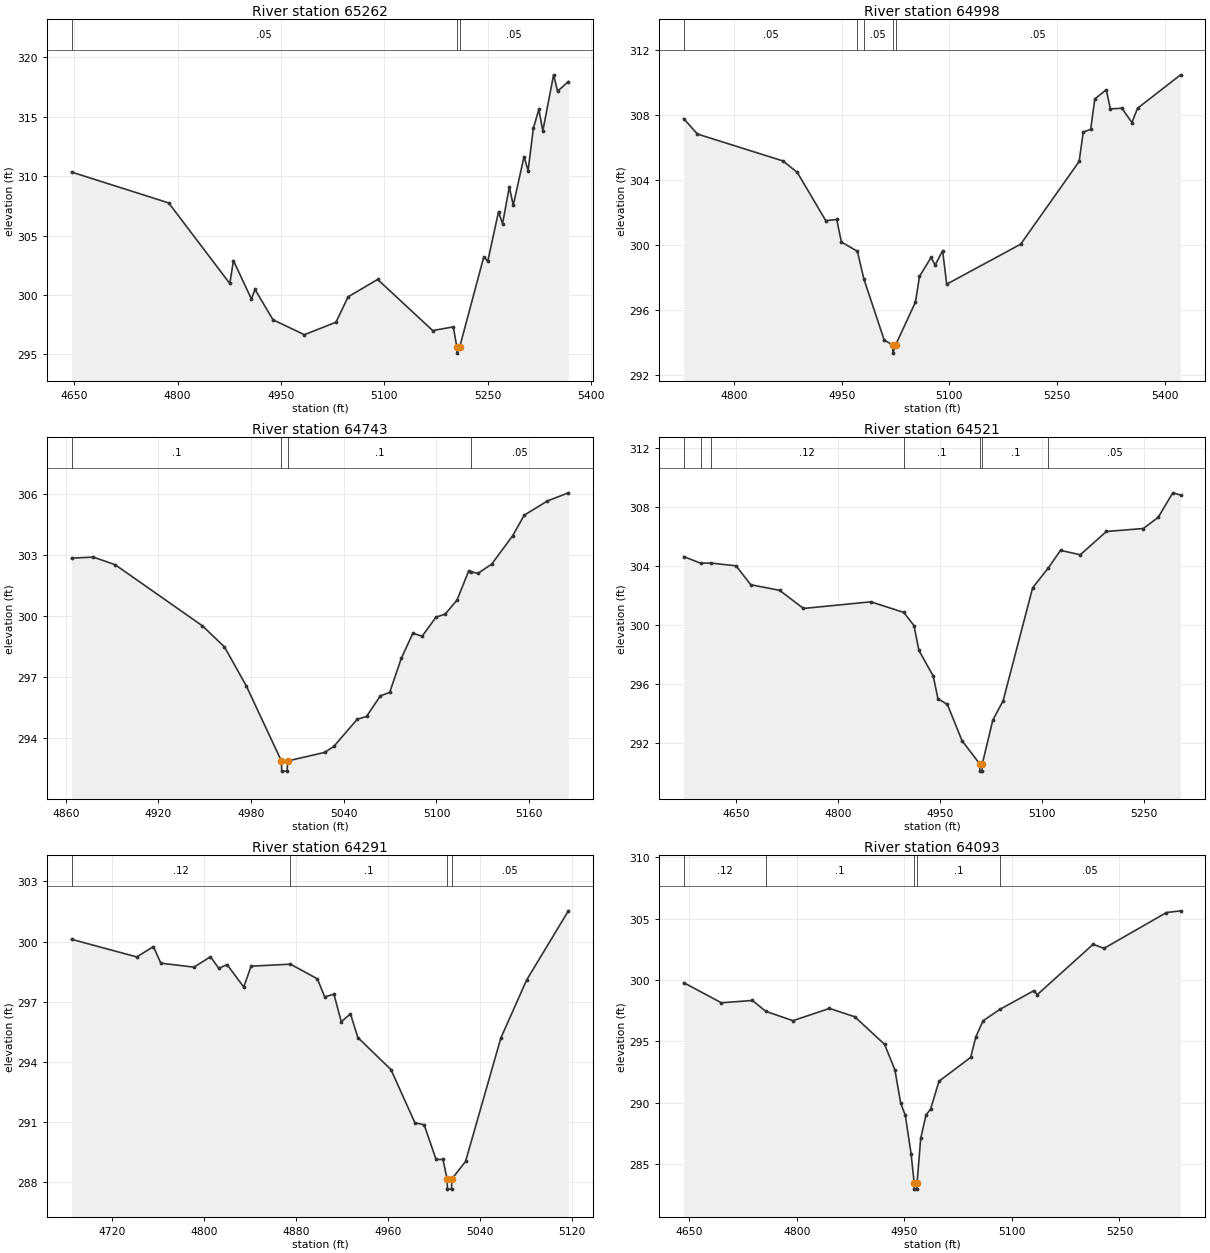
Type RM Length L Ch R = 1 ,65262   ,264,264,264
BEGIN DESCRIPTION:
CUERO CREEK 81.0
END DESCRIPTION:
XS GIS Cut Line= 3
      2533775.01     13642324.98      2533651.14     13642688.33
      2533479.24     13642978.79
#Sta/Elev= 30
  4645.9  310.35    4787  307.75  4875.7  300.97    4881   302.9  4907.1  299.66
  4912.3  300.47  4938.4  297.92    4984  296.66  5029.8  297.71  5047.5  299.85
  5090.4  301.31  5170.3  297.01  5200.2  297.32  5205.4  295.61  5205.6  295.11
  5209.4  295.61  5244.4   303.2  5250.3  302.85  5265.9  307.02  5271.7  305.99
  5281.5  309.09  5287.3  307.56  5302.9  311.65  5308.8  310.47  5316.4  314.02
  5324.4  315.62  5330.2  313.81  5345.8  318.53  5351.6  317.15  5367.3  317.96
#Mann= 3 ,-1 , 0
  4645.9     .05       0  5205.4     .05       0  5209.4     .05       0
Bank Sta=5205.4,5209.4
XS Rating Curve= 0 ,0
Exp/Cntr=0.3,0.1

Type RM Length L Ch R = 1 ,64998   ,255,255,255
BEGIN DESCRIPTION:
X18682
END DESCRIPTION:
XS GIS Cut Line= 2
      2533576.48     13642288.29      2533242.09     13642894.37
#Sta/Elev= 30
  4729.8  307.78  4748.9  306.83  4868.1  305.17  4888.1  304.46  4927.7  301.49
    4943  301.56  4949.5  300.17  4971.8   299.6  4980.7  297.91  5009.1  294.13
    5021  293.82  5021.2  293.32    5025  293.82  5052.6  296.46  5058.3  298.05
  5074.4  299.22  5080.1  298.75  5090.5  299.64  5096.2  297.57  5199.3  300.04
  5280.7  305.14  5286.4  306.95  5296.8  307.12  5302.5  308.99  5318.5  309.56
  5324.2  308.38  5340.3  308.42  5354.2  307.54  5362.1  308.42    5422  310.48
#Mann= 5 ,-1 , 0
  4729.8     .05       0  4971.8      .1       0  4980.7     .05       0
    5021     .05       0    5025     .05       0
Bank Sta=5021,5025
XS Rating Curve= 0 ,0
Exp/Cntr=0.3,0.1

Type RM Length L Ch R = 1 ,64743   ,222,222,222
BEGIN DESCRIPTION:
CUERO CREEK 80.0
END DESCRIPTION:
XS GIS Cut Line= 3
      2533324.97     13642325.03        2533225.       13642425.
      2533124.98     13642575.03
#Sta/Elev= 30
  4863.7  302.84  4877.8  302.89  4891.9  302.52  4948.5  299.51  4962.7  298.48
  4976.8  296.57  4999.6  292.87  4999.8  292.37  5003.3  292.37  5003.6  292.87
  5027.6  293.29  5033.6  293.59  5048.7  294.92  5054.7  295.06  5063.7  296.07
  5069.7  296.24  5077.2  297.91  5084.7  299.15  5090.7     299  5099.7  299.94
  5105.7  300.09  5113.3  300.78  5120.8   302.2  5122.4  302.17  5126.8  302.09
  5135.8  302.55  5149.3  303.94  5156.8  304.95  5171.8  305.65  5185.4  306.05
#Mann= 4 ,-1 , 0
  4863.7      .1       0  4999.6     .05       0  5003.6      .1       0
  5122.4     .05       0
Bank Sta=4999.6,5003.6
XS Rating Curve= 0 ,0
Exp/Cntr=0.3,0.1

Type RM Length L Ch R = 1 ,64521   ,230,230,230
BEGIN DESCRIPTION:
X18683
END DESCRIPTION:
XS GIS Cut Line= 3
      2533307.78     13642058.36      2533024.15     13642368.86
      2532901.74     13642655.47
#Sta/Elev= 30
  4572.3  304.66  4597.1  304.21  4612.1  304.22  4649.5  304.03  4671.1  302.75
  4713.6  302.37  4748.8  301.14  4848.1  301.59  4896.7  300.87  4911.6  299.98
    4919  298.29    4940  296.56    4947  295.02  4960.9  294.63  4982.5  292.17
  5008.4  290.61  5008.6  290.11  5012.1  290.11  5012.4  290.61  5027.8  293.57
    5043  294.88  5086.5  302.54  5109.8   303.9  5127.6  305.08  5156.7  304.78
  5195.2  306.36  5249.6  306.56  5271.4  307.31  5293.1  308.98  5304.5  308.83
#Mann= 7 ,-1 , 0
  4572.3     .12       0  4597.1     .05       0  4612.1     .12       0
  4896.7      .1       0  5008.4     .05       0  5012.4      .1       0
  5109.8     .05       0
Bank Sta=5008.4,5012.4
XS Rating Curve= 0 ,0
Exp/Cntr=0.3,0.1

Type RM Length L Ch R = 1 ,64291   ,198,198,198
BEGIN DESCRIPTION:
CUERO CREEK 79.0
END DESCRIPTION:
XS GIS Cut Line= 3
      2533074.99     13642075.01        2532825.       13642275.
      2532775.02     13642374.96
#Sta/Elev= 30
    4685  300.11  4741.8  299.23  4756.2  299.75  4762.6  298.92  4791.4  298.72
  4805.8  299.24    4813  298.66  4820.2  298.85  4834.7  297.73  4841.1  298.77
  4875.3  298.87  4898.7  298.14  4905.1  297.24  4913.1  297.37  4919.5     296
  4927.5  296.39  4933.9  295.21  4962.7  293.61  4983.5  290.96  4991.5  290.86
  5001.9  289.13  5007.9  289.13  5011.5  288.15  5011.8  287.65  5015.3  287.65
  5015.5  288.15  5027.5  289.03  5058.2  295.19  5080.6  298.08  5116.9  301.53
#Mann= 4 ,-1 , 0
    4685     .12       0  4875.3      .1       0  5011.5     .05       0
  5015.5     .05       0
Bank Sta=5011.5,5015.5
XS Rating Curve= 0 ,0
Exp/Cntr=0.3,0.1

Type RM Length L Ch R = 1 ,64093   ,249,249,249
BEGIN DESCRIPTION:
X18684
END DESCRIPTION:
XS GIS Cut Line= 3
      2532889.79     13641885.19      2532668.85     13642165.84
       2532597.2     13642494.24
#Sta/Elev= 30
    4642  299.79  4694.6  298.15  4737.9  298.34  4756.6  297.45  4794.5  296.69
  4845.4  297.69  4880.7  297.01  4922.3  294.76  4936.7  292.68  4944.8  289.95
  4951.2  288.98  4959.3  285.83  4963.6  283.45  4963.9  282.95  4967.4  282.95
  4967.6  283.45  4972.7  287.08  4980.1     289  4986.5  289.48  4998.2  291.75
  5042.5   293.7  5049.5  295.35  5059.7  296.68  5083.4  297.62  5130.4  299.13
  5135.5  298.82  5213.3  302.92  5228.5  302.59  5315.6  305.51  5335.3  305.65
#Mann= 5 ,-1 , 0
    4642     .12       0  4756.6      .1       0  4963.6     .05       0
  4967.6      .1       0  5083.4     .05       0
Bank Sta=4963.6,4967.6
XS Rating Curve= 0 ,0
Exp/Cntr=0.3,0.1

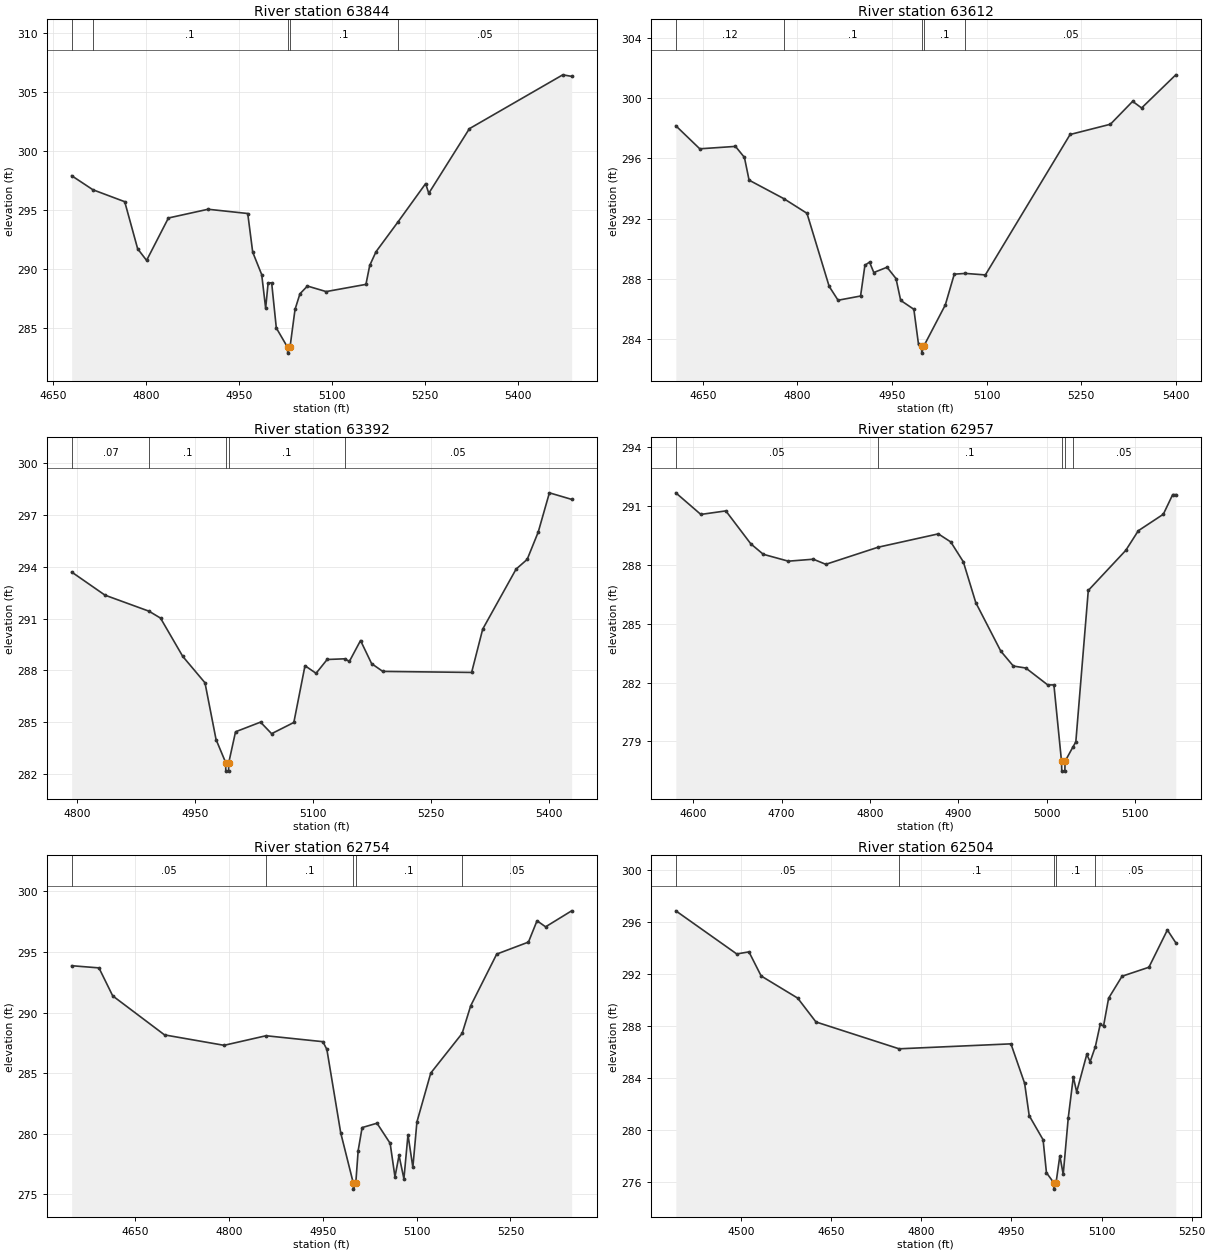
Type RM Length L Ch R = 1 ,63844   ,232,232,232
BEGIN DESCRIPTION:
CUERO CREEK 78.0
END DESCRIPTION:
XS GIS Cut Line= 3
        2532725.       13641825.        2532475.       13642025.
      2532522.56     13642509.21
#Sta/Elev= 30
  4680.4  297.91  4714.7  296.72    4766  295.71  4786.9  291.72  4801.3  290.74
  4836.5  294.33  4900.5  295.07  4964.5  294.71  4972.5  291.44    4987  289.54
  4993.4  286.69  4997.4  288.84  5003.1  288.84  5010.6  285.02  5028.7  283.39
    5029  282.89  5032.7  283.39  5040.8  286.59  5048.7  287.91  5060.8  288.57
    5091   288.1  5155.2  288.71  5161.3  290.31  5171.4  291.47  5207.1  294.01
  5251.5  297.24  5256.6  296.42  5322.1  301.89  5472.8  306.45  5487.1  306.32
#Mann= 5 ,-1 , 0
  4680.4     .12       0  4714.7      .1       0  5028.7     .05       0
  5032.7      .1       0  5207.1     .05       0
Bank Sta=5028.7,5032.7
XS Rating Curve= 0 ,0
Exp/Cntr=0.3,0.1

Type RM Length L Ch R = 1 ,63612   ,220,220,220
BEGIN DESCRIPTION:
X18685
END DESCRIPTION:
XS GIS Cut Line= 2
      2532600.16     13641646.35      2532019.02     13642185.77
#Sta/Elev= 30
  4607.2  298.17  4645.2  296.64  4701.8   296.8    4716  296.07  4723.4  294.56
  4778.6  293.33  4815.2  292.36  4850.4  287.51  4864.5  286.59  4900.2  286.87
  4907.1  288.91  4914.4  289.12  4921.2  288.43  4942.2  288.78  4956.4  288.03
  4963.8  286.58  4984.7  285.99  4992.1  283.66  4996.9  283.58  4997.2  283.08
  5000.9  283.58  5034.6  286.28  5048.8  288.32  5066.5  288.37  5098.1  288.27
  5232.5  297.59  5296.4  298.27  5331.7  299.79  5345.9  299.35  5400.1  301.55
#Mann= 5 ,-1 , 0
  4607.2     .12       0  4778.6      .1       0  4996.9     .05       0
  5000.9      .1       0  5066.5     .05       0
Bank Sta=4996.9,5000.9
XS Rating Curve= 0 ,0
Exp/Cntr=0.3,0.1

Type RM Length L Ch R = 1 ,63392   ,435,435,435
BEGIN DESCRIPTION:
CUERO CREEK 77.0
END DESCRIPTION:
XS GIS Cut Line= 3
      2532374.99     13641575.01        2532225.       13641725.
      2531924.98     13642025.02
#Sta/Elev= 30
    4793   293.7  4835.4  292.36  4891.4  291.43  4906.1  291.03  4934.4  288.81
  4962.7  287.28  4976.8  283.99    4989  282.66  4989.2  282.16  4992.7  282.16
    4993  282.66  5001.6  284.44  5033.4     285  5047.5  284.33  5075.8  284.98
    5090  288.27  5104.1  287.83  5118.2  288.63  5140.4  288.67  5146.5  288.52
  5160.7  289.73  5174.8  288.39    5189  287.94  5302.1  287.88  5316.2  290.39
  5358.7  293.87  5372.8  294.43  5386.9  296.02  5401.1  298.29  5429.4  297.91
#Mann= 5 ,-1 , 0
    4793     .07       0  4891.4      .1       0    4989     .05       0
    4993      .1       0  5140.4     .05       0
Bank Sta=4989,4993
XS Rating Curve= 0 ,0
Exp/Cntr=0.3,0.1

Type RM Length L Ch R = 1 ,62957   ,203,203,203
BEGIN DESCRIPTION:
CUERO CREEK 76.0
END DESCRIPTION:
XS GIS Cut Line= 3
      2532225.02     13641374.98        2531925.       13641675.
      2531825.01     13641774.99
#Sta/Elev= 30
  4580.3  291.66  4608.6  290.56  4636.9  290.74  4665.2  289.06  4679.3  288.53
  4707.6  288.18  4735.9  288.28    4750  288.02  4809.1  288.89  4877.3  289.57
  4891.4  289.16  4905.6  288.15  4919.7  286.07    4948   283.6  4962.2  282.84
  4976.3  282.74  5001.1  281.88  5008.1  281.88  5016.7  277.99    5017  277.49
  5020.5  277.49  5020.7  277.99  5029.4   278.7  5032.9  278.98    5047  286.69
  5089.4  288.73  5103.6  289.73  5131.9  290.57  5142.5  291.57    5146  291.57
#Mann= 5 ,-1 , 0
  4580.3     .05       0  4809.1      .1       0  5016.7     .05       0
  5020.7      .1       0  5029.4     .05       0
Bank Sta=5016.7,5020.7
XS Rating Curve= 0 ,0
Exp/Cntr=0.3,0.1

Type RM Length L Ch R = 1 ,62754   ,250,250,250
BEGIN DESCRIPTION:
X18686
END DESCRIPTION:
XS GIS Cut Line= 3
      2532250.87     13641291.03      2531838.84       13641506.
      2531582.62     13641720.51
#Sta/Elev= 30
  4548.8  293.87  4592.4  293.69  4614.4  291.38  4697.2  288.16  4792.3   287.3
  4859.4  288.09  4950.2   287.6  4956.6  286.96  4978.7  280.08  4998.8  275.93
    4999  275.43  5002.8  275.93  5006.6  278.61  5012.9  280.51  5036.7  280.87
  5057.7  279.21  5065.4  276.44  5071.9  278.21  5079.7  276.28  5086.2  279.92
    5094  277.23  5100.5  280.98  5122.6  285.01  5172.7  288.28  5186.4  290.56
    5228  294.83  5278.7  295.82  5292.4  297.58  5306.1  297.08  5347.7   298.4
#Mann= 5 ,-1 , 0
  4548.8     .05       0  4859.4      .1       0  4998.8     .05       0
  5002.8      .1       0  5172.7     .05       0
Bank Sta=4998.8,5002.8
XS Rating Curve= 0 ,0
Exp/Cntr=0.3,0.1

Type RM Length L Ch R = 1 ,62504   ,472,472,472
BEGIN DESCRIPTION:
CUERO CREEK 75.0
END DESCRIPTION:
XS GIS Cut Line= 3
      2532325.02       13641225.        2531725.       13641325.
        2531525.       13641425.
#Sta/Elev= 30
  4391.6  296.83    4493  293.52  4513.3  293.68  4533.6  291.83  4594.4  290.13
  4624.8   288.3  4763.1  286.24  4949.2  286.62    4972  283.59  4979.6  281.11
  5002.7  279.26  5008.3  276.73  5020.3  275.97  5020.5  275.47  5024.3  275.97
  5030.6  278.03  5036.2   276.6  5044.6  280.95    5053  284.07  5058.6  282.93
  5075.4  285.81    5081  285.25  5089.7  286.41  5097.7  288.11  5103.3  287.99
  5111.7  290.12  5134.1  291.81  5178.8   292.5  5209.5  295.36  5223.5  294.38
#Mann= 5 ,-1 , 0
  4391.6     .05       0  4763.1      .1       0  5020.3     .05       0
  5024.3      .1       0  5089.7     .05       0
Bank Sta=5020.3,5024.3
XS Rating Curve= 0 ,0
Exp/Cntr=0.3,0.1

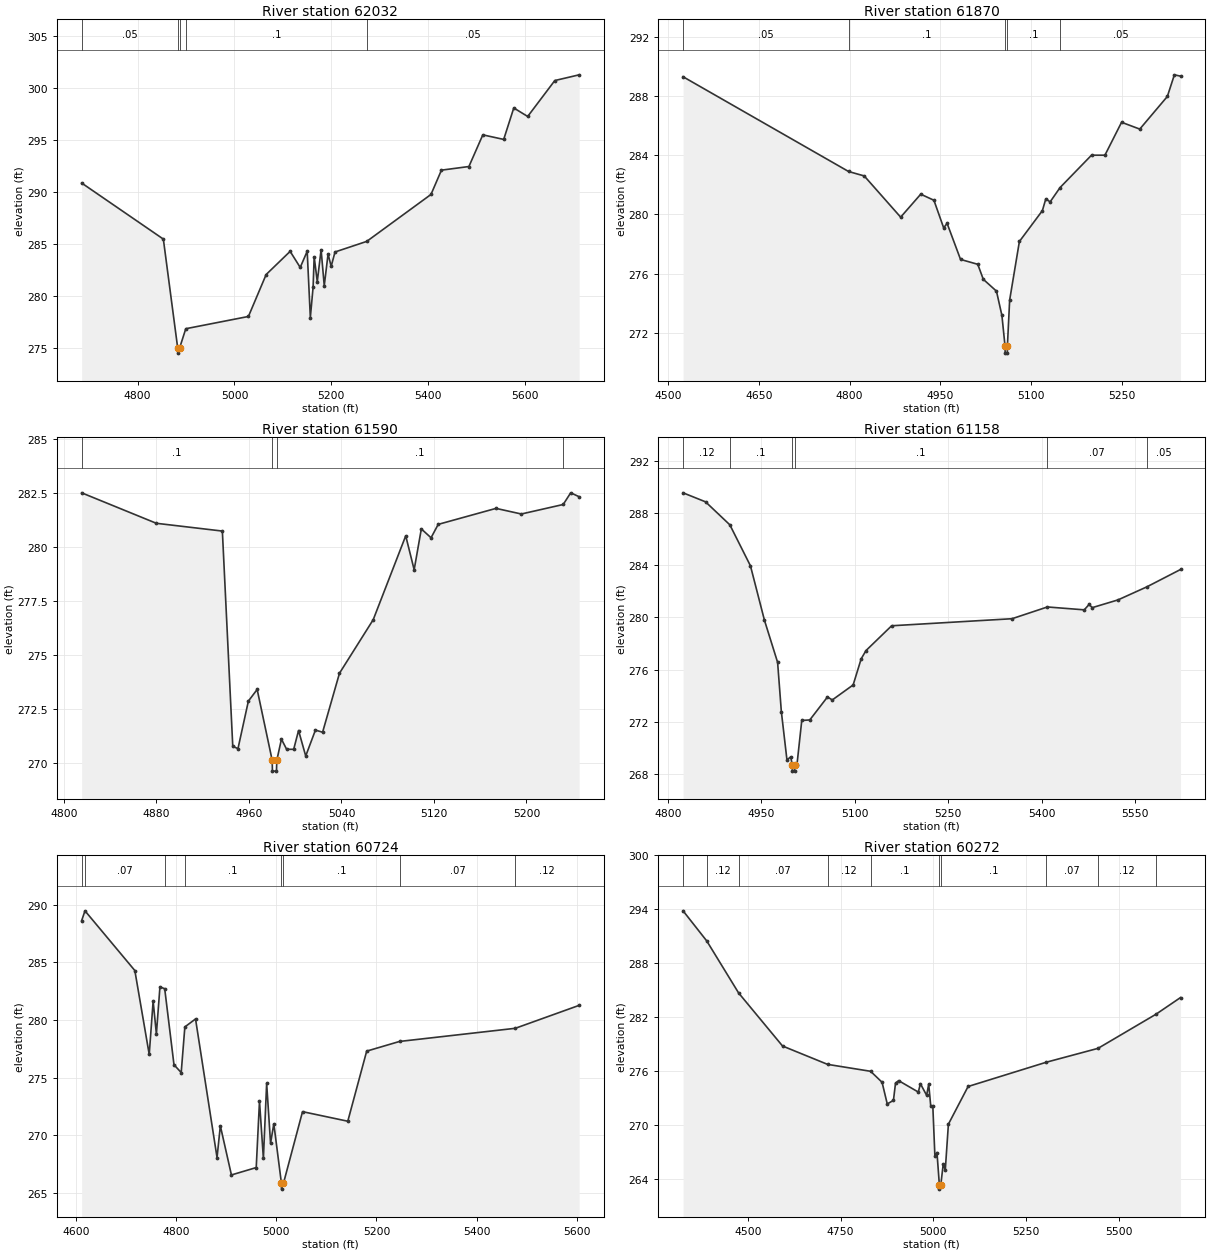
Type RM Length L Ch R = 1 ,62032   ,162,162,162
BEGIN DESCRIPTION:
CUERO CREEK 74.0
END DESCRIPTION:
XS GIS Cut Line= 3
      2532124.97     13641024.99        2531825.       13640925.
      2531275.02     13641374.98
#Sta/Elev= 30
  4684.6  290.85  4853.2  285.45  4882.8  274.97  4883.1  274.47  4886.8  274.97
  4899.5  276.82  5028.8     278  5065.4  282.04  5114.9  284.27  5135.7  282.72
  5150.1  284.28  5156.6   277.9  5162.3  280.83  5164.5  283.75  5170.9  281.35
  5178.8  284.43  5185.3  280.96  5193.2  284.02  5199.6  282.82  5207.5  284.21
    5273  285.23  5405.6  289.75  5427.2  292.09  5483.9  292.44  5512.6  295.49
  5555.7  295.05  5576.5  298.08  5605.2  297.26  5661.2  300.72  5711.4  301.27
#Mann= 5 ,-1 , 0
  4684.6     .05       0  4882.8     .05       0  4886.8     .05       0
  4899.5      .1       0    5273     .05       0
Bank Sta=4882.8,4886.8
XS Rating Curve= 0 ,0
Exp/Cntr=0.3,0.1

Type RM Length L Ch R = 1 ,61870   ,280,280,280
BEGIN DESCRIPTION:
X18687
END DESCRIPTION:
XS GIS Cut Line= 3
      2532173.18     13640804.36      2531788.08     13640768.54
      2531405.87     13640977.56
#Sta/Elev= 30
  4524.7  289.29  4798.3   282.9  4824.2   282.6  4884.4  279.82  4917.6  281.37
  4939.4  280.96  4955.5   279.1  4961.2   279.4  4983.4  276.97  5011.9  276.64
    5021  275.63  5042.8  274.83  5051.8  273.19  5056.9  271.15  5057.2  270.65
  5060.7  270.65  5060.9  271.15  5064.6  274.23  5080.7  278.18  5118.7  280.26
  5124.4  281.06  5131.5  280.85    5148  281.82  5199.9     284  5222.1     284
  5249.6  286.22  5279.7  285.76  5325.3  287.96  5336.9  289.42  5347.1  289.33
#Mann= 5 ,-1 , 0
  4524.7     .05       0  4798.3      .1       0  5056.9     .05       0
  5060.9      .1       0    5148     .05       0
Bank Sta=5056.9,5060.9
XS Rating Curve= 0 ,0
Exp/Cntr=0.3,0.1

Type RM Length L Ch R = 1 ,61590   ,432,432,432
BEGIN DESCRIPTION:
CUERO CREEK 73.0
END DESCRIPTION:
XS GIS Cut Line= 3
      2531775.01     13640424.98        2531675.       13640575.
        2531525.       13640775.
#Sta/Elev= 30
  4815.3  282.49  4879.9  281.08    4937  280.72    4946  270.76  4950.5  270.65
  4959.5  272.85  4967.1  273.39  4980.1  270.11  4980.3  269.61  4983.8  269.61
  4984.1  270.11  4988.1  271.09  4992.6  270.62  4998.7  270.62  5002.9  271.49
  5009.1  270.31  5017.5  271.51  5023.7  271.41  5038.3  274.14  5067.5  276.62
  5095.6   280.5  5102.9  278.93  5109.1  280.82  5117.5  280.41  5123.7  281.03
  5173.7  281.77  5195.6  281.51  5231.8  281.95  5238.3  282.49  5245.6  282.31
#Mann= 4 ,-1 , 0
  4815.3      .1       0  4980.1     .05       0  4984.1      .1       0
  5231.8     .07       0
Bank Sta=4980.1,4984.1
XS Rating Curve= 0 ,0
Exp/Cntr=0.3,0.1

Type RM Length L Ch R = 1 ,61158   ,434,434,434
BEGIN DESCRIPTION:
CUERO CREEK 72.0
END DESCRIPTION:
XS GIS Cut Line= 3
      2531675.04     13640124.98        2531525.       13640225.
        2531375.     13640825.01
#Sta/Elev= 30
  4824.4  289.54  4860.5  288.85  4899.5  287.09  4932.6  283.95  4955.1  279.78
  4976.2  276.56  4982.2  272.79  4991.2  269.09  4997.2  269.32  4999.7  268.73
    5000  268.23  5003.5  268.23  5003.7  268.73  5007.3  268.73    5015  272.11
  5027.9  272.15  5056.3  273.91    5064  273.68  5097.5  274.83  5110.4  276.83
  5118.1  277.46  5159.3  279.36  5352.6   279.9  5409.4   280.8  5468.6  280.58
  5476.3  280.99  5481.5  280.75  5522.7  281.34  5569.1  282.34  5623.2  283.67
#Mann= 6 ,-1 , 0
  4824.4     .12       0  4899.5      .1       0  4999.7     .05       0
  5003.7      .1       0  5409.4     .07       0  5569.1     .05       0
Bank Sta=4999.7,5003.7
XS Rating Curve= 0 ,0
Exp/Cntr=0.3,0.1

Type RM Length L Ch R = 1 ,60724   ,452,452,452
BEGIN DESCRIPTION:
CUERO CREEK 71.0
END DESCRIPTION:
XS GIS Cut Line= 3
      2531475.03     13639824.97        2531225.       13640125.
        2531275.     13640724.96
#Sta/Elev= 30
  4611.8  288.63  4618.4  289.48  4717.9   284.3  4746.6  277.02  4754.4  281.65
  4760.9   278.8    4768  282.89  4777.5  282.72    4796  276.13  4810.4  275.45
  4817.7  279.41    4839   280.1  4881.9  268.08  4888.5  270.83  4910.6  266.57
  4960.1  267.21  4966.6  272.97  4974.4     268  4980.9  274.51  4988.7  269.32
  4995.2  271.01  5010.4  265.84  5010.6  265.34  5014.4  265.84  5052.5  272.06
  5142.8  271.23  5180.5  277.31  5246.1  278.15    5477  279.29  5604.4  281.28
#Mann= 8 ,-1 , 0
  4611.8     .12       0  4618.4     .07       0  4777.5     .12       0
  4817.7      .1       0  5010.4     .05       0  5014.4      .1       0
  5246.1     .07       0    5477     .12       0
Bank Sta=5010.4,5014.4
XS Rating Curve= 0 ,0
Exp/Cntr=0.3,0.1

Type RM Length L Ch R = 1 ,60272   ,459,459,459
BEGIN DESCRIPTION:
CUERO CREEK 70.0
END DESCRIPTION:
XS GIS Cut Line= 3
      2531175.01     13639624.98        2530875.       13640225.
      2531175.02     13640825.04
#Sta/Elev= 30
  4325.3  293.83  4389.2  290.48  4475.1   284.7  4593.6   278.8    4715  276.76
  4831.1  275.99    4862  274.77    4876  272.36  4892.7  272.76  4898.3  274.68
  4906.7  274.95  4959.8  273.68  4965.4  274.61  4982.2  273.32  4987.8  274.56
  4993.3  272.12  4998.9  272.12  5004.5  266.55  5010.1  266.96  5016.5  263.39
  5016.8  262.89  5020.5  263.39  5026.9  265.66  5032.5  265.01  5040.9  270.11
    5094   274.3  5305.1     277  5444.4  278.54  5600.6  282.33    5667  284.19
#Mann= 10 ,-1 , 0
  4325.3    .035       0  4389.2     .12       0  4475.1     .07       0
    4715     .12       0  4831.1      .1       0  5016.5     .05       0
  5020.5      .1       0  5305.1     .07       0  5444.4     .12       0
  5600.6     .05       0
Bank Sta=5016.5,5020.5
XS Rating Curve= 0 ,0
Exp/Cntr=0.3,0.1

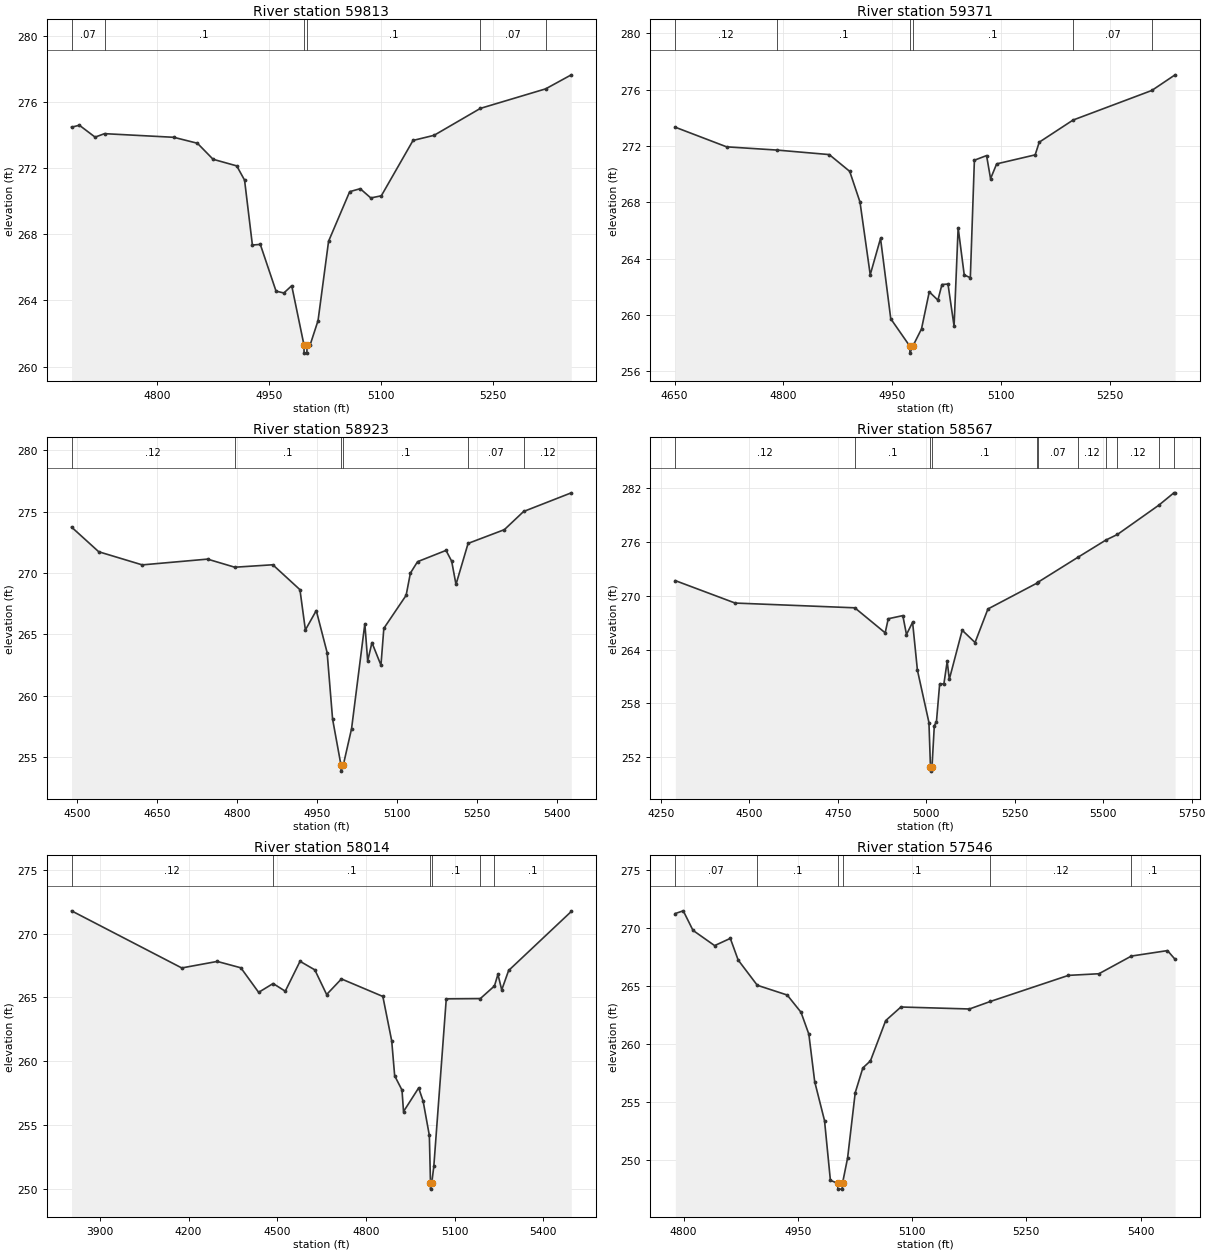
Type RM Length L Ch R = 1 ,59813   ,442,442,442
BEGIN DESCRIPTION:
CUERO CREEK 69.0
END DESCRIPTION:
XS GIS Cut Line= 3
        2530725.       13639825.        2530625.       13640125.
      2530374.99     13640375.01
#Sta/Elev= 30
  4685.2  274.48  4695.7   274.6  4716.8  273.88  4729.4  274.09  4822.2  273.87
  4853.9  273.51  4874.9  272.54  4906.6  272.14  4917.1  271.28  4927.6  267.35
  4938.2  267.39  4959.3  264.56  4969.8  264.45  4980.3  264.89  4996.7  261.31
  4996.9  260.81  5000.6  260.81  5000.9  261.31    5005  261.31  5015.6  262.78
  5029.7  267.58    5058  270.58  5072.1  270.76  5086.3   270.2  5100.4  270.33
  5142.9  273.68  5171.1  273.99  5233.2  275.62  5320.6   276.8    5355  277.65
#Mann= 6 ,-1 , 0
  4685.2     .07       0  4729.4      .1       0  4996.7     .05       0
  5000.9      .1       0  5233.2     .07       0  5320.6     .12       0
Bank Sta=4996.7,5000.9
XS Rating Curve= 0 ,0
Exp/Cntr=0.3,0.1

Type RM Length L Ch R = 1 ,59371   ,448,448,448
BEGIN DESCRIPTION:
CUERO CREEK 68.0
END DESCRIPTION:
XS GIS Cut Line= 3
      2530575.02     13639724.98        2530325.       13639975.
        2530175.       13640275.
#Sta/Elev= 30
    4651  273.33  4721.7  271.94  4791.2  271.71  4863.2  271.39  4891.4   270.2
  4905.6  268.02  4919.7  262.86  4933.9  265.44    4948  259.74  4974.2   257.8
  4974.4   257.3  4978.5   257.8  4990.4  259.02  5001.1  261.65    5013  261.06
  5018.6  262.17  5026.9   262.2  5035.3  259.21  5040.9   266.2  5049.3  262.85
  5057.7  262.65  5063.3  270.99  5080.1  271.32  5085.6  269.68    5094  270.73
  5147.1  271.37  5152.7  272.27  5199.3  273.84  5307.9  275.94    5340  277.05
#Mann= 6 ,-1 , 0
    4651     .12       0  4791.2      .1       0  4974.2     .05       0
  4978.5      .1       0  5199.3     .07       0  5307.9     .12       0
Bank Sta=4974.2,4978.5
XS Rating Curve= 0 ,0
Exp/Cntr=0.3,0.1

Type RM Length L Ch R = 1 ,58923   ,356,356,356
BEGIN DESCRIPTION:
CUERO CREEK 67.0
END DESCRIPTION:
XS GIS Cut Line= 3
      2530525.03     13639624.99        2530025.       13639725.
      2529875.01     13640124.97
#Sta/Elev= 30
  4489.8  273.75  4540.8  271.74  4622.4  270.67  4744.8  271.14  4795.9  270.48
  4867.2  270.68  4918.1  268.65  4928.3  265.37  4948.7  266.95  4969.1  263.52
  4979.3  258.11    4995  254.37  4995.3  253.87  4999.4  254.37  5014.9  257.33
  5039.8  265.88  5045.1  262.84  5053.1  264.34    5070   262.5  5075.4   265.5
  5117.2  268.19  5125.2     270  5138.6  270.93    5192  271.85  5202.6  270.97
  5210.7  269.08  5233.4  272.42  5301.4  273.54  5337.5  275.02  5426.9  276.54
#Mann= 6 ,-1 , 0
  4489.8     .12       0  4795.9      .1       0    4995     .05       0
  4999.4      .1       0  5233.4     .07       0  5337.5     .12       0
Bank Sta=4995,4999.4
XS Rating Curve= 0 ,0
Exp/Cntr=0.3,0.1

Type RM Length L Ch R = 1 ,58567   ,553,553,553
BEGIN DESCRIPTION:
X18688
END DESCRIPTION:
XS GIS Cut Line= 3
      2530459.01     13639297.87      2529777.63     13639467.13
      2529395.67     13640066.12
#Sta/Elev= 30
  4290.7  271.69  4459.7  269.19  4797.9  268.66  4883.8  265.87  4892.5  267.44
  4933.7  267.79    4944  265.68  4961.3  267.05  4974.9  261.71  5007.5  255.87
  5011.8  250.95  5012.1  250.45  5016.2  250.95  5022.7  255.53  5028.7  255.95
  5037.7  260.13  5049.8  260.19  5059.1  262.69  5065.1  260.69  5101.5  266.16
  5137.8  264.79  5174.2  268.53  5313.2  271.42    5316  271.52    5428  274.28
  5507.4  276.21  5540.3  276.84  5657.5  280.11  5698.9  281.45  5703.2  281.48
#Mann= 11 ,-1 , 0
  4290.7     .12       0  4797.9      .1       0  5011.8     .05       0
  5016.2      .1       0  5313.2     .12       0    5316     .07       0
    5428     .12       0  5507.4     .07       0  5540.3     .12       0
  5657.5     .07       0  5698.9     .12       0
Bank Sta=5011.8,5016.2
XS Rating Curve= 0 ,0
Exp/Cntr=0.3,0.1

Type RM Length L Ch R = 1 ,58014   ,468,468,468
BEGIN DESCRIPTION:
X18689
END DESCRIPTION:
XS GIS Cut Line= 3
      2530467.69     13639267.48      2529352.28     13639241.44
       2529036.5      13639721.6
#Sta/Elev= 30
  3804.2  271.78    4177  267.31    4297  267.82    4377  267.32  4437.1   265.4
    4486  266.09  4527.1  265.49  4577.1  267.83  4627.1  267.16  4667.1  265.23
  4717.1  266.45  4857.2  265.08  4887.2   261.6  4897.2  258.87    4922  257.75
  4927.1  256.07  4978.3  257.92  4993.4  256.89  5014.5   254.2  5018.3   250.5
  5018.6     250  5022.7   250.5  5029.6  251.78  5071.7  264.89  5186.8  264.91
  5234.7   265.9  5246.5  266.81  5259.3  265.59  5282.6  267.11  5494.6  271.73
#Mann= 6 ,-1 , 0
  3804.2     .12       0    4486      .1       0  5018.3     .05       0
  5022.7      .1       0  5186.8     .12       0  5234.7      .1       0
Bank Sta=5018.3,5022.7
XS Rating Curve= 0 ,0
Exp/Cntr=0.3,0.1

Type RM Length L Ch R = 1 ,57546   ,466,466,466
BEGIN DESCRIPTION:
CUERO CREEK 66.0
END DESCRIPTION:
XS GIS Cut Line= 3
      2528924.99     13638924.95        2528975.       13639125.
        2528975.       13639575.
#Sta/Elev= 30
  4789.2  271.22  4799.6  271.45  4812.4  269.77  4840.8  268.46  4861.4  269.08
  4871.7  267.22  4896.8  265.05  4936.1  264.21  4954.2  262.73  4964.5  260.85
  4972.2  256.76  4985.1  253.41  4992.8  248.28  5002.2  248.02  5002.7  247.52
  5008.2  247.52  5008.7  248.02  5015.4   250.2  5025.4  255.81  5035.4  257.94
  5045.4  258.55  5065.4  262.01  5085.4  263.18  5175.4  263.01    5203  263.66
  5305.4   265.9  5345.4  266.04    5388  267.56  5435.4  268.03  5445.4  267.28
#Mann= 6 ,-1 , 0
  4789.2     .07       0  4896.8      .1       0  5002.2     .05       0
  5008.7      .1       0    5203     .12       0    5388      .1       0
Bank Sta=5002.2,5008.7
XS Rating Curve= 0 ,0
Exp/Cntr=0.3,0.1

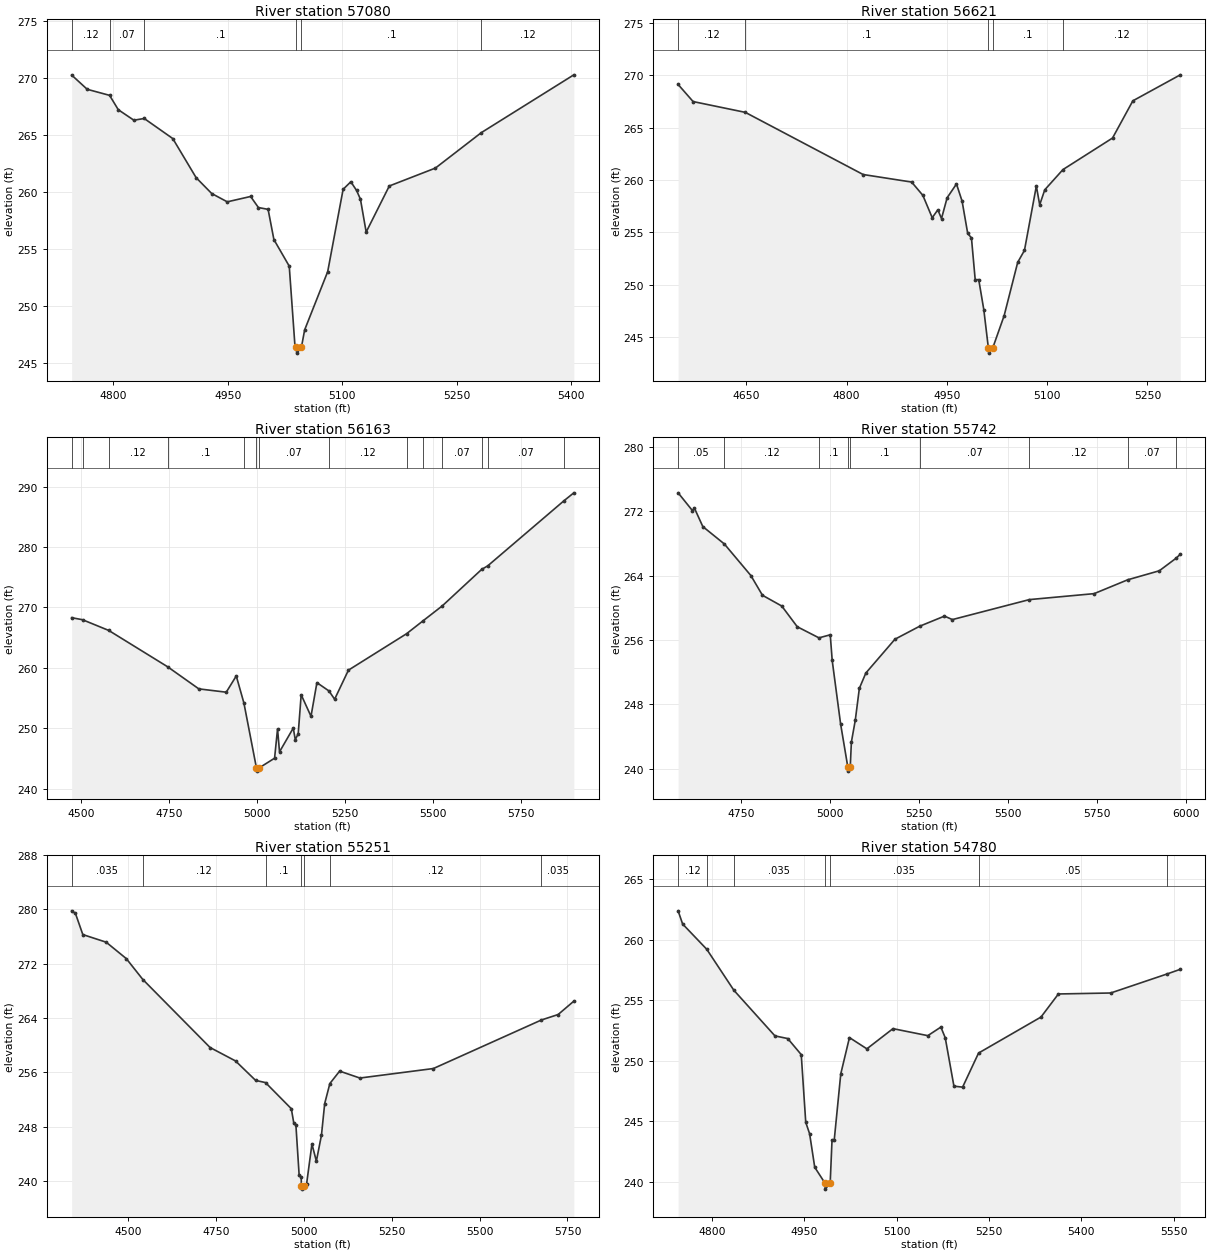
Type RM Length L Ch R = 1 ,57080   ,459,459,459
BEGIN DESCRIPTION:
CUERO CREEK 65.0
END DESCRIPTION:
XS GIS Cut Line= 3
      2528574.99     13638925.04        2528525.       13639175.
        2528475.     13639574.98
#Sta/Elev= 30
  4745.5  270.26  4765.9  269.01  4795.2  268.48  4806.6  267.22    4827   266.3
  4840.6  266.45    4878  264.69  4908.6  261.26    4929  259.87  4949.4  259.14
    4980  259.61  4990.2  258.64  5002.9  258.48  5010.5  255.83  5030.6   253.5
  5038.2  246.41  5039.9  246.37  5040.4  245.87  5046.5  246.37  5050.8  247.91
    5081  253.02  5101.2  260.24  5111.3   260.9  5118.8  260.14  5123.9  259.37
  5131.4  256.49  5161.7  260.53  5222.1   262.1  5282.3  265.21  5403.5  270.28
#Mann= 6 ,-1 , 0
  4745.5     .12       0  4795.2     .07       0  4840.6      .1       0
  5039.9     .05       0  5046.5      .1       0  5282.3     .12       0
Bank Sta=5039.9,5046.5
XS Rating Curve= 0 ,0
Exp/Cntr=0.3,0.1

Type RM Length L Ch R = 1 ,56621   ,458,458,458
BEGIN DESCRIPTION:
CUERO CREEK 64.0
END DESCRIPTION:
XS GIS Cut Line= 3
      2528325.02     13638874.96        2528125.       13639275.
        2528175.     13639575.01
#Sta/Elev= 30
  4547.8  269.12  4570.2  267.49  4648.3  266.46  4824.6  260.53  4897.2  259.81
    4914  258.54    4928  256.41  4936.4  257.16  4941.9  256.33  4950.3  258.31
  4964.3  259.63  4972.7  257.99  4981.1  254.91  4986.7  254.48  4992.3   250.5
  4997.6   250.5  5005.2  247.63    5012  243.99  5012.5  243.49  5018.6  243.99
  5035.6  247.06  5055.9  252.15    5066  253.29  5083.8  259.43  5088.8  257.64
  5096.4  259.07  5123.6     261  5197.8  264.01  5228.2  267.56  5299.2  270.04
#Mann= 5 ,-1 , 0
  4547.8     .12       0  4648.3      .1       0    5012     .05       0
  5018.6      .1       0  5123.6     .12       0
Bank Sta=5012,5018.6
XS Rating Curve= 0 ,0
Exp/Cntr=0.3,0.1

Type RM Length L Ch R = 1 ,56163   ,421,421,421
BEGIN DESCRIPTION:
CUERO CREEK 63.0
END DESCRIPTION:
XS GIS Cut Line= 3
        2528075.       13638825.        2527725.       13639225.
      2528124.98     13640024.97
#Sta/Elev= 30
  4473.5   268.3  4504.5  267.96  4578.8  266.19  4745.9  260.18  4834.6  256.52
  4912.5  255.97  4940.9  258.66  4962.6  254.18  4998.3  243.41  4998.8  242.91
    5005  243.41  5049.7  245.05  5058.1  249.89  5063.7   246.1  5102.8  250.04
  5108.4  248.11  5116.8   249.1  5125.2  255.55  5153.1  251.98  5169.9  257.55
    5204  256.18  5220.2  254.81  5259.4  259.62  5424.3  265.64  5472.1  267.82
    5526  270.26  5637.7  276.29  5654.8  276.87  5871.6  287.66  5899.4  288.96
#Mann= 14 ,-1 , 0
  4473.5      .1       0  4504.5     .07       0  4578.8     .12       0
  4745.9      .1       0  4962.6     .07       0  4998.3     .05       0
    5005     .07       0    5204     .12       0  5424.3     .07       0
  5472.1     .12       0    5526     .07       0  5637.7     .12       0
  5654.8     .07       0  5871.6     .12       0
Bank Sta=4998.3,5005
XS Rating Curve= 0 ,0
Exp/Cntr=0.3,0.1

Type RM Length L Ch R = 1 ,55742   ,491,491,491
BEGIN DESCRIPTION:
X18690
END DESCRIPTION:
XS GIS Cut Line= 3
      2527607.51     13638546.95      2527360.09     13639128.59
      2527680.54     13639838.77
#Sta/Elev= 30
  4572.5  274.27  4612.8  272.06  4618.3  272.37  4641.9  270.08  4702.4  267.92
  4776.9     264  4809.5  261.55  4863.8  260.21  4907.3  257.64  4968.3  256.26
    5000  256.64  5005.5  253.45  5029.1  245.57  5049.4  240.21  5049.9  239.71
  5056.2  240.21  5059.4  243.32  5070.3  246.01  5081.8  249.99    5100  251.89
  5181.8  256.09  5251.1   257.7  5320.9  258.96  5343.3  258.53  5559.4  261.01
  5741.5  261.75  5835.9  263.47  5924.7  264.59  5972.2  266.16  5983.7  266.65
#Mann= 9 ,-1 , 0
  4572.5     .05       0  4702.4     .12       0  4968.3      .1       0
  5049.4     .05       0  5056.2      .1       0  5251.1     .07       0
  5559.4     .12       0  5835.9     .07       0  5972.2     .12       0
Bank Sta=5049.4,5056.2
XS Rating Curve= 0 ,0
Exp/Cntr=0.3,0.1

Type RM Length L Ch R = 1 ,55251   ,471,471,471
BEGIN DESCRIPTION:
CUERO CREEK 62.0
END DESCRIPTION:
XS GIS Cut Line= 3
      2527386.12     13638221.49        2527025.       13638775.
      2526613.56     13639423.73
#Sta/Elev= 30
    4339   279.8  4349.7  279.43  4370.8   276.3  4437.2  275.18  4494.5  272.76
  4541.6  269.68  4732.9  259.66  4805.3  257.68  4862.6  254.81  4890.7  254.49
  4964.1  250.64  4971.2  248.52  4977.2   248.2  4986.4  240.84  4992.3  240.53
  4992.7  239.29  4993.2  238.79  5001.2  239.29  5007.5  239.52  5022.8  245.44
  5035.4  242.91  5049.9  246.75  5059.1   251.4  5073.8  254.35  5101.6  256.18
  5159.2  255.16  5368.4  256.56  5675.6  263.71  5723.4  264.52  5768.1  266.49
#Mann= 7 ,-1 , 0
    4339    .035       0  4541.6     .12       0  4890.7      .1       0
  4992.7     .05       0  5001.2      .1       0  5073.8     .12       0
  5675.6    .035       0
Bank Sta=4992.7,5001.2
XS Rating Curve= 0 ,0
Exp/Cntr=0.3,0.1

Type RM Length L Ch R = 1 ,54780   ,469,469,469
BEGIN DESCRIPTION:
CUERO CREEK 61.0
END DESCRIPTION:
XS GIS Cut Line= 3
      2526925.01     13638324.99        2526725.       13638475.
        2526325.       13638875.
#Sta/Elev= 30
  4744.9   262.4  4752.2  261.31  4791.4  259.22  4835.4  255.83  4902.2  252.05
    4923  251.83  4944.9   250.5  4952.2   244.9  4958.5  243.95  4966.8  241.18
  4983.4  239.87  4983.9  239.37  4991.9  239.87  4994.9  243.44  4998.5  243.44
  5009.1  248.91  5023.2  251.91  5051.5  250.98  5093.9  252.65  5150.5  252.07
  5171.7  252.78  5178.8  251.89  5192.9  247.89    5207  247.81  5232.9  250.63
  5334.3  253.61  5362.6  255.52  5447.5   255.6  5538.8  257.17  5560.6  257.56
#Mann= 7 ,-1 , 0
  4744.9     .12       0  4791.4     .05       0  4835.4    .035       0
  4983.4    .035       0  4991.9    .035       0  5232.9     .05       0
  5538.8    .035       0
Bank Sta=4983.4,4991.9
XS Rating Curve= 0 ,0
Exp/Cntr=0.3,0.1