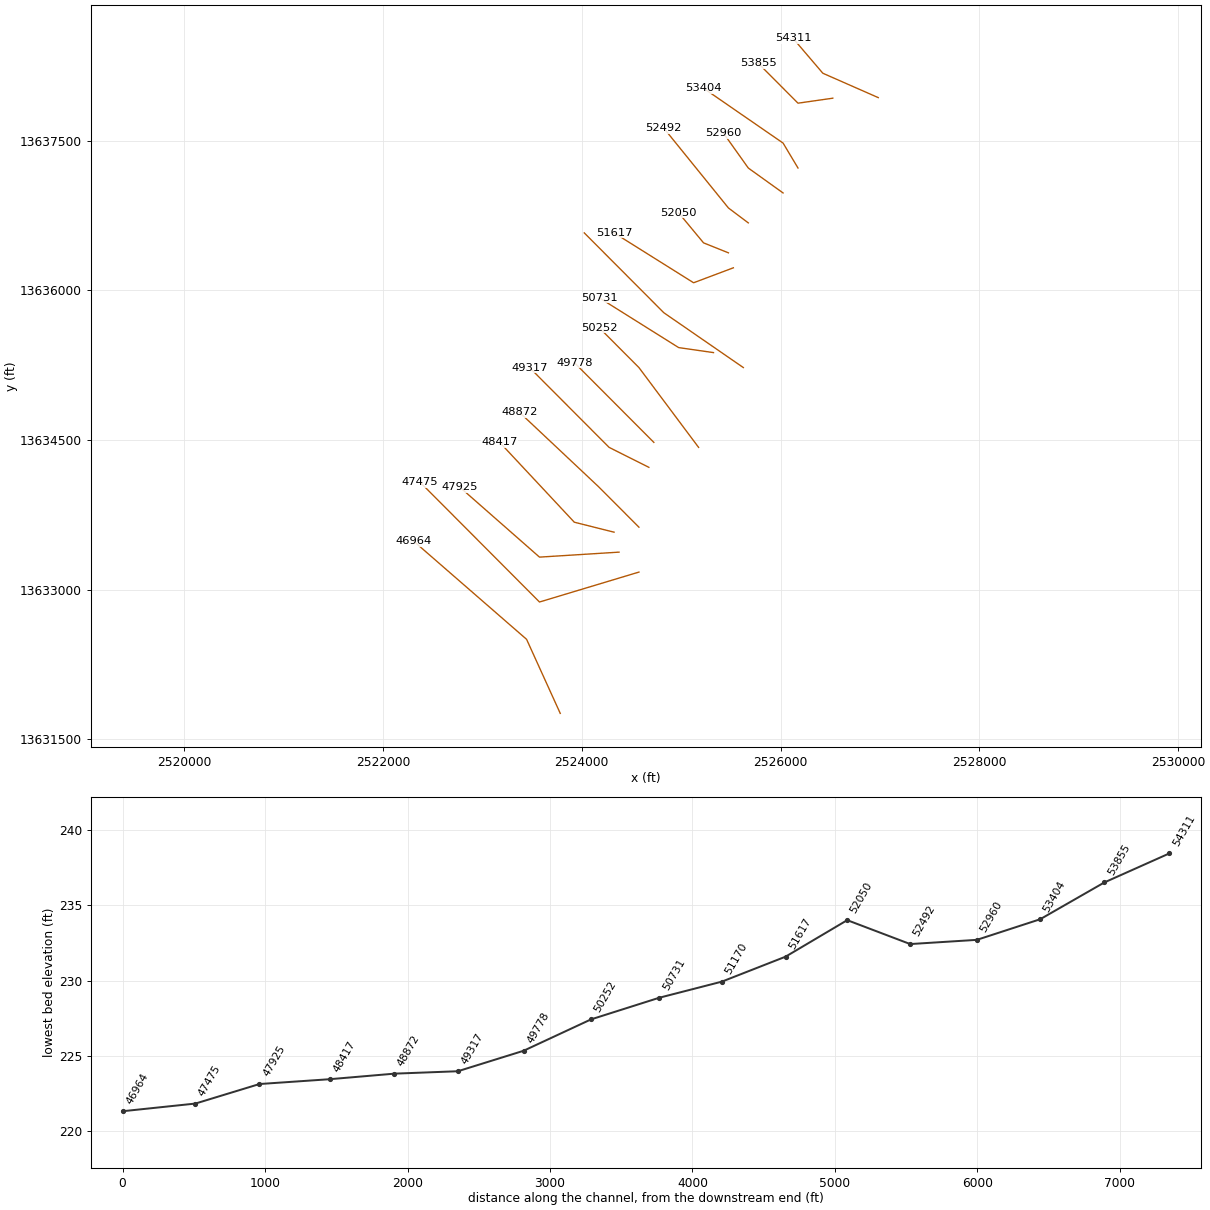
HEC-RAS study CUERO CREEK.prj: CUERO CREEK Base Level Engineering

--- CUERO CREEK.g01 (geometry) --- (continued)

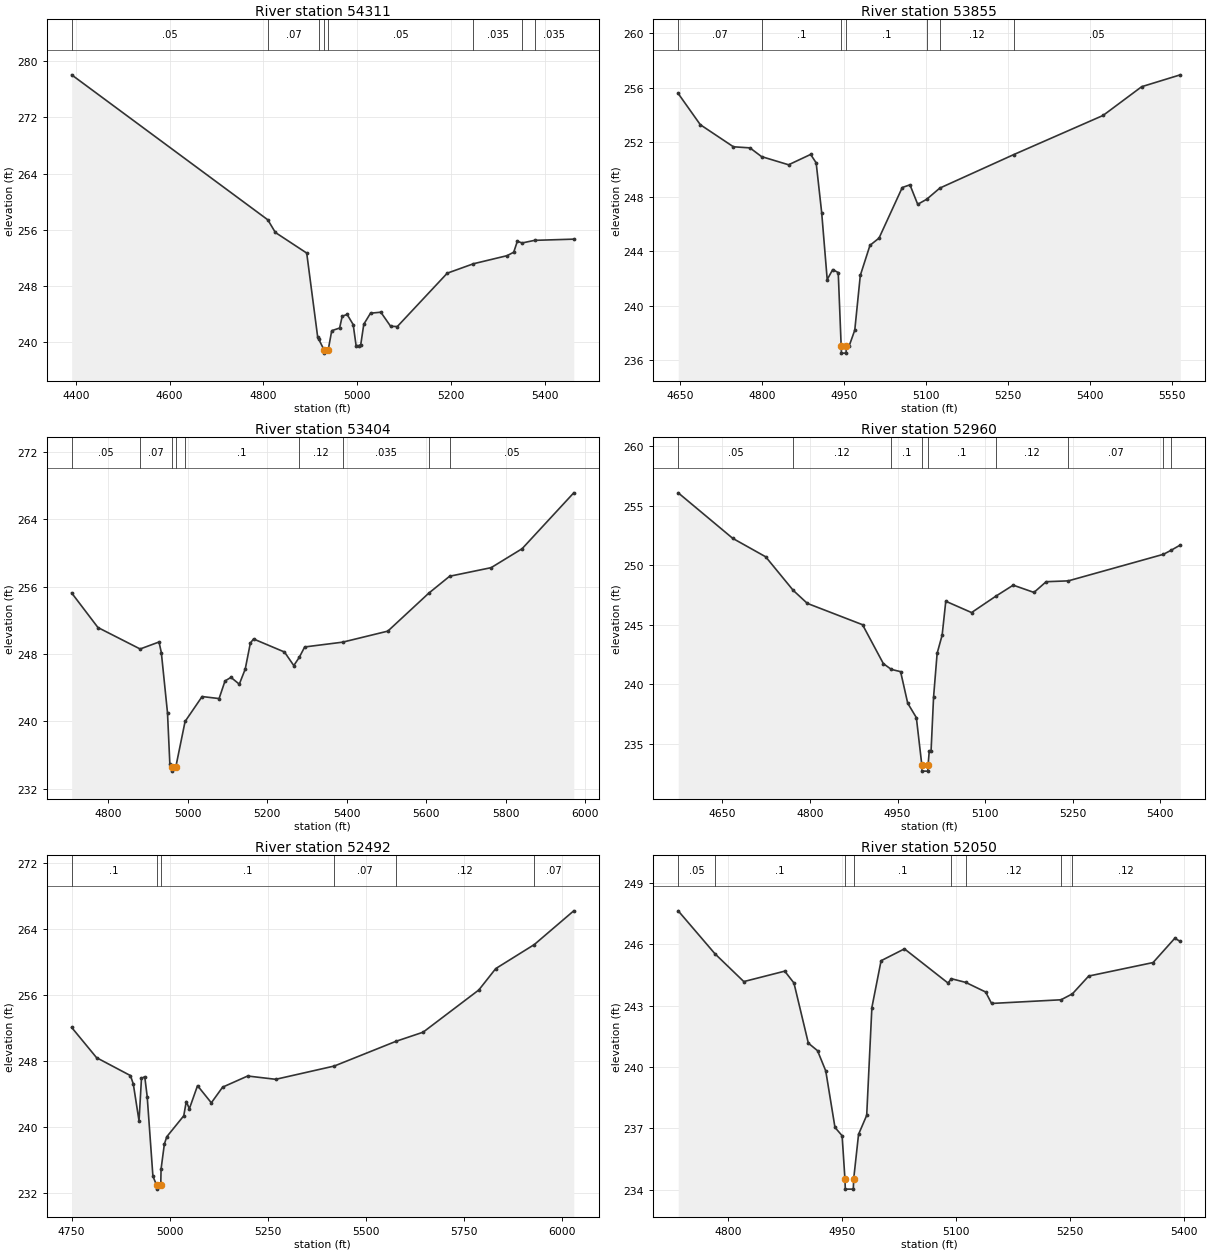
Type RM Length L Ch R = 1 ,54311   ,456,456,456
BEGIN DESCRIPTION:
CUERO CREEK 60.0
END DESCRIPTION:
XS GIS Cut Line= 3
      2526982.53     13637930.65        2526425.       13638175.
        2526125.       13638525.
#Sta/Elev= 30
  4391.3  278.04  4809.2  257.42  4825.3  255.62  4892.1  252.69  4915.5  240.72
    4918   240.4  4928.7  238.96  4929.2  238.46    4938  238.96  4945.4  241.65
  4962.2  242.03  4967.7  243.71  4978.2  243.96  4991.1  242.52  4997.3  239.53
  5003.3  239.53  5007.2  239.66  5013.7  242.57    5028  244.14    5050  244.28
  5070.8  242.28  5085.1  242.24  5191.5  249.83  5247.3  251.17  5318.9  252.32
  5333.1  252.81  5340.8  254.37  5351.1  254.13  5377.6   254.5    5461  254.67
#Mann= 8 ,-1 , 0
  4391.3     .05       0  4809.2     .07       0    4918     .05       0
  4928.7     .05       0    4938     .05       0  5247.3    .035       0
  5351.1     .05       0  5377.6    .035       0
Bank Sta=4928.7,4938
XS Rating Curve= 0 ,0
Exp/Cntr=0.3,0.1

Type RM Length L Ch R = 1 ,53855   ,451,451,451
BEGIN DESCRIPTION:
CUERO CREEK 59.0
END DESCRIPTION:
XS GIS Cut Line= 3
      2526525.05     13637925.01        2526175.       13637875.
      2525774.99     13638275.01
#Sta/Elev= 30
  4646.8  255.58  4687.3  253.29  4747.9  251.67  4778.2  251.59  4799.4  250.95
  4848.9  250.35  4889.3  251.11  4899.4  250.49  4909.5  246.84  4919.6  241.93
  4929.7  242.66  4939.8  242.44  4945.2  237.03  4945.7  236.53  4954.1  236.53
  4954.6  237.03    4960  237.08  4970.1  238.22  4980.2  242.23  4997.9  244.44
  5014.5  244.97    5057  248.68  5071.1  248.88  5085.3  247.45  5101.8  247.82
  5125.8  248.64  5261.3   251.1  5424.7  253.97  5495.4  256.08  5566.1  256.95
#Mann= 7 ,-1 , 0
  4646.8     .07       0  4799.4      .1       0  4945.2     .05       0
  4954.6      .1       0  5101.8    .035       0  5125.8     .12       0
  5261.3     .05       0
Bank Sta=4945.2,4954.6
XS Rating Curve= 0 ,0
Exp/Cntr=0.3,0.1

Type RM Length L Ch R = 1 ,53404   ,444,444,444
BEGIN DESCRIPTION:
CUERO CREEK 58.0
END DESCRIPTION:
XS GIS Cut Line= 3
      2526175.01     13637224.98        2526025.       13637475.
        2525225.       13638025.
#Sta/Elev= 30
  4708.7  255.25  4774.8  251.14  4880.9  248.59  4928.4  249.42  4934.2  248.16
  4949.7     241  4955.6  234.93    4960  234.58  4960.5  234.08  4970.6  234.58
  4993.9  239.98  5036.7  242.94  5079.4   242.7  5094.3  244.79  5109.2  245.22
  5130.2  244.41  5145.1   246.2    5158  249.29    5166  249.78  5243.8  248.23
  5267.2  246.62  5280.9  247.59  5294.6  248.83    5390   249.4  5503.6  250.71
  5606.6  255.22    5659  257.23  5763.4  258.25  5841.2   260.5  5971.1  267.14
#Mann= 9 ,-1 , 0
  4708.7     .05       0  4880.9     .07       0    4960     .05       0
  4970.6     .07       0  4993.9      .1       0  5280.9     .12       0
    5390    .035       0  5606.6     .07       0    5659     .05       0
Bank Sta=4960,4970.6
XS Rating Curve= 0 ,0
Exp/Cntr=0.3,0.1

Type RM Length L Ch R = 1 ,52960   ,468,468,468
BEGIN DESCRIPTION:
CUERO CREEK 57.0
END DESCRIPTION:
XS GIS Cut Line= 3
      2526024.99     13636975.01        2525675.       13637225.
      2525425.01     13637574.98
#Sta/Elev= 30
  4574.2  256.07  4667.6  252.25  4724.1   250.7  4771.3  247.88  4795.4  246.79
    4890     245  4925.7  241.73  4939.3  241.25  4955.2  241.06  4967.4  238.41
  4982.2   237.2  4991.6  233.21  4992.1  232.71  5001.8  232.71  5002.3  233.21
  5004.3   234.4  5007.4   234.4  5011.7  238.93  5017.8   242.6  5026.4  244.13
  5032.6  246.97  5076.8  246.02  5117.9  247.38  5148.1  248.32  5183.7  247.71
  5204.6  248.61  5242.5  248.68  5405.5  250.91  5418.7  251.25  5434.4  251.69
#Mann= 9 ,-1 , 0
  4574.2     .05       0  4771.3     .12       0  4939.3      .1       0
  4991.6     .05       0  5002.3      .1       0  5117.9     .12       0
  5242.5     .07       0  5405.5     .12       0  5418.7     .07       0
Bank Sta=4991.6,5002.3
XS Rating Curve= 0 ,0
Exp/Cntr=0.3,0.1

Type RM Length L Ch R = 1 ,52492   ,442,442,442
BEGIN DESCRIPTION:
CUERO CREEK 56.0
END DESCRIPTION:
XS GIS Cut Line= 3
      2525675.02     13636674.99        2525475.       13636825.
        2524825.       13637625.
#Sta/Elev= 30
    4750  252.03  4813.6  248.36    4900  246.19  4907.3  245.17  4921.9  240.69
  4928.1  245.84  4936.5  246.06  4942.7  243.65  4957.3     234  4966.5  232.93
    4967  232.43  4977.3  232.93  4978.1  234.86  4986.5  237.89  4992.7  238.78
    5036  241.32  5042.4  243.05  5050.3  242.17  5071.1  244.97  5106.3  242.89
  5135.1  244.79    5199  246.14  5270.6  245.74    5420  247.35  5577.6  250.35
  5646.5  251.45  5788.7  256.57  5831.8  259.16  5930.1  262.07  6030.8  266.16
#Mann= 6 ,-1 , 0
    4750      .1       0  4966.5     .05       0  4977.3      .1       0
    5420     .07       0  5577.6     .12       0  5930.1     .07       0
Bank Sta=4966.5,4977.3
XS Rating Curve= 0 ,0
Exp/Cntr=0.3,0.1

Type RM Length L Ch R = 1 ,52050   ,433,433,433
BEGIN DESCRIPTION:
CUERO CREEK 55.0
END DESCRIPTION:
XS GIS Cut Line= 3
      2525475.01       13636375.        2525225.       13636475.
      2524974.99     13636775.01
#Sta/Elev= 30
  4734.8  247.63  4783.1  245.53    4821  244.17  4874.8  244.68  4886.9   244.1
  4905.8  241.16  4917.9  240.79  4928.7   239.8  4940.8  237.04  4950.2  236.63
  4953.9  234.52  4954.4  234.02  4964.9  234.02  4965.4  234.52  4971.8   236.7
  4982.5  237.63  4989.3   242.9  5001.4  245.19  5032.1  245.77  5089.3   244.1
  5093.8  244.31  5112.6  244.13  5138.8  243.66  5146.6   243.1  5237.9  243.28
  5252.8  243.57  5274.2  244.44  5358.8   245.1  5387.4  246.29  5394.6  246.13
#Mann= 8 ,-1 , 0
  4734.8     .05       0  4783.1      .1       0  4953.9     .05       0
  4965.4      .1       0  5093.8     .12       0  5112.6     .12       0
  5237.9      .1       0  5252.8     .12       0
Bank Sta=4953.9,4965.4
XS Rating Curve= 0 ,0
Exp/Cntr=0.3,0.1

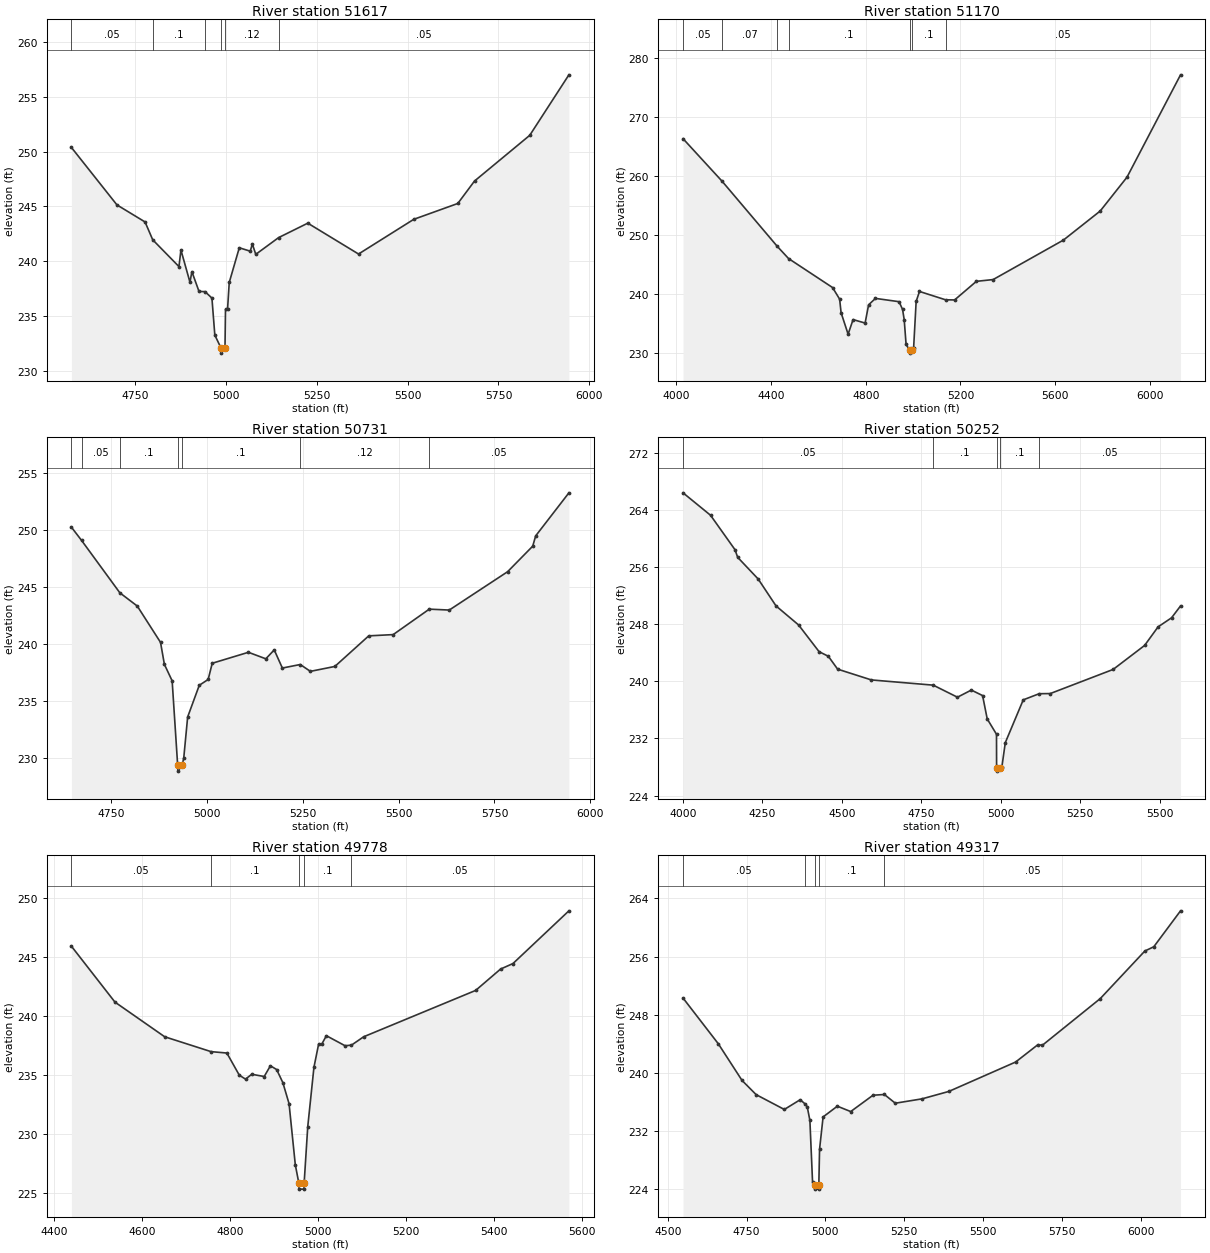
Type RM Length L Ch R = 1 ,51617   ,447,447,447
BEGIN DESCRIPTION:
CUERO CREEK 54.0
END DESCRIPTION:
XS GIS Cut Line= 3
      2525524.96     13636224.98        2525125.       13636075.
      2524324.96     13636575.02
#Sta/Elev= 30
  4573.5  250.39  4698.9  245.14  4776.4  243.58  4797.5  241.95  4869.8   239.5
  4875.2  241.02  4900.1  238.07  4905.4  239.04    4925  237.23  4941.7  237.21
  4960.6  236.62  4968.6  233.24  4985.1  232.09  4985.6  231.59  4996.6  232.09
    4998  235.58  5003.6  235.58  5008.3  238.05    5036  241.22  5066.1  240.91
    5072  241.56  5081.4  240.62  5144.3  242.15  5224.7  243.47  5364.5  240.65
  5516.6  243.82    5638  245.27    5684  247.32  5836.2   251.5  5944.1  257.03
#Mann= 6 ,-1 , 0
  4573.5     .05       0  4797.5      .1       0  4941.7     .12       0
  4985.1     .05       0  4996.6     .12       0  5144.3     .05       0
Bank Sta=4985.1,4996.6
XS Rating Curve= 0 ,0
Exp/Cntr=0.3,0.1

Type RM Length L Ch R = 1 ,51170   ,439,439,439
BEGIN DESCRIPTION:
CUERO CREEK 53.0
END DESCRIPTION:
XS GIS Cut Line= 3
      2525625.03     13635224.98        2524825.       13635775.
      2524025.02     13636574.98
#Sta/Elev= 30
  4027.9  266.37  4193.1  259.13  4426.3  248.06  4473.8     246  4659.8  241.07
  4689.6   239.1  4695.7   236.8  4725.4  233.15  4746.4  235.63  4797.2  235.04
    4812  238.14    4841  239.23  4940.6  238.67  4955.5  237.36  4962.4  235.63
  4970.4   231.4  4985.6  230.43  4986.1  229.93  4997.1  230.43  5002.3  230.88
  5012.9  238.71    5027  240.41  5137.3  238.99  5175.5  238.97  5267.5  242.13
  5338.2  242.43  5635.2  249.14  5790.7  254.08  5903.9  259.83  6130.1  277.22
#Mann= 7 ,-1 , 0
  4027.9     .05       0  4193.1     .07       0  4426.3     .05       0
  4473.8      .1       0  4985.6     .05       0  4997.1      .1       0
  5137.3     .05       0
Bank Sta=4985.6,4997.1
XS Rating Curve= 0 ,0
Exp/Cntr=0.3,0.1

Type RM Length L Ch R = 1 ,50731   ,479,479,479
BEGIN DESCRIPTION:
CUERO CREEK 52.0
END DESCRIPTION:
XS GIS Cut Line= 3
      2525324.98       13635375.        2524975.       13635425.
      2524175.03     13635924.98
#Sta/Elev= 30
  4647.2  250.23  4673.7  249.07  4773.5  244.48  4818.9  243.32  4879.5  240.14
  4889.6  238.21  4909.8  236.77  4924.2  229.36  4924.7  228.86  4935.9  229.36
  4940.1  230.03  4950.2   233.6  4980.5  236.38  5003.7  236.89  5014.3  238.31
  5108.6  239.27    5154   238.7  5175.9  239.48  5197.1  237.89  5243.7   238.2
  5270.2   237.6  5333.9  238.03  5422.3  240.71    5486  240.82  5580.1  243.05
  5632.2  242.97  5784.3  246.33  5849.8  248.57  5857.5  249.47  5944.1  253.24
#Mann= 7 ,-1 , 0
  4647.2     .07       0  4673.7     .05       0  4773.5      .1       0
  4924.2     .05       0  4935.9      .1       0  5243.7     .12       0
  5580.1     .05       0
Bank Sta=4924.2,4935.9
XS Rating Curve= 0 ,0
Exp/Cntr=0.3,0.1

Type RM Length L Ch R = 1 ,50252   ,474,474,474
BEGIN DESCRIPTION:
CUERO CREEK 51.0
END DESCRIPTION:
XS GIS Cut Line= 3
      2525175.01     13634424.98        2524575.       13635225.
      2524175.01     13635624.99
#Sta/Elev= 30
    4000  266.39  4086.5  263.25  4163.6  258.42  4171.9  257.36  4236.5  254.32
  4292.7  250.55  4363.6  247.89  4428.1  244.15  4457.3   243.5  4486.5   241.7
  4592.7  240.19  4787.3  239.46  4863.6  237.77  4907.3  238.77  4942.7     238
  4957.3  234.73  4986.5  232.58  4986.8  227.92  4987.3  227.42  4998.7  227.92
  5003.6  228.06  5014.2  231.41  5070.7   237.4  5120.8  238.26  5155.6  238.28
  5353.6  241.66  5452.6  245.02    5495  247.62  5537.4  248.89  5565.7  250.55
#Mann= 5 ,-1 , 0
    4000     .05       0  4787.3      .1       0  4986.8     .05       0
  4998.7      .1       0  5120.8     .05       0
Bank Sta=4986.8,4998.7
XS Rating Curve= 0 ,0
Exp/Cntr=0.3,0.1

Type RM Length L Ch R = 1 ,49778   ,461,461,461
BEGIN DESCRIPTION:
CUERO CREEK 50.0
END DESCRIPTION:
XS GIS Cut Line= 3
      2524724.97     13634475.03        2524325.       13634875.
      2523925.02     13635274.98
#Sta/Elev= 30
  4438.9  245.93  4537.9  241.19    4651  238.25  4756.4  236.99  4792.4  236.87
  4820.7  234.99  4834.8  234.66    4849  235.07  4877.3  234.88  4891.4  235.79
  4905.6  235.47  4919.7  234.36  4933.8  232.58    4948   227.4  4956.1  225.83
  4956.6  225.33  4967.6  225.33  4968.1  225.83  4976.3  230.62  4990.4  235.66
    5001  237.62  5008.1  237.62  5018.7  238.34  5061.1  237.49  5075.7  237.54
  5103.5  238.25  5358.1  242.18  5414.7  243.99    5443  244.46  5570.2  248.93
#Mann= 5 ,-1 , 0
  4438.9     .05       0  4756.4      .1       0  4956.1     .05       0
  4968.1      .1       0  5075.7     .05       0
Bank Sta=4956.1,4968.1
XS Rating Curve= 0 ,0
Exp/Cntr=0.3,0.1

Type RM Length L Ch R = 1 ,49317   ,445,445,445
BEGIN DESCRIPTION:
CUERO CREEK 49.0
END DESCRIPTION:
XS GIS Cut Line= 3
      2524674.98     13634225.01        2524275.       13634425.
      2523474.98     13635225.02
#Sta/Elev= 30
  4548.3  250.28  4660.1  243.99  4735.6  238.93  4780.3  236.98  4869.7  234.94
    4920  236.28  4935.1  235.72  4942.4   235.3  4950.8  233.43  4959.2  225.01
  4967.1  224.47  4967.6  223.97  4978.6  223.97  4979.1  224.47  4981.5  229.47
  4992.7  233.91  5037.9  235.39  5080.3  234.65  5151.1   236.9  5187.2     237
  5221.8   235.8  5306.6   236.4  5391.5  237.42  5603.6  241.47  5674.3  243.86
  5688.5  243.78  5872.3  250.21  6013.7  256.76    6042  257.34  6126.9  262.29
#Mann= 5 ,-1 , 0
  4548.3     .05       0  4935.1      .1       0  4967.1     .05       0
  4979.1      .1       0  5187.2     .05       0
Bank Sta=4967.1,4979.1
XS Rating Curve= 0 ,0
Exp/Cntr=0.3,0.1

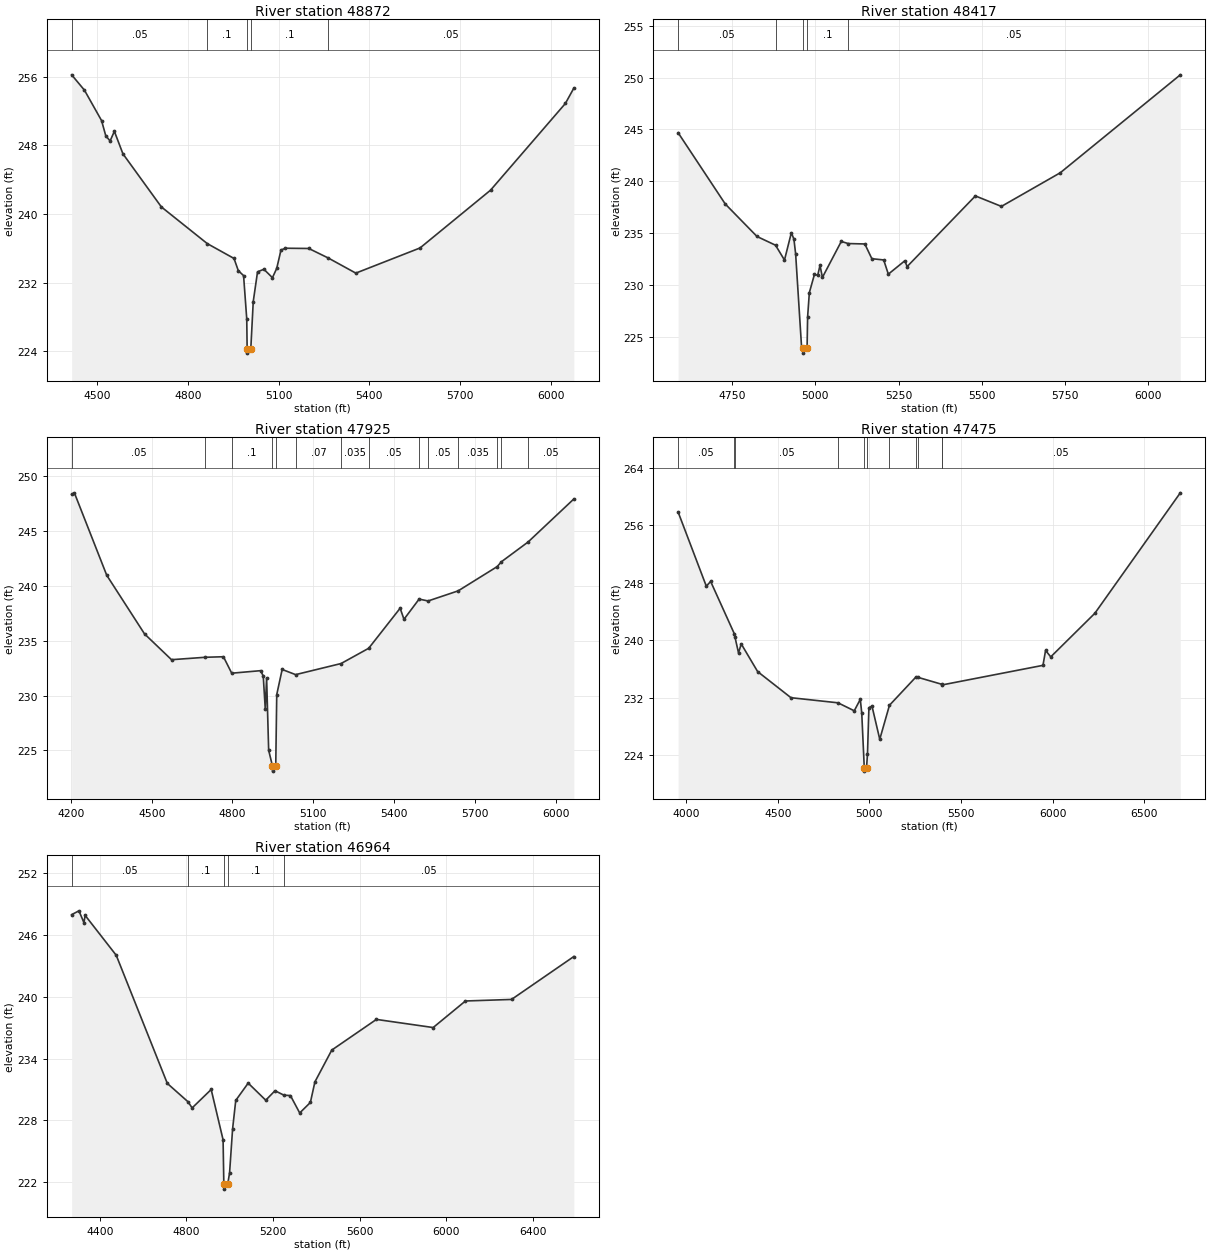
Type RM Length L Ch R = 1 ,48872   ,455,455,455
BEGIN DESCRIPTION:
CUERO CREEK 48.0
END DESCRIPTION:
XS GIS Cut Line= 3
      2524575.01     13633624.99        2524175.       13634025.
      2523374.99     13634775.01
#Sta/Elev= 30
  4414.7  256.23  4457.1  254.44  4513.7   250.9  4527.8  249.11    4542  248.53
  4556.1  249.65  4584.4  247.03  4711.7  240.84  4863.6  236.57  4952.1  234.84
  4966.3  233.42  4983.8  232.84  4994.3  227.79  4995.6  224.31  4996.1  223.81
  5007.7  224.31  5015.8  229.82    5030  233.28    5051  233.58  5079.3   232.6
  5093.5  233.68  5107.6  235.81  5121.8  236.03  5199.7     236  5264.2  234.89
  5355.3  233.13  5567.8  236.06  5801.2  242.79  6048.9  252.89    6077  254.68
#Mann= 5 ,-1 , 0
  4414.7     .05       0  4863.6      .1       0  4995.6     .05       0
  5007.7      .1       0  5264.2     .05       0
Bank Sta=4995.6,5007.7
XS Rating Curve= 0 ,0
Exp/Cntr=0.3,0.1

Type RM Length L Ch R = 1 ,48417   ,492,492,492
BEGIN DESCRIPTION:
CUERO CREEK 47.0
END DESCRIPTION:
XS GIS Cut Line= 3
      2524325.01       13633575.        2523925.       13633675.
      2523175.01     13634474.99
#Sta/Elev= 30
  4587.7  244.68  4729.4  237.81  4824.8  234.68  4880.4  233.84  4907.3  232.41
  4927.9  235.04  4935.6  234.43  4940.8  233.01  4958.8  223.94    4963  223.94
  4963.5  223.44  4975.2  223.94  4976.8  226.93    4982  229.27  4997.4  231.04
  5007.1  230.94    5014  231.89  5021.3  230.74  5077.9   234.2  5098.8     234
  5148.7  233.96  5169.8  232.54  5205.4  232.42  5219.3  231.05  5268.9  232.34
  5275.8  231.78  5480.9  238.59  5559.1  237.58  5735.9  240.82  6096.6  250.26
#Mann= 5 ,-1 , 0
  4587.7     .05       0  4880.4      .1       0    4963     .05       0
  4975.2      .1       0  5098.8     .05       0
Bank Sta=4963,4975.2
XS Rating Curve= 0 ,0
Exp/Cntr=0.3,0.1

Type RM Length L Ch R = 1 ,47925   ,450,450,450
BEGIN DESCRIPTION:
CUERO CREEK 46.0
END DESCRIPTION:
XS GIS Cut Line= 3
      2524375.04       13633375.        2523575.       13633325.
      2522775.01     13634024.99
#Sta/Elev= 30
  4202.8  248.33  4212.9  248.47  4333.1  240.96  4473.4  235.62  4573.6  233.27
  4698.7  233.49  4766.4  233.54  4797.1  232.04  4904.2  232.27  4914.2  231.79
  4921.7  228.77  4926.7   231.6  4934.3  225.02  4948.1  223.62  4948.6  223.12
  4960.6  223.62  4964.3  230.09  4984.4  232.38  5034.4  231.91  5203.1  232.92
  5305.7  234.31  5422.5  237.96  5436.7  236.95  5492.9  238.79  5526.3  238.62
  5637.9  239.54  5782.8  241.75  5798.4  242.19  5897.5  243.99  6067.4  247.91
#Mann= 14 ,-1 , 0
  4202.8     .05       0  4698.7    .035       0  4797.1      .1       0
  4948.1     .05       0  4960.6      .1       0  5034.4     .07       0
  5203.1    .035       0  5305.7     .05       0  5492.9    .035       0
  5526.3     .05       0  5637.9    .035       0  5782.8     .05       0
  5798.4    .035       0  5897.5     .05       0
Bank Sta=4948.1,4960.6
XS Rating Curve= 0 ,0
Exp/Cntr=0.3,0.1

Type RM Length L Ch R = 1 ,47475   ,511,511,511
BEGIN DESCRIPTION:
CUERO CREEK 45.0
END DESCRIPTION:
XS GIS Cut Line= 3
      2524574.99       13633175.        2523575.       13632875.
      2522374.98     13634075.02
#Sta/Elev= 30
    3956  257.85    4110  247.53  4133.5   248.2    4263  240.91  4266.5  240.44
  4285.7  238.26  4300.5  239.51  4390.1  235.66    4572  232.03  4828.6  231.32
  4917.4  230.21  4950.4   231.8  4958.3  229.91    4972  222.32  4972.5  221.82
  4984.5  222.32  4989.6  224.18  4997.4  230.64  5014.2  230.86  5056.6  226.25
  5109.6  230.98  5252.7  234.87  5262.7  234.88  5395.9  233.89  5397.6  233.81
  5947.5  236.53  5961.7   238.6    5990  237.71  6230.4  243.76  6697.1  260.52
#Mann= 11 ,-1 , 0
    3956     .05       0    4263    .035       0  4266.5     .05       0
  4828.6      .1       0    4972     .05       0  4984.5      .1       0
  5109.6     .05       0  5252.7     .07       0  5262.7     .05       0
  5395.9     .07       0  5397.6     .05       0
Bank Sta=4972,4984.5
XS Rating Curve= 0 ,0
Exp/Cntr=0.3,0.1

Type RM Length L Ch R = 1 ,46964   ,409,409,409
BEGIN DESCRIPTION:
X18691
END DESCRIPTION:
XS GIS Cut Line= 3
       2523783.7      13631758.8      2523445.16     13632500.99
      2522309.03     13633485.34
#Sta/Elev= 30
  4269.8  247.98  4303.5  248.35  4326.5   247.2    4332  247.91  4475.7  244.03
  4711.6  231.58    4807   229.8  4826.2   229.2  4914.1  230.99  4969.1   226.1
  4972.5  221.81    4973  221.31  4990.6  221.81  4999.1   222.9    5013  227.16
  5027.6  229.93    5085  231.61  5166.1  229.95  5208.8  230.87  5249.9  230.44
  5280.1   230.4  5322.9  228.71  5372.2  229.73  5393.1  231.73    5471  234.82
  5677.1   237.8  5939.2  237.01  6088.3  239.59  6301.1  239.74  6588.8  243.91
#Mann= 5 ,-1 , 0
  4269.8     .05       0    4807      .1       0  4972.5     .05       0
  4990.6      .1       0  5249.9     .05       0
Bank Sta=4972.5,4990.6
XS Rating Curve= 0 ,0
Exp/Cntr=0.3,0.1