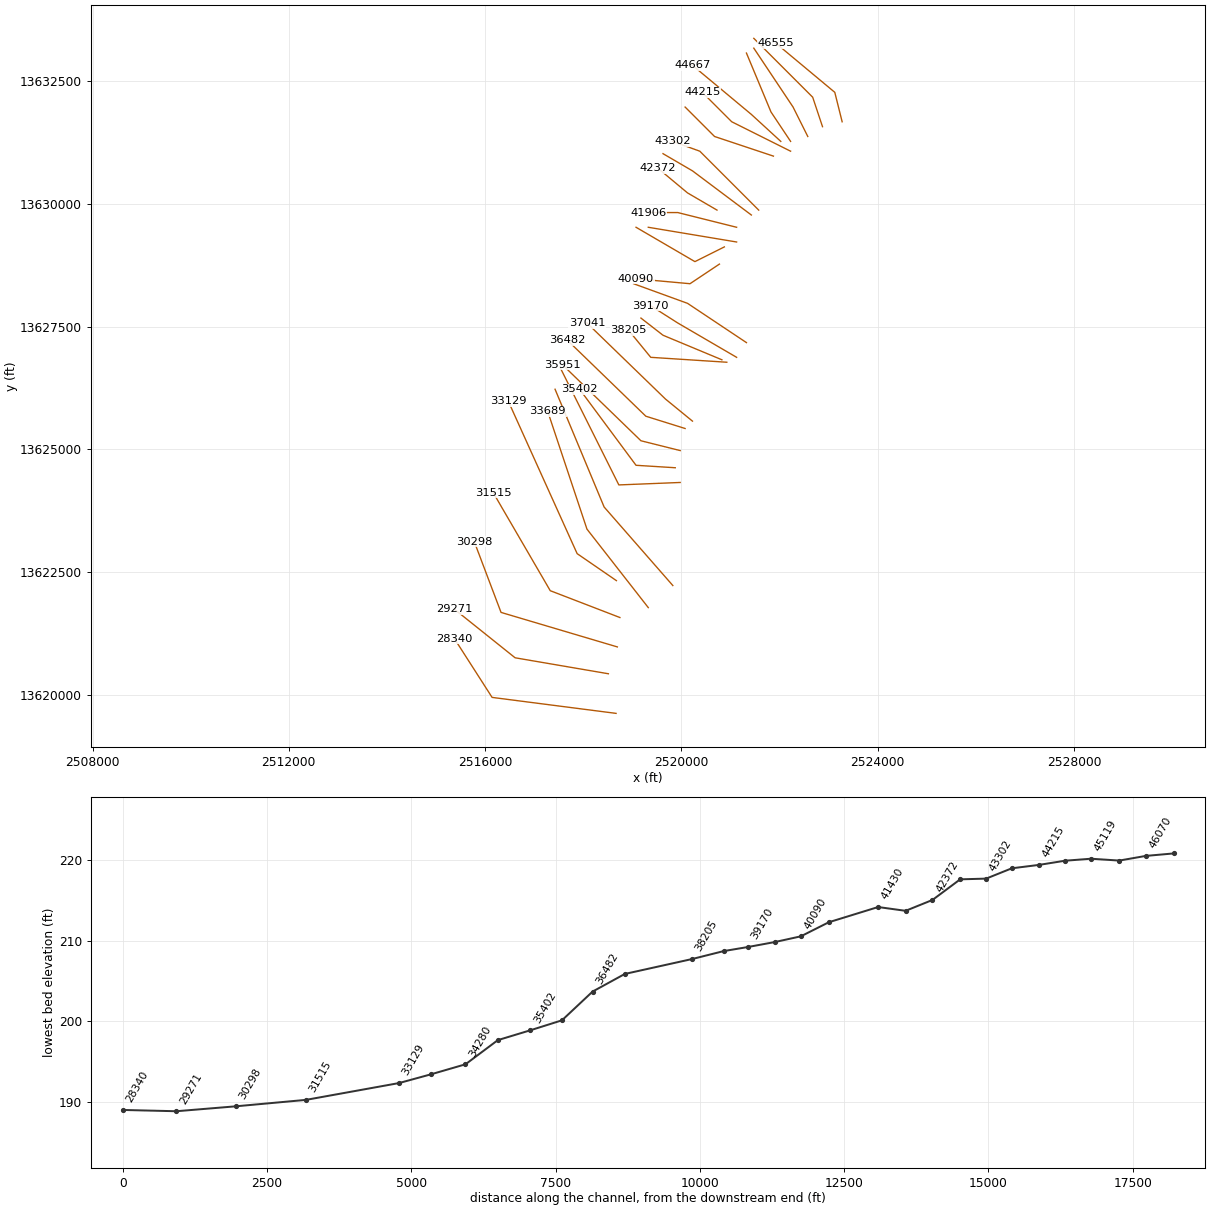
HEC-RAS study CUERO CREEK.prj: CUERO CREEK Base Level Engineering

--- CUERO CREEK.g01 (geometry) --- (continued)

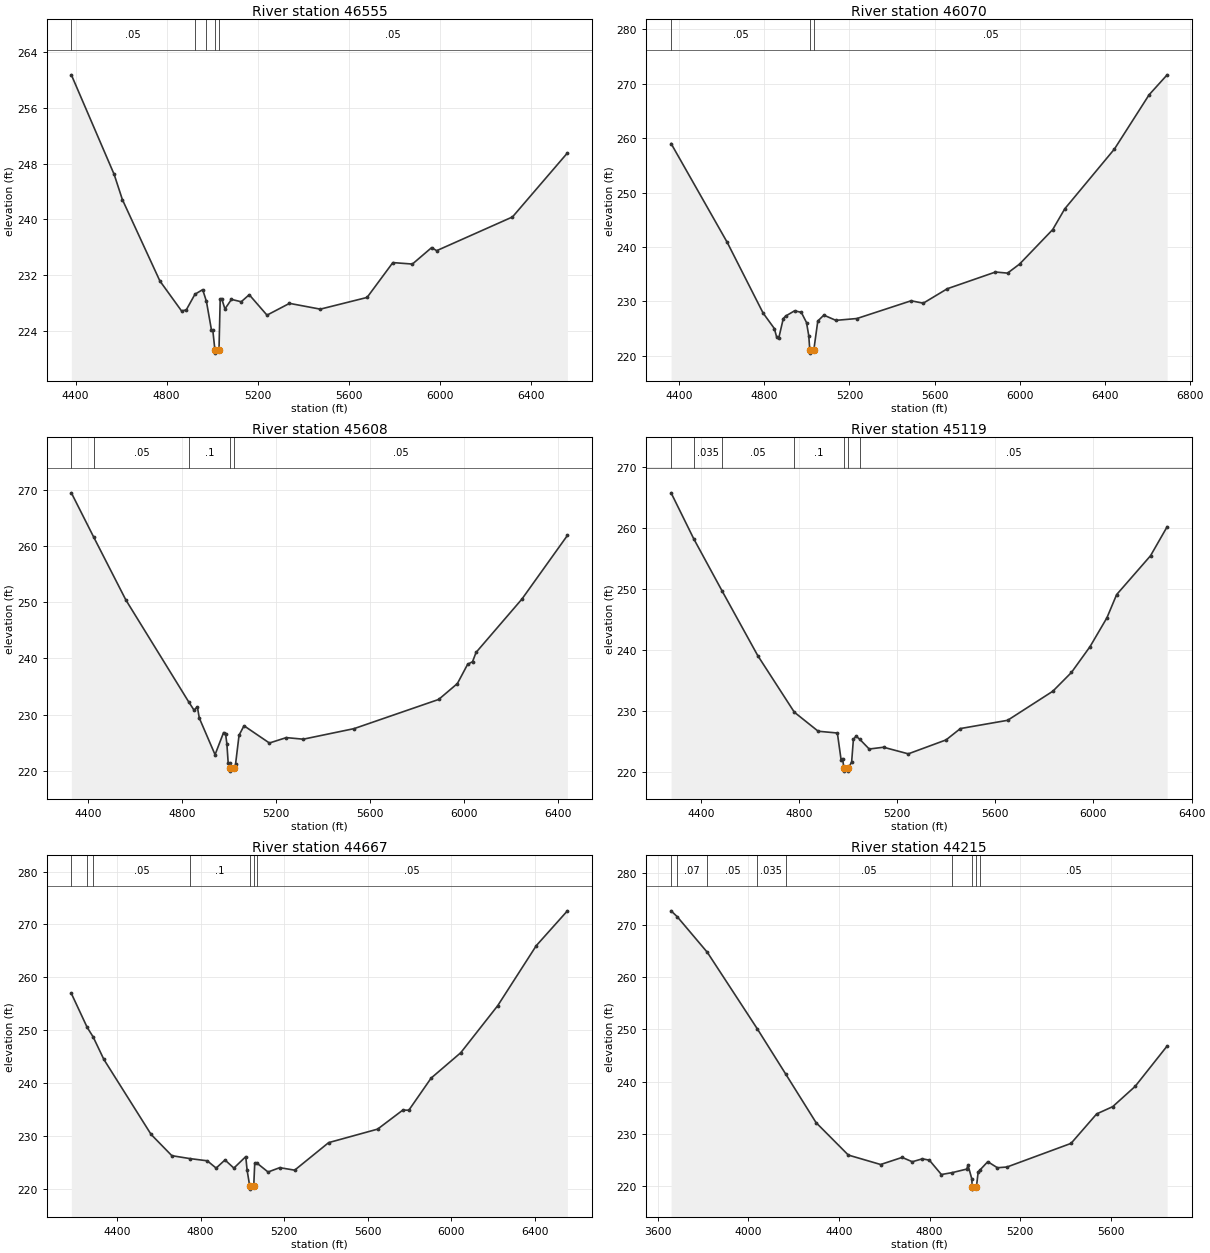
Type RM Length L Ch R = 1 ,46555   ,485,485,485
BEGIN DESCRIPTION:
CUERO CREEK 44.0
END DESCRIPTION:
XS GIS Cut Line= 3
      2523275.01     13631674.98        2523125.       13632275.
      2521925.03     13633274.97
#Sta/Elev= 30
  4381.6  260.75  4569.7  246.47  4605.8  242.86  4770.7  231.18  4866.1  226.87
  4886.7  227.02    4925  229.27  4958.9  229.93  4975.3  228.25  4997.5  224.14
  5003.3  224.14  5012.5  221.32    5013  220.82  5030.6  221.32  5035.9  228.52
  5042.4  228.65  5056.7  227.16  5085.4  228.53  5128.3  228.19  5163.5   229.2
  5241.6  226.27  5340.5  227.96  5475.9  227.13  5681.5  228.81  5794.8  233.81
  5880.7   233.6  5965.3  235.96  5987.4  235.52  6320.7  240.36  6562.1  249.54
#Mann= 5 ,-1 , 0
  4381.6     .05       0    4925      .1       0  4975.3     .05       0
  5012.5     .05       0  5030.6     .05       0
Bank Sta=5012.5,5030.6
XS Rating Curve= 0 ,0
Exp/Cntr=0.3,0.1

Type RM Length L Ch R = 1 ,46070   ,462,462,462
BEGIN DESCRIPTION:
CUERO CREEK 43.0
END DESCRIPTION:
XS GIS Cut Line= 3
        2522875.       13631575.        2522675.       13632175.
      2521475.01     13633374.99
#Sta/Elev= 30
  4362.5  259.02    4626  240.87  4794.7  227.87  4847.4  225.03  4857.9  223.52
  4868.5  223.33  4889.5  226.87  4900.1  227.31  4942.2  228.28  4973.9  228.01
  4998.5  226.13  5009.1   223.7    5014  221.01  5014.5  220.51  5032.5  221.01
  5051.5  226.41  5079.8  227.49  5136.4  226.53  5235.4  226.87  5489.9  230.13
  5546.5  229.68  5659.6  232.34  5885.9  235.41  5942.5  235.21    5999  236.87
  6154.6  243.21  6211.2  247.02  6444.5  258.01  6607.2  267.97    6692  271.64
#Mann= 3 ,-1 , 0
  4362.5     .05       0    5014     .05       0  5032.5     .05       0
Bank Sta=5014,5032.5
XS Rating Curve= 0 ,0
Exp/Cntr=0.3,0.1

Type RM Length L Ch R = 1 ,45608   ,489,489,489
BEGIN DESCRIPTION:
CUERO CREEK 42.0
END DESCRIPTION:
XS GIS Cut Line= 3
      2522575.02     13631374.96        2522275.       13631975.
      2521474.99     13633175.01
#Sta/Elev= 30
  4328.9  269.51  4424.5  261.59  4560.9  250.44  4830.2  232.17  4851.6  230.79
  4865.6  231.39    4874  229.38  4941.1  222.86  4977.4  226.81  4985.8   226.6
  4991.4  224.81    4997  221.36  5002.8  221.36    5004  220.43  5004.5  219.93
  5022.5  220.43  5028.3  221.14  5043.3  226.33  5064.4  228.01  5172.5  224.94
  5244.6   225.9  5316.8  225.62  5533.1   227.5  5893.6   232.7  5973.3  235.53
  6016.8  238.95  6037.9  239.43  6052.9  241.08  6248.2  250.58    6442  261.92
#Mann= 5 ,-1 , 0
  4328.9    .035       0  4424.5     .05       0  4830.2      .1       0
    5004     .05       0  5022.5     .05       0
Bank Sta=5004,5022.5
XS Rating Curve= 0 ,0
Exp/Cntr=0.3,0.1

Type RM Length L Ch R = 1 ,45119   ,452,452,452
BEGIN DESCRIPTION:
CUERO CREEK 41.0
END DESCRIPTION:
XS GIS Cut Line= 3
        2522225.       13631275.        2521825.       13631875.
        2521325.     13633074.99
#Sta/Elev= 30
    4279  265.72  4371.3   258.2  4487.5  249.61    4632  239.08  4781.1  229.81
  4878.4  226.69  4956.5   226.4  4971.6  222.04  4977.6  222.22  4983.3  220.66
  4983.8  220.16  5001.3  220.16  5001.8  220.66  5014.7  221.68  5021.8  225.35
  5032.6   225.9  5048.3  225.35  5086.2  223.78  5144.7  224.07  5245.5  222.99
  5399.3  225.27  5457.8  227.13  5650.1  228.48  5834.3  233.24  5910.1  236.31
  5985.9  240.54  6054.7  245.26  6094.3  249.06  6232.4  255.42  6300.1  260.17
#Mann= 7 ,-1 , 0
    4279     .05       0  4371.3    .035       0  4487.5     .05       0
  4781.1      .1       0  4983.3     .05       0  5001.8      .1       0
  5048.3     .05       0
Bank Sta=4983.3,5001.8
XS Rating Curve= 0 ,0
Exp/Cntr=0.3,0.1

Type RM Length L Ch R = 1 ,44667   ,452,452,452
BEGIN DESCRIPTION:
CUERO CREEK 40.0
END DESCRIPTION:
XS GIS Cut Line= 3
        2522025.       13631275.        2521425.       13631825.
      2520224.99     13632825.01
#Sta/Elev= 30
  4181.3  256.94  4257.2  250.51  4285.6  248.72    4337  244.46  4563.3  230.26
  4662.6  226.24  4748.8  225.69  4832.4  225.27  4874.7  223.89  4917.2  225.43
  4959.8  223.89  5016.7  226.06  5023.2  223.47    5036  220.41  5036.5  219.91
  5054.8  220.41  5059.7  224.82  5068.3   224.9  5123.5  223.15  5179.4  223.97
    5251   223.5  5413.7  228.71    5648  231.26  5769.1  234.87  5797.7  234.84
  5904.5  240.92  6046.4  245.72  6223.4  254.62  6408.2  265.98  6557.3  272.57
#Mann= 7 ,-1 , 0
  4181.3     .05       0  4257.2    .035       0  4285.6     .05       0
  4748.8      .1       0    5036     .05       0  5054.8      .1       0
  5068.3     .05       0
Bank Sta=5036,5054.8
XS Rating Curve= 0 ,0
Exp/Cntr=0.3,0.1

Type RM Length L Ch R = 1 ,44215   ,469,469,469
BEGIN DESCRIPTION:
CUERO CREEK 39.0
END DESCRIPTION:
XS GIS Cut Line= 3
      2522225.02     13631074.99        2521025.       13631675.
        2520425.       13632275.
#Sta/Elev= 30
  3658.3  272.74  3685.1  271.63  3818.6  264.77  4038.8  250.13  4163.7   241.5
  4298.4  232.14  4440.9  225.92  4583.5  224.11  4678.5  225.47  4723.3  224.64
    4768   225.2  4798.7  224.94  4851.8  222.19  4900.1  222.56  4963.6  223.23
  4969.2  223.98    4986  221.36  4987.8  219.89  4988.3  219.39  5006.6  219.89
  5014.1  222.64  5020.6  222.99  5056.5  224.65    5099  223.49  5141.4  223.63
  5424.2  228.16  5537.4  233.81  5608.1   235.2  5707.1  239.08  5848.5  246.83
#Mann= 9 ,-1 , 0
  3658.3     .05       0  3685.1     .07       0  3818.6     .05       0
  4038.8    .035       0  4163.7     .05       0  4900.1     .12       0
  4987.8     .05       0  5006.6     .12       0  5020.6     .05       0
Bank Sta=4987.8,5006.6
XS Rating Curve= 0 ,0
Exp/Cntr=0.3,0.1

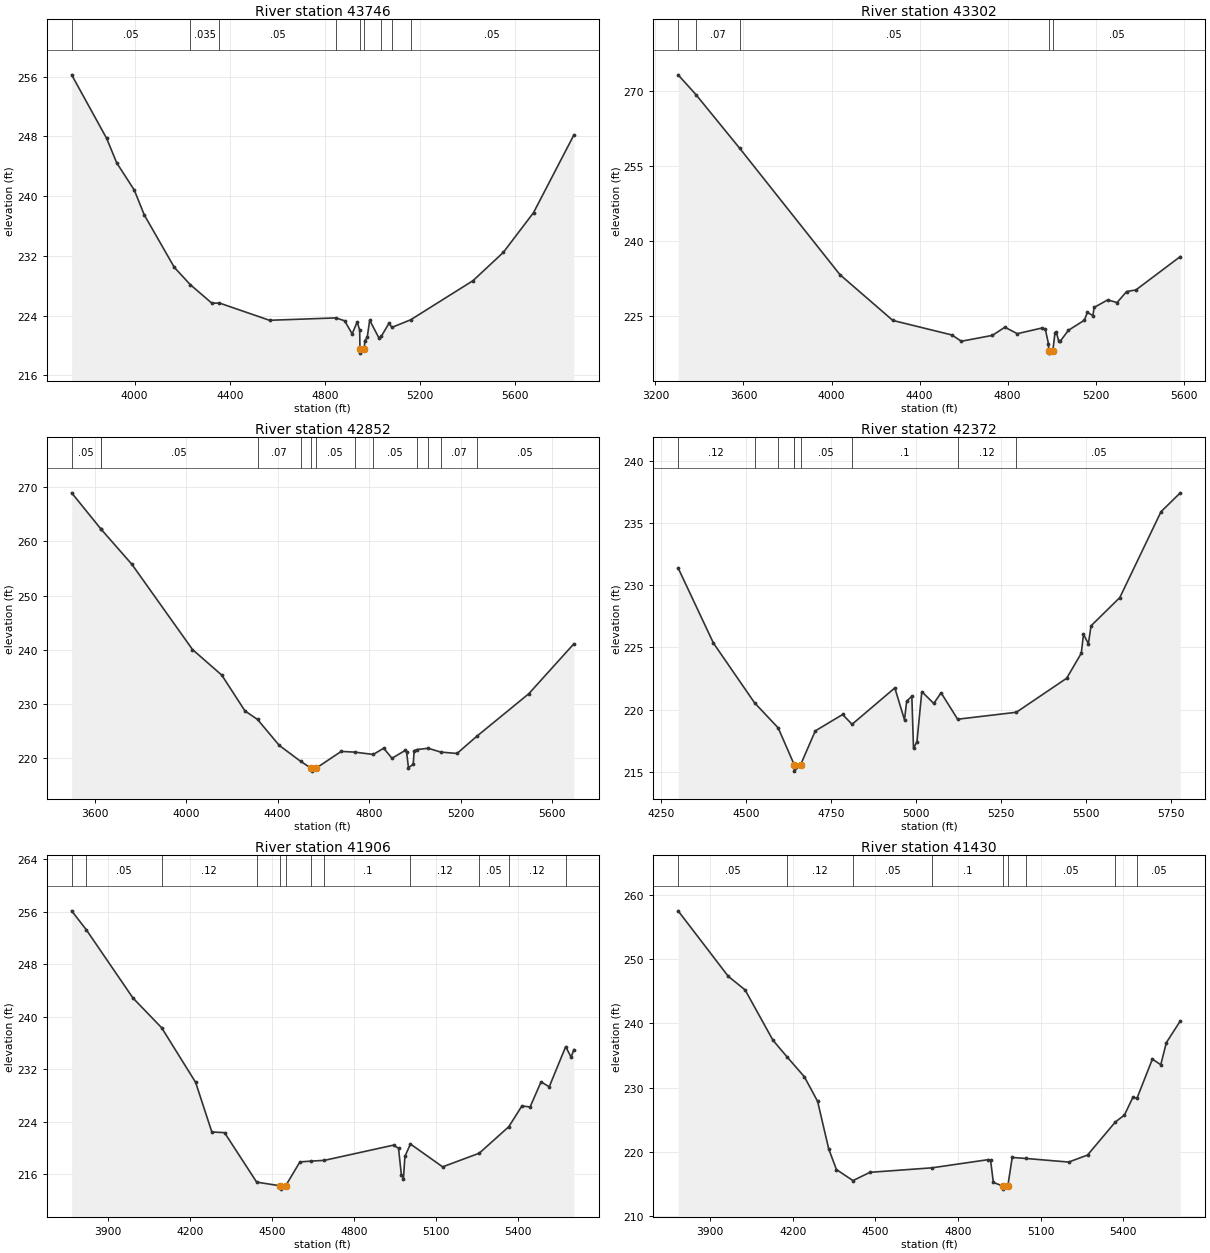
Type RM Length L Ch R = 1 ,43746   ,444,444,444
BEGIN DESCRIPTION:
CUERO CREEK 38.0
END DESCRIPTION:
XS GIS Cut Line= 3
      2521874.97     13630975.01        2520675.       13631375.
        2520075.       13631975.
#Sta/Elev= 30
  3734.9  256.26  3882.4  247.73  3924.6  244.46  3998.4  240.82  4040.5  237.49
    4167  230.46  4234.6  228.13  4325.2  225.66  4357.1  225.68  4567.6  223.37
  4847.3  223.69  4883.8   223.3  4915.4  221.55  4936.5  223.15  4947.1  222.04
  4948.2  219.47  4948.7  218.97    4967  219.47  4968.2  220.62  4978.7  221.08
  4989.2  223.38  5028.1     221  5038.6  221.25  5070.5  222.98  5082.6  222.42
  5161.2  223.43    5424  228.68  5551.3  232.46  5678.6  237.79  5848.3  248.19
#Mann= 9 ,-1 , 0
  3734.9     .05       0  4234.6    .035       0  4357.1     .05       0
  4847.3     .12       0  4948.2     .05       0    4967     .12       0
  5038.6     .05       0  5082.6     .12       0  5161.2     .05       0
Bank Sta=4948.2,4967
XS Rating Curve= 0 ,0
Exp/Cntr=0.3,0.1

Type RM Length L Ch R = 1 ,43302   ,450,450,450
BEGIN DESCRIPTION:
CUERO CREEK 37.0
END DESCRIPTION:
XS GIS Cut Line= 3
      2521575.03     13629874.97        2520375.       13631075.
      2519825.03     13631274.99
#Sta/Elev= 30
  3302.9  273.19  3383.8  269.25  3582.8  258.54  4038.3  233.34  4278.7  224.21
  4547.4  221.31  4589.9  220.06  4731.3  221.23  4787.9  222.86  4844.4  221.57
  4957.6  222.71  4971.7  222.45  4985.9   219.6    4987  218.19  4987.5  217.69
  5005.9  218.19  5015.3  221.63  5021.3  221.97  5031.9   220.2  5040.6  220.12
  5076.5  222.24    5149  224.25  5162.9  225.81  5188.2  225.18  5193.5   226.8
  5255.4  228.31  5297.9  227.77  5341.2  229.98  5383.1  230.28  5585.2  236.95
#Mann= 5 ,-1 , 0
  3302.9     .05       0  3383.8     .07       0  3582.8     .05       0
    4987     .05       0  5005.9     .05       0
Bank Sta=4987,5005.9
XS Rating Curve= 0 ,0
Exp/Cntr=0.3,0.1

Type RM Length L Ch R = 1 ,42852   ,480,480,480
BEGIN DESCRIPTION:
CUERO CREEK 36.0
END DESCRIPTION:
XS GIS Cut Line= 3
        2521425.       13629775.        2520225.       13630675.
      2519625.02     13631024.99
#Sta/Elev= 30
    3500  268.98  3626.6  262.37  3628.3  262.28  3763.5  255.77  4028.1  240.05
  4156.2  235.32  4257.3  228.72  4312.3  227.14  4407.3  222.35  4500.1  219.43
  4547.8   218.1  4548.3   217.6  4566.7   218.1  4678.1  221.24  4736.4  221.11
  4818.2  220.68  4863.5  221.83    4900  219.97  4957.3  221.42  4963.5  221.18
  4971.9  218.25  4992.7  218.85  4996.9  221.39  5010.1  221.59  5058.4  221.82
  5112.7  221.12    5184  220.86  5269.9  224.01  5497.8  231.89  5694.6   241.1
#Mann= 13 ,-1 , 0
    3500     .05       0  3626.6     .07       0  3628.3     .05       0
  4312.3     .07       0  4500.1     .05       0  4547.8     .05       0
  4566.7     .05       0  4736.4     .07       0  4818.2     .05       0
  5010.1     .07       0  5058.4     .05       0  5112.7     .07       0
  5269.9     .05       0
Bank Sta=4547.8,4566.7
XS Rating Curve= 0 ,0
Exp/Cntr=0.3,0.1

Type RM Length L Ch R = 1 ,42372   ,466,466,466
BEGIN DESCRIPTION:
CUERO CREEK 35.0
END DESCRIPTION:
XS GIS Cut Line= 3
      2520725.01     13629874.99        2520125.       13630225.
      2519524.97     13630725.02
#Sta/Elev= 30
    4301   231.4  4404.8  225.35  4525.7  220.54  4595.1  218.52  4641.5   215.6
  4641.8  215.54  4642.3  215.04  4660.7  215.54  4704.1  218.28  4784.4   219.6
  4812.1  218.81  4937.8  221.74  4966.3  219.16  4972.5  220.66  4987.8  221.08
  4992.7  216.87  5002.8  217.41  5017.1  221.44  5052.3  220.49  5073.7  221.35
  5122.4  219.22  5294.9  219.78  5442.8  222.52  5485.7  224.53  5492.2  226.06
  5506.6   225.3  5514.4  226.74    5599  229.02    5720  235.93  5776.7  237.45
#Mann= 9 ,-1 , 0
    4301     .12       0  4525.7     .07       0  4595.1     .12       0
  4641.5     .05       0  4641.8     .05       0  4660.7     .05       0
  4812.1      .1       0  5122.4     .12       0  5294.9     .05       0
Bank Sta=4641.8,4660.7
XS Rating Curve= 0 ,0
Exp/Cntr=0.3,0.1

Type RM Length L Ch R = 1 ,41906   ,476,476,476
BEGIN DESCRIPTION:
CUERO CREEK 34.0
END DESCRIPTION:
XS GIS Cut Line= 3
        2521125.       13629525.        2519925.       13629825.
      2519325.03       13629825.
#Sta/Elev= 30
  3767.3  256.16  3821.1  253.26  3991.5  242.86  4096.6  238.31  4220.8  229.98
  4280.1  222.41  4326.5  222.31    4444  214.76  4530.9  214.19  4531.4  213.69
  4549.9  214.19  4602.2  217.84  4644.4  217.97  4691.5  218.08    4945  220.41
    4963   219.9  4973.3  215.89    4981  215.31  4986.2  218.67  5006.5  220.58
  5124.2  217.09  5258.1  219.17  5366.1  223.21  5414.2  226.38  5444.2  226.23
  5484.2  230.06  5514.2  229.31  5574.4  235.44  5594.2  233.82  5604.2  234.98
#Mann= 12 ,-1 , 0
  3767.3     .07       0  3821.1     .05       0  4096.6     .12       0
    4444     .07       0  4530.9     .05       0  4549.9     .07       0
  4644.4     .05       0  4691.5      .1       0  5006.5     .12       0
  5258.1     .05       0  5366.1     .12       0  5574.4     .05       0
Bank Sta=4530.9,4549.9
XS Rating Curve= 0 ,0
Exp/Cntr=0.3,0.1

Type RM Length L Ch R = 1 ,41430   ,855,855,855
BEGIN DESCRIPTION:
CUERO CREEK 33.0
END DESCRIPTION:
XS GIS Cut Line= 3
      2521124.95     13629225.01        2519925.       13629425.
      2519324.98       13629525.
#Sta/Elev= 30
  3783.1  257.54  3965.5  247.32  4026.4  245.22  4127.7  237.37  4179.2  234.76
  4241.8  231.68  4289.9  227.85  4330.5   220.4  4358.4  217.21  4418.6  215.49
    4480  216.78  4705.3  217.48  4910.9  218.76  4918.5  218.63  4928.6   215.2
  4962.2  214.66  4962.7  214.16  4981.2  214.66  4997.1   219.1  5046.6  218.94
  5202.4  218.38  5270.8  219.47  5371.7  224.62  5405.1  225.72  5435.5  228.47
  5450.4  228.32  5506.5  234.43  5536.9  233.55  5557.2     237  5607.9  240.38
#Mann= 9 ,-1 , 0
  3783.1     .05       0  4179.2     .12       0  4418.6     .05       0
  4705.3      .1       0  4962.2     .05       0  4981.2      .1       0
  5046.6     .05       0  5371.7     .12       0  5450.4     .05       0
Bank Sta=4962.2,4981.2
XS Rating Curve= 0 ,0
Exp/Cntr=0.3,0.1

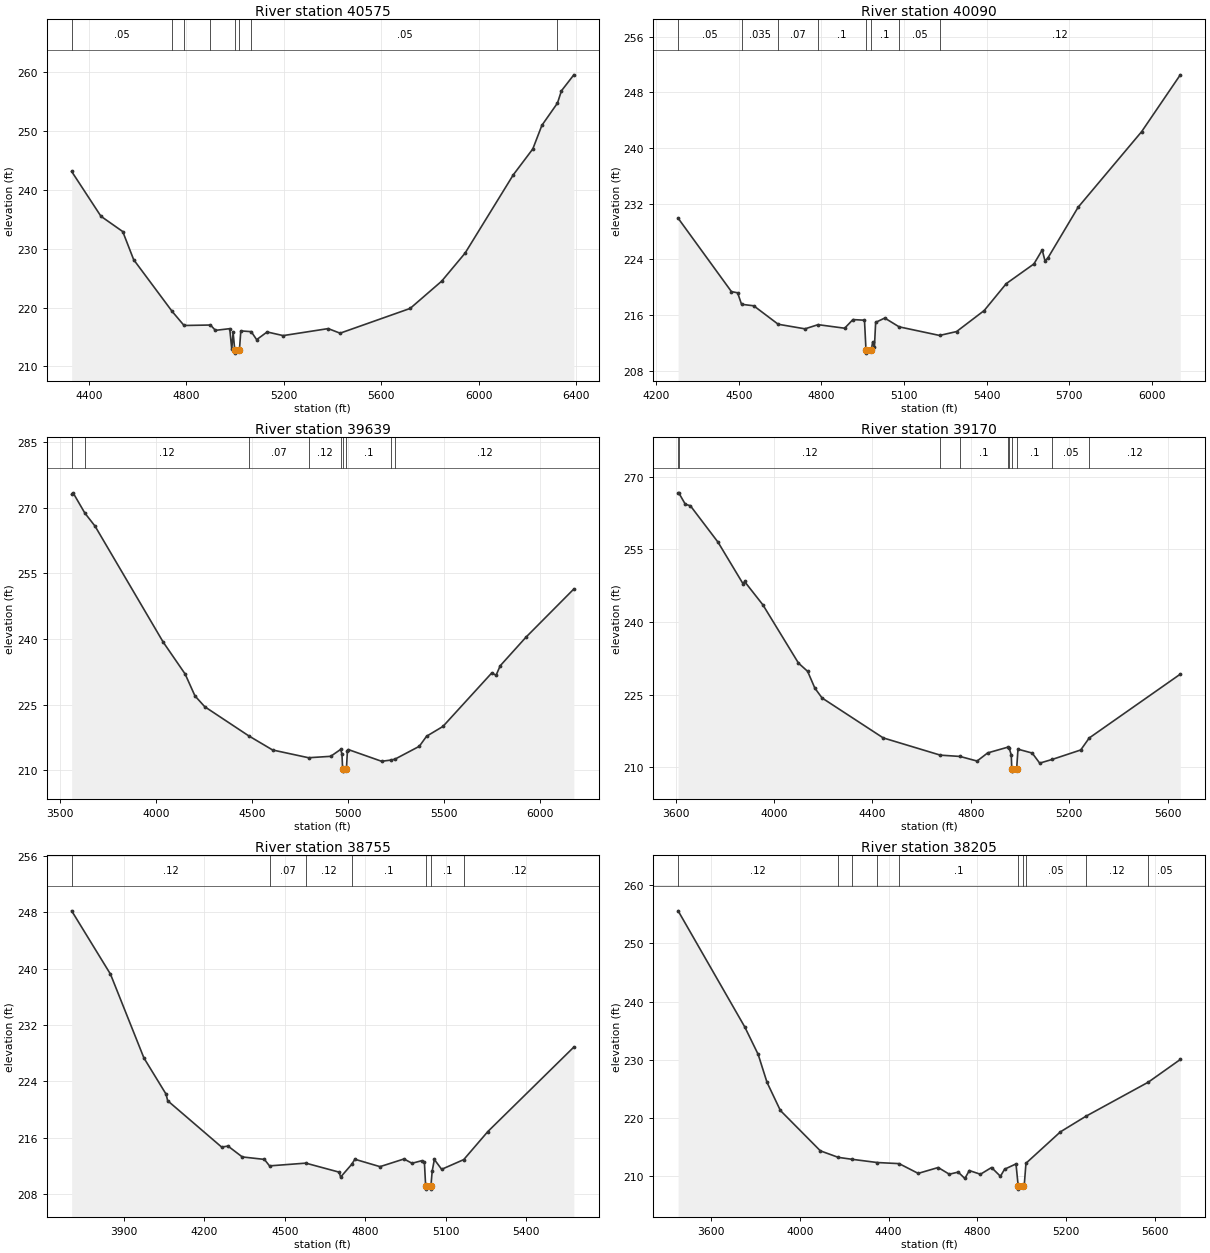
Type RM Length L Ch R = 1 ,40575   ,485,485,485
BEGIN DESCRIPTION:
CUERO CREEK 32.0
END DESCRIPTION:
XS GIS Cut Line= 3
        2520875.       13629125.        2520275.       13628825.
      2519074.97     13629525.02
#Sta/Elev= 30
  4329.2  243.16  4449.4  235.54  4538.8  232.94  4583.6  228.16  4741.7  219.35
  4790.3  216.97  4898.7  217.05    4919  216.14  4977.7  216.43    4986  212.95
  4991.6   215.8  4998.3  212.77  4998.8  212.27  5017.4  212.77  5023.2  216.05
  5065.9  215.92  5088.1  214.56  5131.1  215.87  5196.8  215.25  5381.6  216.44
  5430.4  215.66  5717.8  219.87  5847.2  224.51  5943.1  229.27  6140.8  242.58
    6221  246.99  6258.2     251  6322.2  254.79  6338.4  256.87  6389.3  259.59
#Mann= 8 ,-1 , 0
  4329.2     .05       0  4741.7     .07       0  4790.3     .05       0
  4898.7      .1       0  4998.3     .05       0  5017.4      .1       0
  5065.9     .05       0  6322.2     .07       0
Bank Sta=4998.3,5017.4
XS Rating Curve= 0 ,0
Exp/Cntr=0.3,0.1

Type RM Length L Ch R = 1 ,40090   ,451,451,451
BEGIN DESCRIPTION:
CUERO CREEK 31.0
END DESCRIPTION:
XS GIS Cut Line= 3
        2520775.       13628775.        2520175.       13628375.
      2519075.04       13628475.
#Sta/Elev= 30
  4278.9  229.91  4472.7  219.36  4495.2  219.19  4509.4  217.54  4553.8  217.32
  4642.7  214.67  4740.1  214.01  4787.7  214.61  4884.3   214.1  4914.4  215.34
  4956.4  215.25  4961.8  211.02  4962.3  210.52  4981.1  211.02  4986.5  212.15
  4992.5  211.37    4997  214.94  5030.1  215.56  5082.2   214.3  5229.4  213.06
  5291.2  213.62  5391.6  216.64  5471.9  220.51  5572.4  223.34  5602.5  225.35
  5612.5  223.79  5622.6  224.16    5733  231.48    5964  242.35  6104.5  250.51
#Mann= 8 ,-1 , 0
  4278.9     .05       0  4509.4    .035       0  4642.7     .07       0
  4787.7      .1       0  4961.8     .05       0  4981.1      .1       0
  5082.2     .05       0  5229.4     .12       0
Bank Sta=4961.8,4981.1
XS Rating Curve= 0 ,0
Exp/Cntr=0.3,0.1

Type RM Length L Ch R = 1 ,39639   ,469,469,469
BEGIN DESCRIPTION:
CUERO CREEK 30.0
END DESCRIPTION:
XS GIS Cut Line= 3
      2521325.01     13627174.99        2520125.       13627975.
        2519025.       13628375.
#Sta/Elev= 30
  3562.1  273.04  3569.6  273.39  3630.8  268.76  3683.8  265.78  4038.3  239.29
  4152.5     232  4203.6     227  4254.7  224.52  4484.1  217.85  4607.7  214.64
  4794.6  212.87  4909.7  213.19  4961.2  214.76  4968.3   213.8  4971.9  210.31
  4972.4  209.81  4991.6  210.31  4996.8   214.4  5001.3  214.74  5174.6  212.06
    5222  212.33  5243.9  212.54  5370.8  215.48  5408.7  217.78  5493.8  220.02
  5747.2  232.21  5770.5  231.74  5791.7  233.88  5925.4  240.39  6174.8  251.42
#Mann= 9 ,-1 , 0
  3562.1     .05       0  3630.8     .12       0  4484.1     .07       0
  4794.6     .12       0  4961.2      .1       0  4971.9     .05       0
  4991.6      .1       0    5222     .05       0  5243.9     .12       0
Bank Sta=4971.9,4991.6
XS Rating Curve= 0 ,0
Exp/Cntr=0.3,0.1

Type RM Length L Ch R = 1 ,39170   ,415,415,415
BEGIN DESCRIPTION:
CUERO CREEK 29.0
END DESCRIPTION:
XS GIS Cut Line= 3
      2521125.04     13626874.98        2519925.       13627575.
      2519375.01       13627925.
#Sta/Elev= 30
  3610.5  266.64    3613  266.64  3639.9  264.27  3660.2  263.98  3772.6  256.46
  3874.7  247.84  3880.5  248.34    3955  243.52  4099.7  231.49  4136.9  229.79
  4166.2  226.33  4195.6  224.29  4444.1  216.05  4676.2  212.49  4756.4  212.22
  4825.7  211.27  4868.7  212.95    4953  214.17  4955.5  214.06  4964.6  212.52
  4966.7  209.69  4967.2  209.19  4986.5  209.69  4991.9  213.72  5049.7  212.92
  5080.2  210.84  5131.9  211.62    5247  213.56  5281.4  216.03  5651.7  229.21
#Mann= 10 ,-1 , 0
  3610.5     .05       0    3613     .12       0  4676.2     .07       0
  4756.4      .1       0    4953     .12       0  4955.5      .1       0
  4966.7     .05       0  4986.5      .1       0  5131.9     .05       0
  5281.4     .12       0
Bank Sta=4966.7,4986.5
XS Rating Curve= 0 ,0
Exp/Cntr=0.3,0.1

Type RM Length L Ch R = 1 ,38755   ,550,550,550
BEGIN DESCRIPTION:
CUERO CREEK 28.0
END DESCRIPTION:
XS GIS Cut Line= 3
      2520825.01     13626824.99        2519625.       13627325.
        2519175.       13627675.
#Sta/Elev= 30
  3706.5  248.19  3851.1   239.2  3975.7   227.3  4058.1  222.17    4064  221.24
    4265  214.66  4288.8   214.8  4341.9  213.26  4424.2  212.91  4443.4  211.99
  4578.4  212.38  4702.6   211.1  4708.1   210.4  4749.4  212.21  4761.1  212.93
  4854.8  211.88  4944.2  212.97    4974  212.36  5009.7  212.72  5020.1  212.52
  5024.7  209.19  5025.2  208.69    5044  208.69  5044.5  209.19    5049  211.21
  5057.2   212.9  5084.3   211.5  5166.6  212.88  5256.3  216.86  5576.6  228.85
#Mann= 7 ,-1 , 0
  3706.5     .12       0  4443.4     .07       0  4578.4     .12       0
  4749.4      .1       0  5024.7     .05       0  5044.5      .1       0
  5166.6     .12       0
Bank Sta=5024.7,5044.5
XS Rating Curve= 0 ,0
Exp/Cntr=0.3,0.1

Type RM Length L Ch R = 1 ,38205   ,1164,1164,1164
BEGIN DESCRIPTION:
CUERO CREEK 27.0
END DESCRIPTION:
XS GIS Cut Line= 3
      2520925.01       13626775.        2519375.       13626875.
      2518924.98     13627425.03
#Sta/Elev= 30
  3450.9  255.61  3751.5  235.61  3811.7   230.9  3851.7  226.08  3911.9  221.24
  4092.2  214.29  4172.8  213.17  4234.1  212.84  4348.4  212.28  4447.2  212.09
  4533.2  210.41  4623.3  211.42  4673.4  210.27  4713.5  210.63  4743.6  209.53
  4763.6   210.9  4813.7  210.26  4863.8  211.42  4903.9  209.91  4922.7  211.13
  4974.1  212.04  4984.1   208.2  4984.6   207.7  5004.1   208.2  5011.3  208.37
    5019  212.15  5174.3  217.56  5288.1  220.22  5570.8  226.12  5714.8  230.02
#Mann= 10 ,-1 , 0
  3450.9     .12       0  4172.8     .07       0  4234.1     .12       0
  4348.4    .035       0  4447.2      .1       0  4984.1     .05       0
  5004.1      .1       0    5019     .05       0  5288.1     .12       0
  5570.8     .05       0
Bank Sta=4984.1,5004.1
XS Rating Curve= 0 ,0
Exp/Cntr=0.3,0.1

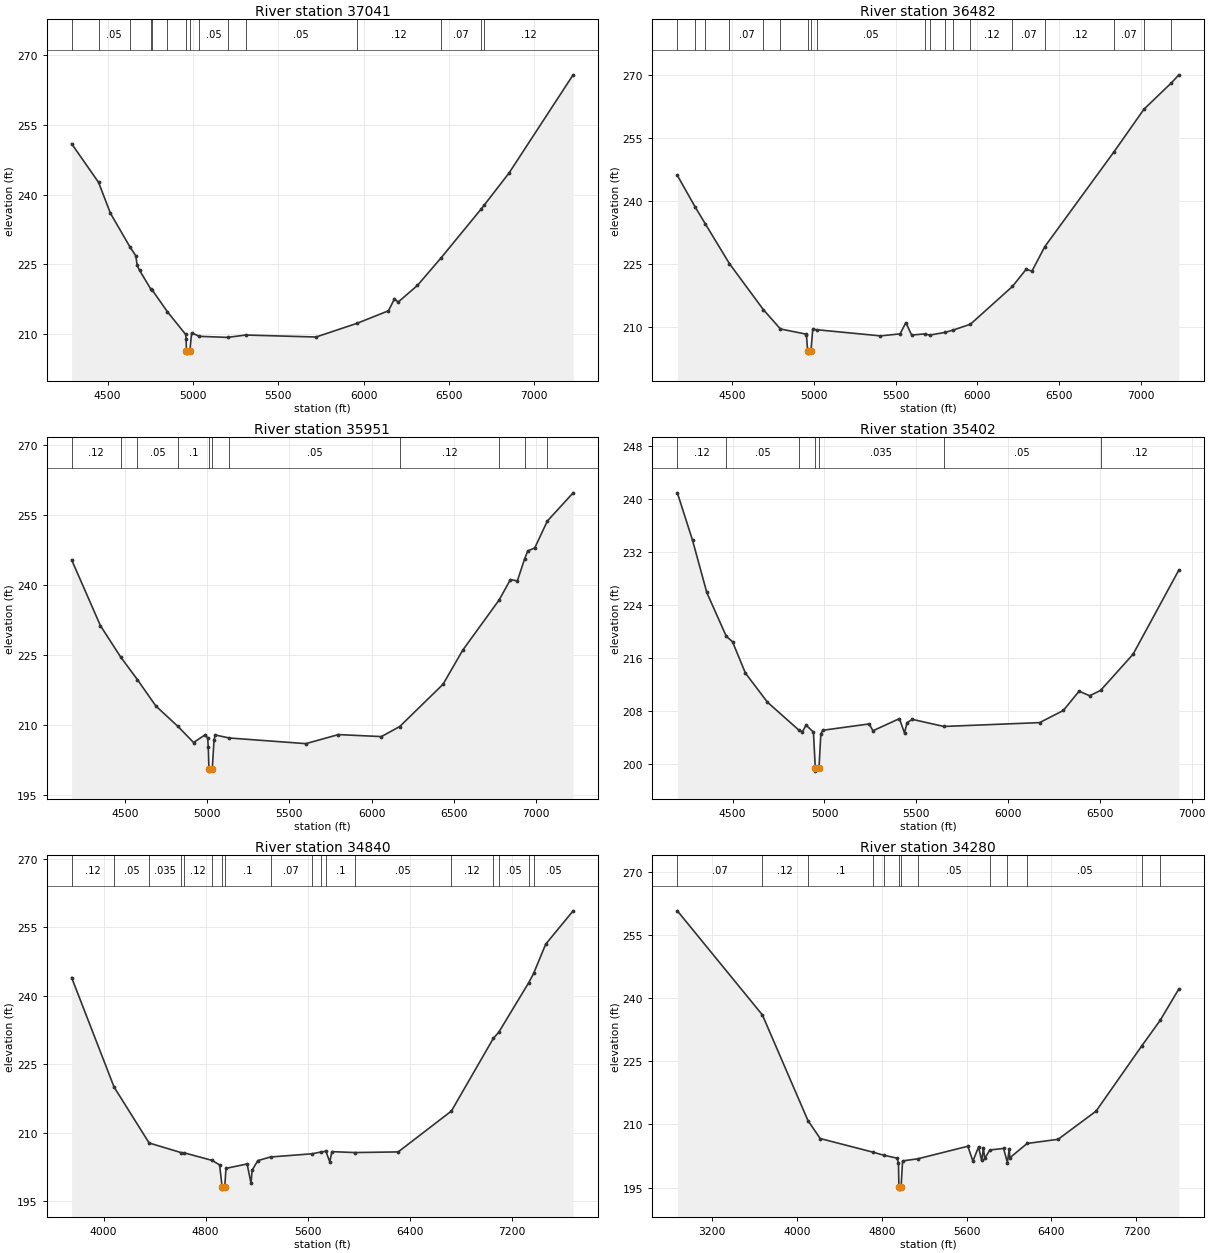
Type RM Length L Ch R = 1 ,37041   ,559,559,559
BEGIN DESCRIPTION:
CUERO CREEK 26.0
END DESCRIPTION:
XS GIS Cut Line= 3
      2520224.98     13625575.01        2519675.       13626025.
      2518074.99     13627575.01
#Sta/Elev= 30
  4289.6  250.95  4447.5  242.62  4517.1  235.96  4631.6  228.71  4665.7  226.81
  4673.6  224.77    4688  223.66  4753.1  219.67  4761.7  219.44  4851.2  214.74
  4957.9  209.87  4960.7  208.99  4962.2  206.35  4962.7  205.85  4982.3  206.35
    4993  210.25  5036.2  209.47  5203.7  209.24  5309.7  209.75  5721.6  209.32
  5960.3  212.25  6145.8  214.96  6181.3  217.55  6202.4  216.83  6315.6  220.43
  6454.3  226.37  6687.6  236.82  6708.5   237.8    6853  244.67  7227.9  265.78
#Mann= 15 ,-1 , 0
  4289.6     .12       0  4447.5     .05       0  4631.6     .12       0
  4753.1      .1       0  4761.7     .12       0  4851.2      .1       0
  4962.2     .05       0  4982.3      .1       0  5036.2     .05       0
  5203.7      .1       0  5309.7     .05       0  5960.3     .12       0
  6454.3     .07       0  6687.6     .05       0  6708.5     .12       0
Bank Sta=4962.2,4982.3
XS Rating Curve= 0 ,0
Exp/Cntr=0.3,0.1

Type RM Length L Ch R = 1 ,36482   ,531,531,531
BEGIN DESCRIPTION:
CUERO CREEK 25.0
END DESCRIPTION:
XS GIS Cut Line= 3
      2520075.02     13625424.99        2519275.       13625675.
      2517675.03     13627224.97
#Sta/Elev= 30
  4165.7  245.98    4276  238.37  4335.9   234.5    4484  224.98    4692  213.99
    4796  209.41  4949.9  208.21  4955.2  207.88  4962.3  204.16  4962.8  203.66
  4982.5  204.16  4993.4  209.35  5018.2  209.23  5407.1  207.77  5527.2  208.24
  5562.5  210.92    5598  207.97  5680.3  208.24  5708.1  207.95  5801.2  208.59
    5849  209.11  5957.5  210.55  6213.9  219.53  6298.1  223.63  6333.4  223.19
  6412.3  229.03  6834.7  251.58  7018.1  261.74    7186  268.02  7231.5  269.93
#Mann= 19 ,-1 , 0
  4165.7     .12       0    4276     .07       0  4335.9     .05       0
    4484     .07       0    4692     .12       0    4796      .1       0
  4962.3     .05       0  4982.5      .1       0  5018.2     .05       0
  5680.3    .035       0  5708.1     .05       0  5801.2    .035       0
    5849     .07       0  5957.5     .12       0  6213.9     .07       0
  6412.3     .12       0  6834.7     .07       0  7018.1    .035       0
    7186     .05       0
Bank Sta=4962.3,4982.5
XS Rating Curve= 0 ,0
Exp/Cntr=0.3,0.1

Type RM Length L Ch R = 1 ,35951   ,549,549,549
BEGIN DESCRIPTION:
CUERO CREEK 24.0
END DESCRIPTION:
XS GIS Cut Line= 3
      2519975.02       13624975.        2519175.       13625175.
        2517575.       13626725.
#Sta/Elev= 30
  4174.8  245.37  4350.1  231.26  4472.6  224.58  4574.7  219.72  4687.6  214.04
  4822.3  209.66    4917  206.22  4989.1  207.91  5002.9  207.13  5006.5  205.24
  5010.5  200.59    5011  200.09  5030.8  200.59  5041.8  206.86    5049  207.84
  5134.1  207.19  5600.5  205.98  5798.5  207.92  6060.2  207.49  6171.9  209.65
    6435  218.69  6555.3  226.01  6777.2  236.79  6845.2  241.12  6887.7  240.85
  6931.4  245.53  6951.2  247.28  6993.7  247.93    7070  253.67  7227.1  259.72
#Mann= 11 ,-1 , 0
  4174.8     .12       0  4472.6     .07       0  4574.7     .05       0
  4822.3      .1       0  5010.5     .05       0  5030.8      .1       0
  5134.1     .05       0  6171.9     .12       0  6777.2     .07       0
  6931.4    .035       0    7070     .05       0
Bank Sta=5010.5,5030.8
XS Rating Curve= 0 ,0
Exp/Cntr=0.3,0.1

Type RM Length L Ch R = 1 ,35402   ,562,562,562
BEGIN DESCRIPTION:
CUERO CREEK 23.0
END DESCRIPTION:
XS GIS Cut Line= 3
      2519874.96       13624625.        2519075.       13624675.
      2517924.97     13626225.04
#Sta/Elev= 30
  4198.8  240.96  4281.4   233.8  4359.1  225.89  4465.3  219.25  4499.3  218.43
  4569.5  213.69  4689.7  209.28    4861  205.05  4880.1  204.82  4900.1  205.81
  4940.2  204.75  4950.1  199.35  4950.6  198.85  4970.4  199.35  4980.3  204.44
  4990.3  205.03  5243.4  205.99  5264.2  204.96  5408.3  206.79  5436.1  204.62
  5449.9  206.19  5479.2  206.68  5650.3  205.61  6171.9  206.19  6301.3  208.03
  6386.8  210.94  6444.7  210.26    6504  211.06    6681  216.54  6930.4  229.28
#Mann= 7 ,-1 , 0
  4198.8     .12       0  4465.3     .05       0    4861    .035       0
  4950.1     .05       0  4970.4    .035       0  5650.3     .05       0
    6504     .12       0
Bank Sta=4950.1,4970.4
XS Rating Curve= 0 ,0
Exp/Cntr=0.3,0.1

Type RM Length L Ch R = 1 ,34840   ,560,560,560
BEGIN DESCRIPTION:
CUERO CREEK 22.0
END DESCRIPTION:
XS GIS Cut Line= 3
      2519974.96       13624325.        2518725.       13624275.
      2517525.02     13626674.96
#Sta/Elev= 30
  3748.8  244.02  4081.9  220.01  4356.7  207.75  4607.4  205.64  4634.2  205.57
    4851  203.93  4909.7  202.94  4929.4  198.13  4929.9  197.63    4950  198.13
  4959.7  202.18  5125.5  203.15  5156.3  198.92  5164.7  201.78  5209.4  203.88
  5309.2  204.68    5635  205.38  5701.5  205.75  5743.6  205.94    5774   203.6
  5790.8  205.85  5970.6  205.65  6310.7  205.79    6728  214.75  7057.1  230.69
  7100.3  232.06  7333.4  242.84  7372.8  244.91  7467.8  251.34    7683  258.65
#Mann= 18 ,-1 , 0
  3748.8     .12       0  4081.9     .05       0  4356.7    .035       0
  4607.4      .1       0  4634.2     .12       0    4851      .1       0
  4929.4     .05       0    4950      .1       0  5309.2     .07       0
    5635      .1       0  5701.5     .05       0  5743.6      .1       0
  5970.6     .05       0    6728     .12       0  7057.1     .07       0
  7100.3     .05       0  7333.4    .035       0  7372.8     .05       0
Bank Sta=4929.4,4950
XS Rating Curve= 0 ,0
Exp/Cntr=0.3,0.1

Type RM Length L Ch R = 1 ,34280   ,591,591,591
BEGIN DESCRIPTION:
CUERO CREEK 21.0
END DESCRIPTION:
XS GIS Cut Line= 3
        2519825.       13622225.        2518425.       13623825.
      2517425.01     13626224.97
#Sta/Elev= 30
  2874.2   260.7  3675.8  235.98    4105  210.91  4220.5  206.64  4716.8  203.41
  4817.6  202.69  4943.8  201.99    4958  200.93  4961.9  195.13  4962.4  194.63
  4982.5  195.13  4996.9  201.33  5140.1  201.83  5611.8  204.81  5659.4  201.28
  5712.5  204.63  5741.8  201.43  5758.6   204.3    5771  201.93  5818.6  203.92
  5948.7  204.29  5984.5  200.93  6001.8  204.19  6007.7  202.06  6170.1  205.47
  6462.7  206.46  6820.2  213.15  7250.3  228.62  7423.3  234.67  7600.2  242.16
#Mann= 13 ,-1 , 0
  2874.2     .07       0  3675.8     .12       0    4105      .1       0
  4716.8     .05       0  4817.6      .1       0  4961.9     .05       0
  4982.5      .1       0  5140.1     .05       0  5818.6     .07       0
  5984.5     .12       0  6170.1     .05       0  7250.3    .035       0
  7423.3     .05       0
Bank Sta=4961.9,4982.5
XS Rating Curve= 0 ,0
Exp/Cntr=0.3,0.1

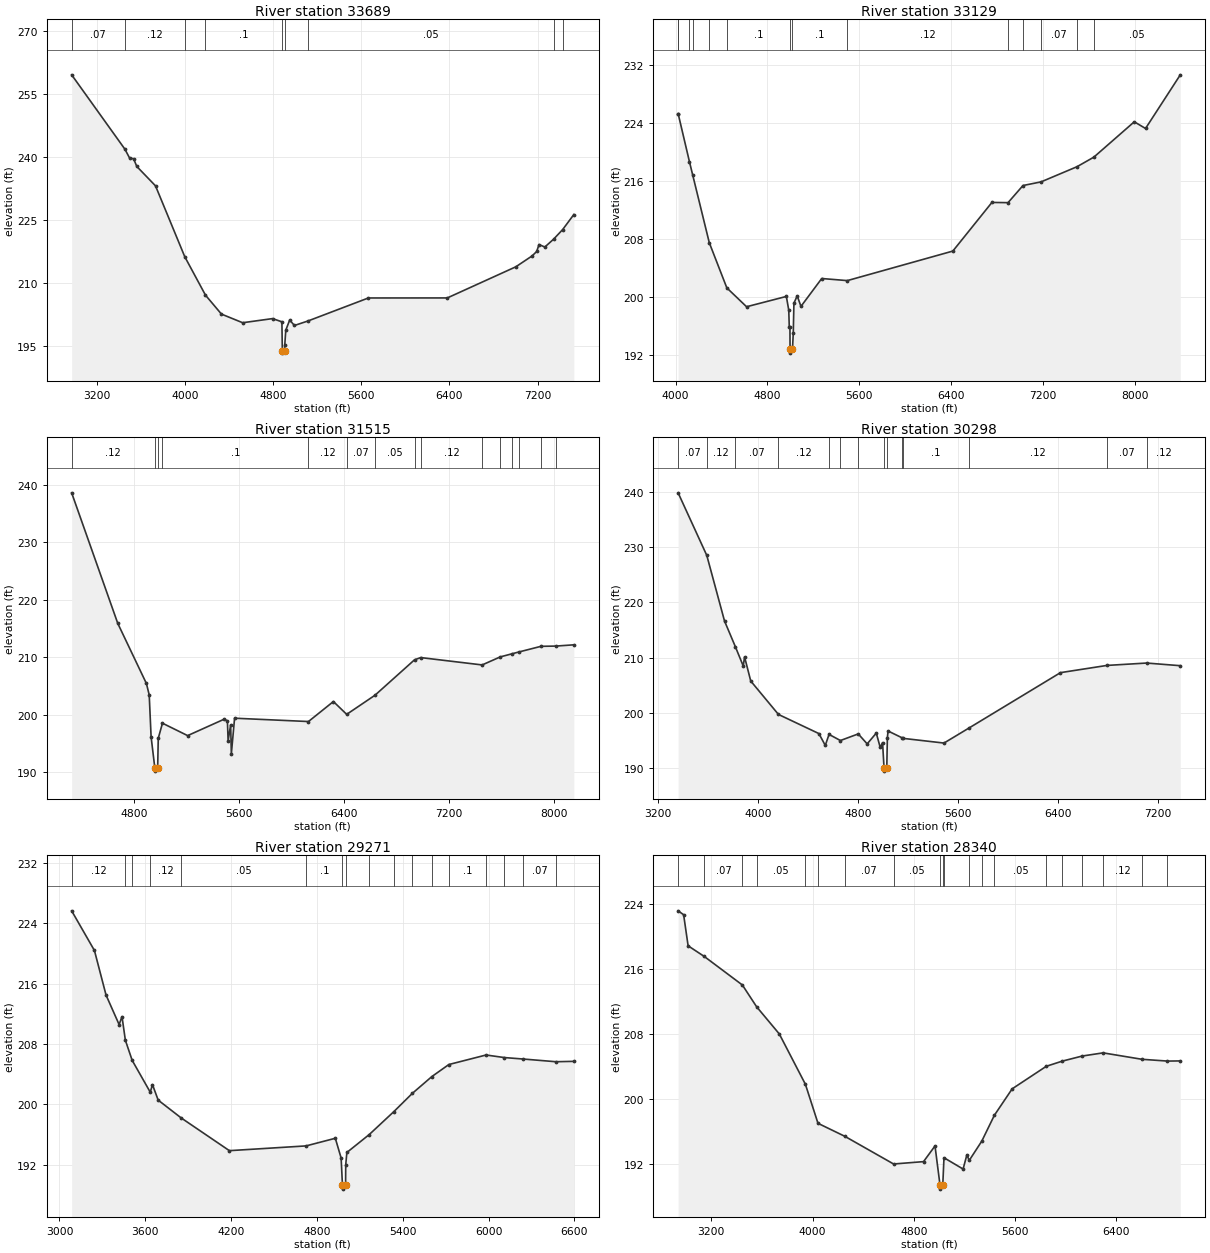
Type RM Length L Ch R = 1 ,33689   ,560,560,560
BEGIN DESCRIPTION:
CUERO CREEK 20.0
END DESCRIPTION:
XS GIS Cut Line= 3
      2519324.99     13621775.01        2518075.       13623375.
        2517275.     13625774.99
#Sta/Elev= 30
  2969.3   259.5  3453.1  241.83  3496.6  239.68  3531.8  239.57  3560.8  237.74
  3730.8  233.13  3996.4   216.3  4184.6  207.17  4329.5  202.67  4522.2  200.62
  4793.5   201.6  4878.5  200.84  4882.5   193.9    4883   193.4  4903.5   193.9
  4904.5  195.31  4913.8  198.85  4949.1  201.25  4992.5  199.97  5114.6  201.03
  5663.8   206.5  6380.5  206.51  7002.5   213.9    7150  216.48  7192.2  217.54
  7213.3  219.19    7266   218.6  7345.1  220.45  7428.1  222.75  7529.5  226.32
#Mann= 9 ,-1 , 0
  2969.3     .07       0  3453.1     .12       0  3996.4     .07       0
  4184.6      .1       0  4882.5     .05       0  4903.5      .1       0
  5114.6     .05       0  7345.1    .035       0  7428.1     .05       0
Bank Sta=4882.5,4903.5
XS Rating Curve= 0 ,0
Exp/Cntr=0.3,0.1

Type RM Length L Ch R = 1 ,33129   ,1614,1614,1614
BEGIN DESCRIPTION:
CUERO CREEK 19.0
END DESCRIPTION:
XS GIS Cut Line= 3
      2518674.99     13622325.01        2517875.       13622875.
      2516474.99     13625975.02
#Sta/Elev= 30
  4022.6  225.26  4023.3  225.26  4121.1  218.68  4149.4  216.85    4294  207.51
  4446.7  201.29  4618.6  198.69    4965  200.11    4986  198.21  4990.4  195.88
  4996.2  195.88  4997.2   192.8  4997.7   192.3  5018.3   192.8  5025.3  195.11
  5030.8  199.18  5059.4  200.19  5092.2  198.74    5273  202.58  5495.6  202.29
  6414.5  206.36  6754.7  213.06  6895.1  213.03  7025.2  215.39  7182.3  215.89
  7495.3  217.98  7642.2   219.3  7994.2  224.17  8092.2  223.25  8394.9  230.64
#Mann= 14 ,-1 , 0
  4022.6     .12       0  4023.3     .07       0  4121.1     .12       0
  4149.4     .07       0    4294     .12       0  4446.7      .1       0
  4997.2     .05       0  5018.3      .1       0  5495.6     .12       0
  6895.1    .035       0  7025.2     .12       0  7182.3     .07       0
  7495.3    .035       0  7642.2     .05       0
Bank Sta=4997.2,5018.3
XS Rating Curve= 0 ,0
Exp/Cntr=0.3,0.1

Type RM Length L Ch R = 1 ,31515   ,1217,1217,1217
BEGIN DESCRIPTION:
X18692
END DESCRIPTION:
XS GIS Cut Line= 3
      2518746.41     13621573.02      2517327.11     13622119.91
      2516168.28     13624112.05
#Sta/Elev= 30
  4323.8  238.64  4675.3  215.91  4893.3  205.46  4914.7  203.47    4929  196.19
  4957.7  190.71  4958.2  190.21    4979  190.71  4983.6  195.92  5015.6  198.55
  5207.4  196.39  5485.8  199.25  5510.4  198.95  5515.8  195.46    5535  198.28
  5540.4  193.22    5565  199.42  6127.8  198.84  6317.8  202.32  6419.1  200.09
  6634.8  203.42  6935.7  209.58  6982.7  209.97    7451  208.69  7589.3  210.09
  7675.3  210.61  7733.4  210.96  7899.5  211.93  8011.7  211.97  8149.5  212.19
#Mann= 15 ,-1 , 0
  4323.8     .12       0  4957.7     .05       0    4979     .12       0
  5015.6      .1       0  6127.8     .12       0  6419.1     .07       0
  6634.8     .05       0  6935.7    .035       0  6982.7     .12       0
    7451     .07       0  7589.3     .05       0  7675.3     .07       0
  7733.4    .035       0  7899.5     .07       0  8011.7     .12       0
Bank Sta=4957.7,4979
XS Rating Curve= 0 ,0
Exp/Cntr=0.3,0.1

Type RM Length L Ch R = 1 ,30298   ,1027,1027,1027
BEGIN DESCRIPTION:
X18693
END DESCRIPTION:
XS GIS Cut Line= 3
      2518694.33     13620974.06       2516324.5      13621677.2
      2515778.11     13623121.25
#Sta/Elev= 30
  3362.6  239.88  3591.9  228.53  3733.6  216.64  3820.3  211.98  3883.4  208.47
  3893.9  210.13  3943.4  205.75    4165  199.69  4488.4  196.22  4539.5  194.07
  4569.5  196.07  4660.4  194.96  4803.1  196.16  4874.4  194.35  4947.4  196.31
  4978.7  193.71  4997.5  194.58  5009.6  189.91  5010.1  189.41  5031.2  189.91
  5035.9  195.42  5041.3  196.69    5152  195.47  5158.1  195.36  5488.7   194.5
  5689.6  197.24  6420.2  207.27    6792  208.58  7109.5  209.01  7378.5  208.53
#Mann= 14 ,-1 , 0
  3362.6     .07       0  3591.9     .12       0  3820.3     .07       0
    4165     .12       0  4569.5      .1       0  4660.4     .12       0
  4803.1      .1       0  5009.6     .05       0  5031.2      .1       0
    5152     .12       0  5158.1      .1       0  5689.6     .12       0
    6792     .07       0  7109.5     .12       0
Bank Sta=5009.6,5031.2
XS Rating Curve= 0 ,0
Exp/Cntr=0.3,0.1

Type RM Length L Ch R = 1 ,29271   ,931,931,931
BEGIN DESCRIPTION:
X18694
END DESCRIPTION:
XS GIS Cut Line= 3
        2518512.      13620427.2      2516610.96     13620752.72
       2515375.4     13621741.17
#Sta/Elev= 30
  3085.2  225.63  3244.5  220.38  3325.7  214.48    3417  210.58  3437.3  211.63
  3460.7  208.51  3508.4  205.84  3634.7  201.63  3650.3  202.63  3690.1  200.58
  3851.1  198.22    4188  193.89  4724.1  194.52  4928.6  195.53  4969.2  192.92
  4978.6   189.3  4979.1   188.8  5000.4   189.3  5001.3  191.98  5009.3  193.65
  5165.6  196.02    5338  199.06  5466.9  201.47  5603.8   203.7  5722.4  205.29
  5982.5  206.55  6111.4  206.21  6240.3  206.02  6470.9  205.66  6596.2  205.71
#Mann= 17 ,-1 , 0
  3085.2     .12       0  3460.7     .05       0  3508.4     .07       0
  3634.7     .12       0  3851.1     .05       0  4724.1      .1       0
  4978.6     .05       0  5000.4      .1       0  5165.6     .12       0
    5338    .035       0  5466.9     .05       0  5603.8     .12       0
  5722.4      .1       0  5982.5     .07       0  6111.4     .12       0
  6240.3     .07       0  6470.9     .12       0
Bank Sta=4978.6,5000.4
XS Rating Curve= 0 ,0
Exp/Cntr=0.3,0.1

Type RM Length L Ch R = 1 ,28340   ,853,853,853
BEGIN DESCRIPTION:
X18695
END DESCRIPTION:
XS GIS Cut Line= 3
      2518668.29      13619619.9      2516142.21     13619945.43
      2515375.04      13621141.7
#Sta/Elev= 30
    2938  223.17  2981.6  222.69    3017  218.87  3144.7  217.56  3445.9  214.05
  3558.1  211.38  3737.8  208.03  3943.7  201.85  4043.2  197.05  4255.6  195.45
  4640.6  192.05  4877.2  192.34  4967.9  194.27  5007.4  189.46  5007.9  188.96
  5029.2  189.46  5038.8  192.82  5189.8  191.43    5220  193.19  5237.9  192.48
  5337.5  194.86    5437  198.04  5577.6  201.29  5847.3  204.06  5974.7   204.7
    6131  205.32  6296.1  205.71    6603  204.92  6804.9   204.7  6906.1  204.72
#Mann= 20 ,-1 , 0
    2938     .07       0  3144.7     .07       0  3445.9    .035       0
  3558.1     .05       0  3943.7    .035       0  4043.2     .05       0
  4255.6     .07       0  4640.6     .05       0  5007.4     .05       0
  5029.2     .12       0  5038.8     .05       0  5237.9    .035       0
  5337.5     .12       0    5437     .05       0  5847.3     .12       0
  5974.7     .05       0    6131     .07       0  6296.1     .12       0
    6603    .035       0  6804.9     .07       0
Bank Sta=5007.4,5029.2
XS Rating Curve= 0 ,0
Exp/Cntr=0.3,0.1