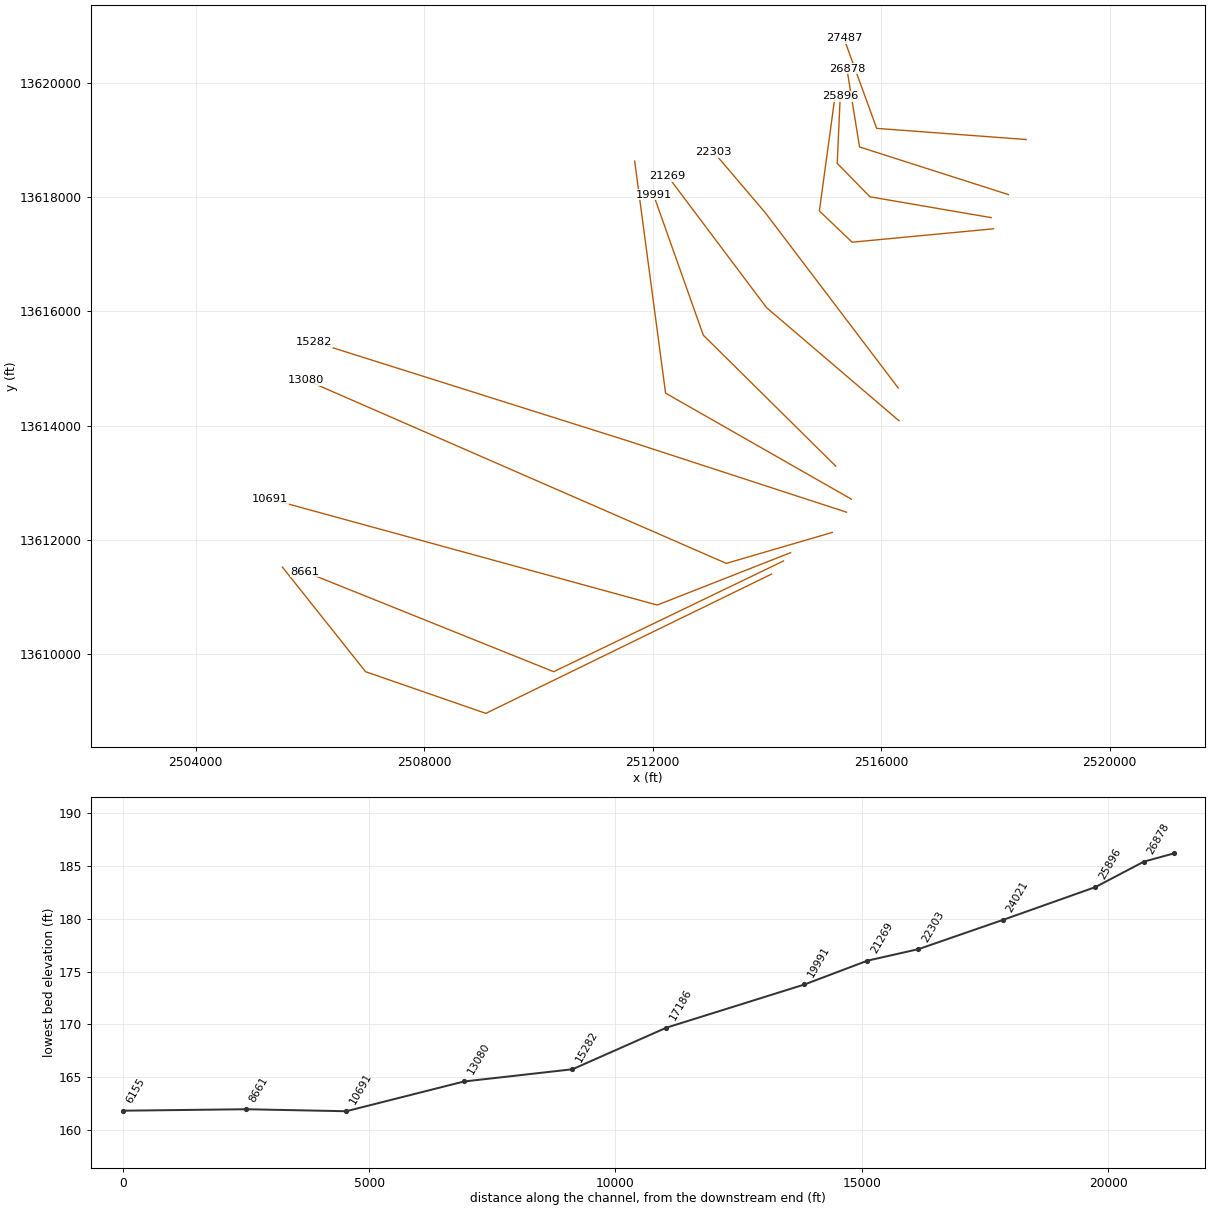
HEC-RAS study CUERO CREEK.prj: CUERO CREEK Base Level Engineering

--- CUERO CREEK.g01 (geometry) --- (continued)

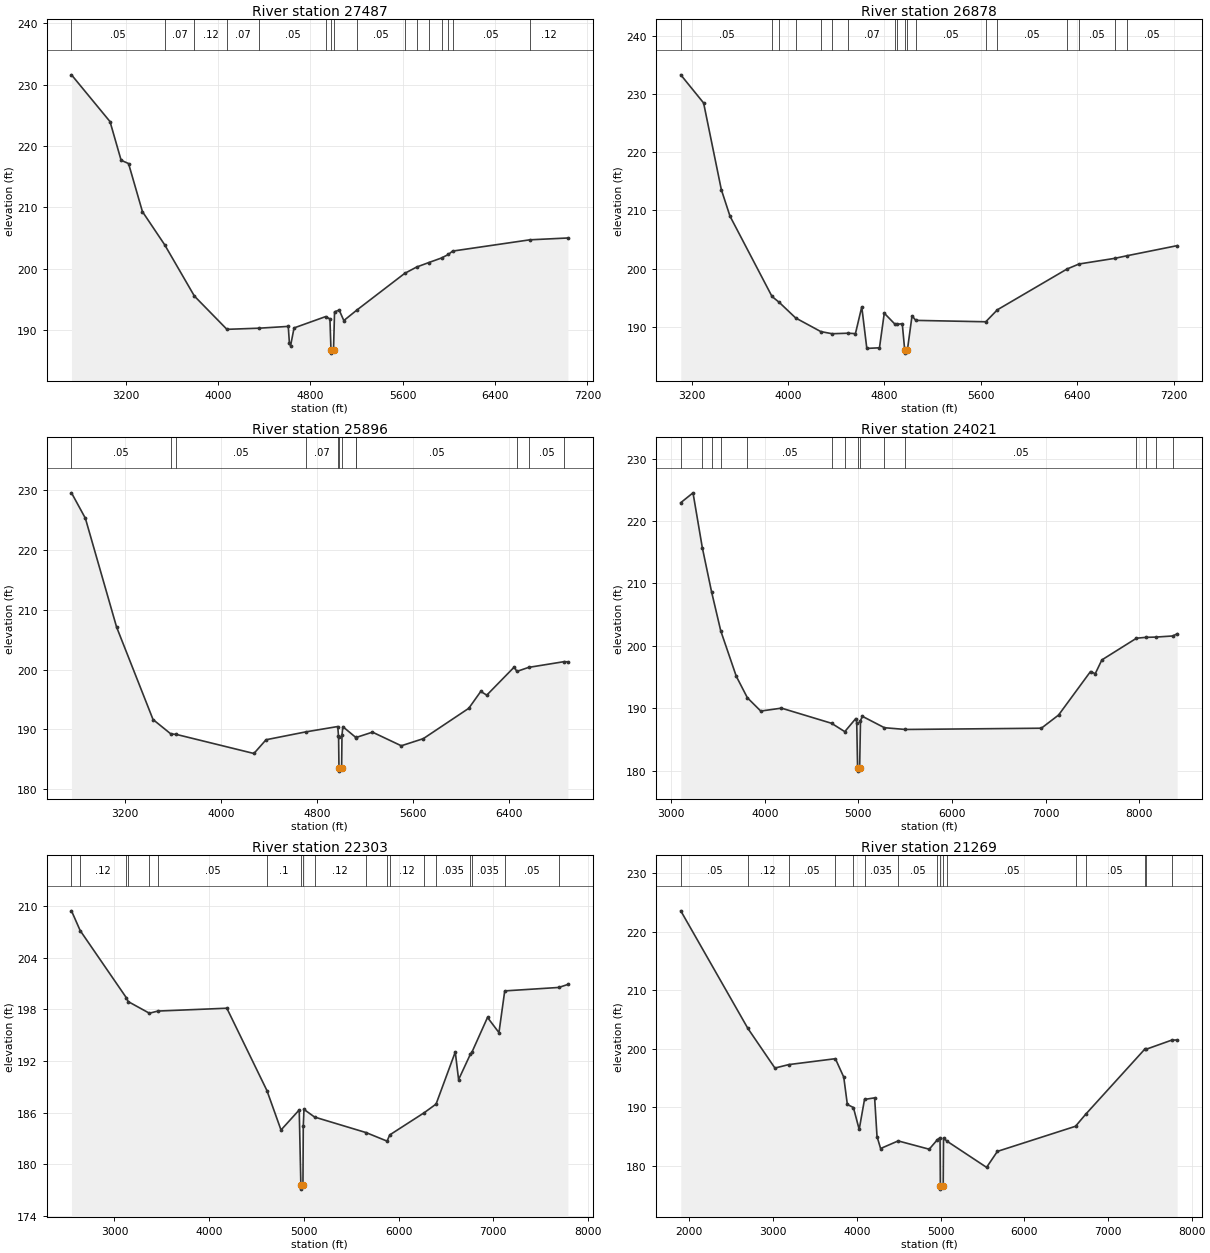
Type RM Length L Ch R = 1 ,27487   ,609,609,609
BEGIN DESCRIPTION:
X18696
END DESCRIPTION:
XS GIS Cut Line= 3
        2518538.     13619007.93      2515920.86     13619203.24
      2515347.93     13620778.78
#Sta/Elev= 30
  2730.3   231.6  3064.2  223.97  3160.3  217.67  3224.7  217.13    3345  209.29
  3537.4  203.89  3795.4  195.51    4077  190.09  4357.8  190.28  4608.5  190.57
  4618.5  187.82  4628.6  187.42  4658.7  190.32  4932.5  192.17  4969.5  191.79
  4978.7  186.71  4979.2  186.21  5000.5  186.71  5009.6  192.94  5049.7  193.24
  5089.8  191.52  5207.3   193.3  5616.8  199.21  5720.6  200.25  5824.4  200.97
  5937.9  201.74  5996.3  202.31  6031.9  202.85    6701  204.69  7031.2  204.99
#Mann= 16 ,-1 , 0
  2730.3     .05       0  3537.4     .07       0  3795.4     .12       0
    4077     .07       0  4357.8     .05       0  4932.5      .1       0
  4978.7     .05       0  5000.5      .1       0  5207.3     .05       0
  5616.8    .035       0  5720.6     .05       0  5824.4     .12       0
  5937.9     .05       0  5996.3     .12       0  6031.9     .05       0
    6701     .12       0
Bank Sta=4978.7,5000.5
XS Rating Curve= 0 ,0
Exp/Cntr=0.3,0.1

Type RM Length L Ch R = 1 ,26878   ,982,982,982
BEGIN DESCRIPTION:
X18697
END DESCRIPTION:
XS GIS Cut Line= 3
      2518225.58     13618044.38      2515621.38     13618877.72
      2515400.02     13620244.93
#Sta/Elev= 30
    3110  233.36  3299.6  228.51  3446.6  213.59  3518.5  209.02  3867.1  195.19
  3927.9  194.16  4063.8  191.48  4272.3  189.14    4366  188.77  4496.3  188.86
  4559.5  188.79    4612   193.4    4654  186.24    4759  186.35  4798.8  192.31
  4888.7  190.39  4904.6  190.39    4948   190.5  4968.6  185.93  4969.1  185.43
  4990.4  185.93  5029.1  191.85  5060.1  191.07    5641  190.83  5737.1  192.89
  6315.6  199.92    6415  200.78    6713  201.76  6812.4   202.2  7229.3  203.94
#Mann= 18 ,-1 , 0
    3110     .05       0  3867.1     .07       0  3927.9     .05       0
  4063.8     .12       0  4272.3     .07       0    4366     .05       0
  4496.3     .07       0  4888.7     .05       0  4904.6     .07       0
  4968.6     .05       0  4990.4     .07       0  5060.1     .05       0
    5641     .12       0  5737.1     .05       0  6315.6    .035       0
    6415     .05       0    6713     .12       0  6812.4     .05       0
Bank Sta=4968.6,4990.4
XS Rating Curve= 0 ,0
Exp/Cntr=0.3,0.1

Type RM Length L Ch R = 1 ,25896   ,1875,1875,1875
BEGIN DESCRIPTION:
X18698
END DESCRIPTION:
XS GIS Cut Line= 4
      2517926.07     13617640.74      2515803.67     13618005.33
      2515230.75     13618591.26      2515282.77     13619761.54
#Sta/Elev= 30
  2751.2  229.57    2867  225.32  3127.7  207.12  3432.1  191.65  3580.8  189.24
    3627  189.16  4274.3  185.97  4375.7  188.27  4706.2  189.58  4974.2  190.48
  4980.3  188.95  4981.3   188.7  4984.5  183.52    4985  183.02  5006.4  183.52
  5009.6  189.01  5016.6  190.46  5125.2  188.65  5126.1  188.64  5264.2  189.54
  5504.7  187.26  5688.4  188.45  6068.2  193.53  6168.3  196.35  6218.4  195.73
  6448.6  200.45  6468.7  199.69  6567.4  200.37  6863.7  201.33  6895.6   201.3
#Mann= 12 ,-1 , 0
  2751.2     .05       0  3580.8    .035       0    3627     .05       0
  4706.2     .07       0  4980.3     .12       0  4984.5     .05       0
  5006.4     .12       0  5125.2     .12       0  5126.1     .05       0
  6468.7    .035       0  6567.4     .05       0  6863.7     .12       0
Bank Sta=4984.5,5006.4
XS Rating Curve= 0 ,0
Exp/Cntr=0.3,0.1

Type RM Length L Ch R = 1 ,24021   ,1718,1718,1718
BEGIN DESCRIPTION:
X18699
END DESCRIPTION:
XS GIS Cut Line= 4
      2517965.11     13617445.43      2515491.17     13617211.05
      2514918.25     13617757.93      2515191.47     13619761.54
#Sta/Elev= 30
  3103.5  222.95  3234.2  224.53  3333.3  215.76  3431.9  208.69  3530.4   202.4
  3696.3  195.11  3814.8  191.67  3957.4  189.54  4178.4  190.01  4713.1  187.58
  4854.5  186.24  4971.9  188.34    4982  187.68  4991.1  180.41  4991.6  179.91
    5013  180.41  5022.2  188.02  5042.3   188.7  5277.6  186.87  5501.6  186.59
  6952.9  186.79  7136.6   188.9  7477.7  195.88  7528.1  195.53  7598.8  197.74
  7968.5  201.22  8068.3  201.36  8173.3   201.4    8356  201.58  8402.7  201.93
#Mann= 15 ,-1 , 0
  3103.5     .07       0  3333.3     .12       0  3431.9     .07       0
  3530.4     .12       0  3814.8     .05       0  4713.1    .035       0
  4854.5      .1       0  4991.1     .05       0    5013      .1       0
  5277.6     .07       0  5501.6     .05       0  7968.5    .035       0
  8068.3     .05       0  8173.3     .12       0    8356     .05       0
Bank Sta=4991.1,5013
XS Rating Curve= 0 ,0
Exp/Cntr=0.3,0.1

Type RM Length L Ch R = 1 ,22303   ,1034,1034,1034
BEGIN DESCRIPTION:
CUERO CREEK 13.0
END DESCRIPTION:
XS GIS Cut Line= 3
      2516298.45     13614658.99      2513967.73     13617731.89
      2513069.67     13618786.13
#Sta/Elev= 30
  2545.9  209.42  2637.7  207.13  3126.8  199.31  3144.6  198.89  3368.3  197.54
  3457.9  197.79  4186.5  198.12  4609.5  188.57  4758.4  183.99  4950.7  186.32
    4968  177.63  4968.5  177.13    4990  177.63  4993.5  184.41  5000.9  186.38
  5113.4  185.49  5656.7  183.69  5878.3   182.7  5906.5  183.42  6269.7  185.99
  6395.8     187  6598.5  193.04  6633.6  189.84  6757.4  192.77  6773.2  192.99
  6938.9  197.05  7059.7  195.29  7120.8  200.13  7692.1  200.53  7787.6  200.88
#Mann= 19 ,-1 , 0
  2545.9     .07       0  2637.7     .12       0  3126.8     .07       0
  3144.6     .05       0  3368.3     .07       0  3457.9     .05       0
  4609.5      .1       0    4968     .05       0    4990      .1       0
  5113.4     .12       0  5656.7      .1       0  5878.3    .035       0
  5906.5     .12       0  6269.7     .05       0  6395.8    .035       0
  6757.4    .063       0  6773.2    .035       0  7120.8     .05       0
  7692.1    .035       0
Bank Sta=4968,4990
XS Rating Curve= 0 ,0
Exp/Cntr=0.3,0.1

Type RM Length L Ch R = 1 ,21269   ,1278,1278,1278
BEGIN DESCRIPTION:
CUERO CREEK 12.0
END DESCRIPTION:
XS GIS Cut Line= 3
      2516311.48     13614086.06      2513993.78     13616065.22
      2512261.99     13618369.93
#Sta/Elev= 30
  1896.5   223.6  2698.1  203.51  3021.4  196.73  3185.9  197.32  3743.7  198.33
  3843.8  195.18  3886.6  190.51  3959.2  189.98  4028.2  186.24  4091.8  191.37
  4212.6  191.64  4241.2  185.03    4284  182.98  4493.9  184.28  4864.8  182.86
  4962.9   184.5    4994  184.83  4998.1  176.54  4998.7  176.04  5031.9  176.54
  5035.8  184.76  5080.7   184.2  5550.2  179.76  5679.4  182.49  6612.6  186.78
  6733.3  188.82  7440.1  199.96  7455.7  199.94  7763.5  201.51  7827.1  201.53
#Mann= 16 ,-1 , 0
  1896.5     .05       0  2698.1     .12       0  3185.9     .05       0
  3743.7    .035       0  3959.2    .063       0  4091.8    .035       0
  4493.9     .05       0  4962.9      .1       0  4998.1     .05       0
  5031.9      .1       0  5080.7     .05       0  6612.6    .035       0
  6733.3     .05       0  7440.1    .035       0  7455.7     .05       0
  7763.5     .12       0
Bank Sta=4998.1,5031.9
XS Rating Curve= 0 ,0
Exp/Cntr=0.3,0.1

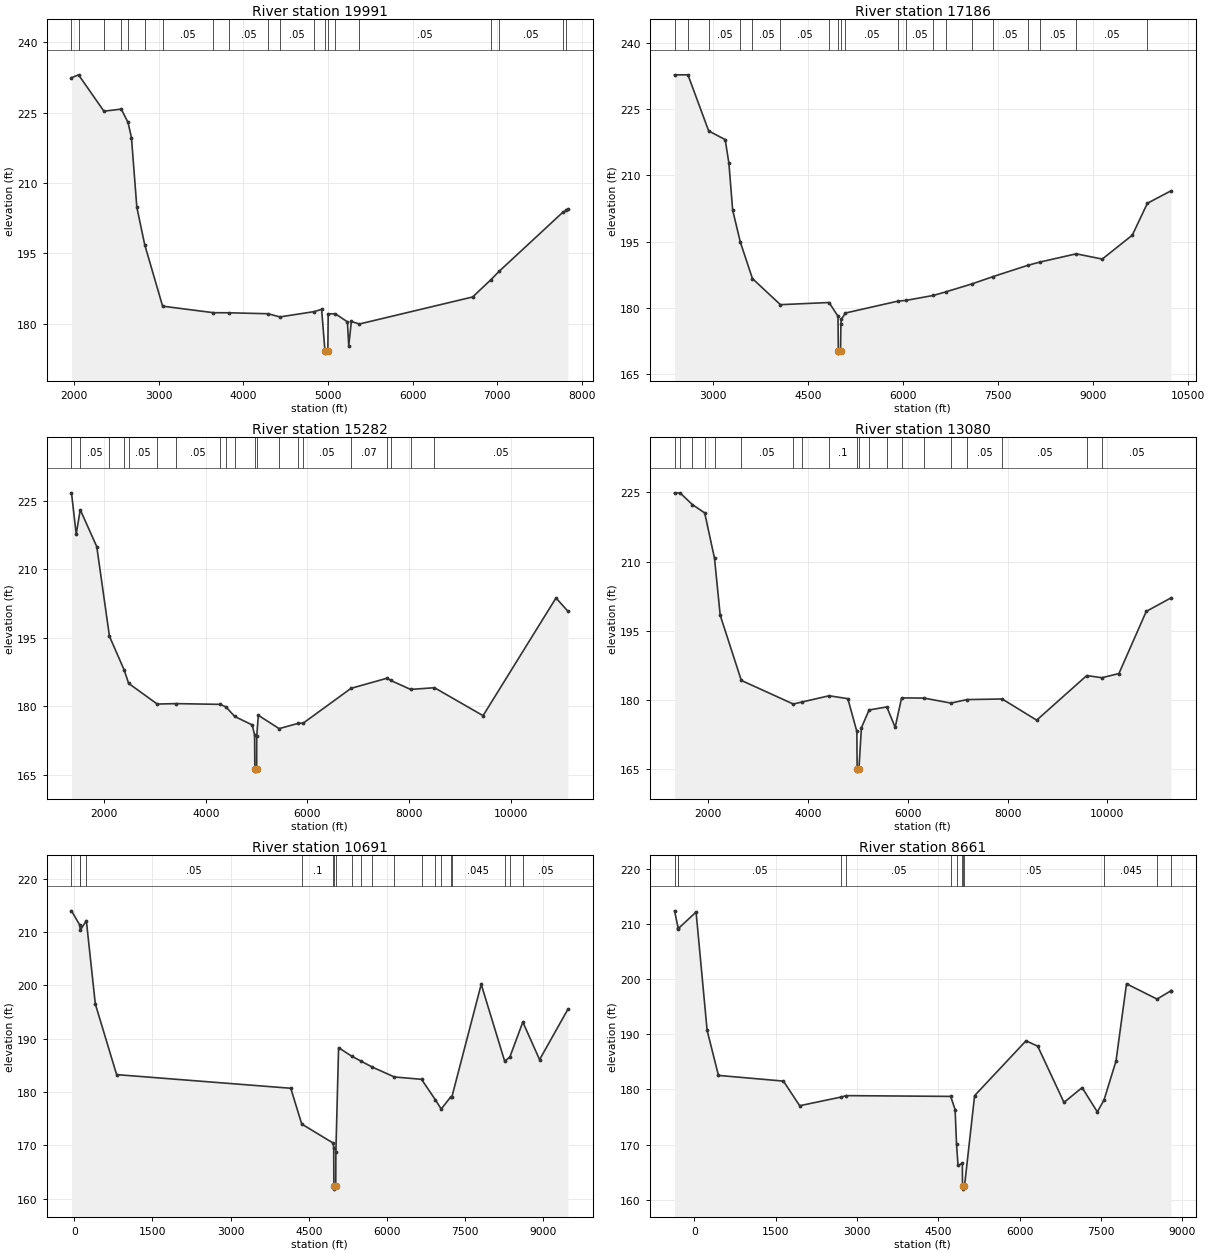
Type RM Length L Ch R = 1 ,19991   ,2805,2805,2805
BEGIN DESCRIPTION:
CUERO CREEK 11.0
END DESCRIPTION:
XS GIS Cut Line= 3
      2515204.68     13613291.81        2512887.     13615583.45
      2512014.62     13618044.37
#Sta/Elev= 30
  1966.2  232.41  2049.7  233.04  2349.5   225.3  2554.7  225.74  2634.4  222.92
  2675.3  219.69    2739  204.83    2832  196.88  3043.6  183.78  3644.5  182.39
    3826  182.37  4288.3  182.17  4431.2  181.49  4839.3  182.63    4924  183.11
  4963.4  174.28  4964.1  173.78  4997.6  174.28  5001.8  182.14  5086.1  182.16
    5229  180.45  5244.8  175.34  5275.7  180.52  5370.2  179.98  6710.1  185.74
  6922.6  189.36  7026.1  191.25  7778.3  203.81  7816.9  204.18  7836.5  204.48
#Mann= 20 ,-1 , 0
  1966.2    .035       0  2049.7     .05       0  2349.5     .07       0
  2554.7     .05       0  2634.4     .07       0    2832     .12       0
  3043.6     .05       0  3644.5     .07       0    3826     .05       0
  4288.3    .035       0  4431.2     .05       0  4839.3      .1       0
  4963.4     .05       0  4997.6      .1       0  5086.1     .12       0
  5370.2     .05       0  6922.6    .035       0  7026.1     .05       0
  7778.3    .035       0  7816.9     .05       0
Bank Sta=4963.4,4997.6
XS Rating Curve= 0 ,0
Exp/Cntr=0.3,0.1

Type RM Length L Ch R = 1 ,17186   ,1904,1904,1904
BEGIN DESCRIPTION:
X18705
END DESCRIPTION:
XS GIS Cut Line= 3
      2515476.83     13612714.97      2512226.85     13614569.13
      2511685.29     13618630.79
#Sta/Elev= 30
  2388.8  232.85  2600.4  232.85    2928  220.11  3188.5  218.15  3247.6  212.74
  3306.6  202.13  3428.3  194.85  3618.7   186.6  4060.7  180.68  4829.5  181.17
  4969.8  178.04  4975.4  170.18  4976.1  169.68  5010.3  170.18  5015.9  176.39
    5022  177.32  5086.6  178.78    5921   181.5  6036.1  181.63  6477.5  182.78
  6675.5   183.6    7093  185.43  7417.9  187.05  7962.8  189.59  8160.9  190.36
  8731.6  192.22  9142.8  191.03  9616.9  196.45  9855.6   203.7 10228.1  206.52
#Mann= 20 ,-1 , 0
  2388.8    .035       0  2600.4     .05       0    2928     .05       0
  3428.3     .07       0  3618.7     .05       0  4060.7     .05       0
  4829.5      .1       0  4975.4     .05       0  5010.3      .1       0
  5086.6     .05       0    5921    .035       0  6036.1     .05       0
  6477.5    .035       0  6675.5     .05       0    7093     .07       0
  7417.9     .05       0  7962.8    .035       0  8160.9     .05       0
  8731.6     .05       0  9855.6     .05       0
Bank Sta=4975.4,5010.3
XS Rating Curve= 0 ,0
Exp/Cntr=0.3,0.1

Type RM Length L Ch R = 1 ,15282   ,2202,2202,2202
BEGIN DESCRIPTION:
X18704
END DESCRIPTION:
XS GIS Cut Line= 3
      2515393.51      13612485.8      2511560.18     13613735.79
      2506081.05     13615464.95
#Sta/Elev= 30
  1353.4   226.8  1446.5  217.74    1526  223.08  1851.1     215  2101.3  195.32
  2393.8  187.86  2478.4     185  3041.7  180.46  3414.6  180.55  4282.5  180.39
  4397.7  179.82  4567.1  177.74  4913.7  175.87  4959.6  173.66  4964.9  166.24
  4965.7  165.74  5000.6  166.24  5001.7  173.39  5033.2  177.99  5443.1  175.07
  5818.9  176.22  5917.7  176.27  6859.8  183.91  7567.7  186.12  7642.1  185.63
  8031.7  183.67  8502.7  184.04  9459.5  177.91 10896.1  203.73 11130.9  200.82
#Mann= 20 ,-1 , 0
  1353.4     .07       0    1526     .05       0  2101.3    .035       0
  2393.8     .07       0  2478.4     .05       0  3041.7     .07       0
  3414.6     .05       0  4282.5     .12       0  4397.7     .05       0
  4567.1      .1       0  4964.9     .05       0  5000.6      .1       0
  5443.1     .05       0  5818.9    .035       0  5917.7     .05       0
  6859.8     .07       0  7567.7     .07       0  7642.1     .12       0
  8031.7     .07       0  8502.7     .05       0
Bank Sta=4964.9,5000.6
XS Rating Curve= 0 ,0
Exp/Cntr=0.3,0.1

Type RM Length L Ch R = 1 ,13080   ,2389,2389,2389
BEGIN DESCRIPTION:
X18703
END DESCRIPTION:
XS GIS Cut Line= 3
      2515143.56     13612131.64      2513289.35     13611589.96
      2505935.14     13614798.31
#Sta/Elev= 30
  1321.8  224.92  1436.6  224.87  1679.6  222.37  1926.1  220.57  2123.1  210.73
  2237.1  198.39  2660.5  184.25    3702  179.13  3882.6  179.58  4421.4  180.92
  4796.6  180.29  4977.9  173.18  4983.4  165.08  4984.3  164.58  5019.2  165.08
  5069.4     174  5223.3  177.84  5578.5   178.5  5745.8  174.07  5875.3  180.46
  6321.7  180.42  6864.7  179.33  7182.7  180.09  7892.6  180.22  8584.1  175.63
  9587.4   185.3  9891.1  184.83 10233.1  185.74   10781  199.21 11277.1  202.14
#Mann= 20 ,-1 , 0
  1321.8    .035       0  1436.6     .05       0  1679.6    .035       0
  1926.1     .07       0  2123.1     .05       0  2660.5     .05       0
    3702    .035       0  3882.6     .05       0  4421.4      .1       0
  4983.4     .05       0  5019.2      .1       0  5223.3    .035       0
  5578.5     .05       0  5875.3     .12       0  6321.7     .05       0
  6864.7    .035       0  7182.7     .05       0  7892.6     .05       0
  9587.4     .07       0  9891.1     .05       0
Bank Sta=4983.4,5019.2
XS Rating Curve= 0 ,0
Exp/Cntr=0.3,0.1

Type RM Length L Ch R = 1 ,10691   ,2030,2030,2030
BEGIN DESCRIPTION:
X18702
END DESCRIPTION:
XS GIS Cut Line= 3
      2514414.33     13611777.46      2512081.01     13610860.79
      2505310.22     13612714.95
#Sta/Elev= 30
   -53.8  213.99   101.2  211.39   116.7  210.38   231.5  212.15   403.1  196.53
   812.4  183.25  4154.2  180.69  4365.1  173.97    4964  170.43  4978.8  169.56
  4981.6  162.26  4982.4  161.76  5017.6  162.26  5019.9  168.73  5072.1  188.31
  5325.1   186.7  5499.4   185.8  5719.7  184.66  6142.8  182.81  6663.9  182.37
  6931.3   178.5  7041.3  176.79  7221.4  179.03  7246.9   179.1  7809.3  200.21
  8259.9  185.75  8358.9  186.56  8607.9  193.12  8929.3  186.06  9473.2  195.53
#Mann= 20 ,-1 , 0
   -53.8     .07       0   101.2     .05       0   116.7     .07       0
   231.5     .05       0  4365.1      .1       0    4964     .12       0
  4981.6     .05       0  5017.6     .12       0  5325.1    .035       0
  5499.4     .12       0  5719.7      .1       0  6142.8     .12       0
  6663.9     .07       0  6931.3     .12       0  7041.3    .035       0
  7221.4     .12       0  7246.9    .045       0  8259.9     .05       0
  8358.9    .035       0  8607.9     .05       0
Bank Sta=4981.6,5017.6
XS Rating Curve= 0 ,0
Exp/Cntr=0.3,0.1

Type RM Length L Ch R = 1 ,8661    ,2506,2506,2506
BEGIN DESCRIPTION:
X18701
END DESCRIPTION:
XS GIS Cut Line= 3
      2514289.37     13611631.64      2510268.51     13609694.13
      2505914.35     13611444.13
#Sta/Elev= 30
  -363.2  212.34  -294.3  209.13  -292.1  209.15      34  212.12   237.5   190.7
   446.6  182.54    1645  181.51  1944.6  177.05  2711.6  178.63  2803.8  178.88
  4730.3  178.74  4811.4  176.33  4837.6  170.08  4865.2  166.23  4944.8  166.63
  4948.1  162.45  4948.9  161.95  4984.2  162.45  5170.9  178.88  6119.3  188.81
  6334.8  187.83  6819.3  177.65  7153.9  180.33  7434.1  175.93  7557.2  178.07
    7779  185.15  7972.5  199.13  8535.4  196.36  8787.5  197.84  8792.8  197.91
#Mann= 13 ,-1 , 0
  -363.2     .05       0  -294.3     .07       0  -292.1     .05       0
  2711.6    .035       0  2803.8     .05       0  4730.3     .12       0
  4837.6     .07       0  4944.8     .05       0  4948.1     .05       0
  4984.2     .05       0  7557.2    .045       0  8535.4     .05       0
  8787.5     .07       0
Bank Sta=4948.1,4984.2
XS Rating Curve= 0 ,0
Exp/Cntr=0.3,0.1

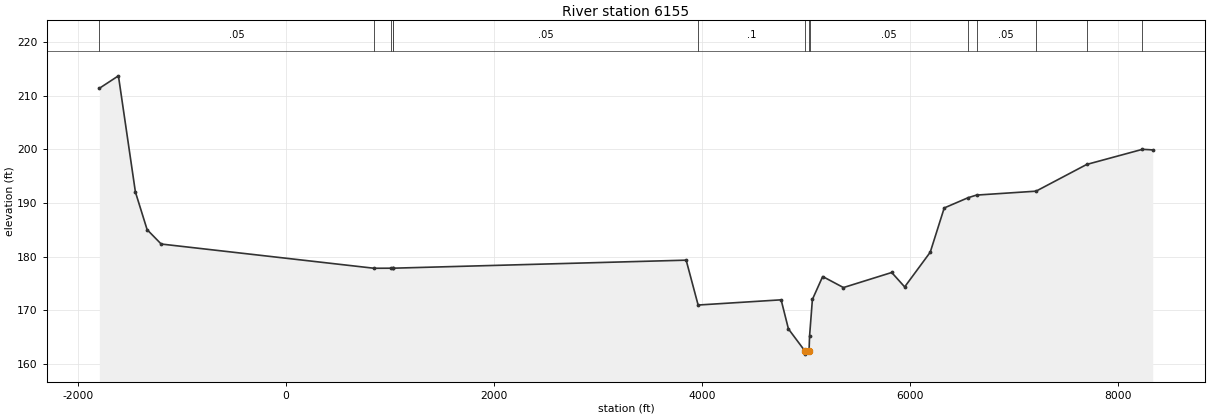
Type RM Length L Ch R = 1 ,6155    ,0,0,0
BEGIN DESCRIPTION:
X18700
END DESCRIPTION:
XS GIS Cut Line= 4
      2514080.97     13611402.44      2509081.01     13608964.96
      2506976.85     13609694.13      2505519.26     13611526.53
#Sta/Elev= 30
 -1793.7   211.4 -1610.1  213.73 -1446.8  192.05 -1334.1  185.03 -1198.9  182.35
   848.5  177.83  1007.4  177.84  1026.3  177.84  1027.2  177.84  3849.9  179.34
    3965  170.97  4763.1  171.94  4833.5  166.51  4995.3  162.31  4996.1  161.81
  5031.5  162.31  5036.8  165.18  5063.9  172.01  5162.7  176.29  5362.6  174.23
  5826.7  177.04  5951.3  174.35  6197.1  180.82  6331.7  189.08  6562.3     191
  6642.3  191.48  7214.6  192.21  7702.4   197.2  8238.5  200.02  8337.1  199.91
#Mann= 14 ,-1 , 0
 -1793.7     .05       0   848.5    .035       0  1007.4     .05       0
  1026.3    .035       0  1027.2     .05       0    3965      .1       0
  4995.3     .05       0  5031.5      .1       0  5036.8     .05       0
  6562.3     .07       0  6642.3     .05       0  7214.6    .035       0
  7702.4     .07       0  8238.5     .05       0
Bank Sta=4995.3,5031.5
XS Rating Curve= 0 ,0
Exp/Cntr=0.3,0.1

Chan Stop Cuts=-1
Use User Specified Reach Order=0
Composite Channel Slope=5