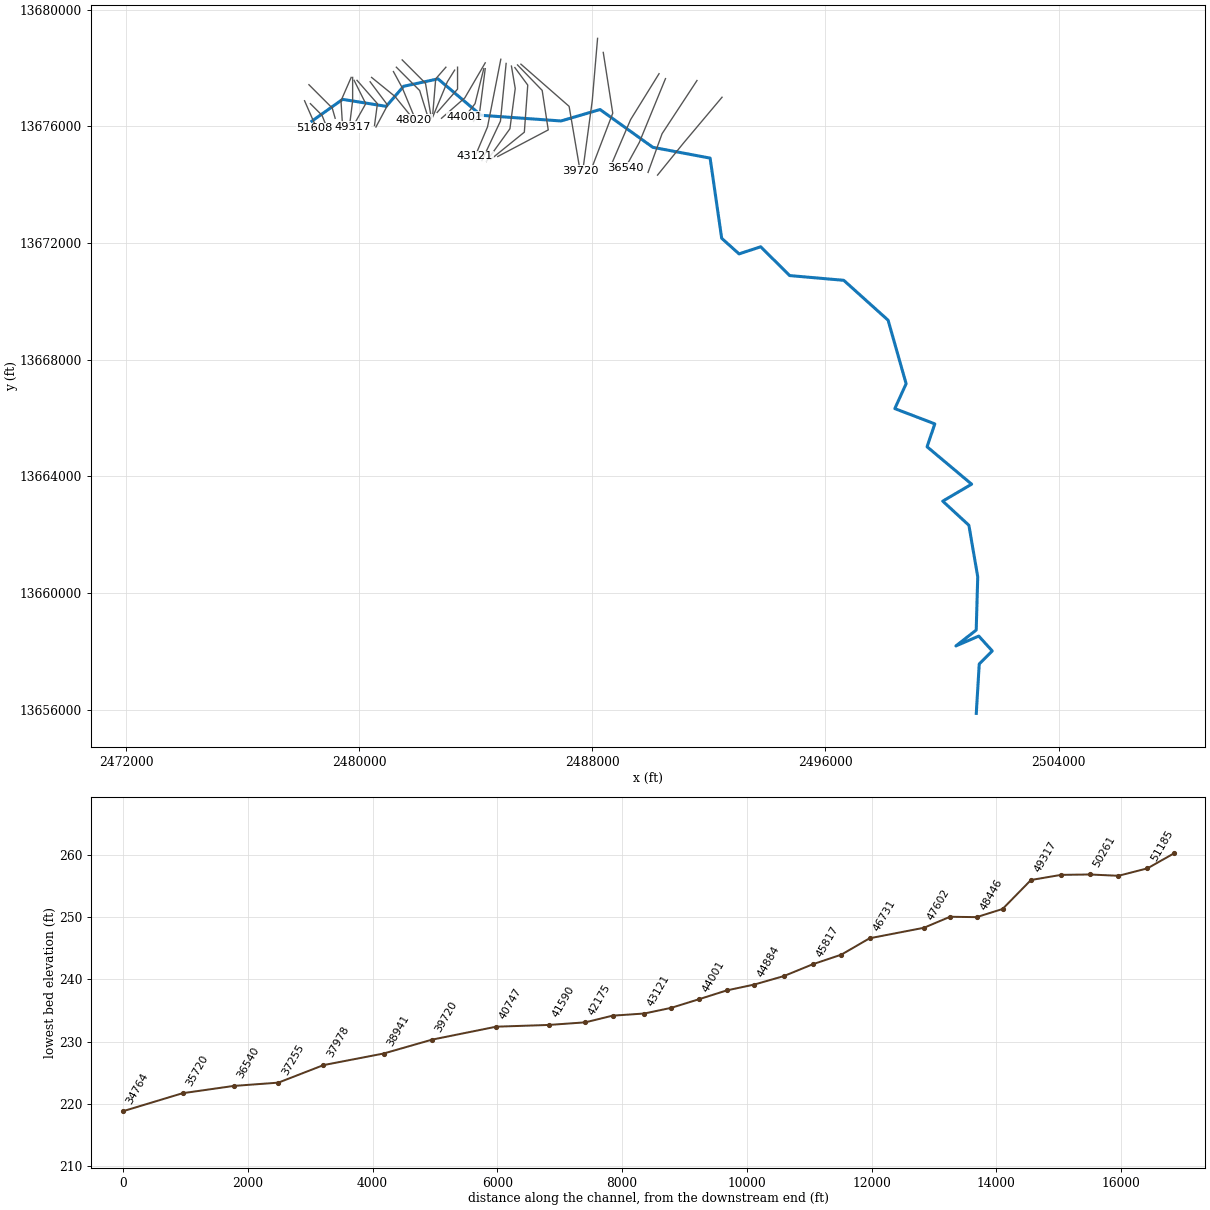
--- DENTON CREEK.prj (project) ---

Proj Title=DENTON CREEK Base Level Engineering
Current Plan=p01
Default Exp/Contr=0.3,0.1
English Units
Geom File=g01
Flow File=f01
Plan File=p01
Y Axis Title=Elevation
X Axis Title(PF)=Main Channel Distance
X Axis Title(XS)=Station
BEGIN DESCRIPTION:
DENTON CREEK
END DESCRIPTION:
DSS Export Rating Curves= 0
DSS Export Rating Curve Sorted= 0
DSS Export Volume Flow Curves= 0
DXF OffsetX= 0
DXF OffsetY= 0
DXF ScaleX= 1
DXF ScaleY= 10

--- DENTON CREEK.p01 (plan) ---

Plan Title=Multiple Run
Short Identifier=Multiple
Geom File=g01
Flow File=f01
Subcritical Flow
K Sum by GR= 0
Std Step Tol= 0.01
Critical Tol= 0.01
Num of Std Step Trials= 20
Max Error Tol= 0.3
Flow Tol Ratio= 0.001
Split Flow NTrial= 30
Split Flow Tol= 0.02
Split Flow Ratio= 0.02
Log Output Level= 0
Friction Slope Method= 1
Unsteady Friction Slope Method= 2
Unsteady Bridges Friction Slope Method= 1
Parabolic Critical Depth
Global Vel Dist=  1 , 1 , 1
Global Log Level= 0
CheckData=True
Encroach Param= -1, 0, 0, 0
BEGIN DESCRIPTION:
Multiple Run
END DESCRIPTION:

--- DENTON CREEK.f01 (steady flow) ---

Flow Title=Multiple
Number of Profiles=7
Profile Names=10-year,25-year,50-year,1pct_min,100-year,1pct_plu,500-year
River Rch & RM= DENTON CREEK,Reach-1,51608
     771    1249    1683    1097    2189    4368    3669
River Rch & RM= DENTON CREEK,Reach-1,49800
     829    1343    1807    1177    2348    4685    3925
River Rch & RM= DENTON CREEK,Reach-1,48020
    1206    1993    2720    1793    3578    7138    6133
River Rch & RM= DENTON CREEK,Reach-1,44884
    1190    1948    2640    1728    3447    6878    5822
River Rch & RM= DENTON CREEK,Reach-1,39720
    2053    3458    4779    3184    6352   12674   11125
River Rch & RM= DENTON CREEK,Reach-1,37255
    3347    5658    7836    5219   10414   20778   18229
River Rch & RM= DENTON CREEK,Reach-1,27192
    3765    6360    8803    5857   11686   23317   20409
River Rch & RM= DENTON CREEK,Reach-1,16208
    4096    6918    9574    6367   12705   25349   22168
Boundary for River Rch & Prof#=DENTON CREEK,Reach-1,1
Up Type=0
Dn Type=3
Dn Slope=0.005
Boundary for River Rch & Prof#=DENTON CREEK,Reach-1,2
Up Type=0
Dn Type=3
Dn Slope=0.005
Boundary for River Rch & Prof#=DENTON CREEK,Reach-1,3
Up Type=0
Dn Type=3
Dn Slope=0.005
Boundary for River Rch & Prof#=DENTON CREEK,Reach-1,4
Up Type=0
Dn Type=3
Dn Slope=0.005
Boundary for River Rch & Prof#=DENTON CREEK,Reach-1,5
Up Type=0
Dn Type=3
Dn Slope=0.005
Boundary for River Rch & Prof#=DENTON CREEK,Reach-1,6
Up Type=0
Dn Type=3
Dn Slope=0.005
Boundary for River Rch & Prof#=DENTON CREEK,Reach-1,7
Up Type=0
Dn Type=3
Dn Slope=0.005

--- DENTON CREEK.g01 (geometry) ---

Geom Title=Existing Conditions
Program Version=4.10

River Reach=DENTON CREEK    ,Reach-1
Reach XY= 30
        2478375.       13676175.      2479431.12     13676923.18
      2480928.31     13676683.07      2481522.71     13677369.94
      2482704.79     13677624.96      2484180.89     13676376.96
      2486924.91     13676182.29      2488264.53     13676574.47
      2490076.72     13675278.34      2492041.68     13674908.36
      2492438.49     13672161.44      2493034.62     13671625.68
      2493777.71      13671869.6       2494771.6     13670882.41
      2496627.71     13670719.72      2498148.98     13669352.49
      2498767.92       13667175.      2498380.06      13666322.7
      2499752.35     13665799.03      2499485.96       13665015.
      2501016.05     13663731.66      2500024.37     13663149.92
      2500921.46     13662323.54      2501225.21     13660554.95
      2501172.77      13658730.9      2500476.16     13658186.99
      2501259.91     13658524.82      2501724.07     13658014.52
      2501276.98     13657569.33        2501175.       13655875.

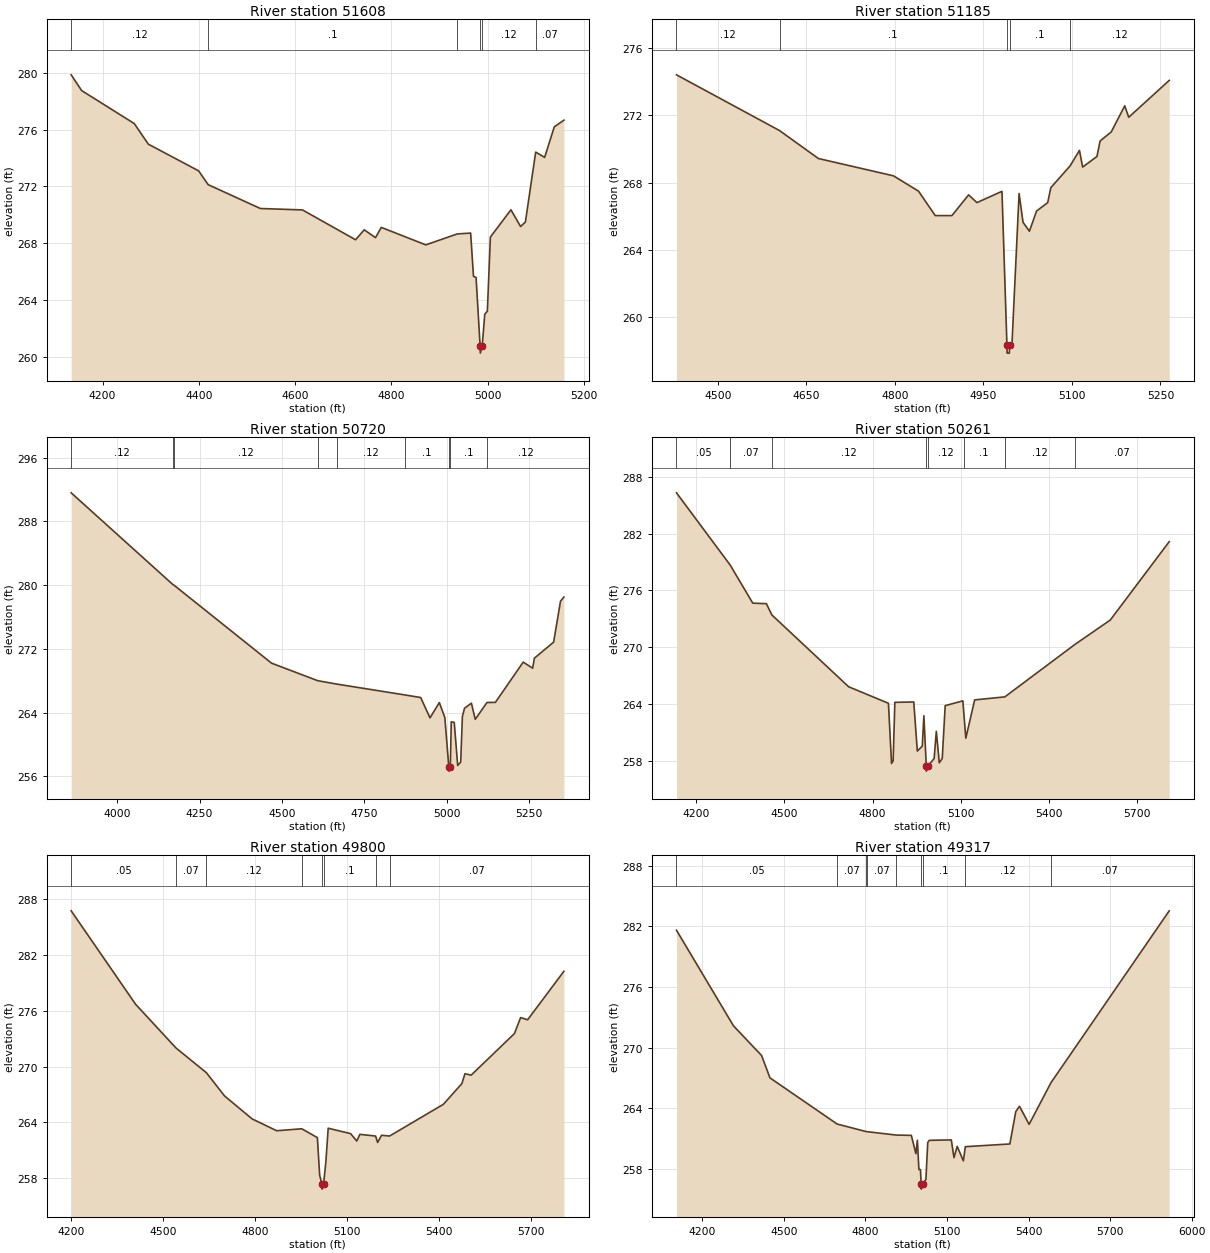
Type RM Length L Ch R = 1 ,51608   ,423,423,423
BEGIN DESCRIPTION:
DENTON CREEK 54.0
END DESCRIPTION:
XS GIS Cut Line= 3
        2478125.     13676874.99        2478475.       13676075.
        2478475.       13675925.
#Sta/Elev= 30
  4134.9  279.86  4156.7  278.75  4265.9  276.43  4295.1  274.98  4399.6   273.1
  4419.3  272.13  4527.8  270.45  4615.2  270.35  4725.5  268.25  4743.4  268.95
  4766.8   268.4  4778.9  269.12  4871.3  267.89  4936.6  268.66  4964.4  268.72
  4970.3  265.68  4975.7  265.59  4984.1  260.77  4984.4  260.27  4988.4  260.77
  4993.7     263  4999.1  263.22  5005.4  268.44  5048.1  270.36  5068.1  269.18
  5078.1   269.5  5099.5  274.42  5118.1  274.05  5138.1   276.2  5158.1  276.67
#Mann= 6 ,-1 , 0
  4134.9     .12       0  4419.3      .1       0  4936.6     .12       0
  4984.1     .05       0  4988.4     .12       0  5099.5     .07       0
Bank Sta=4984.1,4988.4
XS Rating Curve= 0 ,0
Exp/Cntr=0.3,0.1

Type RM Length L Ch R = 1 ,51185   ,465,465,465
BEGIN DESCRIPTION:
DENTON CREEK 53.0
END DESCRIPTION:
XS GIS Cut Line= 3
        2478325.       13676775.        2478725.       13676375.
      2478824.98     13676125.04
#Sta/Elev= 30
    4430   274.4  4604.6  271.09  4670.4  269.43  4797.7   268.4  4840.1  267.49
  4868.4  266.04  4896.7  266.04    4925  267.27  4939.1  266.81  4981.5  267.48
  4989.9  258.37  4990.2  257.87    4994  257.87  4994.3  258.37  4998.4  258.37
  5010.5  267.35  5017.2  265.64    5028  265.11  5040.1  266.31    5059  266.81
  5064.3   267.7  5096.9  268.99  5112.8  269.91  5118.2  268.92  5142.4  269.55
  5147.8  270.47  5166.7  271.01  5189.5  272.56  5196.3  271.88  5264.9  274.07
#Mann= 5 ,-1 , 0
    4430     .12       0  4604.6      .1       0  4989.9     .05       0
  4994.3      .1       0  5096.9     .12       0
Bank Sta=4989.9,4994.3
XS Rating Curve= 0 ,0
Exp/Cntr=0.3,0.1

Type RM Length L Ch R = 1 ,50720   ,459,459,459
BEGIN DESCRIPTION:
DENTON CREEK 52.0
END DESCRIPTION:
XS GIS Cut Line= 3
      2478274.98     13677425.02        2479075.       13676625.
        2479175.     13676275.01
#Sta/Elev= 30
  3860.2  291.57  4168.5  280.08  4172.2  279.99  4468.3  270.21  4608.5  268.01
  4665.6  267.59  4872.1  266.23  4920.9   265.9  4949.2  263.35  4977.5  265.27
  4994.2   263.4  5006.3  257.17  5006.6  256.67  5010.8  257.17  5013.7  262.86
  5022.8  262.78  5033.2  257.38  5042.3   257.8  5047.5  263.53    5054  264.56
  5074.8  265.19  5086.5  263.17  5122.1  265.28  5147.6  265.29  5232.1  270.34
  5260.7  269.58  5265.9  270.83  5324.4  272.85  5345.2  277.97  5355.6   278.5
#Mann= 9 ,-1 , 0
  3860.2     .12       0  4168.5     .07       0  4172.2     .12       0
  4608.5     .07       0  4665.6     .12       0  4872.1      .1       0
  5006.3     .05       0  5010.8      .1       0  5122.1     .12       0
Bank Sta=5006.3,5010.8
XS Rating Curve= 0 ,0
Exp/Cntr=0.3,0.1

Type RM Length L Ch R = 1 ,50261   ,461,461,461
BEGIN DESCRIPTION:
DENTON CREEK 51.0
END DESCRIPTION:
XS GIS Cut Line= 3
        2479725.       13677675.        2479375.       13676875.
        2479425.     13676074.97
#Sta/Elev= 30
  4133.4   286.3    4316  278.66  4392.6  274.64    4439  274.58  4457.6  273.39
  4718.5   265.8  4853.8  264.05  4864.3  257.69  4869.8  257.97  4875.6  264.15
  4939.9  264.19    4952     259  4968.8  259.52  4974.3  262.73  4982.5  257.38
  4982.8  256.88    4987  257.38  5009.1  258.21  5016.6  261.09  5026.6  257.76
  5036.7  258.22  5046.7   263.8  5106.8  264.31  5109.2  263.36  5116.8  260.36
  5146.9  264.41  5249.5  264.73    5488  270.28  5607.8  272.85  5808.2  281.14
#Mann= 8 ,-1 , 0
  4133.4     .05       0    4316     .07       0  4457.6     .12       0
  4982.5     .05       0    4987     .12       0  5109.2      .1       0
  5249.5     .12       0    5488     .07       0
Bank Sta=4982.5,4987
XS Rating Curve= 0 ,0
Exp/Cntr=0.3,0.1

Type RM Length L Ch R = 1 ,49800   ,483,483,483
BEGIN DESCRIPTION:
DENTON CREEK 50.0
END DESCRIPTION:
XS GIS Cut Line= 3
        2479775.     13677674.97        2479775.       13676875.
        2479675.     13676074.99
#Sta/Elev= 30
  4200.5  286.75  4410.5   276.7  4542.5  271.99    4641  269.35  4700.5  266.84
  4790.5  264.37  4870.5   263.1  4952.1  263.31    5003  262.36  5010.5  258.32
  5018.1  257.32  5018.5  256.82  5023.1  257.32  5030.7  259.74  5038.3  263.37
  5111.3  262.79  5131.5  261.99  5141.6  262.71  5192.7  262.53  5199.5  261.84
  5212.1  262.61  5238.4  262.53  5413.7  265.94  5474.1  268.17  5484.2  269.23
  5504.4  269.08  5645.4  273.55  5665.6  275.27  5688.3  275.03  5806.7  280.25
#Mann= 8 ,-1 , 0
  4200.5     .05       0  4542.5     .07       0    4641     .12       0
  4952.1      .1       0  5018.1     .05       0  5023.1      .1       0
  5192.7     .12       0  5238.4     .07       0
Bank Sta=5018.1,5023.1
XS Rating Curve= 0 ,0
Exp/Cntr=0.3,0.1

Type RM Length L Ch R = 1 ,49317   ,455,455,455
BEGIN DESCRIPTION:
DENTON CREEK 49.0
END DESCRIPTION:
XS GIS Cut Line= 3
        2479825.     13677575.01        2480225.       13676775.
      2479775.01     13675975.01
#Sta/Elev= 30
  4105.2  281.61  4314.8  272.15  4418.3  269.21    4449     267  4696.2  262.43
  4803.5  261.68  4804.7  261.68  4913.3  261.34  4968.9  261.31  4985.7   259.5
  4991.2  260.83  4996.8  257.93  5002.5  257.93  5005.1  256.49  5005.5  255.99
  5010.1  256.49  5022.6  256.95  5029.3   260.6    5035  260.82    5116  260.86
  5125.8   259.1  5137.6  260.22  5160.3  258.79  5167.5  260.19  5331.4  260.46
  5353.1  263.66  5366.8  264.19  5402.2   262.4  5482.5  266.52  5917.5  283.53
#Mann= 9 ,-1 , 0
  4105.2     .05       0  4696.2     .07       0  4803.5     .05       0
  4804.7     .07       0  4913.3      .1       0  5005.1     .05       0
  5010.1      .1       0  5167.5     .12       0  5482.5     .07       0
Bank Sta=5005.1,5010.1
XS Rating Curve= 0 ,0
Exp/Cntr=0.3,0.1

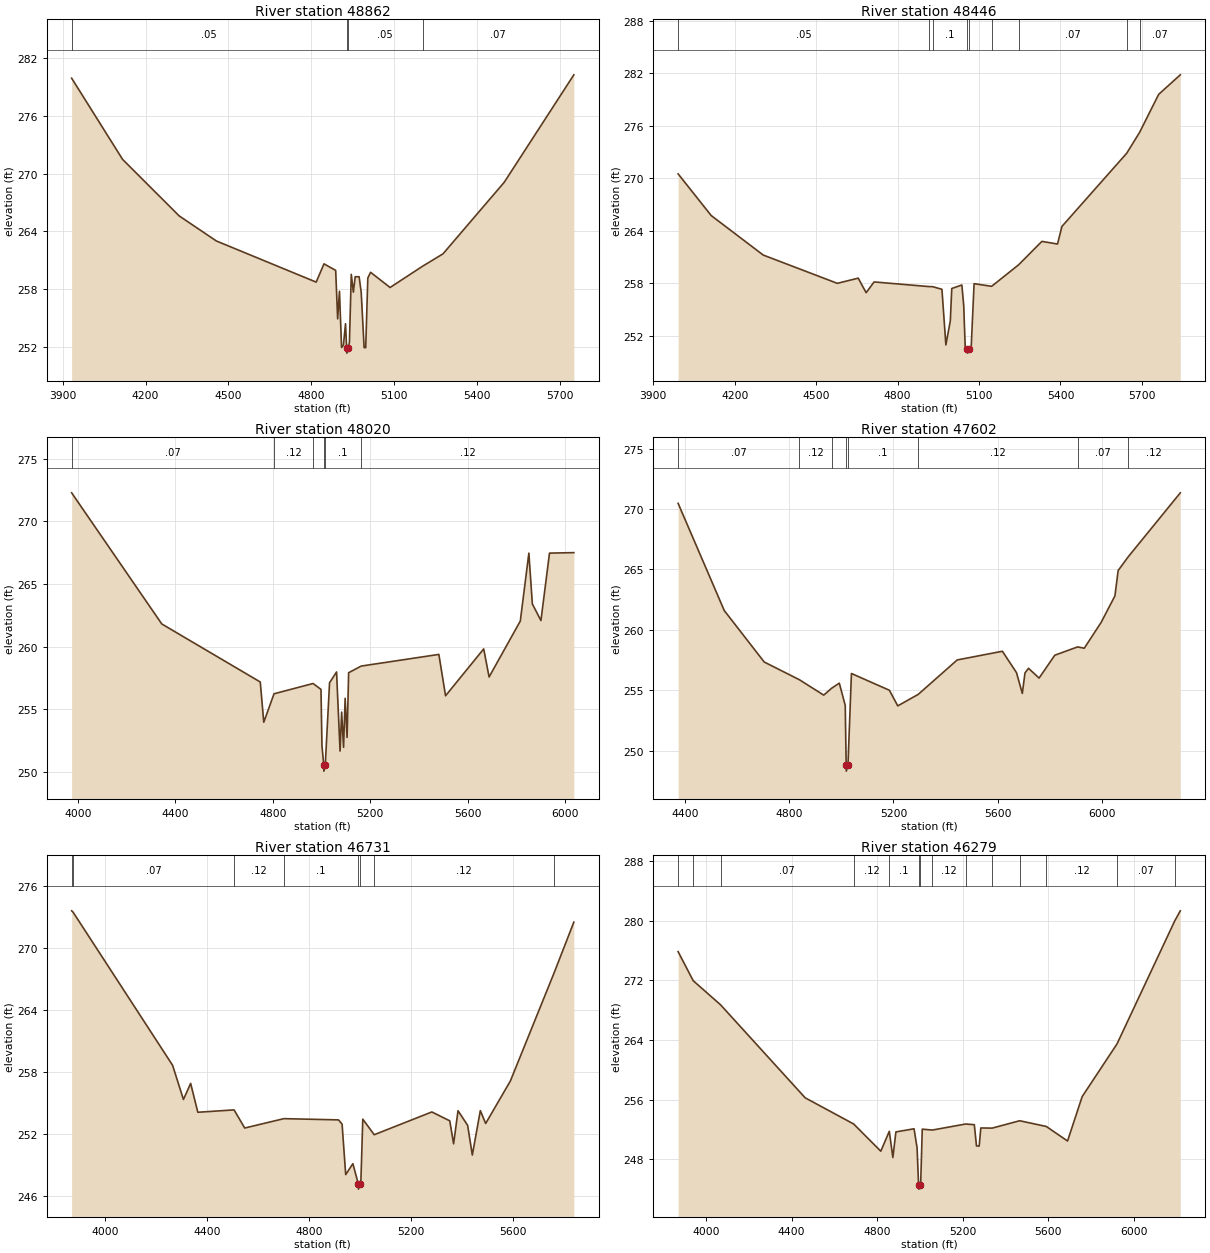
Type RM Length L Ch R = 1 ,48862   ,416,416,416
BEGIN DESCRIPTION:
DENTON CREEK 48.0
END DESCRIPTION:
XS GIS Cut Line= 3
      2479925.02     13677574.98        2480625.       13676775.
        2480525.     13676025.02
#Sta/Elev= 30
  3932.3  279.94  4116.9  271.49  4321.9  265.61  4456.7     263  4818.3  258.72
  4846.7  260.62    4889  259.94  4896.1   254.9  4902.7  257.77  4910.3  251.92
    4917  252.14  4924.6  254.39  4928.7  251.83  4929.1  251.33  4933.8  251.83
  4938.8  252.44  4945.5  259.53    4953  257.67  4959.7  259.28  4973.9  259.28
  4981.5  257.65    4992   251.9  4997.8   251.9  5005.4  259.14  5015.5  259.74
  5086.1  258.16  5203.7  260.37  5277.8  261.66  5499.7  269.11  5751.9  280.29
#Mann= 4 ,-1 , 0
  3932.3     .05       0  4928.7     .05       0  4933.8     .05       0
  5203.7     .07       0
Bank Sta=4928.7,4933.8
XS Rating Curve= 0 ,0
Exp/Cntr=0.3,0.1

Type RM Length L Ch R = 1 ,48446   ,426,426,426
BEGIN DESCRIPTION:
DENTON CREEK 47.0
END DESCRIPTION:
XS GIS Cut Line= 3
      2480375.01     13677524.99        2480975.       13676725.
        2480575.     13675974.99
#Sta/Elev= 30
  3991.5  270.49  4113.4  265.73    4305  261.22  4577.9  257.99    4655  258.58
  4684.2  256.92  4713.4  258.15  4915.3  257.62  4928.9  257.61  4963.4  257.31
  4977.9  250.96  4994.3  253.72  4999.6   257.4  5036.8   257.8  5043.6  255.48
  5049.2  250.63  5056.9  250.52  5057.3  250.02    5062  250.52  5071.2  250.72
  5081.8  257.95  5146.5  257.65  5246.1  260.11  5331.5  262.78  5389.2  262.48
  5405.5  264.49  5644.2  272.85  5691.6  275.23  5761.8  279.57  5841.5   281.8
#Mann= 9 ,-1 , 0
  3991.5     .05       0  4915.3     .12       0  4928.9      .1       0
  5056.9     .05       0    5062      .1       0  5146.5     .12       0
  5246.1     .07       0  5644.2     .12       0  5691.6     .07       0
Bank Sta=5056.9,5062
XS Rating Curve= 0 ,0
Exp/Cntr=0.3,0.1

Type RM Length L Ch R = 1 ,48020   ,418,418,418
BEGIN DESCRIPTION:
DENTON CREEK 46.0
END DESCRIPTION:
XS GIS Cut Line= 3
      2480424.98     13677675.01        2481225.       13677025.
      2481875.02     13676224.98
#Sta/Elev= 30
    3974  272.28    4344  261.82  4748.3  257.19  4762.7  253.98  4804.8  256.25
  4965.1  257.07  4997.6   256.6  5001.6  252.11  5008.8  250.58  5009.3  250.08
  5015.2  250.58  5032.8  257.13  5061.5  257.99  5075.9  251.68  5082.4  254.79
  5090.3  251.98  5096.7  255.89  5104.7  252.77  5111.1  257.93  5162.7  258.46
  5481.5  259.39    5509  256.09  5665.6  259.83  5687.7  257.59  5815.8  262.05
    5851  267.47  5865.3  263.42  5900.5  262.09  5935.7  267.47  6035.6  267.51
#Mann= 6 ,-1 , 0
    3974     .07       0  4804.8     .12       0  4965.1      .1       0
  5008.8     .05       0  5015.2      .1       0  5162.7     .12       0
Bank Sta=5008.8,5015.2
XS Rating Curve= 0 ,0
Exp/Cntr=0.3,0.1

Type RM Length L Ch R = 1 ,47602   ,871,871,871
BEGIN DESCRIPTION:
DENTON CREEK 45.0
END DESCRIPTION:
XS GIS Cut Line= 3
      2481175.01     13677874.98        2481475.       13677325.
      2481975.01     13676124.98
#Sta/Elev= 30
  4373.8  270.47  4550.8   261.6  4704.1  257.34  4839.3  255.87  4932.4   254.6
  4962.8  255.17  4992.2  255.59  5014.9  253.75  5018.5  248.81    5019  248.31
  5025.4  248.81  5038.7  256.39  5184.4     255  5216.4  253.71  5294.9  254.66
  5444.4  257.51  5617.8  258.23  5671.9  256.46  5694.2  254.74  5704.4  256.43
    5718  256.82  5758.6  256.01  5818.7   257.9  5906.3  258.59  5931.9  258.48
  5996.4  260.61  6049.5  262.81  6061.9  264.91  6099.9  266.03  6300.3  271.34
#Mann= 8 ,-1 , 0
  4373.8     .07       0  4839.3     .12       0  4962.8      .1       0
  5018.5     .05       0  5025.4      .1       0  5294.9     .12       0
  5906.3     .07       0  6099.9     .12       0
Bank Sta=5018.5,5025.4
XS Rating Curve= 0 ,0
Exp/Cntr=0.3,0.1

Type RM Length L Ch R = 1 ,46731   ,452,452,452
BEGIN DESCRIPTION:
DENTON CREEK 44.0
END DESCRIPTION:
XS GIS Cut Line= 3
      2481275.03     13678024.97        2482075.       13677225.
        2482325.     13676424.98
#Sta/Elev= 30
  3868.1  273.63    3874  273.49    4264  258.64  4306.5  255.32  4334.8  256.88
    4363  254.08  4505.1  254.31  4546.9  252.55  4700.6  253.46  4914.6  253.34
  4928.7  252.93  4942.9  248.03  4971.1  249.09  4992.4  247.12  4992.9  246.62
  4999.4  247.12  5002.1  247.12  5009.9  253.41  5054.7   251.9  5280.7  254.11
  5350.9  253.25  5366.1  251.02  5383.4  254.23  5421.1  252.81  5439.5  249.93
  5470.9  254.24  5491.8  252.99  5588.8  257.12  5760.1   267.6  5837.6  272.53
#Mann= 8 ,-1 , 0
  3868.1     .12       0    3874     .07       0  4505.1     .12       0
  4700.6      .1       0  4992.4     .05       0  4999.4      .1       0
  5054.7     .12       0  5760.1     .07       0
Bank Sta=4992.4,4999.4
XS Rating Curve= 0 ,0
Exp/Cntr=0.3,0.1

Type RM Length L Ch R = 1 ,46279   ,462,462,462
BEGIN DESCRIPTION:
DENTON CREEK 43.0
END DESCRIPTION:
XS GIS Cut Line= 3
      2481474.97     13678275.03        2482275.       13677475.
      2482475.01     13676274.96
#Sta/Elev= 30
  3869.1  275.87  3939.6  271.97  4067.4  268.74  4463.1  256.25  4690.1  252.73
  4816.7  249.08  4856.5  251.75  4873.2  248.23  4887.4  251.67  4972.2  252.09
  4986.4  249.54  4993.5  244.49    4994  243.99  5000.5  244.49    5003  244.49
  5010.6  252.04  5057.7  251.92  5213.4  252.73    5254  252.64  5264.1  249.79
  5276.8  249.77  5284.4   252.2  5337.6  252.18  5466.1  253.17  5590.7   252.4
  5689.9  250.45  5758.3  256.41  5921.3  263.49  6191.8  280.04  6217.1  281.35
#Mann= 14 ,-1 , 0
  3869.1     .07       0  3939.6     .12       0  4067.4     .07       0
  4690.1     .12       0  4856.5      .1       0  4993.5     .05       0
  5000.5      .1       0  5057.7     .12       0  5213.4     .07       0
  5337.6     .12       0  5466.1     .07       0  5590.7     .12       0
  5921.3     .07       0  6191.8     .05       0
Bank Sta=4993.5,5000.5
XS Rating Curve= 0 ,0
Exp/Cntr=0.3,0.1

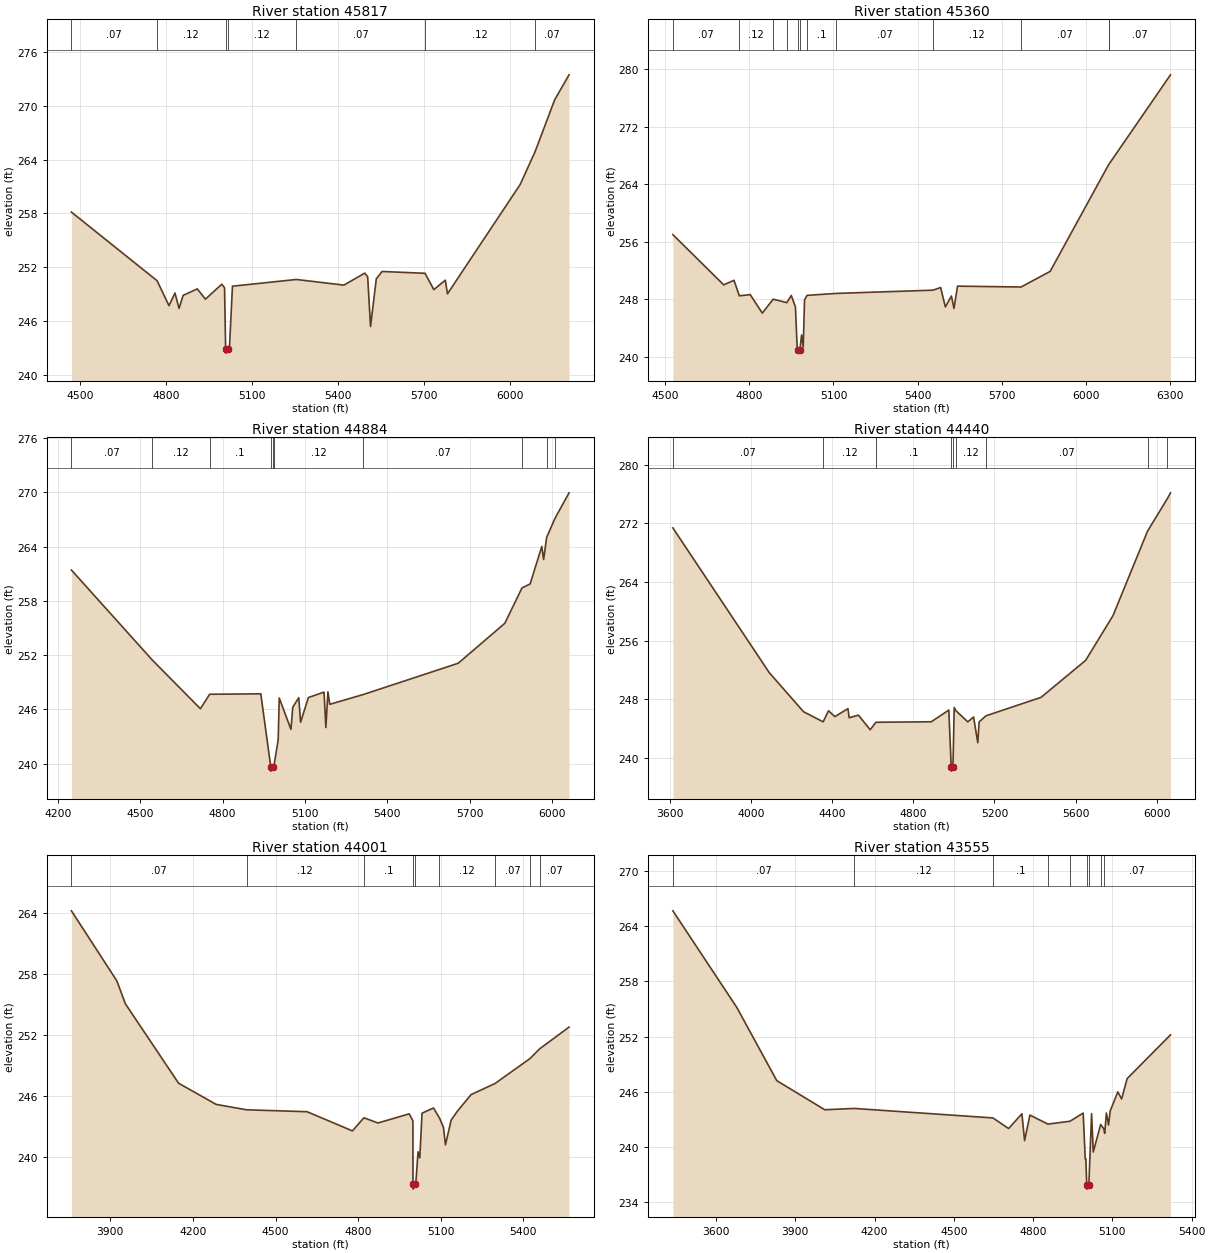
Type RM Length L Ch R = 1 ,45817   ,457,457,457
BEGIN DESCRIPTION:
DENTON CREEK 42.0
END DESCRIPTION:
XS GIS Cut Line= 3
      2482975.03     13678025.03        2482625.       13677625.
        2482525.     13676425.01
#Sta/Elev= 30
  4469.2  258.15    4768   250.5  4809.5  247.72  4830.4  249.13  4844.6  247.42
  4858.9  248.87  4908.2  249.59  4936.7  248.45  4993.6  250.11  5003.3  249.72
  5007.1  242.93  5007.6  242.43  5014.5  242.93  5020.8  243.29  5030.9  249.89
  5253.7  250.64  5419.7  250.01  5492.4  251.35  5502.5  250.94  5512.5   245.4
  5532.6  250.71  5552.7  251.53  5702.5  251.33  5733.3  249.51  5773.4  250.56
  5780.9  249.04  6034.3  261.22  6086.2  264.86  6154.7  270.66  6204.9  273.45
#Mann= 7 ,-1 , 0
  4469.2     .07       0    4768     .12       0  5007.1     .05       0
  5014.5     .12       0  5253.7     .07       0  5702.5     .12       0
  6086.2     .07       0
Bank Sta=5007.1,5014.5
XS Rating Curve= 0 ,0
Exp/Cntr=0.3,0.1

Type RM Length L Ch R = 1 ,45360   ,476,476,476
BEGIN DESCRIPTION:
DENTON CREEK 41.0
END DESCRIPTION:
XS GIS Cut Line= 3
      2483275.02     13677925.03        2483025.       13677525.
      2482525.01     13676325.03
#Sta/Elev= 30
  4528.3     257  4709.3  250.03  4745.9  250.66    4765  248.51  4803.7  248.67
  4846.7  246.11  4885.5  248.04  4933.9  247.56  4949.9  248.55  4964.7  246.96
  4971.1  241.12  4973.3  241.05  4973.8  240.55  4980.7  241.05  4986.5  243.07
  4992.4  241.42  4997.1  247.95  5006.1  248.57  5109.3  248.84  5454.7  249.29
  5481.6  249.66  5498.4  246.97    5520  248.48  5529.2  246.75  5541.7  249.85
  5768.2  249.73  5871.6   251.9  6079.5   266.7  6080.9  266.78    6300  279.19
#Mann= 12 ,-1 , 0
  4528.3     .07       0    4765     .12       0  4885.5      .1       0
  4933.9     .12       0  4973.3     .05       0  4980.7     .12       0
  5006.1      .1       0  5109.3     .07       0  5454.7     .12       0
  5768.2     .07       0  6079.5     .12       0  6080.9     .07       0
Bank Sta=4973.3,4980.7
XS Rating Curve= 0 ,0
Exp/Cntr=0.3,0.1

Type RM Length L Ch R = 1 ,44884   ,444,444,444
BEGIN DESCRIPTION:
DENTON CREEK 40.0
END DESCRIPTION:
XS GIS Cut Line= 3
        2483375.     13678025.04        2483375.       13677275.
      2482674.97     13676474.97
#Sta/Elev= 30
  4249.5  261.42  4543.8  251.48  4719.5  246.08    4753  247.68  4939.5  247.73
  4975.7  239.68  4976.2  239.18  4983.3  239.68  4987.4  239.77  5002.9  242.66
  5006.7  247.27  5049.4   243.8    5056  246.25  5077.8   247.3  5084.5  244.59
    5113  247.32  5169.9  247.92  5176.6     244  5184.1  247.95  5190.8  246.57
  5312.7  247.65  5658.7  251.11  5828.6  255.53  5891.1  259.44  5920.7  259.88
  5963.4  264.03    5970  262.59    5981  265.03  6011.6  267.15  6062.6  269.96
#Mann= 10 ,-1 , 0
  4249.5     .07       0  4543.8     .12       0    4753      .1       0
  4975.7     .05       0  4983.3      .1       0  4987.4     .12       0
  5312.7     .07       0  5891.1     .05       0    5981     .07       0
  6011.6     .05       0
Bank Sta=4975.7,4983.3
XS Rating Curve= 0 ,0
Exp/Cntr=0.3,0.1

Type RM Length L Ch R = 1 ,44440   ,439,439,439
BEGIN DESCRIPTION:
DENTON CREEK 39.0
END DESCRIPTION:
XS GIS Cut Line= 3
      2484325.01     13678175.01        2483625.       13676975.
      2482824.98     13676274.98
#Sta/Elev= 30
  3615.6  271.39  4090.3  251.67  4259.4  246.33  4356.2  244.95  4382.6  246.46
    4414  245.66  4478.5  246.75  4484.3  245.51  4530.2  245.86  4588.1  243.87
  4616.2  244.89  4889.1  244.96  4975.5  246.55  4987.4  238.73  4987.9  238.23
  4995.1  238.73    4997  240.16    5002   246.9    5011  246.45  5068.9  244.95
  5097.4  245.61  5118.3   242.1  5124.9  244.94  5158.5  245.77  5430.1  248.29
  5649.8  253.33  5784.6  259.43  5954.9  270.95  6053.1  275.41  6067.9  276.17
#Mann= 9 ,-1 , 0
  3615.6     .07       0  4356.2     .12       0  4616.2      .1       0
  4987.4     .05       0  4995.1      .1       0    5011     .12       0
  5158.5     .07       0  5954.9     .05       0  6053.1     .07       0
Bank Sta=4987.4,4995.1
XS Rating Curve= 0 ,0
Exp/Cntr=0.3,0.1

Type RM Length L Ch R = 1 ,44001   ,446,446,446
BEGIN DESCRIPTION:
DENTON CREEK 38.0
END DESCRIPTION:
XS GIS Cut Line= 3
        2484275.     13677975.02        2483975.       13676775.
      2483625.02     13676325.03
#Sta/Elev= 30
  3758.7  264.26  3923.6  257.36  3954.6   255.1  4147.8  247.27  4284.4  245.18
  4394.8  244.65  4614.3  244.46  4779.2  242.57  4820.7  243.86    4872  243.35
  4985.3  244.25  4998.8  243.56    4999  237.33  4999.5  236.83  5006.8  237.33
  5009.2  237.37  5017.4  240.51  5023.7  239.91  5031.8  244.31  5073.5  244.83
  5095.2  243.84  5109.7  242.91  5116.9   241.2  5137.7  243.64  5160.3  244.51
  5210.1  246.15  5296.3  247.23  5423.6  249.69  5459.1  250.66  5565.7   252.8
#Mann= 9 ,-1 , 0
  3758.7     .07       0  4394.8     .12       0  4820.7      .1       0
    4999     .05       0  5006.8      .1       0  5095.2     .12       0
  5296.3     .07       0  5423.6     .12       0  5459.1     .07       0
Bank Sta=4999,5006.8
XS Rating Curve= 0 ,0
Exp/Cntr=0.3,0.1

Type RM Length L Ch R = 1 ,43555   ,434,434,434
BEGIN DESCRIPTION:
DENTON CREEK 37.0
END DESCRIPTION:
XS GIS Cut Line= 3
        2484325.     13677974.97        2484125.       13676425.
      2483924.98     13676174.98
#Sta/Elev= 30
  3436.9  265.66  3678.9  255.17  3830.1  247.22  4011.6  244.06  4123.4   244.2
  4648.3  243.17  4707.3  242.02  4757.7  243.62  4767.8  240.71    4788  243.48
  4856.1   242.5  4939.5  242.81  4989.6   243.7  4997.2  238.72  4999.7  238.72
  5002.9  235.94  5003.4  235.44    5011  235.94  5021.3  243.63  5027.7  239.47
  5055.6  242.46  5067.6  241.98    5071   241.5  5077.4  243.71  5085.4  242.41
  5091.8  243.93  5120.6     246    5135  245.23  5155.8  247.44  5319.9  252.19
#Mann= 9 ,-1 , 0
  3436.9     .07       0  4123.4     .12       0  4648.3      .1       0
  4856.1     .12       0  4939.5      .1       0  5002.9     .05       0
    5011      .1       0  5055.6     .12       0  5067.6     .07       0
Bank Sta=5002.9,5011
XS Rating Curve= 0 ,0
Exp/Cntr=0.3,0.1

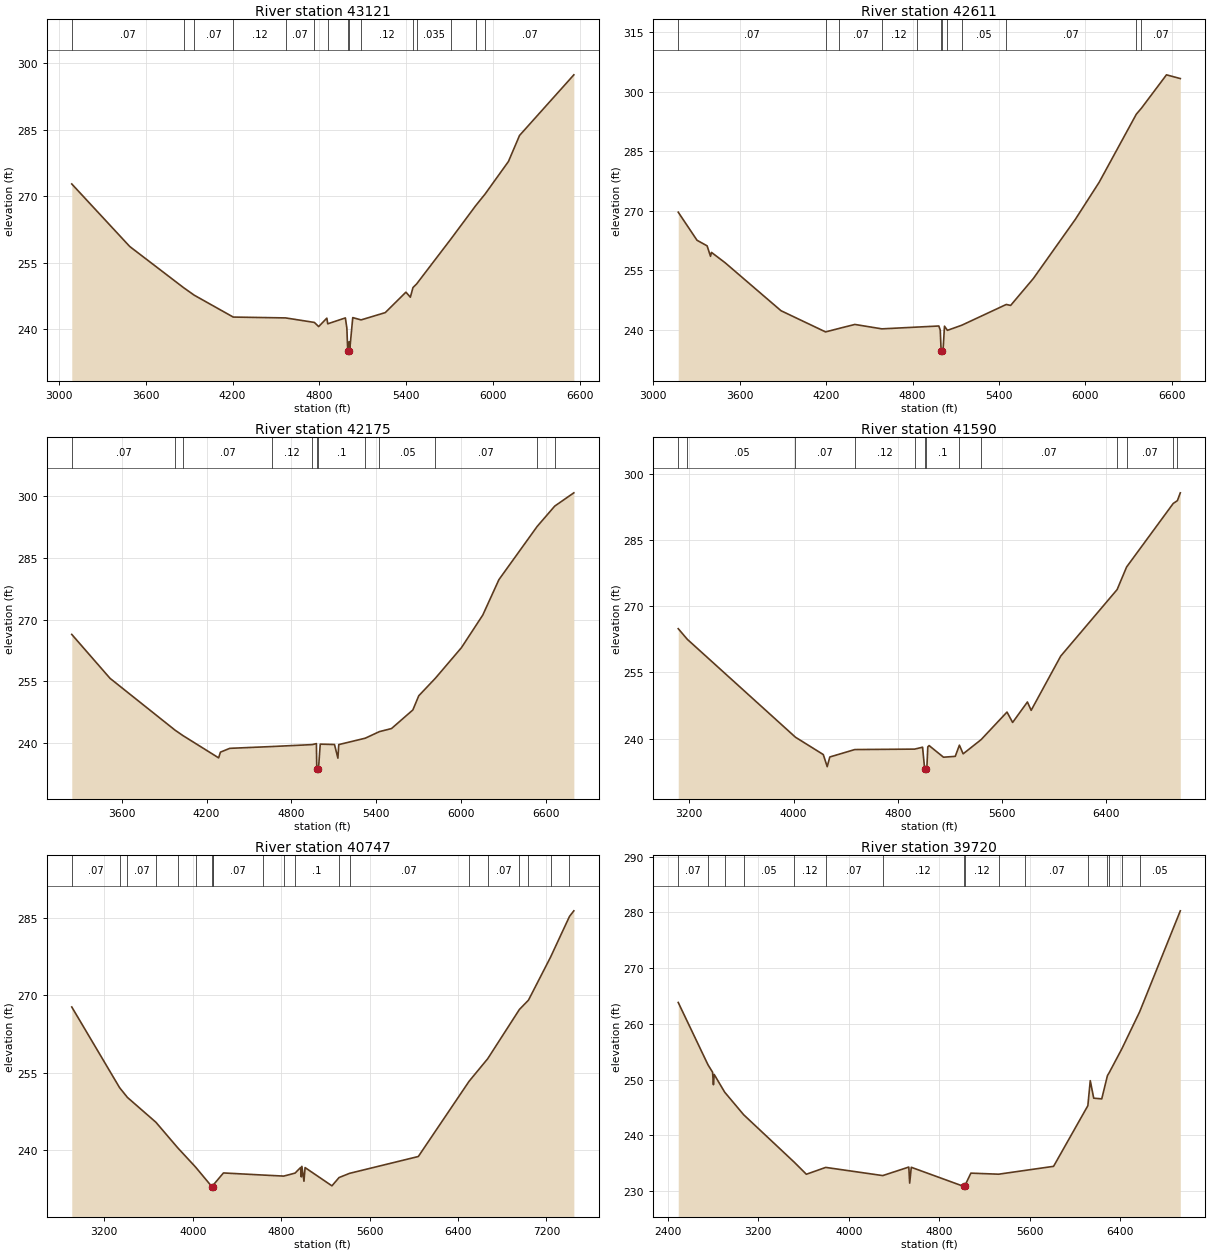
Type RM Length L Ch R = 1 ,43121   ,510,510,510
BEGIN DESCRIPTION:
X18863
END DESCRIPTION:
XS GIS Cut Line= 3
      2484859.55     13678297.71      2484403.82     13675980.04
      2483974.15     13674964.45
#Sta/Elev= 30
  3090.7  272.76  3490.9  258.62  3863.5  249.29  3936.1  247.61    4205  242.67
  4566.2  242.48    4765  241.46  4794.6  240.52    4851  242.43  4857.2  241.15
  4978.9  242.48  4989.1  240.18  4995.2  235.02  4995.7  234.52  5003.4  235.02
  5005.2   237.1  5010.3  235.75  5029.8  242.55  5087.2  242.03  5254.1  243.68
  5396.7   248.3  5427.3  247.16  5445.4  249.35  5469.8  250.13  5706.5  260.29
  5877.9  267.84  5943.2  270.49  6104.2  277.84  6180.7  283.72  6555.5  297.43
#Mann= 15 ,-1 , 0
  3090.7     .07       0  3863.5     .12       0  3936.1     .07       0
    4205     .12       0  4566.2     .07       0    4765     .12       0
  4857.2      .1       0  4995.2     .05       0  5003.4      .1       0
  5087.2     .12       0  5445.4     .07       0  5469.8    .035       0
  5706.5     .07       0  5877.9    .035       0  5943.2     .07       0
Bank Sta=4995.2,5003.4
XS Rating Curve= 0 ,0
Exp/Cntr=0.3,0.1

Type RM Length L Ch R = 1 ,42611   ,436,436,436
BEGIN DESCRIPTION:
X18862
END DESCRIPTION:
XS GIS Cut Line= 3
      2485041.85     13678154.54      2484846.53     13676175.35
      2484209.26     13674822.77
#Sta/Elev= 30
  3174.1  269.65  3304.3  262.59  3374.6  261.17  3398.1  258.54  3404.8  259.53
  3499.3  256.93  3887.1  244.85  4196.5  239.51  4288.2  240.37  4399.6  241.39
  4587.4  240.28  4828.1  240.72  4982.4     241  4992.4  239.96  4998.4  234.67
  4998.9  234.17  5006.6  234.67  5012.5  235.36  5021.7  240.95  5042.1  239.91
  5141.4  241.19  5450.4  246.42  5480.8  246.18  5638.6  252.97  5930.3  267.88
  6095.3   277.2  6352.8  294.32  6388.3  295.83  6562.1  304.23  6658.1  303.29
#Mann= 12 ,-1 , 0
  3174.1     .07       0  4196.5     .12       0  4288.2     .07       0
  4587.4     .12       0  4828.1      .1       0  4998.4     .05       0
  5006.6      .1       0  5042.1     .07       0  5141.4     .05       0
  5450.4     .07       0  6352.8    .035       0  6388.3     .07       0
Bank Sta=4998.4,5006.6
XS Rating Curve= 0 ,0
Exp/Cntr=0.3,0.1

Type RM Length L Ch R = 1 ,42175   ,585,585,585
BEGIN DESCRIPTION:
X18861
END DESCRIPTION:
XS GIS Cut Line= 4
      2485224.14     13678063.33      2485354.34     13677295.14
      2485172.05     13675914.93      2484364.76     13674795.14
#Sta/Elev= 30
  3246.3   266.4  3517.1   255.7  3978.5  243.04  4032.6  241.76  4285.3  236.33
  4297.9  237.72  4363.8  238.65  4662.1  239.09  4947.8  239.56  4976.9   239.8
  4979.6   233.6  4980.1   233.1    4988   233.6  4993.9  234.73    5004  239.67
  5104.9  239.58    5129  236.26  5135.1  239.56  5322.4  241.12  5423.2  242.73
  5508.3  243.47  5659.2     248  5701.1  251.46  5818.9  255.74  6002.8  263.17
  6153.8  271.11  6268.2  279.75  6538.8  292.71  6662.7  297.65  6798.1  300.89
#Mann= 12 ,-1 , 0
  3246.3     .07       0  3978.5     .05       0  4032.6     .07       0
  4662.1     .12       0  4947.8      .1       0  4979.6     .05       0
    4988      .1       0  5322.4     .12       0  5423.2     .05       0
  5818.9     .07       0  6538.8    .035       0  6662.7     .12       0
Bank Sta=4979.6,4988
XS Rating Curve= 0 ,0
Exp/Cntr=0.3,0.1

Type RM Length L Ch R = 1 ,41590   ,843,843,843
BEGIN DESCRIPTION:
X18860
END DESCRIPTION:
XS GIS Cut Line= 4
      2485341.33     13678011.28      2485784.03     13677412.33
      2485666.84     13675797.75      2484509.01     13674861.07
#Sta/Elev= 30
    3115   264.9  3185.9  262.46  4014.7  240.35  4228.1  236.43  4258.2  233.69
  4278.2  235.88  4469.8  237.56  4929.2  237.66  4990.1  238.09  5005.9  233.18
  5006.4  232.68  5014.3  233.18  5022.9  233.44  5030.2  238.17  5040.2  238.46
  5150.5  235.83  5240.8  236.02  5272.7  238.55  5301.4  236.59  5439.1   239.8
  5637.9  246.04  5681.1  243.69  5794.6  248.32  5823.3  246.43  6050.4  258.71
  6483.1  273.75  6555.6  278.85  6913.6  293.23  6945.4  293.86  6967.9  295.63
#Mann= 13 ,-1 , 0
    3115     .07       0  3185.9     .05       0  4014.7     .07       0
  4469.8     .12       0  4929.2      .1       0  5005.9     .05       0
  5014.3      .1       0  5272.7     .12       0  5439.1     .07       0
  6483.1     .12       0  6555.6     .07       0  6913.6    .035       0
  6945.4     .12       0
Bank Sta=5005.9,5014.3
XS Rating Curve= 0 ,0
Exp/Cntr=0.3,0.1

Type RM Length L Ch R = 1 ,40747   ,1027,1027,1027
BEGIN DESCRIPTION:
DENTON CREEK 36.0
END DESCRIPTION:
XS GIS Cut Line= 4
      2485432.47     13678102.43      2486278.82     13677230.04
      2486487.16     13675875.87      2484755.35     13674964.39
#Sta/Elev= 30
  2905.9  267.75  3338.6  252.09  3409.4   250.2  3667.1  245.38  3864.9  240.41
  4026.5  236.67  4172.8   232.9  4173.3   232.4  4181.3   232.9  4184.1  233.15
  4278.2  235.54  4637.7  235.13  4823.7  234.93  4926.3  235.51  4976.4   236.6
  4982.7  234.78  4987.8  236.82  5006.7  233.93  5016.8  236.58  5259.7  233.04
  5324.6  234.65    5419  235.46  6041.4  238.73  6500.7  253.33  6669.2  257.71
  6956.1  267.27  7037.8  269.07  7237.7  277.42    7409  285.32  7448.5  286.41
#Mann= 20 ,-1 , 0
  2905.9     .07       0  3338.6     .05       0  3409.4     .07       0
  3667.1     .05       0  3864.9     .07       0  4026.5     .12       0
  4172.8     .05       0  4181.3     .12       0  4184.1     .07       0
  4637.7     .07       0  4823.7     .12       0  4926.3      .1       0
  5324.6     .12       0    5419     .07       0  6500.7     .12       0
  6669.2     .07       0  6956.1     .12       0  7037.8     .07       0
  7237.7     .12       0    7409     .07       0
Bank Sta=4172.8,4181.3
XS Rating Curve= 0 ,0
Exp/Cntr=0.3,0.1

Type RM Length L Ch R = 1 ,39720   ,779,779,779
BEGIN DESCRIPTION:
DENTON CREEK 35.0
END DESCRIPTION:
XS GIS Cut Line= 3
      2485549.65     13678128.48       2487203.3     13676683.16
      2487580.88     13674469.79
#Sta/Elev= 30
  2491.3  263.83  2754.3  252.65  2795.1  251.31  2802.7  249.06  2809.3  250.91
  2902.1  247.73  3069.8  243.68  3518.9  235.13  3624.7  232.99  3796.1  234.22
  4300.3  232.75  4531.1  234.28  4538.7   231.4    4553  234.24  5015.7  230.82
  5016.2  230.32  5024.3  230.82  5080.2  233.19    5326     233  5559.9  233.68
  5811.7  234.41    6115   245.3  6136.3  249.79  6166.8  246.65  6237.8  246.52
  6288.3   250.7  6304.2  251.24  6416.7  255.55  6573.6  262.17  6932.9  280.28
#Mann= 16 ,-1 , 0
  2491.3     .07       0  2754.3     .05       0  2902.1     .07       0
  3069.8     .05       0  3518.9     .12       0  3796.1     .07       0
  4300.3     .12       0  5015.7     .05       0  5024.3     .12       0
    5326     .05       0  5559.9     .07       0    6115     .12       0
  6288.3     .07       0  6304.2     .05       0  6416.7     .07       0
  6573.6     .05       0
Bank Sta=5015.7,5024.3
XS Rating Curve= 0 ,0
Exp/Cntr=0.3,0.1

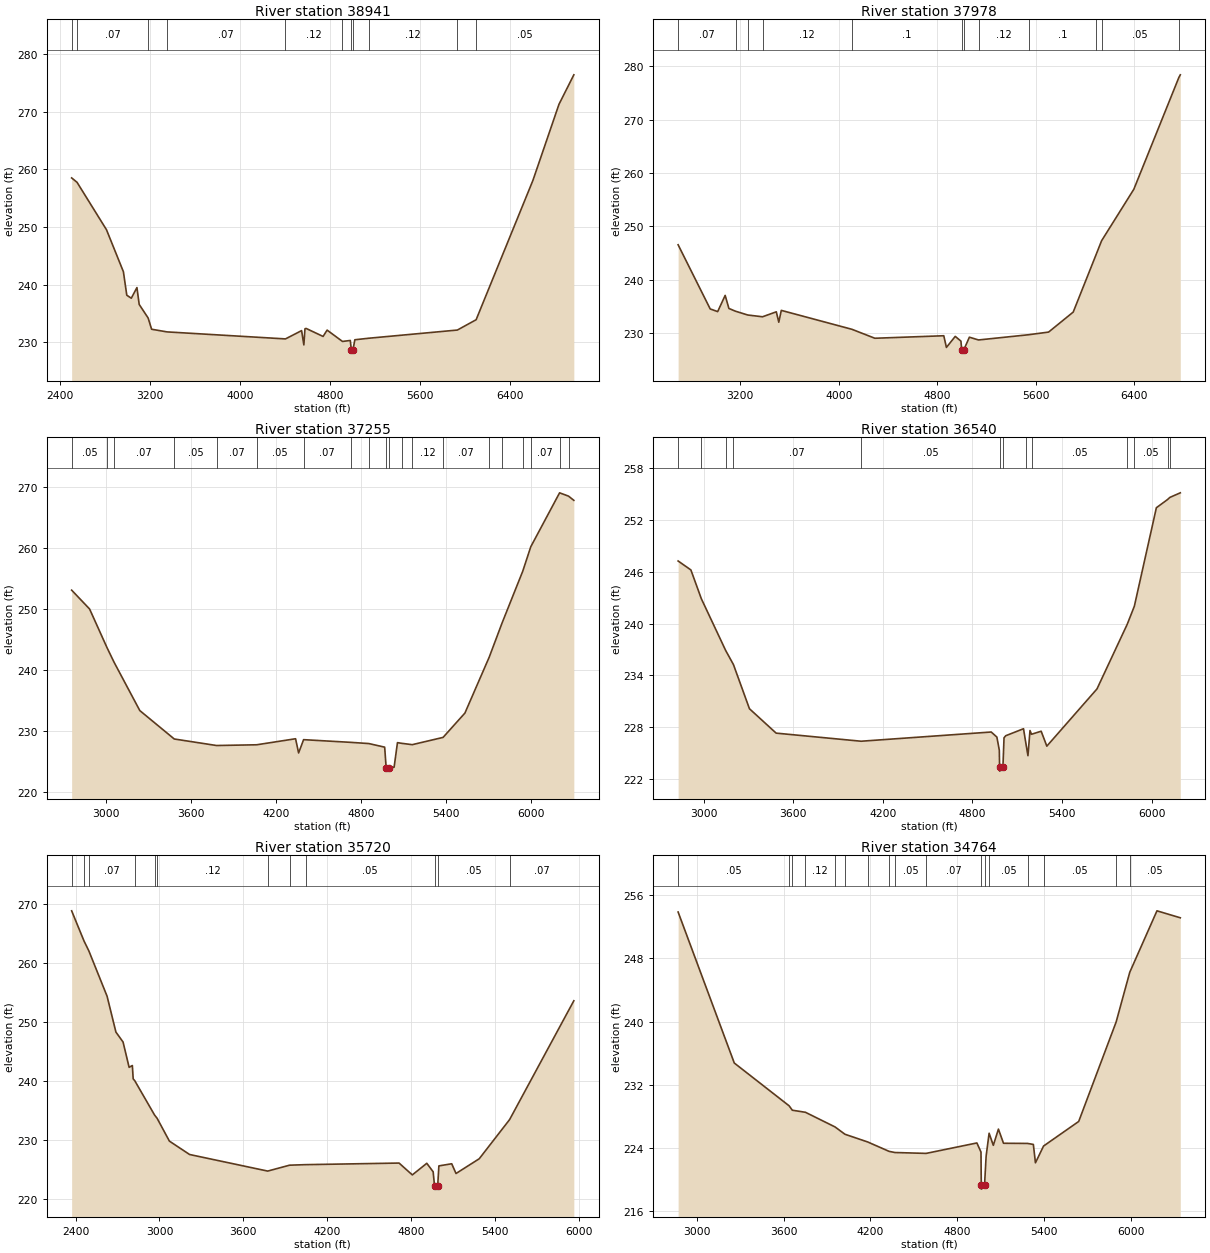
Type RM Length L Ch R = 1 ,38941   ,963,963,963
BEGIN DESCRIPTION:
DENTON CREEK 34.0
END DESCRIPTION:
XS GIS Cut Line= 3
      2488179.86      13679013.9      2487997.57     13676878.48
      2487685.07     13674573.76
#Sta/Elev= 30
  2499.8  258.52  2547.6  257.76  2809.8  249.52  2960.4  242.22  2990.5  238.14
  3030.6  237.62  3080.8  239.47  3100.9  236.54  3180.6  234.18  3211.3  232.23
  3347.8  231.77  4402.7  230.55  4546.1  231.99  4566.2  229.51  4576.2  232.31
  4586.3  232.37  4737.3  230.98  4773.2  232.08  4909.9  230.11  4979.5  230.28
  4988.9  228.58  4989.4  228.08  5002.9  228.58  5019.9   230.4  5144.6  230.67
  5932.3  232.09  6099.2  233.88  6604.3  258.07  6836.4   271.3  6968.8  276.43
#Mann= 11 ,-1 , 0
  2499.8     .12       0  2547.6     .07       0  3180.6     .12       0
  3347.8     .07       0  4402.7     .12       0  4909.9      .1       0
  4988.9     .05       0  5002.9      .1       0  5144.6     .12       0
  5932.3      .1       0  6099.2     .05       0
Bank Sta=4988.9,5002.9
XS Rating Curve= 0 ,0
Exp/Cntr=0.3,0.1

Type RM Length L Ch R = 1 ,37978   ,723,723,723
BEGIN DESCRIPTION:
DENTON CREEK 33.0
END DESCRIPTION:
XS GIS Cut Line= 3
      2488375.17     13678532.14       2488700.7     13676448.79
      2487997.58     13674612.86
#Sta/Elev= 30
  2697.1  246.55  2957.4  234.51  3018.1  234.01  3078.8  237.05  3109.2   234.6
  3163.2  234.08  3262.5  233.37  3382.1  233.04  3493.8  233.97    3514  232.02
  3534.3  234.24  4107.3  230.69  4293.4  229.01  4852.6  229.48    4874  227.29
  4945.6  229.36  4991.8  228.47  4998.5  226.72    4999  226.22  5012.9  226.72
  5060.4  229.21  5134.5  228.69  5540.8  229.67  5703.2  230.17  5902.8  233.92
  6091.6  244.88    6133   247.3  6394.6  256.96  6759.8  277.92  6771.7  278.43
#Mann= 12 ,-1 , 0
  2697.1     .07       0  3163.2     .12       0  3262.5     .07       0
  3382.1     .12       0  4107.3      .1       0  4998.5     .05       0
  5012.9      .1       0  5134.5     .12       0  5540.8      .1       0
  6091.6     .07       0    6133     .05       0  6759.8     .07       0
Bank Sta=4998.5,5012.9
XS Rating Curve= 0 ,0
Exp/Cntr=0.3,0.1

Type RM Length L Ch R = 1 ,37255   ,715,715,715
BEGIN DESCRIPTION:
DENTON CREEK 32.0
END DESCRIPTION:
XS GIS Cut Line= 3
      2490289.25     13677802.97      2489312.68     13676227.43
      2488649.73     13674680.56
#Sta/Elev= 30
  2761.6  253.08  2887.9  249.99  3011.3  243.62  3060.1  241.27  3241.6  233.33
  3484.3  228.67  3781.9   227.6  4064.7  227.72  4338.6  228.71  4359.9  226.38
  4395.1  228.56  4726.4  228.12  4854.6  227.92    4966  227.33  4976.7   223.9
  4977.2   223.4    4999   223.9  5032.5  224.05  5056.1  228.07  5088.9  227.95
  5160.3  227.74  5377.2  228.93  5531.1  232.92  5702.6  242.11  5791.9  247.64
  5938.6   256.2    5995   260.2  6197.9  269.04  6260.6   268.5  6298.2  267.81
#Mann= 20 ,-1 , 0
  2761.6     .05       0  3011.3     .05       0  3060.1     .07       0
  3484.3     .05       0  3781.9     .07       0  4064.7     .05       0
  4395.1     .07       0  4726.4     .05       0  4854.6     .07       0
  4976.7     .05       0    4999     .12       0  5088.9     .07       0
  5160.3     .12       0  5377.2     .07       0  5702.6     .05       0
  5791.9     .07       0  5938.6     .05       0    5995     .07       0
  6197.9     .05       0  6260.6    .035       0
Bank Sta=4976.7,4999
XS Rating Curve= 0 ,0
Exp/Cntr=0.3,0.1

Type RM Length L Ch R = 1 ,36540   ,820,820,820
BEGIN DESCRIPTION:
DENTON CREEK 31.0
END DESCRIPTION:
XS GIS Cut Line= 3
      2490510.58     13677633.66      2489612.16     13675446.18
      2489130.37     13674573.76
#Sta/Elev= 30
  2829.9  247.26  2915.4  246.22  2985.1  242.89  3148.6  236.86  3200.2  235.24
  3307.4  230.11    3486  227.28  4054.9  226.34  4925.7  227.41  4963.5  226.82
  4979.8  225.31  4981.7  223.37  4982.2  222.87  5004.1  223.37  5011.4  226.74
    5023  226.98  5141.9  227.79  5155.7   226.3  5171.5  224.66  5185.2  227.58
  5195.4  227.15    5260   227.5  5297.9  225.77  5633.6  232.41  5836.2  239.92
  5883.7  242.01  6031.1  253.44  6105.8  254.39  6121.6  254.64  6191.3  255.17
#Mann= 13 ,-1 , 0
  2829.9     .07       0  2985.1     .05       0  3148.6     .12       0
  3200.2     .07       0  4054.9     .05       0  4981.7     .05       0
  5004.1     .05       0  5155.7     .07       0  5195.4     .05       0
  5836.2     .07       0  5883.7     .05       0  6105.8     .07       0
  6121.6     .05       0
Bank Sta=4981.7,5004.1
XS Rating Curve= 0 ,0
Exp/Cntr=0.3,0.1

Type RM Length L Ch R = 1 ,35720   ,956,956,956
BEGIN DESCRIPTION:
DENTON CREEK 30.0
END DESCRIPTION:
XS GIS Cut Line= 3
      2491591.34     13677568.61      2490393.41     13675745.66
      2489912.09     13674418.79
#Sta/Elev= 30
  2371.9  268.89  2460.7  263.76  2495.1  262.09  2625.4  254.41  2688.6  248.33
  2739.8  246.64  2783.1  242.35  2806.2  242.66  2812.2  240.39  2823.3  240.09
  2965.3  234.26  2983.6   233.7  3071.3  229.84  3215.9  227.57  3774.5  224.76
    3931  225.76  4047.6  225.85  4714.3  226.12  4809.2  224.11  4912.7  226.08
  4958.2  224.64  4968.2   222.2  4968.7   221.7  4990.6   222.2  4999.2  225.64
  5091.1     226  5121.7  224.35  5287.9  226.85  5505.1  233.49  5964.7  253.64
#Mann= 12 ,-1 , 0
  2371.9     .07       0  2460.7     .05       0  2495.1     .07       0
  2823.3     .12       0  2965.3     .07       0  2983.6     .12       0
  3774.5     .07       0    3931     .12       0  4047.6     .05       0
  4968.2     .05       0  4990.6     .05       0  5505.1     .07       0
Bank Sta=4968.2,4990.6
XS Rating Curve= 0 ,0
Exp/Cntr=0.3,0.1

Type RM Length L Ch R = 1 ,34764   ,865,865,865
BEGIN DESCRIPTION:
DENTON CREEK 29.0
END DESCRIPTION:
XS GIS Cut Line= 3
      2492450.73      13676995.7      2491135.59     13675433.16
      2490237.13     13674326.36
#Sta/Elev= 30
    2872  253.85  3259.9  234.75  3638.4  229.34  3660.7  228.78  3751.1  228.52
  3955.3  226.67  4024.1  225.74  4180.5  224.77  4328.6  223.58  4369.5  223.43
  4584.7  223.32  4935.2  224.64  4963.5  223.49  4965.6   219.3  4966.1   218.8
    4988   219.3  4999.1  222.99  5019.6  225.87  5048.7  224.34  5083.9  226.39
    5119   224.6    5286  224.58  5325.2  224.45  5339.6  222.13  5395.6  224.25
  5638.4  227.36  5896.8  239.94  5990.7  246.22  6178.7     254  6339.9  253.12
#Mann= 17 ,-1 , 0
    2872     .05       0  3638.4     .12       0  3660.7     .05       0
  3751.1     .12       0  3955.3     .05       0  4024.1     .12       0
  4180.5     .05       0  4328.6     .07       0  4369.5     .05       0
  4584.7     .07       0  4965.6     .05       0    4988     .07       0
  5019.6     .05       0    5286     .12       0  5395.6     .05       0
  5896.8     .07       0  5990.7     .05       0
Bank Sta=4965.6,4988
XS Rating Curve= 0 ,0
Exp/Cntr=0.3,0.1