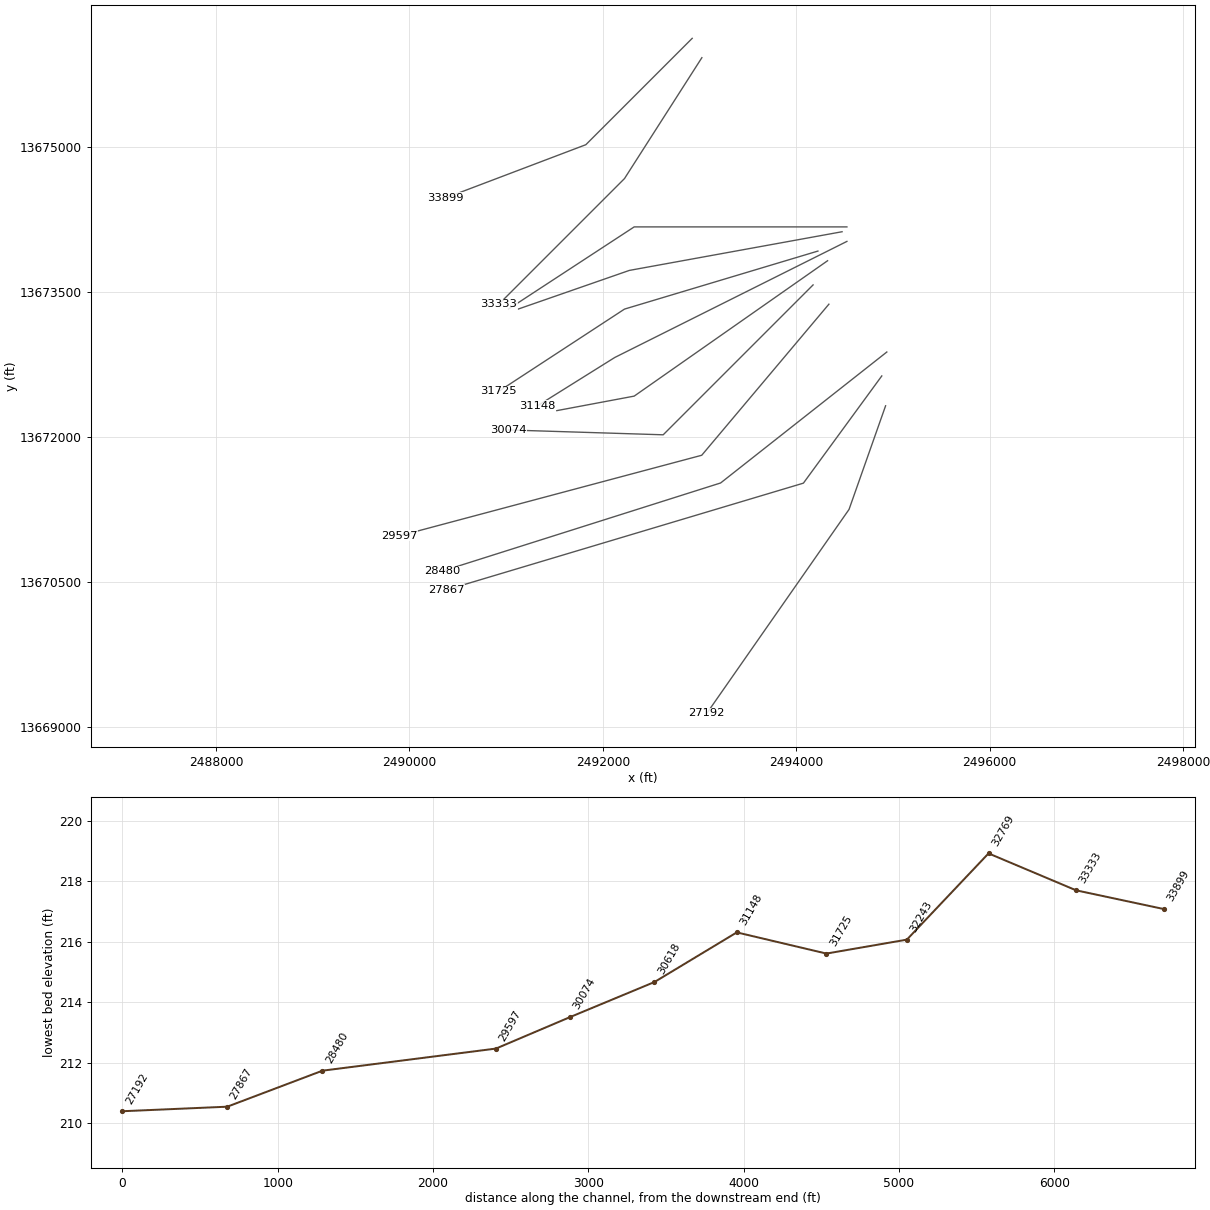
HEC-RAS study DENTON CREEK.prj: DENTON CREEK Base Level Engineering

--- DENTON CREEK.g01 (geometry) --- (continued)

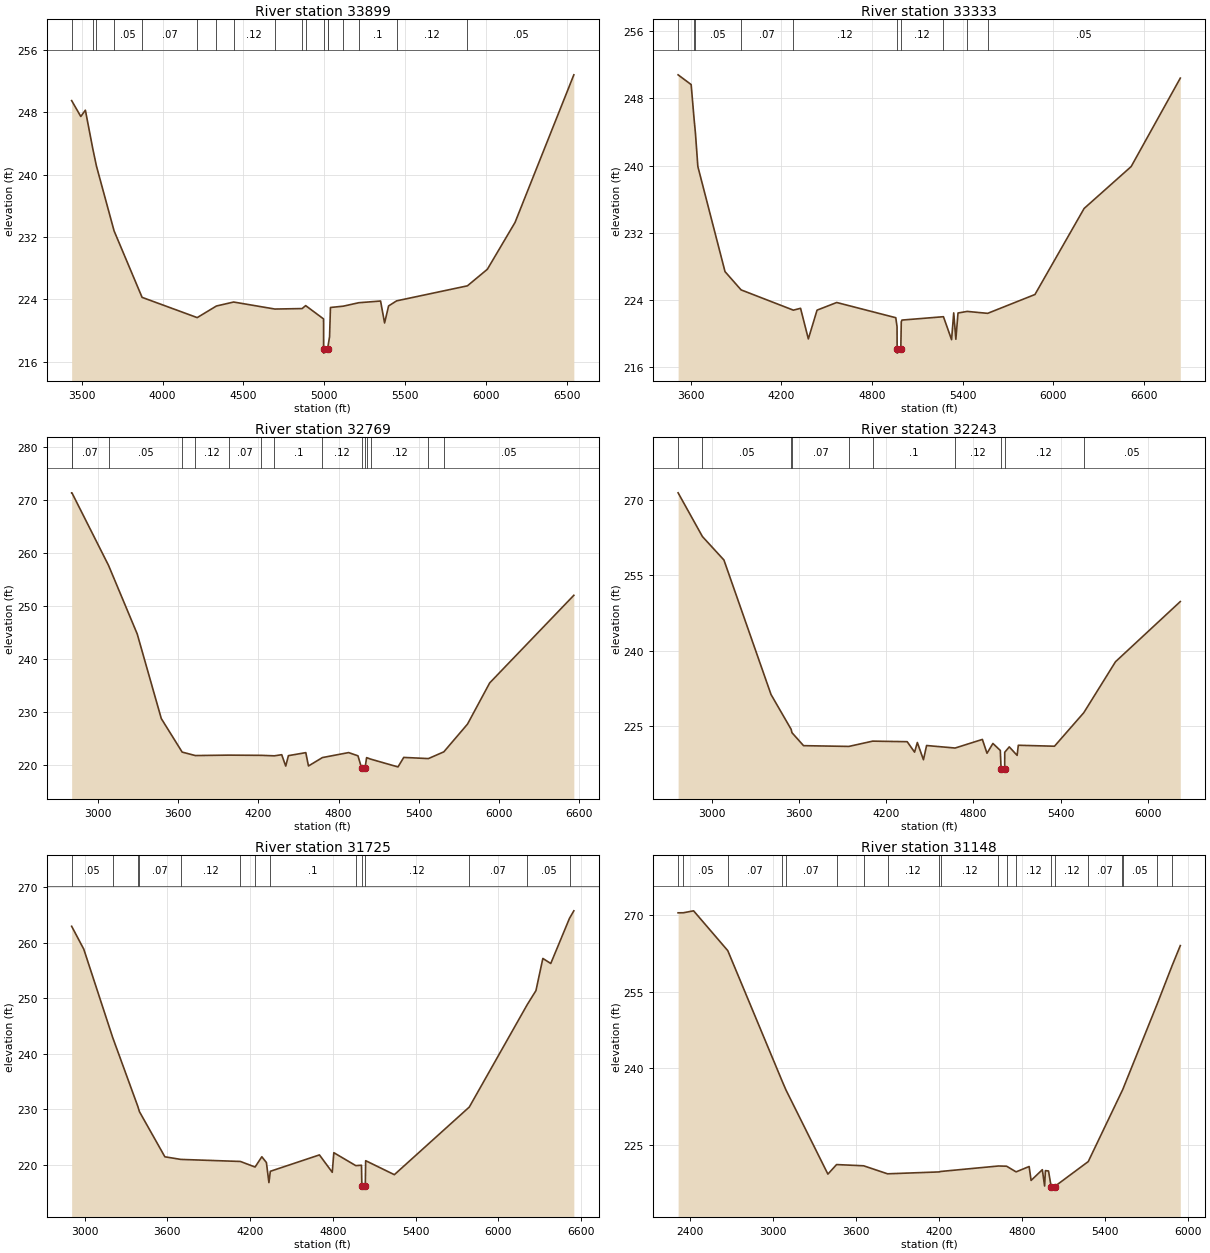
Type RM Length L Ch R = 1 ,33899   ,566,566,566
BEGIN DESCRIPTION:
DENTON CREEK 28.0
END DESCRIPTION:
XS GIS Cut Line= 3
      2492925.02     13676125.02        2491825.       13675025.
      2490374.97     13674474.99
#Sta/Elev= 30
  3437.2   249.5  3493.8  247.46  3522.1  248.27  3568.3  243.29  3590.6   241.1
  3699.6  232.78  3872.9  224.24  4213.9  221.64  4332.8  223.13  4439.2  223.64
  4694.2  222.74  4862.8   222.8  4884.9  223.18  4995.5  221.47  4995.8  217.58
  4996.3  217.08  5020.1  217.58  5020.7  217.66  5032.7   219.2  5038.1  222.94
  5118.1  223.11  5213.1  223.55  5348.2  223.77    5373  220.95  5397.8  223.14
  5447.3  223.79  5885.4  225.72  6008.9  227.85    6180  233.86  6543.7  252.81
#Mann= 18 ,-1 , 0
  3437.2     .07       0  3568.3     .05       0  3590.6     .07       0
  3699.6     .05       0  3872.9     .07       0  4213.9     .12       0
  4332.8     .07       0  4439.2     .12       0  4694.2     .07       0
  4862.8     .12       0  4884.9     .07       0  4995.8     .05       0
  5020.1     .07       0  5020.7     .07       0  5118.1     .12       0
  5213.1      .1       0  5447.3     .12       0  5885.4     .05       0
Bank Sta=4995.8,5020.1
XS Rating Curve= 0 ,0
Exp/Cntr=0.3,0.1

Type RM Length L Ch R = 1 ,33333   ,564,564,564
BEGIN DESCRIPTION:
DENTON CREEK 27.0
END DESCRIPTION:
XS GIS Cut Line= 3
        2493025.       13675925.        2492225.       13674675.
      2490924.97     13673374.97
#Sta/Elev= 30
  3516.6  250.79  3602.9  249.63  3622.1  245.58  3631.1  243.88  3647.2  239.89
    3827  227.39  3933.2  225.22  4279.1  222.81  4326.7  223.03  4378.3  219.39
  4435.8  222.81    4566  223.72  4956.7  221.91  4965.1  220.84  4965.7   218.2
  4966.2   217.7    4990   218.2  4993.1  221.43  4997.7  221.63  5272.1  222.03
  5325.9   219.3  5340.1  222.49  5354.2  219.35  5368.4  222.47  5429.2  222.66
  5564.6  222.43  5877.5  224.67  6202.8   234.9  6513.9  239.88  6839.2   250.4
#Mann= 10 ,-1 , 0
  3516.6     .05       0  3622.1     .07       0  3631.1     .05       0
  3933.2     .07       0  4279.1     .12       0  4965.7     .05       0
    4990     .12       0  5272.1      .1       0  5429.2     .07       0
  5564.6     .05       0
Bank Sta=4965.7,4990
XS Rating Curve= 0 ,0
Exp/Cntr=0.3,0.1

Type RM Length L Ch R = 1 ,32769   ,526,526,526
BEGIN DESCRIPTION:
DENTON CREEK 26.0
END DESCRIPTION:
XS GIS Cut Line= 3
      2494525.04       13674175.        2492325.       13674175.
      2491024.97     13673324.98
#Sta/Elev= 30
  2804.5  271.29  2806.6  271.29  3080.7  257.61  3294.5  244.74  3474.5  228.81
  3630.5   222.5  3728.9  221.85    3978  221.93    4221  221.89  4319.4   221.8
  4374.5  222.01  4404.5  219.87  4424.5  221.83  4554.5   222.4  4574.5  219.89
  4678.6  221.47  4874.5  222.41  4944.5   221.8  4972.4  219.42  4972.9  218.92
  4996.7  219.42    5009  221.46  5039.3  221.18  5243.5  219.71  5286.5   221.5
  5470.8  221.28  5586.2  222.55  5763.1  227.77  5928.9  235.52  6557.8  252.01
#Mann= 15 ,-1 , 0
  2804.5     .12       0  2806.6     .07       0  3080.7     .05       0
  3630.5     .07       0  3728.9     .12       0    3978     .07       0
    4221     .12       0  4319.4      .1       0  4678.6     .12       0
  4972.4     .05       0  4996.7     .12       0    5009      .1       0
  5039.3     .12       0  5470.8     .07       0  5586.2     .05       0
Bank Sta=4972.4,4996.7
XS Rating Curve= 0 ,0
Exp/Cntr=0.3,0.1

Type RM Length L Ch R = 1 ,32243   ,518,518,518
BEGIN DESCRIPTION:
DENTON CREEK 25.0
END DESCRIPTION:
XS GIS Cut Line= 3
      2494475.01       13674125.        2492275.       13673725.
      2491124.96     13673324.99
#Sta/Elev= 30
  2768.7  271.38  2935.9  262.69  3083.8  258.03  3407.8  231.29    3546  224.38
  3551.7  223.71  3631.4  221.13  3942.9  220.98  4106.5  222.03  4344.1  221.92
  4394.9  219.84    4414  221.76  4455.9  218.33  4477.5  221.16  4673.7  220.66
  4861.2  222.37    4893  219.62  4933.6  221.57  4984.5  220.18  4989.8  216.57
  4990.3  216.07  5014.6  216.57    5015  219.82  5046.1  220.89  5100.1   219.2
  5108.3  221.21  5357.1  221.02  5558.6  227.68  5776.7  237.81  6222.4  249.77
#Mann= 10 ,-1 , 0
  2768.7     .07       0  2935.9     .05       0    3546     .12       0
  3551.7     .07       0  3942.9     .12       0  4106.5      .1       0
  4673.7     .12       0  4989.8     .05       0  5014.6     .12       0
  5558.6     .05       0
Bank Sta=4989.8,5014.6
XS Rating Curve= 0 ,0
Exp/Cntr=0.3,0.1

Type RM Length L Ch R = 1 ,31725   ,577,577,577
BEGIN DESCRIPTION:
DENTON CREEK 24.0
END DESCRIPTION:
XS GIS Cut Line= 3
      2494225.03     13673925.01        2492225.       13673325.
      2490925.01     13672475.01
#Sta/Elev= 30
  2906.6  262.93  2994.5  258.81    3204  242.92  3386.5   230.5  3398.5  229.54
  3582.6  221.43    3698  220.96  4130.3  220.59  4236.7  219.59  4285.6  221.44
  4318.7   220.4    4337  216.78  4347.2  218.82  4703.2  221.77  4796.3  218.64
  4807.6  222.17  4966.8  219.84  5008.2  219.91  5010.9  216.11  5011.4  215.61
  5035.7  216.11  5038.4  220.73  5246.5  218.21    5790  230.39  6210.1  248.83
  6273.1  251.34  6323.2  257.14  6380.6  256.23  6516.6  264.37  6547.9  265.71
#Mann= 14 ,-1 , 0
  2906.6     .05       0    3204     .07       0  3386.5     .12       0
  3398.5     .07       0    3698     .12       0  4130.3     .07       0
  4236.7     .12       0  4347.2      .1       0  4966.8     .12       0
  5010.9     .05       0  5035.7     .12       0    5790     .07       0
  6210.1     .05       0  6516.6     .07       0
Bank Sta=5010.9,5035.7
XS Rating Curve= 0 ,0
Exp/Cntr=0.3,0.1

Type RM Length L Ch R = 1 ,31148   ,530,530,530
BEGIN DESCRIPTION:
DENTON CREEK 23.0
END DESCRIPTION:
XS GIS Cut Line= 3
      2494524.98     13674024.99        2492125.       13672825.
      2491324.96     13672324.98
#Sta/Elev= 30
  2315.6  270.43  2353.4  270.44  2427.4  270.82  2674.3  263.02    3067  237.46
  3094.7  235.72  3397.3  219.25    3460  221.12  3655.4  220.88    3828  219.31
  4200.6  219.68  4212.3  219.77  4628.8  220.84  4687.9   220.8  4756.5  219.69
  4850.7  220.74  4864.7  218.01  4945.8  220.12  4962.5  216.92  4968.1  219.93
  4990.5  219.87  5009.5  216.81    5010  216.31  5034.3  216.81  5277.6  221.71
  5521.6  235.54  5525.1  235.72  5776.5  252.65  5883.8  260.13  5942.3  264.01
#Mann= 20 ,-1 , 0
  2315.6     .12       0  2353.4     .05       0  2674.3     .07       0
    3067     .05       0  3094.7     .07       0    3460     .12       0
  3655.4     .07       0    3828     .12       0  4200.6     .07       0
  4212.3     .12       0  4628.8      .1       0  4687.9     .07       0
  4756.5     .12       0  5009.5     .05       0  5034.3     .12       0
  5277.6     .07       0  5521.6    .035       0  5525.1     .05       0
  5776.5     .07       0  5883.8     .05       0
Bank Sta=5009.5,5034.3
XS Rating Curve= 0 ,0
Exp/Cntr=0.3,0.1

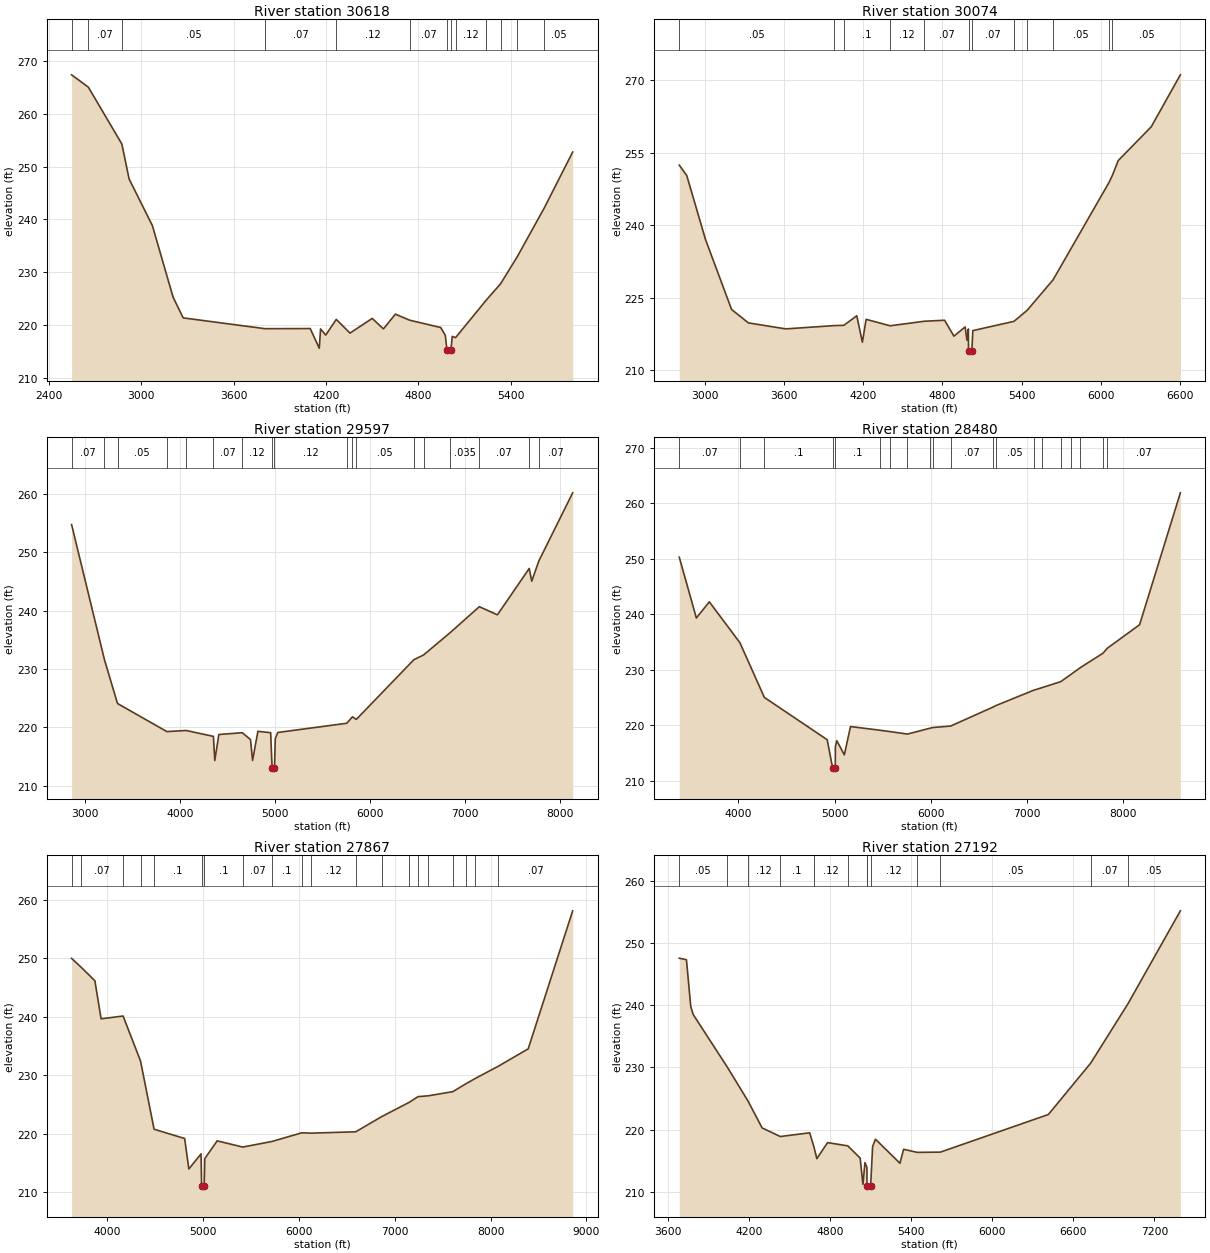
Type RM Length L Ch R = 1 ,30618   ,544,544,544
BEGIN DESCRIPTION:
DENTON CREEK 22.0
END DESCRIPTION:
XS GIS Cut Line= 3
      2494324.99     13673824.99        2492325.       13672425.
      2491525.04     13672275.01
#Sta/Elev= 30
  2547.1  267.42  2655.8  265.09  2873.8   254.3  2920.7  247.68    3072  238.84
  3206.7  225.26  3272.1  221.35  3804.5   219.3  4097.3  219.33  4156.2   215.6
  4164.5  219.26    4198  218.09  4266.5  221.06  4355.8  218.47  4500.1  221.25
  4572.9  219.26  4650.5  222.06  4743.4  220.91  4945.2  219.52  4974.9  218.04
  4986.1  215.17  4986.6  214.67    5011  215.17  5019.8  217.84  5041.7  217.61
  5240.9  224.72  5334.2  227.82  5442.6  232.96  5616.7  242.13  5802.3  252.78
#Mann= 13 ,-1 , 0
  2547.1     .05       0  2655.8     .07       0  2873.8     .05       0
  3804.5     .07       0  4266.5     .12       0  4743.4     .07       0
  4986.1     .05       0    5011     .07       0  5041.7     .12       0
  5240.9     .07       0  5334.2     .05       0  5442.6    .035       0
  5616.7     .05       0
Bank Sta=4986.1,5011
XS Rating Curve= 0 ,0
Exp/Cntr=0.3,0.1

Type RM Length L Ch R = 1 ,30074   ,477,477,477
BEGIN DESCRIPTION:
DENTON CREEK 21.0
END DESCRIPTION:
XS GIS Cut Line= 3
      2494174.97     13673574.97        2492625.       13672025.
      2491024.97       13672075.
#Sta/Elev= 30
    2808  252.44  2864.5   250.3  3005.9  237.09  3203.9  222.55  3331.2  219.77
  3614.1  218.53  3980.6  219.21  4054.1  219.27  4151.5  221.25  4193.9  215.77
  4222.2  220.51  4403.5  219.17    4662  220.11  4816.1  220.32  4886.8  217.03
  4971.7  218.93  4985.8  216.18  4996.4  218.51  4997.4  214.01  4997.9  213.51
  5022.5  214.01    5030  218.17  5341.3  220.09  5440.3  222.35  5637.4  228.69
    6062  248.91  6086.9  250.36  6130.5  253.38  6380.7  260.39  6600.8  271.14
#Mann= 12 ,-1 , 0
    2808     .05       0  3980.6     .07       0  4054.1      .1       0
  4403.5     .12       0    4662     .07       0  4997.4     .05       0
  5022.5     .07       0  5341.3     .05       0  5440.3    .035       0
  5637.4     .05       0    6062     .07       0  6086.9     .05       0
Bank Sta=4997.4,5022.5
XS Rating Curve= 0 ,0
Exp/Cntr=0.3,0.1

Type RM Length L Ch R = 1 ,29597   ,1117,1117,1117
BEGIN DESCRIPTION:
X18859
END DESCRIPTION:
XS GIS Cut Line= 3
      2494338.69     13673375.84      2493023.61     13671813.37
      2489899.33     13670980.23
#Sta/Elev= 30
  2856.8  254.76  3202.9  231.58  3340.2  224.07  3860.3  219.25  4063.6  219.44
  4349.9  218.43  4364.3  214.29  4407.2  218.75  4653.5  219.06  4740.2  217.89
  4762.3  214.31  4818.5   219.3  4952.7  219.06  4967.9  212.97  4968.4  212.47
    4993  212.97  5001.1  218.04  5027.8   219.1    5754  220.68  5813.4  221.78
  5855.1  221.35  6461.6   231.6  6562.7   232.4  6844.5  236.25  7149.6  240.68
  7340.1  239.28  7674.7  247.23  7701.8  245.06  7775.8   248.5  8132.5  260.21
#Mann= 18 ,-1 , 0
  2856.8     .07       0  3202.9     .12       0  3340.2     .05       0
  3860.3     .07       0  4063.6      .1       0  4349.9     .07       0
  4653.5     .12       0  4967.9     .05       0    4993     .12       0
    5754     .05       0  5813.4     .07       0  5855.1     .05       0
  6461.6    .035       0  6562.7     .05       0  6844.5    .035       0
  7149.6     .07       0  7674.7    .035       0  7775.8     .07       0
Bank Sta=4967.9,4993
XS Rating Curve= 0 ,0
Exp/Cntr=0.3,0.1

Type RM Length L Ch R = 1 ,28480   ,613,613,613
BEGIN DESCRIPTION:
X18858
END DESCRIPTION:
XS GIS Cut Line= 3
      2494937.71     13672881.11      2493218.93     13671526.91
      2490341.29     13670615.45
#Sta/Elev= 30
  3386.3  250.31  3563.7  239.35  3698.4  242.27  4016.4  234.89  4270.4  225.03
  4923.5   217.4  4980.5  212.24    4981  211.74  5007.4  212.24  5008.4  216.16
  5022.9  217.23  5101.5  214.68  5165.6  219.78  5472.6  219.11    5575  218.87
  5757.2  218.42  5994.7  219.49  6020.5   219.6  6206.4  219.87    6644  223.27
  6679.4  223.58  7069.4  226.33  7158.9  226.81  7350.6  227.88  7452.9  229.14
  7555.2  230.42  7787.5  232.98  7835.8  233.92  8169.5  238.14    8593  261.92
#Mann= 20 ,-1 , 0
  3386.3     .07       0  4016.4     .12       0  4270.4      .1       0
  4980.5     .05       0  5007.4      .1       0  5472.6     .12       0
    5575      .1       0  5757.2     .12       0  5994.7     .07       0
  6020.5     .12       0  6206.4     .07       0    6644    .035       0
  6679.4     .05       0  7069.4     .07       0  7158.9     .05       0
  7350.6     .07       0  7452.9     .05       0  7555.2     .07       0
  7787.5     .05       0  7835.8     .07       0
Bank Sta=4980.5,5007.4
XS Rating Curve= 0 ,0
Exp/Cntr=0.3,0.1

Type RM Length L Ch R = 1 ,27867   ,675,675,675
BEGIN DESCRIPTION:
DENTON CREEK 20.0
END DESCRIPTION:
XS GIS Cut Line= 3
      2494885.58     13672633.66        2494075.       13671525.
      2490380.35     13670420.13
#Sta/Elev= 30
  3626.5  249.99  3724.9   248.5  3869.8  246.16  3934.5  239.66    4164  240.14
    4346  232.45  4487.5  220.79  4806.5   219.2  4850.4     214  4977.9  216.58
  4983.3  211.05  4983.8  210.55  5010.3  211.05  5016.4  215.76    5146   218.8
  5413.2  217.74  5718.8   218.7  6027.6  220.17  6126.2  220.12  6592.2  220.35
  6863.4  222.95  7144.8  225.34  7243.2  226.36  7348.5   226.5  7605.5  227.21
    7743  228.57  7841.3  229.48  8078.1  231.54  8392.1  234.53  8856.2  258.12
#Mann= 20 ,-1 , 0
  3626.5    .035       0  3724.9     .07       0    4164     .07       0
    4346     .12       0  4487.5      .1       0  4983.3     .05       0
  5010.3      .1       0  5413.2     .07       0  5718.8      .1       0
  6027.6     .12       0  6126.2     .12       0  6592.2     .07       0
  6863.4     .07       0  7144.8    .035       0  7243.2      .1       0
  7348.5     .07       0  7605.5     .05       0    7743     .07       0
  7841.3     .05       0  8078.1     .07       0
Bank Sta=4983.3,5010.3
XS Rating Curve= 0 ,0
Exp/Cntr=0.3,0.1

Type RM Length L Ch R = 1 ,27192   ,784,784,784
BEGIN DESCRIPTION:
DENTON CREEK 19.0
END DESCRIPTION:
XS GIS Cut Line= 3
      2494925.01     13672325.03      2494547.05     13671253.48
      2493075.69     13669144.09
#Sta/Elev= 30
  3683.6  247.59  3736.6  247.35  3768.5  239.83  3786.6  238.52  4039.1  230.05
  4192.3  224.59  4296.6  220.26  4431.2  218.87  4648.6  219.47  4678.3  217.32
  4701.6  215.31    4781  217.89  4930.5  217.37  5021.8  215.41  5042.7  211.17
  5057.6  214.67  5072.3  213.87  5072.7   210.9  5073.2   210.4  5099.7   210.9
  5114.3  217.25  5135.2  218.44  5316.7  214.57  5343.7  216.82  5444.1  216.32
  5615.9  216.36  6415.2  222.42    6728  230.69  7003.9  240.25  7391.7  255.22
#Mann= 13 ,-1 , 0
  3683.6     .05       0  4039.1     .07       0  4192.3     .12       0
  4431.2      .1       0  4678.3     .12       0  4930.5      .1       0
  5072.3     .12       0  5072.7     .05       0  5099.7     .12       0
  5444.1     .07       0  5615.9     .05       0    6728     .07       0
  7003.9     .05       0
Bank Sta=5072.7,5099.7
XS Rating Curve= 0 ,0
Exp/Cntr=0.3,0.1