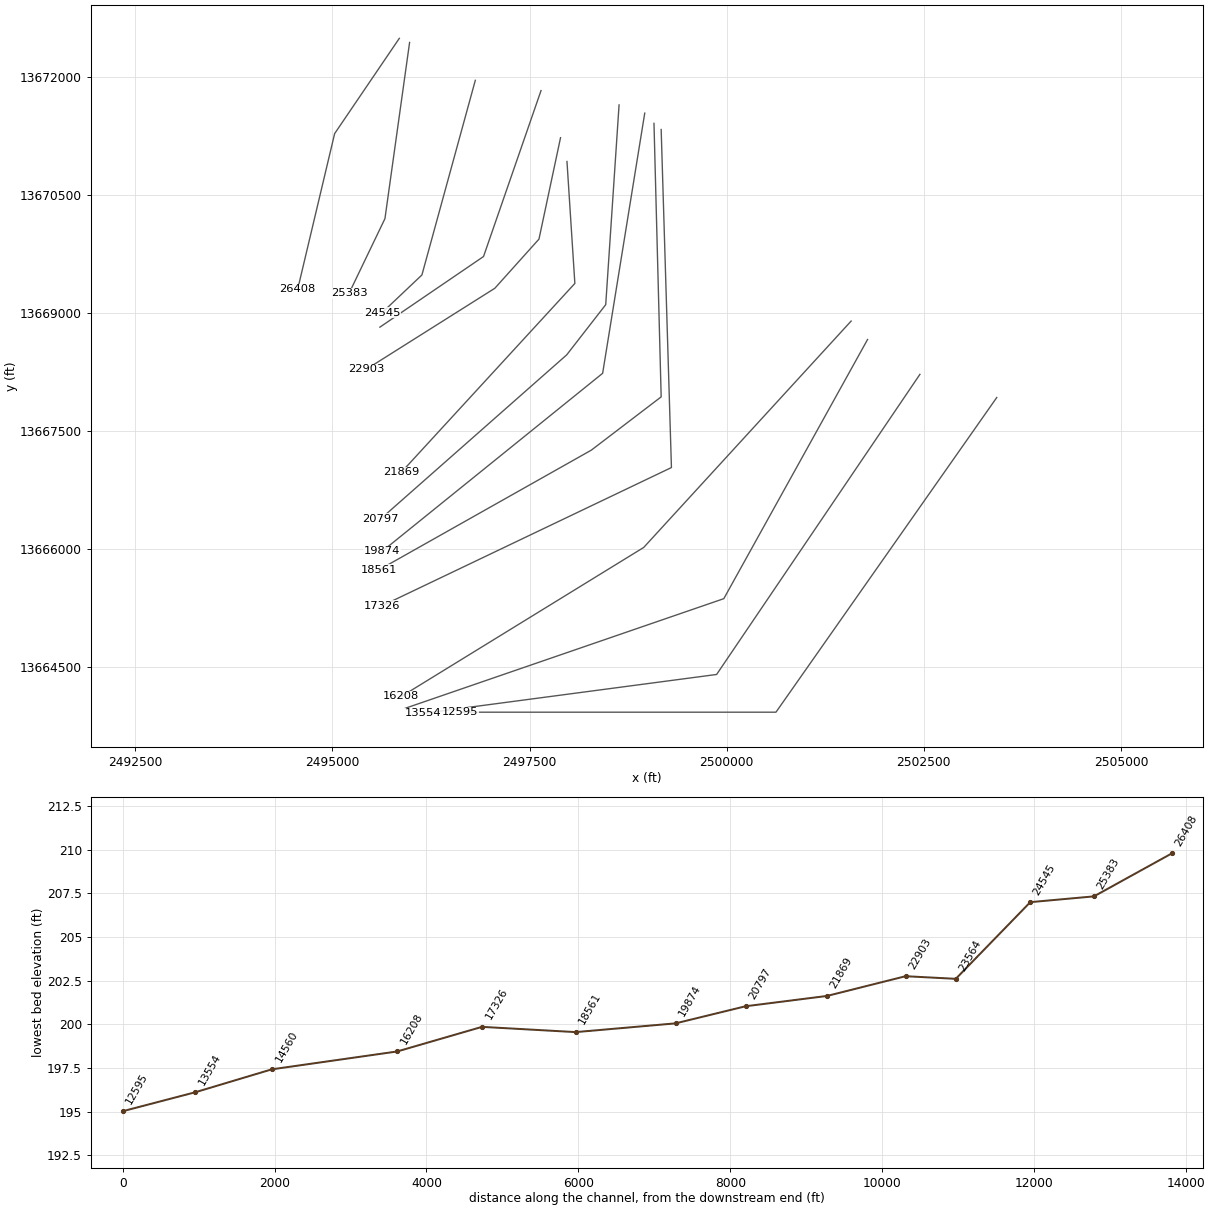
HEC-RAS study DENTON CREEK.prj: DENTON CREEK Base Level Engineering

--- DENTON CREEK.g01 (geometry) --- (continued)

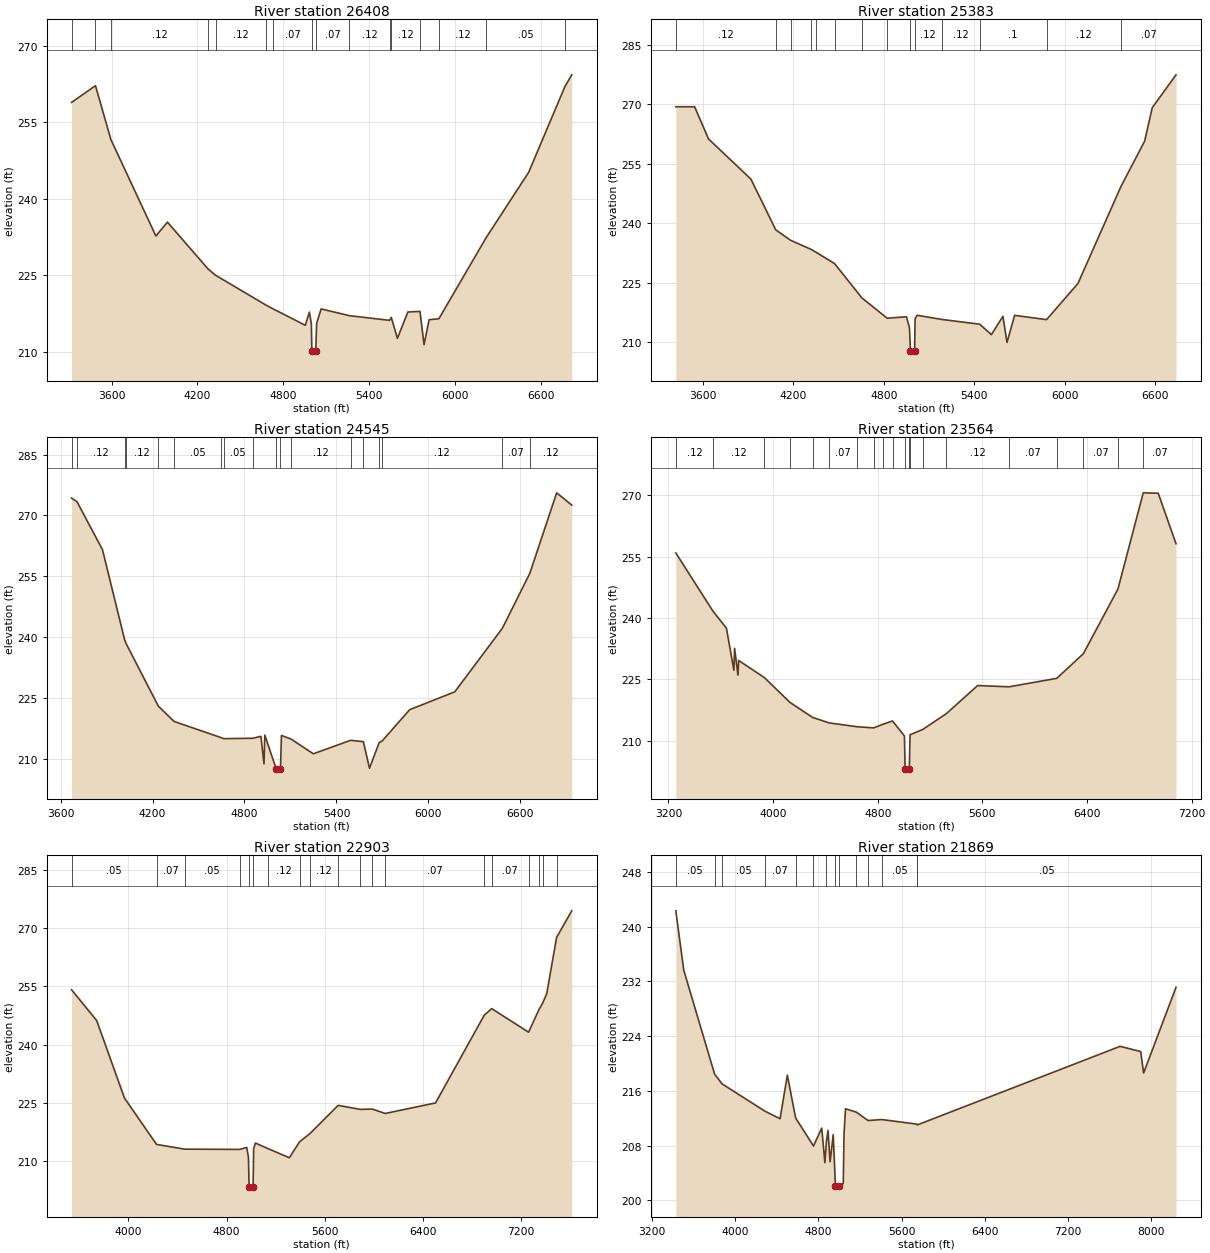
Type RM Length L Ch R = 1 ,26408   ,1025,1025,1025
BEGIN DESCRIPTION:
DENTON CREEK 18.0
END DESCRIPTION:
XS GIS Cut Line= 3
      2495849.12     13672490.43      2495028.82     13671279.52
      2494560.08     13669300.37
#Sta/Elev= 30
  3320.6  258.93  3487.9  262.21  3595.7  251.65  3910.2  232.74    3991  235.46
  4276.1  226.24  4326.9  225.06    4679  219.21  4729.2  218.46  4954.5  215.24
  4983.1  217.81  4996.8  215.59  5000.4  210.28  5000.9  209.78  5027.5  210.28
  5033.9  215.64  5065.3  218.45  5263.4  217.12  5543.6  216.21  5555.8  216.78
  5598.5  212.69  5671.6  217.84  5756.3  217.96  5784.7  211.43  5820.1  216.33
  5888.3  216.52  6220.4  232.49  6516.6  245.26  6769.5  262.05  6817.1  264.34
#Mann= 16 ,-1 , 0
  3320.6     .12       0  3487.9     .07       0  3595.7     .12       0
  4276.1     .07       0  4326.9     .12       0    4679     .05       0
  4729.2     .07       0  5000.4     .05       0  5027.5     .07       0
  5263.4     .12       0  5543.6      .1       0  5555.8     .12       0
  5756.3      .1       0  5888.3     .12       0  6220.4     .05       0
  6769.5     .07       0
Bank Sta=5000.4,5027.5
XS Rating Curve= 0 ,0
Exp/Cntr=0.3,0.1

Type RM Length L Ch R = 1 ,25383   ,838,838,838
BEGIN DESCRIPTION:
DENTON CREEK 17.0
END DESCRIPTION:
XS GIS Cut Line= 3
      2495979.34     13672438.36      2495666.84     13670198.79
      2495211.54     13669249.16
#Sta/Elev= 30
  3422.4   269.4    3547   269.4  3638.8   261.3  3919.8  251.18  4084.7  238.38
  4184.5  235.72  4317.1   233.5  4349.3  232.79  4474.2  229.89  4655.3  221.24
  4822.7  216.12  4950.4  216.48  4970.6  213.73  4977.2  207.82  4977.7  207.32
  5004.5  207.82  5007.8  215.96  5021.1  216.86    5187   215.8  5435.5  214.61
  5513.5  211.97    5590   216.6  5616.8  210.01  5667.3  216.84    5879  215.76
  6087.1  224.88  6372.9  249.39  6528.7  260.72  6579.5  269.19  6736.8  277.45
#Mann= 14 ,-1 , 0
  3422.4     .12       0  4084.7     .05       0  4184.5     .07       0
  4317.1     .05       0  4349.3     .07       0  4474.2     .12       0
  4655.3     .05       0  4822.7     .12       0  4977.2     .05       0
  5004.5     .12       0    5187     .12       0  5435.5      .1       0
    5879     .12       0  6372.9     .07       0
Bank Sta=4977.2,5004.5
XS Rating Curve= 0 ,0
Exp/Cntr=0.3,0.1

Type RM Length L Ch R = 1 ,24545   ,981,981,981
BEGIN DESCRIPTION:
DENTON CREEK 16.0
END DESCRIPTION:
XS GIS Cut Line= 3
      2496812.67     13671956.58      2496135.59     13669482.64
      2495628.87      13669001.9
#Sta/Elev= 30
  3671.7  274.27  3706.9  273.41  3873.4  261.57  4017.8  239.38  4029.5  238.29
  4237.9     223  4340.8  219.23  4649.5  215.22  4663.1  214.99  4855.4  215.09
  4907.1  215.57  4927.3   208.8  4932.5  215.87  5007.4  207.49  5007.9  206.99
  5034.8  207.49  5041.1  215.78  5102.6  214.92  5249.2  211.26  5492.1  214.58
  5575.7  214.25  5615.5   207.7  5678.6  214.01  5698.9  214.45  5877.7  222.13
    6172  226.53  6482.2  242.18  6661.9  255.76  6836.6  275.57  6935.1  272.56
#Mann= 18 ,-1 , 0
  3671.7     .07       0  3706.9     .12       0  4017.8     .07       0
  4029.5     .12       0  4237.9     .07       0  4340.8     .05       0
  4649.5     .07       0  4663.1     .05       0  4855.4      .1       0
  5007.4     .05       0  5034.8      .1       0  5102.6     .12       0
  5492.1      .1       0  5575.7    .035       0  5678.6      .1       0
  5698.9     .12       0  6482.2     .07       0  6661.9     .12       0
Bank Sta=5007.4,5034.8
XS Rating Curve= 0 ,0
Exp/Cntr=0.3,0.1

Type RM Length L Ch R = 1 ,23564   ,661,661,661
BEGIN DESCRIPTION:
X18856
END DESCRIPTION:
XS GIS Cut Line= 3
      2497646.02     13671826.43      2496916.84     13669717.02
       2495602.8     13668819.31
#Sta/Elev= 30
  3256.8  255.87  3540.9  241.65  3643.5  237.52  3700.6  227.23  3705.9   232.6
  3731.8  226.03    3737  229.63  3933.5  225.44  4129.3  219.38    4303   215.7
  4429.6  214.37  4642.5  213.44  4768.8  213.16  4839.6  214.04  4913.1  214.85
  5004.1  211.19  5009.4   203.1  5009.9   202.6  5041.2   203.1  5047.2  211.47
  5144.9  212.79  5325.6  216.66  5563.6  223.49  5804.3  223.19  6168.6  225.26
  6372.1  231.28    6636  247.05  6829.6  270.55  6944.2  270.44  7080.1  258.12
#Mann= 20 ,-1 , 0
  3256.8     .12       0  3540.9     .12       0  3933.5     .05       0
  4129.3     .07       0    4303     .05       0  4429.6     .07       0
  4642.5      .1       0  4768.8     .07       0  4839.6      .1       0
  4913.1     .07       0  5009.4     .05       0  5041.2     .07       0
  5047.2     .12       0  5144.9     .07       0  5325.6     .12       0
  5804.3     .07       0  6168.6     .12       0  6372.1     .07       0
    6636     .12       0  6829.6     .07       0
Bank Sta=5009.4,5041.2
XS Rating Curve= 0 ,0
Exp/Cntr=0.3,0.1

Type RM Length L Ch R = 1 ,22903   ,1034,1034,1034
BEGIN DESCRIPTION:
X18857
END DESCRIPTION:
XS GIS Cut Line= 4
      2497893.41     13671227.44      2497619.97     13669938.37
      2497060.07     13669313.37      2495432.45     13668284.71
#Sta/Elev= 30
  3535.3  254.11  3740.8  246.16  3967.1  226.22  4228.8  214.27  4458.2  213.05
    4908  212.98    4965  213.49    4979  210.98  4984.7  203.25  4985.2  202.75
  5016.7  203.25  5021.6   213.2  5035.8  214.62  5135.5  213.23  5312.5  210.84
  5396.9  214.96  5480.1  217.04  5711.1  224.32  5892.8  223.29  5988.9  223.38
  6095.2  222.24  6505.9  224.95  6904.3   247.6  6964.7  249.25  7265.2  243.17
  7350.7  249.04  7379.6  250.63  7413.5  253.11    7494  267.59  7617.6  274.44
#Mann= 19 ,-1 , 0
  3535.3     .05       0  4228.8     .07       0  4458.2     .05       0
    4908      .1       0  4984.7     .05       0  5016.7      .1       0
  5135.5     .12       0  5396.9     .05       0  5480.1     .12       0
  5711.1     .05       0  5892.8     .07       0  5988.9     .12       0
  6095.2     .07       0  6904.3     .05       0  6964.7     .07       0
  7265.2    .035       0  7350.7     .07       0  7379.6     .05       0
    7494     .07       0
Bank Sta=4984.7,5016.7
XS Rating Curve= 0 ,0
Exp/Cntr=0.3,0.1

Type RM Length L Ch R = 1 ,21869   ,1072,1072,1072
BEGIN DESCRIPTION:
DENTON CREEK 15.0
END DESCRIPTION:
XS GIS Cut Line= 3
        2497975.     13670925.03        2498075.       13669375.
      2495875.01     13666975.02
#Sta/Elev= 30
  3430.1  242.34  3506.5  233.65  3802.8  218.45  3873.8  217.03  4286.6  213.03
  4432.2  211.92  4502.4   218.3  4582.1  212.03  4753.4  207.93    4833  210.55
  4863.1   205.5  4877.7  208.56  4893.2   210.2  4913.2  205.63  4943.3  209.59
  4964.8  202.12  4965.3  201.62    4997  202.12  5039.8  202.43  5047.2  209.67
  5061.4  213.38    5165  212.89  5277.9  211.66    5411   211.8  5747.9  211.13
  5750.9  211.01  7701.1  222.51  7899.7  221.75  7927.4  218.61  8239.1  231.15
#Mann= 14 ,-1 , 0
  3430.1     .05       0  3802.8     .07       0  3873.8     .05       0
  4286.6     .07       0  4582.1     .05       0  4753.4     .07       0
  4877.7      .1       0  4964.8     .05       0    4997      .1       0
    5165     .07       0  5277.9     .12       0    5411     .05       0
  5747.9     .12       0  5750.9     .05       0
Bank Sta=4964.8,4997
XS Rating Curve= 0 ,0
Exp/Cntr=0.3,0.1

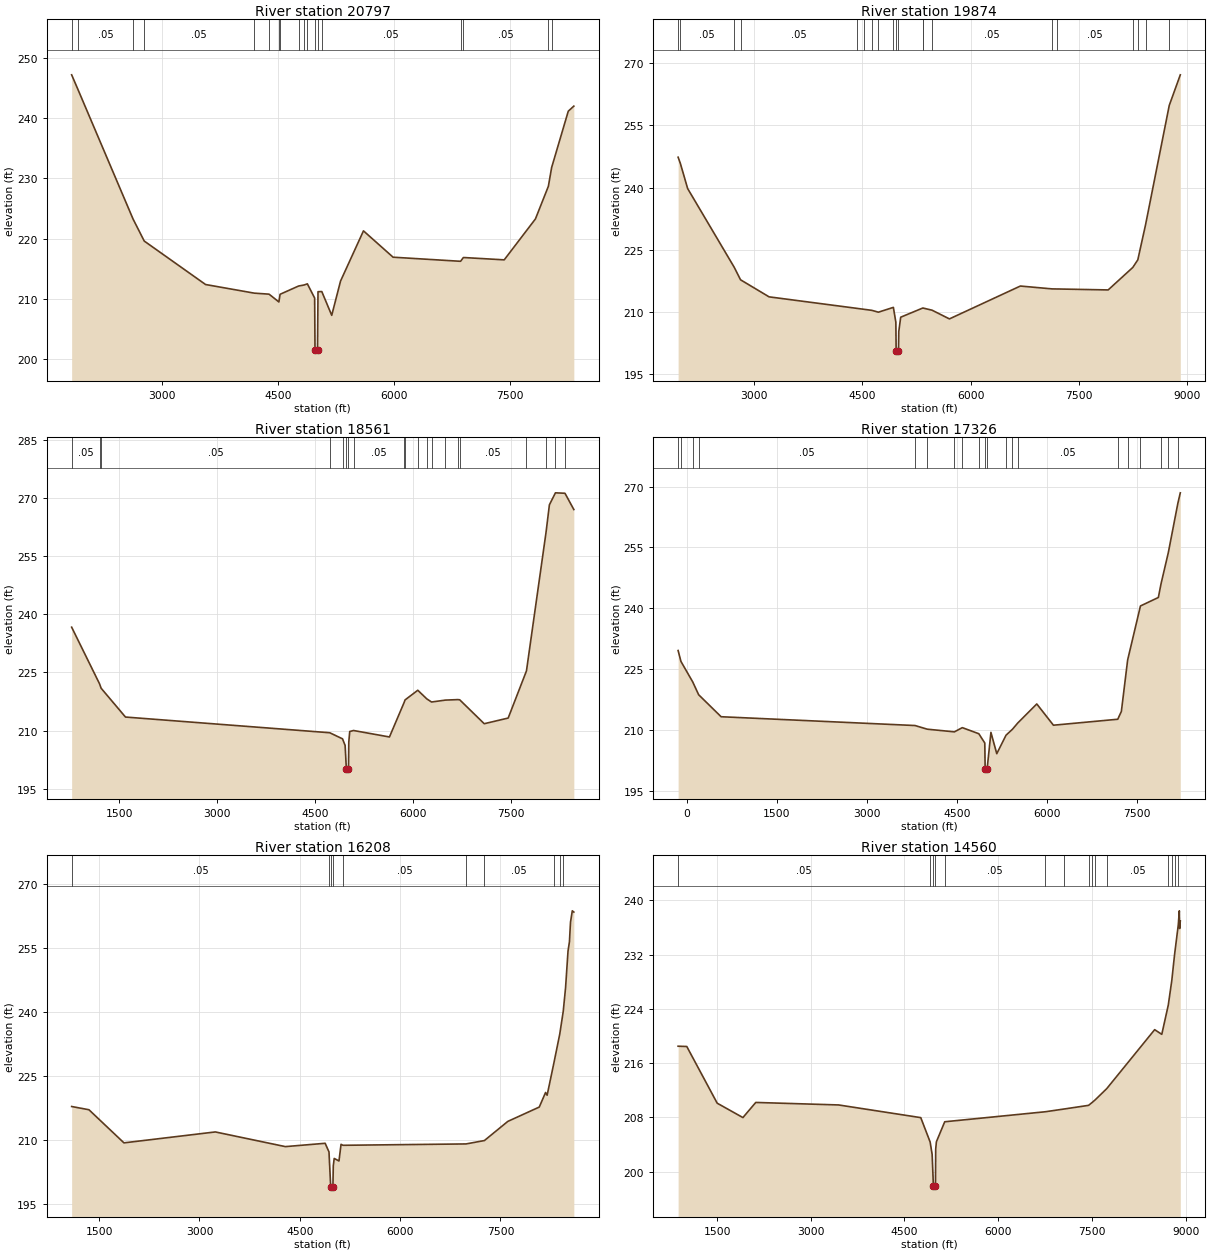
Type RM Length L Ch R = 1 ,20797   ,923,923,923
BEGIN DESCRIPTION:
X18855
END DESCRIPTION:
XS GIS Cut Line= 4
      2498635.59     13671644.08      2498466.32     13669105.04
      2497971.53     13668467.02      2495614.72     13666383.65
#Sta/Elev= 30
  1834.1  247.19  1913.7  244.82  2628.4  223.28  2773.3  219.62  3566.9  212.41
  4196.5  210.98  4388.2  210.81  4515.6  209.52  4531.1  210.79  4770.5  212.16
    4841  212.33  4884.1  212.52  4978.2  210.17  4982.9  201.53  4983.4  201.03
  5015.1  201.53  5021.7  211.22  5070.8  211.24  5199.2   207.3    5313  212.97
  5609.9  221.31    5993  216.94  6866.4  216.26  6902.9  216.89  7430.9   216.5
    7835  223.29  8002.5  228.71  8044.4  231.81  8259.9  241.16  8331.8     242
#Mann= 18 ,-1 , 0
  1834.1     .12       0  1913.7     .05       0  2628.4    .035       0
  2773.3     .05       0  4196.5     .07       0  4388.2     .05       0
  4515.6     .07       0  4531.1     .05       0  4770.5     .07       0
    4841     .05       0  4884.1     .07       0  4982.9     .05       0
  5015.1     .07       0  5070.8     .05       0  6866.4    .035       0
  6902.9     .05       0  8002.5    .035       0  8044.4     .05       0
Bank Sta=4982.9,5015.1
XS Rating Curve= 0 ,0
Exp/Cntr=0.3,0.1

Type RM Length L Ch R = 1 ,19874   ,1313,1313,1313
BEGIN DESCRIPTION:
X18854
END DESCRIPTION:
XS GIS Cut Line= 3
      2498961.11     13671539.92      2498427.26     13668232.64
      2495628.86     13665967.89
#Sta/Elev= 30
  1951.4  247.33  1983.1   245.8  2083.4  239.76  2727.1  220.79  2815.3  217.75
  3210.4  213.63  4426.8  210.85  4522.5  210.63  4633.8  210.37  4722.8  209.93
  4930.5  211.09  4964.8  207.51  4968.9  200.55  4969.4  200.05  5001.3  200.55
  5005.3  205.27    5032  208.72  5338.4  210.94    5343  210.92  5465.9  210.41
  5706.4  208.31    6688  216.24  7127.4  215.55  7200.2  215.53  7903.1   215.3
  8243.6  220.72  8313.4  222.56  8420.8  231.04  8748.6  259.83  8901.5  267.21
#Mann= 20 ,-1 , 0
  1951.4     .07       0  1983.1     .05       0  2727.1     .07       0
  2815.3     .05       0  4426.8     .05       0  4522.5     .07       0
  4633.8     .05       0  4722.8     .07       0  4930.5     .12       0
  4968.9     .05       0  5001.3     .12       0  5338.4     .05       0
    5343     .07       0  5465.9     .05       0  7127.4    .035       0
  7200.2     .05       0  8243.6    .035       0  8313.4     .05       0
  8420.8     .07       0  8748.6     .05       0
Bank Sta=4968.9,5001.3
XS Rating Curve= 0 ,0
Exp/Cntr=0.3,0.1

Type RM Length L Ch R = 1 ,18561   ,1235,1235,1235
BEGIN DESCRIPTION:
X18853
END DESCRIPTION:
XS GIS Cut Line= 4
       2499078.3     13671409.71      2499169.45     13667933.16
      2498284.03     13667256.08      2495589.36       13665733.
#Sta/Elev= 30
   771.6  236.68  1198.4  222.08  1223.1  220.93  1595.6   213.5  4722.9  209.45
  4918.3  207.88    4958  206.18  4977.2  200.05  4977.7  199.55  5009.6  200.05
  5014.2  207.05  5028.7  209.77  5086.7  210.03  5636.7  208.36  5859.8   217.2
  5875.7  217.92  6070.5  220.41  6209.5  218.17  6281.3  217.38    6492  217.87
  6682.9     218  6712.1  217.95  7087.5  211.78  7454.2  213.24    7734   225.4
    8034  261.18  8085.2  268.25  8177.7  271.34  8323.5  271.23  8459.3  267.03
#Mann= 20 ,-1 , 0
   771.6     .05       0  1198.4     .07       0  1223.1     .05       0
  4722.9     .07       0  4918.3      .1       0  4977.2     .05       0
  5009.6      .1       0  5086.7     .05       0  5859.8    .035       0
  5875.7     .05       0  6070.5    .035       0  6209.5     .05       0
  6281.3    .035       0    6492     .05       0  6682.9    .035       0
  6712.1     .05       0    7734     .07       0    8034     .05       0
  8177.7     .07       0  8323.5     .05       0
Bank Sta=4977.2,5009.6
XS Rating Curve= 0 ,0
Exp/Cntr=0.3,0.1

Type RM Length L Ch R = 1 ,17326   ,1118,1118,1118
BEGIN DESCRIPTION:
DENTON CREEK 14.0
END DESCRIPTION:
XS GIS Cut Line= 3
      2499169.45     13671331.55      2499299.66     13667034.73
      2495624.98     13665274.99
#Sta/Elev= 30
  -147.8  229.58  -100.7   226.9    96.2  221.83   194.7  218.68   569.1  213.26
  3802.8  211.09  4006.2  210.19  4458.5  209.53  4590.6  210.57  4865.9  209.07
  4965.5  206.78  4971.5  200.35    4972  199.85    5004  200.35  5067.9   209.4
  5165.1  204.15  5319.7  208.71  5427.4  210.18  5514.1   211.7  5832.4  216.41
  6109.9  211.17  7182.3  212.64  7242.7  214.57  7347.3  227.25  7560.8  240.57
  7859.4  242.66  7903.4  245.99  8026.2  253.77  8184.7  265.89  8225.3  268.46
#Mann= 20 ,-1 , 0
  -147.8     .07       0  -100.7     .05       0    96.2     .07       0
   194.7     .05       0  3802.8    .035       0  4006.2     .05       0
  4458.5    .035       0  4590.6     .05       0  4865.9      .1       0
  4971.5     .05       0    5004      .1       0  5319.7     .05       0
  5427.4    .035       0  5514.1     .05       0  7182.3     .07       0
  7347.3     .05       0  7560.8     .07       0  7903.4     .12       0
  8026.2     .05       0  8184.7     .07       0
Bank Sta=4971.5,5004
XS Rating Curve= 0 ,0
Exp/Cntr=0.3,0.1

Type RM Length L Ch R = 1 ,16208   ,1648,1648,1648
BEGIN DESCRIPTION:
DENTON CREEK 13.0
END DESCRIPTION:
XS GIS Cut Line= 3
      2501578.28     13668896.68      2498948.09      13666019.1
      2495875.02     13664125.01
#Sta/Elev= 30
  1089.3   217.8  1347.9  217.04  1871.5  209.28  3237.4  211.84  4285.2   208.4
  4879.7  209.18  4936.9  207.15  4962.6  198.94  4963.1  198.44  4995.5  198.94
  5001.2  203.89  5014.9  205.63  5086.3  205.04  5117.1  208.94  5146.6  208.71
  6985.9  209.03  7260.3  209.82  7610.7  214.31  8080.9  217.67  8174.8  221.08
  8198.3  220.44  8302.2   228.2  8387.6  234.81  8439.3  240.11  8474.1  245.65
  8510.8  254.22  8532.1  256.41  8547.5  260.95  8574.6  263.65  8597.7  263.36
#Mann= 10 ,-1 , 0
  1089.3     .05       0  4936.9      .1       0  4962.6     .05       0
  4995.5      .1       0  5146.6     .05       0  6985.9     .07       0
  7260.3     .05       0  8302.2    .035       0  8387.6     .05       0
  8439.3     .07       0
Bank Sta=4962.6,4995.5
XS Rating Curve= 0 ,0
Exp/Cntr=0.3,0.1

Type RM Length L Ch R = 1 ,14560   ,1006,1006,1006
BEGIN DESCRIPTION:
DENTON CREEK 12.0
END DESCRIPTION:
XS GIS Cut Line= 3
      2501786.63     13668662.32      2499963.72     13665368.06
      2495925.01       13663975.
#Sta/Elev= 30
   877.2  218.49  1015.9  218.45  1502.7  210.09  1914.2  207.97  2119.9   210.2
  3445.6  209.83  4760.7  207.96  4910.6  204.37  4942.6  202.55  4962.8  197.92
  4963.4  197.42  4995.8  197.92  4999.7  203.32  5011.1  204.41  5144.1  207.35
  6756.6  208.83    7053  209.23  7445.9  209.77  7505.4  210.21  7550.8  210.57
  7737.4  212.24  8503.8  220.93    8618  220.24  8721.7  224.54  8778.8  228.22
  8821.7  231.92  8881.9  236.37  8898.8  238.45  8904.1  235.84  8914.4  236.96
#Mann= 15 ,-1 , 0
   877.2     .05       0  4910.6      .1       0  4962.8     .05       0
  4995.8      .1       0  5144.1     .05       0  6756.6     .07       0
    7053     .12       0  7445.9     .07       0  7505.4     .05       0
  7550.8     .07       0  7737.4     .05       0  8721.7    .035       0
  8778.8     .05       0  8821.7    .035       0  8881.9     .05       0
Bank Sta=4962.8,4995.8
XS Rating Curve= 0 ,0
Exp/Cntr=0.3,0.1

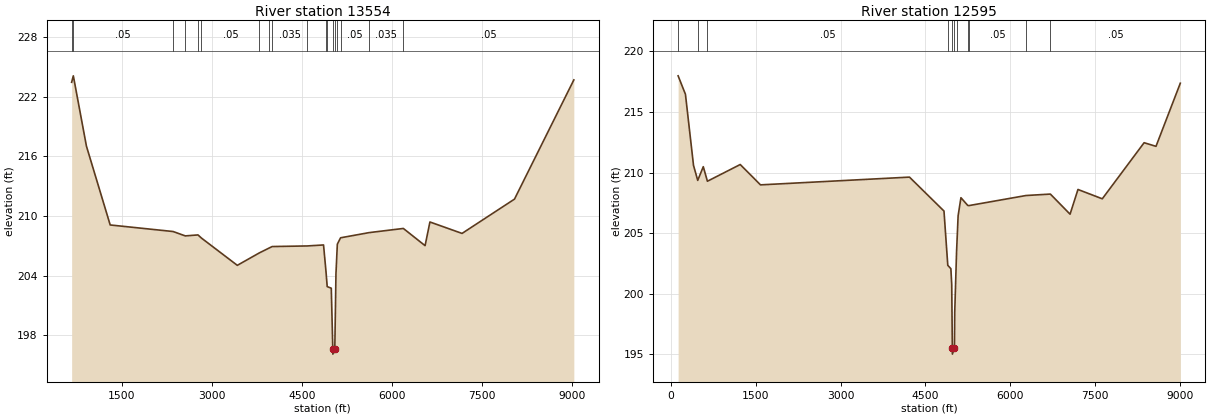
Type RM Length L Ch R = 1 ,13554   ,959,959,959
BEGIN DESCRIPTION:
DENTON CREEK 11.0
END DESCRIPTION:
XS GIS Cut Line= 3
      2502450.71     13668219.64      2499872.57     13664404.52
      2496150.34     13663909.95
#Sta/Elev= 30
     664  223.45     692   224.1   910.1  217.03  1305.7   209.1  2353.3  208.44
  2556.2     208  2767.1   208.1  2825.3  207.78  3421.6  205.04  3787.9  206.29
  3951.3  206.78  4002.1  206.93  4586.1  206.99    4857  207.09  4898.2  204.39
    4918   202.9  4985.9  202.74  5011.3  196.61  5011.9  196.11  5044.4  196.61
  5063.8  204.19  5086.7  207.17  5140.6  207.81    5615  208.33  6185.5  208.75
  6547.3  207.02    6628   209.4  7162.6  208.25  8035.7   211.7  9023.5  223.69
#Mann= 18 ,-1 , 0
     664    .035       0     692     .05       0  2353.3    .035       0
  2556.2     .05       0  2767.1    .035       0  2825.3     .05       0
  3787.9    .035       0  3951.3     .05       0  4002.1    .035       0
  4586.1     .05       0  4898.2     .07       0    4918     .12       0
  5011.3     .05       0  5044.4     .12       0  5086.7     .12       0
  5140.6     .05       0    5615    .035       0  6185.5     .05       0
Bank Sta=5011.3,5044.4
XS Rating Curve= 0 ,0
Exp/Cntr=0.3,0.1

Type RM Length L Ch R = 1 ,12595   ,0,0,0
BEGIN DESCRIPTION:
DENTON CREEK 10.0
END DESCRIPTION:
XS GIS Cut Line= 3
      2503424.99     13667924.99        2500625.       13663925.
        2496625.       13663925.
#Sta/Elev= 30
   125.3  217.99   254.8  216.47   397.7   210.6   472.1  209.36   570.4  210.49
   643.6  209.29  1223.9  210.67  1582.7  208.99  4217.5  209.63  4827.9  206.83
  4895.3  202.35  4949.9  202.07  4964.7  200.77  4975.8  195.52  4976.8  195.02
  5012.9  195.52  5017.9  198.45  5050.2  203.45  5077.9  206.44  5127.9  207.93
    5249  207.29  5269.9  207.28  6277.4  208.11  6709.7  208.23  7057.9  206.57
  7197.9  208.61  7627.9  207.84  8367.9  212.47  8577.9  212.17  9007.9  217.38
#Mann= 11 ,-1 , 0
   125.3    .045       0   472.1    .035       0   643.6     .05       0
  4895.3     .12       0  4975.8     .05       0  5012.9     .12       0
  5050.2     .05       0    5249     .07       0  5269.9     .05       0
  6277.4    .035       0  6709.7     .05       0
Bank Sta=4975.8,5012.9
XS Rating Curve= 0 ,0
Exp/Cntr=0.3,0.1

Chan Stop Cuts=-1
Use User Specified Reach Order=0
Composite Channel Slope=5