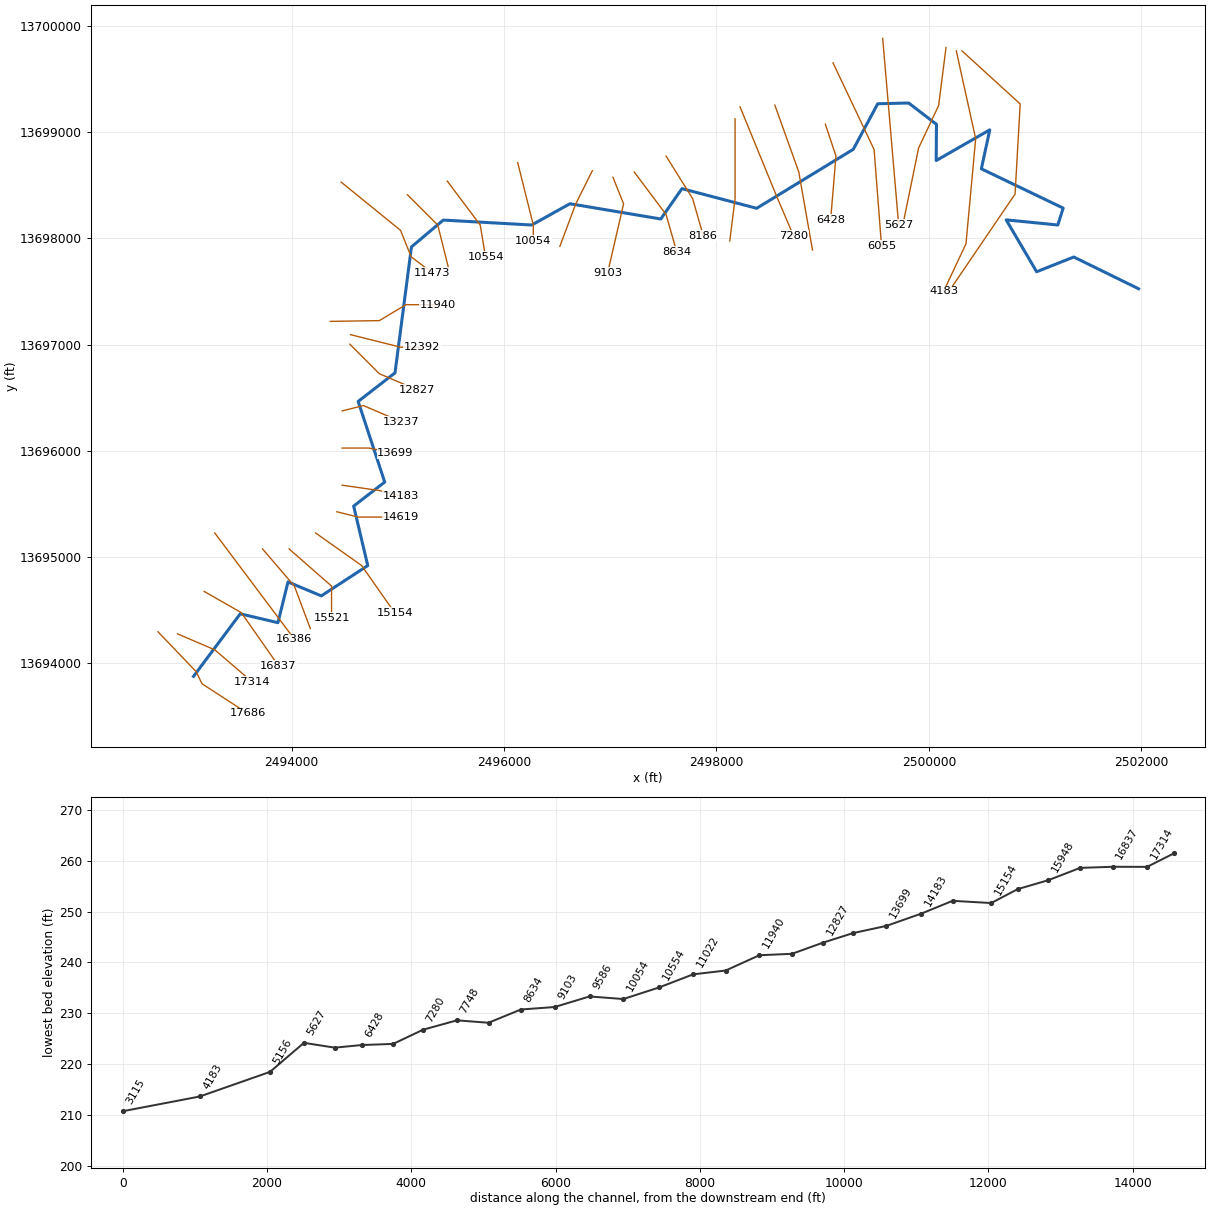
--- FREEMAN CREEK.prj (project) ---

Proj Title=FREEMAN CREEK Base Level Engineering
Current Plan=p01
Default Exp/Contr=0.3,0.1
English Units
Geom File=g01
Flow File=f01
Plan File=p01
Y Axis Title=Elevation
X Axis Title(PF)=Main Channel Distance
X Axis Title(XS)=Station
BEGIN DESCRIPTION:
FREEMAN CREEK
END DESCRIPTION:
DSS Export Rating Curves= 0
DSS Export Rating Curve Sorted= 0
DSS Export Volume Flow Curves= 0
DXF OffsetX= 0
DXF OffsetY= 0
DXF ScaleX= 1
DXF ScaleY= 10

--- FREEMAN CREEK.p01 (plan) ---

Plan Title=Multiple Run
Short Identifier=Multiple
Geom File=g01
Flow File=f01
Subcritical Flow
K Sum by GR= 0
Std Step Tol= 0.01
Critical Tol= 0.01
Num of Std Step Trials= 20
Max Error Tol= 0.3
Flow Tol Ratio= 0.001
Split Flow NTrial= 30
Split Flow Tol= 0.02
Split Flow Ratio= 0.02
Log Output Level= 0
Friction Slope Method= 1
Unsteady Friction Slope Method= 2
Unsteady Bridges Friction Slope Method= 1
Parabolic Critical Depth
Global Vel Dist=  1 , 1 , 1
Global Log Level= 0
CheckData=True
Encroach Param= -1, 0, 0, 0
BEGIN DESCRIPTION:
Multiple Run
END DESCRIPTION:

--- FREEMAN CREEK.f01 (steady flow) ---

Flow Title=Multiple
Number of Profiles=7
Profile Names=10-year,25-year,50-year,1pct_min,100-year,1pct_plu,500-year
River Rch & RM= FREEMAN CREEK,Reach-1,17686
     679    1091    1462     949    1893    3777    3142
River Rch & RM= FREEMAN CREEK,Reach-1,17314
    1136    1881    2572    1700    3392    6767    5845
River Rch & RM= FREEMAN CREEK,Reach-1,16837
    1198    1978    2699    1779    3550    7083    6085
River Rch & RM= FREEMAN CREEK,Reach-1,11473
    1505    2512    3453    2291    4570    9119    7937
River Rch & RM= FREEMAN CREEK,Reach-1,9103
    1734    2893    3975    2634    5256   10488    9107
Boundary for River Rch & Prof#=FREEMAN CREEK,Reach-1,1
Up Type=0
Dn Type=3
Dn Slope=0.005
Boundary for River Rch & Prof#=FREEMAN CREEK,Reach-1,2
Up Type=0
Dn Type=3
Dn Slope=0.005
Boundary for River Rch & Prof#=FREEMAN CREEK,Reach-1,3
Up Type=0
Dn Type=3
Dn Slope=0.005
Boundary for River Rch & Prof#=FREEMAN CREEK,Reach-1,4
Up Type=0
Dn Type=3
Dn Slope=0.005
Boundary for River Rch & Prof#=FREEMAN CREEK,Reach-1,5
Up Type=0
Dn Type=3
Dn Slope=0.005
Boundary for River Rch & Prof#=FREEMAN CREEK,Reach-1,6
Up Type=0
Dn Type=3
Dn Slope=0.005
Boundary for River Rch & Prof#=FREEMAN CREEK,Reach-1,7
Up Type=0
Dn Type=3
Dn Slope=0.005

--- FREEMAN CREEK.g01 (geometry) ---

Geom Title=Existing Conditions
Program Version=4.10

River Reach=FREEMAN CREEK   ,Reach-1
Reach XY= 30
        2493075.       13693875.      2493514.92     13694463.93
      2493869.83     13694380.41      2493964.92     13694763.91
       2494278.4     13694632.78      2494715.87     13694918.26
      2494583.04     13695478.32      2494875.51     13695704.76
      2494625.39     13696463.98      2494972.48     13696733.11
      2495127.24     13697919.07      2495426.65     13698171.89
      2496259.84     13698125.39      2496619.97     13698325.81
       2497475.3      13698182.2      2497674.75     13698468.02
      2498378.22     13698282.88       2499288.3      13698838.4
      2499518.48     13699267.33      2499809.79     13699274.49
      2500071.54      13699073.5      2500068.93     13698732.45
      2500573.56     13699021.47      2500494.23     13698654.62
      2501264.58     13698284.81      2501214.55     13698125.53
      2500728.36     13698173.75      2501014.88     13697685.34
      2501364.65     13697824.12        2501975.       13697525.

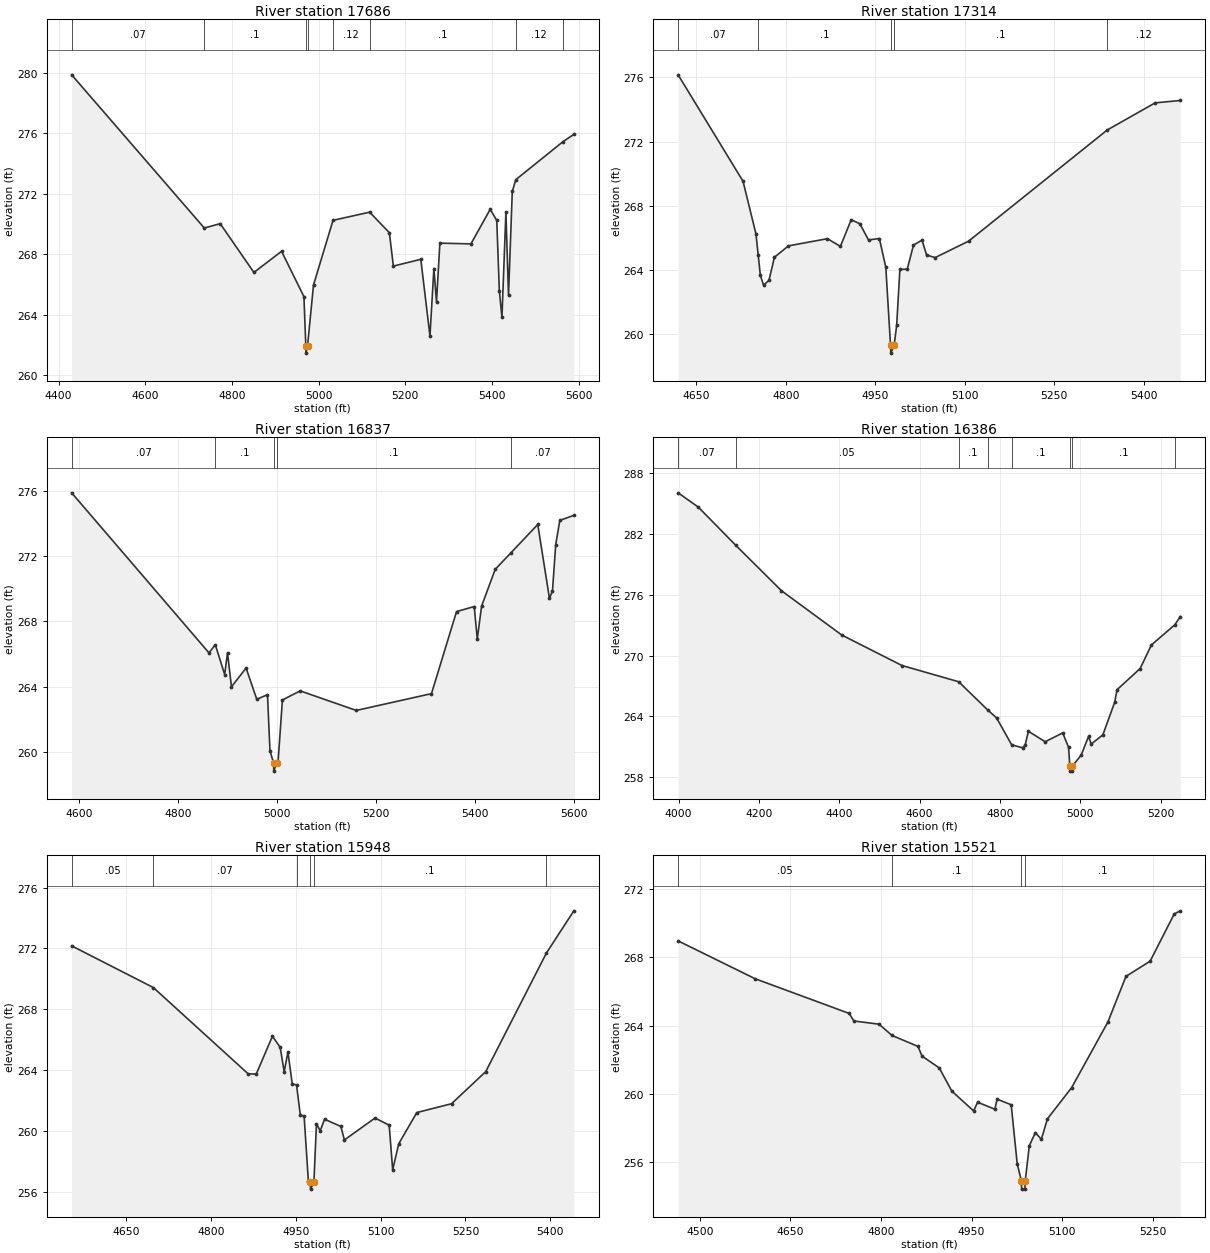
Type RM Length L Ch R = 1 ,17686   ,372,372,372
BEGIN DESCRIPTION:
X19220
END DESCRIPTION:
XS GIS Cut Line= 4
      2492740.39     13694294.78      2493100.45      13693918.6
      2493154.19     13693805.75      2493584.05     13693526.34
#Sta/Elev= 30
  4430.3  279.87  4736.3  269.73    4773  270.02  4850.7  266.79  4914.5  268.19
  4966.1  265.19  4970.4  261.95  4970.6  261.45  4974.5  261.95  4988.2  265.96
  5033.2  270.24  5117.7  270.78  5163.2  269.42  5172.4  267.21  5235.7  267.66
  5256.8  262.59  5265.9  267.05  5271.9  264.84  5279.7  268.73  5351.3  268.68
  5395.8  270.97  5410.9  270.23  5416.9  265.55  5422.9  263.82    5432  270.79
    5438  265.28  5446.7  272.15  5454.8  272.93  5563.4  275.44  5588.7  275.93
#Mann= 8 ,-1 , 0
  4430.3     .07       0  4736.3      .1       0  4970.4     .05       0
  4974.5      .1       0  5033.2     .12       0  5117.7      .1       0
  5454.8     .12       0  5563.4     .07       0
Bank Sta=4970.4,4974.5
XS Rating Curve= 0 ,0
Exp/Cntr=0.3,0.1

Type RM Length L Ch R = 1 ,17314   ,477,477,477
BEGIN DESCRIPTION:
FREEMAN CREEK 36.0
END DESCRIPTION:
XS GIS Cut Line= 3
      2492925.02     13694274.99        2493275.       13694125.
      2493624.96     13693825.03
#Sta/Elev= 30
  4619.5  276.16  4728.3  269.52    4750  266.23  4753.7  264.93  4757.3  263.66
  4762.7  263.04  4771.8  263.34  4780.9  264.78  4804.4  265.49  4869.7  265.94
  4891.5  265.46  4909.6  267.12  4924.1  266.87  4938.6  265.86  4956.8  265.95
  4967.6  264.16  4975.5   259.3    4976   258.8  4981.6   259.3  4985.8  260.53
  4991.2  264.02  5003.6  264.04    5014  265.54  5028.3  265.85  5035.9  264.92
  5050.2  264.76  5106.2  265.78  5338.8  272.72    5419  274.41  5461.2  274.56
#Mann= 5 ,-1 , 0
  4619.5     .07       0  4753.7      .1       0  4975.5     .05       0
  4981.6      .1       0  5338.8     .12       0
Bank Sta=4975.5,4981.6
XS Rating Curve= 0 ,0
Exp/Cntr=0.3,0.1

Type RM Length L Ch R = 1 ,16837   ,451,451,451
BEGIN DESCRIPTION:
FREEMAN CREEK 35.0
END DESCRIPTION:
XS GIS Cut Line= 3
      2493175.02     13694674.99        2493525.       13694475.
      2493874.99     13693975.01
#Sta/Elev= 30
  4585.7  275.88  4862.8  266.07  4875.6  266.57  4894.5  264.74  4900.2  266.07
  4908.2  263.99  4937.7  265.14  4959.3  263.22  4980.9  263.51  4985.9  260.07
  4993.1  259.32  4993.6  258.82  4999.3  259.32  5002.3  259.41    5011  263.18
  5046.8  263.74  5160.1  262.54  5311.8  263.57  5362.4   268.6  5398.1  268.91
  5404.2  266.91    5413  268.94  5440.4  271.19  5472.7  272.22  5526.3  273.94
  5549.9  269.41    5556  269.87  5562.5   272.7  5570.8  274.19  5599.1   274.5
#Mann= 5 ,-1 , 0
  4585.7     .07       0  4875.6      .1       0  4993.1     .05       0
  4999.3      .1       0  5472.7     .07       0
Bank Sta=4993.1,4999.3
XS Rating Curve= 0 ,0
Exp/Cntr=0.3,0.1

Type RM Length L Ch R = 1 ,16386   ,438,438,438
BEGIN DESCRIPTION:
FREEMAN CREEK 34.0
END DESCRIPTION:
XS GIS Cut Line= 3
      2493274.99     13695225.01        2493875.       13694425.
      2494024.99     13694225.01
#Sta/Elev= 30
    3999  286.06    4049  284.66  4142.3  280.89  4256.3   276.4  4406.3  272.03
  4556.3  269.02  4697.3  267.42  4769.7  264.63  4791.7  263.85  4829.2   261.2
  4856.3   260.9  4862.6  261.14  4870.9  262.53  4912.6   261.5  4956.3  262.37
  4970.9  260.94    4974   259.1  4974.5   258.6  4979.8   258.6  4980.3   259.1
  5002.1  260.17  5020.9  262.05  5027.1  261.27  5056.3  262.18  5085.5  265.38
  5091.7  266.64    5149  268.72  5177.1  271.05  5235.4  273.04    5249  273.85
#Mann= 8 ,-1 , 0
    3999     .07       0  4142.3     .05       0  4697.3      .1       0
  4769.7     .07       0  4829.2      .1       0    4974     .05       0
  4980.3      .1       0  5235.4     .07       0
Bank Sta=4974,4980.3
XS Rating Curve= 0 ,0
Exp/Cntr=0.3,0.1

Type RM Length L Ch R = 1 ,15948   ,427,427,427
BEGIN DESCRIPTION:
FREEMAN CREEK 33.0
END DESCRIPTION:
XS GIS Cut Line= 3
      2493724.99     13695075.01        2494025.       13694725.
        2494175.     13694324.99
#Sta/Elev= 30
  4553.5  272.17    4698  269.43  4865.8  263.76    4880  263.75  4908.6  266.23
  4922.3  265.51  4929.4  263.89    4936   265.2  4943.7  263.09  4951.2  263.04
    4958  261.04  4964.6     261  4972.2  256.71  4975.6  256.69  4976.1  256.19
    4982  256.69  4986.5  260.49  4993.1  260.02  5000.8  260.78  5029.6  260.31
  5035.9  259.42  5090.1  260.86  5115.1  260.39  5121.3  257.46    5132  259.17
    5164  261.22  5225.4   261.8  5285.9  263.91  5393.1  271.69  5441.7  274.47
#Mann= 6 ,-1 , 0
  4553.5     .05       0    4698     .07       0  4951.2      .1       0
  4975.6     .05       0    4982      .1       0  5393.1     .07       0
Bank Sta=4975.6,4982
XS Rating Curve= 0 ,0
Exp/Cntr=0.3,0.1

Type RM Length L Ch R = 1 ,15521   ,367,367,367
BEGIN DESCRIPTION:
FREEMAN CREEK 32.0
END DESCRIPTION:
XS GIS Cut Line= 3
      2493974.98     13695075.02        2494375.       13694725.
        2494375.     13694425.03
#Sta/Elev= 30
  4464.1  268.96  4591.8  266.74  4747.4  264.71    4755  264.27  4796.8  264.08
  4818.3  263.42  4861.3  262.78    4868  262.21  4896.5  261.52  4917.3  260.16
  4953.4     259    4960  259.51  4988.5   259.1  4992.3  259.69  5015.6  259.36
  5025.6  255.89  5032.4  254.92  5032.9  254.42  5038.4  254.42  5038.9  254.92
  5045.6  256.96  5055.6  257.73  5065.6  257.34  5075.6  258.54  5115.6  260.36
  5175.6   264.2  5205.6  266.88  5245.6  267.77  5285.6  270.54  5295.6  270.72
#Mann= 4 ,-1 , 0
  4464.1     .05       0  4818.3      .1       0  5032.4     .05       0
  5038.9      .1       0
Bank Sta=5032.4,5038.9
XS Rating Curve= 0 ,0
Exp/Cntr=0.3,0.1

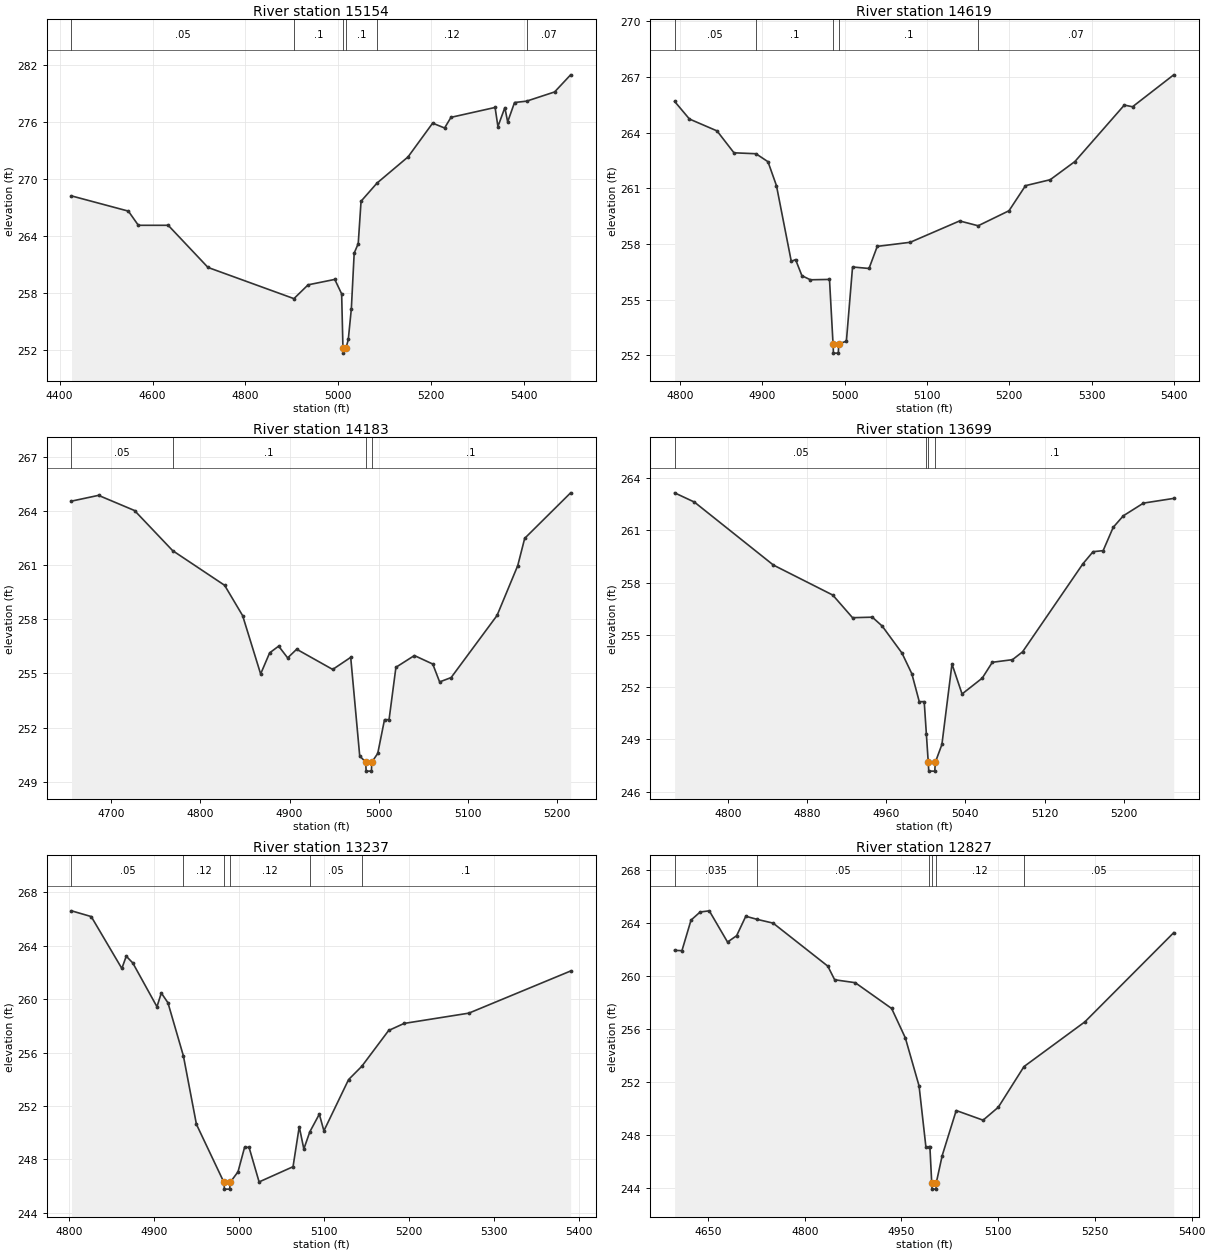
Type RM Length L Ch R = 1 ,15154   ,535,535,535
BEGIN DESCRIPTION:
FREEMAN CREEK 31.0
END DESCRIPTION:
XS GIS Cut Line= 3
      2494224.98     13695225.01      2494658.81      13694918.1
      2494970.24     13694472.45
#Sta/Elev= 30
  4425.5  268.21    4548  266.61  4569.5  265.12  4633.8  265.12  4719.5  260.69
  4904.6  257.41  4935.1  258.86  4992.6  259.43  5007.4  257.91  5010.2  252.18
  5010.7  251.68  5016.7  252.18  5021.7  253.12  5028.3  256.35  5034.4   262.2
  5043.1  263.19  5049.2  267.65  5083.6  269.56  5150.4  272.31  5203.4  275.86
  5229.1  275.35  5242.9  276.47  5337.9  277.51    5344   275.5  5358.9  277.49
    5365  275.99  5379.8  278.03  5405.6  278.17  5466.1  279.14  5500.6  280.94
#Mann= 6 ,-1 , 0
  4425.5     .05       0  4904.6      .1       0  5010.2     .05       0
  5016.7      .1       0  5083.6     .12       0  5405.6     .07       0
Bank Sta=5010.2,5016.7
XS Rating Curve= 0 ,0
Exp/Cntr=0.3,0.1

Type RM Length L Ch R = 1 ,14619   ,436,436,436
BEGIN DESCRIPTION:
FREEMAN CREEK 30.0
END DESCRIPTION:
XS GIS Cut Line= 3
      2494425.02     13695424.99        2494625.       13695375.
      2495024.97       13695375.
#Sta/Elev= 30
  4793.5  265.68  4811.5  264.73    4845  264.09  4865.6  262.91  4892.3  262.86
  4906.9  262.43  4917.2  261.14  4935.2  257.06  4940.4  257.16  4948.1  256.29
  4958.4  256.07  4981.6  256.09  4985.9  252.62  4986.4  252.12  4992.3  252.12
  4992.8  252.62  5002.1  252.76  5009.6  256.76  5029.6  256.68  5039.6  257.87
  5079.6  258.09  5139.6  259.24  5162.1  258.98  5199.6  259.79  5219.6  261.14
  5249.6  261.46  5279.6  262.44  5339.6  265.48  5349.6  265.39  5399.6  267.11
#Mann= 5 ,-1 , 0
  4793.5     .05       0  4892.3      .1       0  4985.9     .05       0
  4992.8      .1       0  5162.1     .07       0
Bank Sta=4985.9,4992.8
XS Rating Curve= 0 ,0
Exp/Cntr=0.3,0.1

Type RM Length L Ch R = 1 ,14183   ,484,484,484
BEGIN DESCRIPTION:
FREEMAN CREEK 29.0
END DESCRIPTION:
XS GIS Cut Line= 3
      2494475.02       13695675.        2494825.       13695625.
      2495025.01       13695575.
#Sta/Elev= 30
  4655.5  264.54  4685.8  264.86  4726.2  264.02  4768.9   261.8  4827.2  259.88
  4847.4   258.2  4867.6  254.97  4877.7  256.14  4887.8  256.51  4897.9  255.86
    4908  256.34  4948.4  255.22  4968.6  255.89  4978.7  250.43  4985.4  250.09
  4985.9  249.59  4991.8  249.59  4992.3  250.09  4998.9  250.57  5006.5  252.44
  5011.6  252.44  5019.3  255.34    5040  255.99  5060.6  255.52  5068.3  254.53
  5081.2  254.77  5132.7  258.21  5155.9  260.97  5163.7  262.48  5215.2     265
#Mann= 4 ,-1 , 0
  4655.5     .05       0  4768.9      .1       0  4985.4     .05       0
  4992.3      .1       0
Bank Sta=4985.4,4992.3
XS Rating Curve= 0 ,0
Exp/Cntr=0.3,0.1

Type RM Length L Ch R = 1 ,13699   ,462,462,462
BEGIN DESCRIPTION:
FREEMAN CREEK 28.0
END DESCRIPTION:
XS GIS Cut Line= 3
      2494475.03       13696025.        2494725.       13696025.
      2494974.98       13695975.
#Sta/Elev= 30
  4745.8  263.16  4765.8  262.63  4845.8  259.01  4905.8  257.29  4925.8  255.99
  4945.8  256.02  4955.8  255.51  4975.8  253.96  4985.8  252.77  4993.3  251.17
  4998.3  251.17  5000.5   249.3  5002.4  247.68  5002.9  247.18    5009  247.18
  5009.5  247.68  5016.2  248.71  5026.4  253.33  5036.6  251.61    5057  252.52
  5067.2  253.43  5087.6  253.58  5097.8  254.03  5158.9  259.09  5169.1  259.78
  5179.3  259.84  5189.5  261.18  5199.7  261.84  5220.1  262.57  5250.7  262.84
#Mann= 4 ,-1 , 0
  4745.8     .05       0  5000.5      .1       0  5002.4     .05       0
  5009.5      .1       0
Bank Sta=5002.4,5009.5
XS Rating Curve= 0 ,0
Exp/Cntr=0.3,0.1

Type RM Length L Ch R = 1 ,13237   ,410,410,410
BEGIN DESCRIPTION:
FREEMAN CREEK 27.0
END DESCRIPTION:
XS GIS Cut Line= 3
      2494475.03     13696375.01        2494675.       13696425.
      2495024.99     13696275.01
#Sta/Elev= 30
    4803  266.62  4826.2  266.19  4862.2   262.3  4867.4  263.22  4875.1  262.71
  4903.5  259.43  4908.6  260.46  4916.4  259.73  4934.6  255.74  4949.9  250.62
  4982.3  246.26  4982.8  245.76    4989  245.76  4989.5  246.26  4998.8  247.06
  5006.5  248.89  5011.8  248.89  5023.6   246.3  5063.5  247.44  5070.8  250.44
  5076.2  248.77  5083.2  250.05  5094.4  251.38  5099.8  250.13  5128.8  253.97
  5144.4  254.97  5175.9  257.65  5194.1  258.18  5270.2  258.95  5389.9  262.11
#Mann= 6 ,-1 , 0
    4803     .05       0  4934.6     .12       0  4982.3     .05       0
  4989.5     .12       0  5083.2     .05       0  5144.4      .1       0
Bank Sta=4982.3,4989.5
XS Rating Curve= 0 ,0
Exp/Cntr=0.3,0.1

Type RM Length L Ch R = 1 ,12827   ,435,435,435
BEGIN DESCRIPTION:
FREEMAN CREEK 26.0
END DESCRIPTION:
XS GIS Cut Line= 4
      2494546.97     13697003.03        2494725.       13696825.
        2494825.       13696725.      2495175.01       13696575.
#Sta/Elev= 30
  4598.2  261.95  4609.6  261.93  4623.7  264.24  4637.8  264.85    4652  264.94
  4680.3  262.58  4694.4  263.06  4708.6  264.53  4725.8   264.3    4751  264.01
  4835.8  260.76  4846.4  259.73  4878.3  259.51  4934.8  257.56    4956  255.34
  4977.3  251.71  4987.9   247.1  4992.5   247.1  4994.1   247.1  4996.9  244.41
  4997.4  243.91  5003.6  243.91  5004.1  244.41  5013.2  246.45  5034.9  249.85
  5076.6  249.12  5100.2   250.1    5140  253.17  5234.4  256.55  5372.2  263.29
#Mann= 6 ,-1 , 0
  4598.2    .035       0  4725.8     .05       0  4992.5     .12       0
  4996.9     .05       0  5004.1     .12       0    5140     .05       0
Bank Sta=4996.9,5004.1
XS Rating Curve= 0 ,0
Exp/Cntr=0.3,0.1

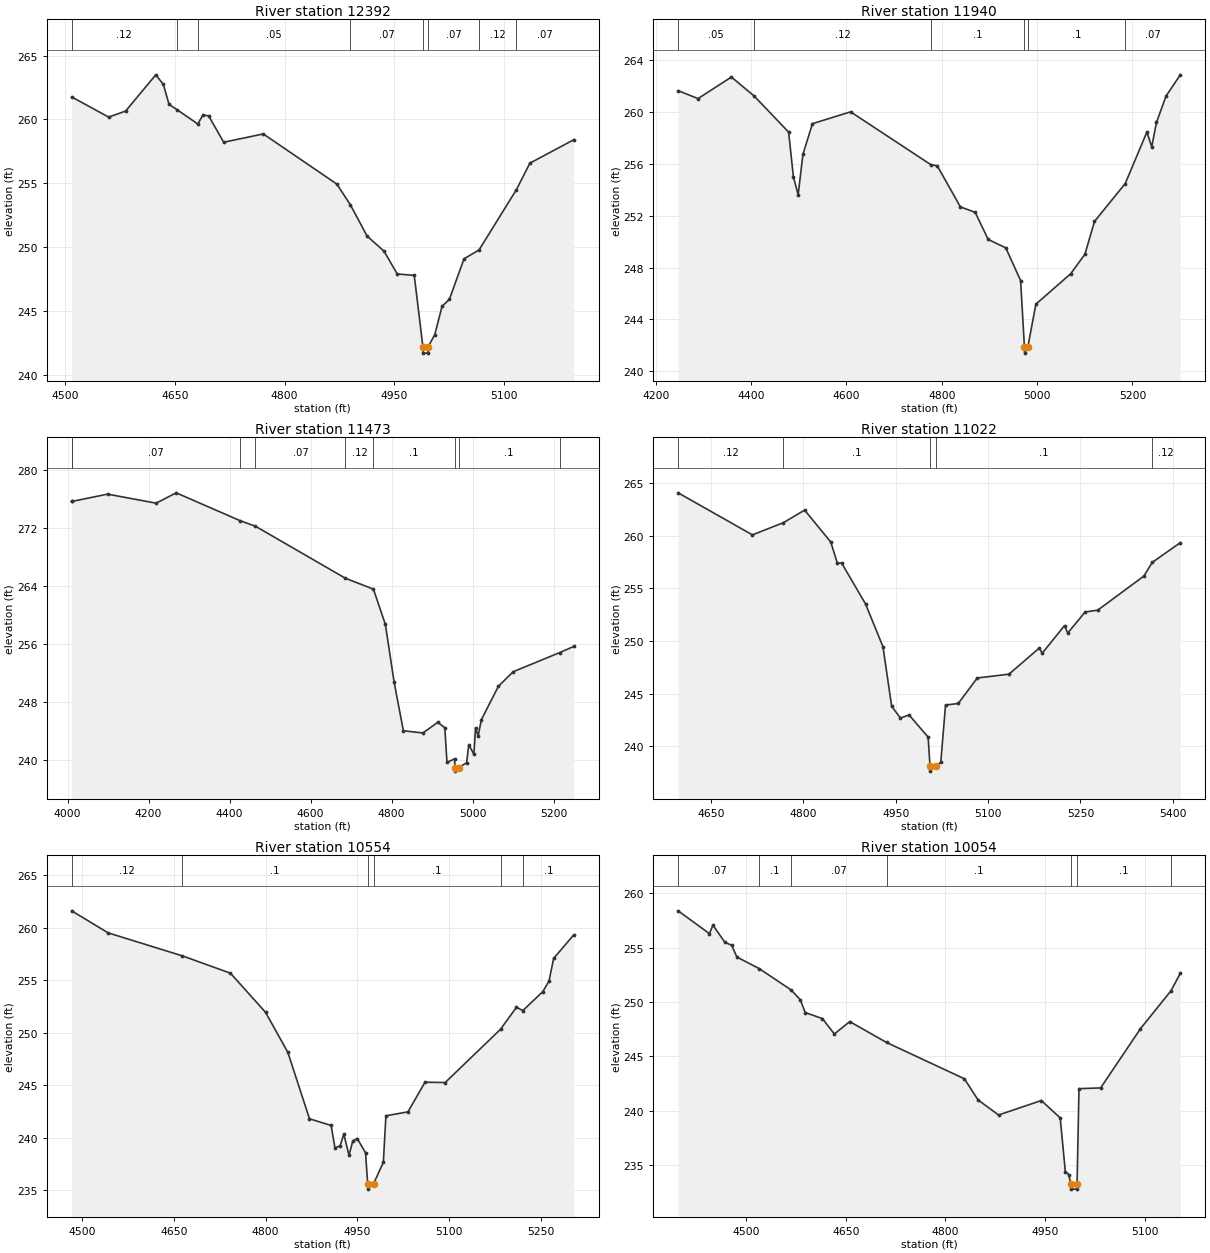
Type RM Length L Ch R = 1 ,12392   ,452,452,452
BEGIN DESCRIPTION:
FREEMAN CREEK 25.0
END DESCRIPTION:
XS GIS Cut Line= 4
      2494553.49     13697092.88        2494825.       13697025.
        2495025.       13696975.      2495224.98       13696975.
#Sta/Elev= 30
  4509.2  261.76  4559.7  260.18  4582.9  260.65  4624.1  263.49  4634.5  262.74
  4642.2  261.18  4652.9  260.77  4681.5  259.64  4688.6  260.34  4696.3  260.28
  4716.9  258.21    4771  258.86  4871.5  254.93  4889.9  253.31  4912.8  250.86
    4936  249.67    4954  247.89  4977.2  247.78    4989  242.19  4989.5  241.69
  4995.7  241.69  4996.2  242.19  5005.2  243.13  5015.2  245.36  5025.2   245.9
  5045.2  249.08  5065.7  249.77  5116.7  254.49  5135.2  256.57  5195.2  258.41
#Mann= 8 ,-1 , 0
  4509.2     .12       0  4652.9    .035       0  4681.5     .05       0
  4889.9     .07       0    4989     .05       0  4996.2     .07       0
  5065.7     .12       0  5116.7     .07       0
Bank Sta=4989,4996.2
XS Rating Curve= 0 ,0
Exp/Cntr=0.3,0.1

Type RM Length L Ch R = 1 ,11940   ,467,467,467
BEGIN DESCRIPTION:
FREEMAN CREEK 24.0
END DESCRIPTION:
XS GIS Cut Line= 4
      2494363.22     13697218.04        2494825.       13697225.
        2495075.       13697375.      2495375.02       13697375.
#Sta/Elev= 30
  4247.1  261.62  4288.9  261.01  4358.9  262.67  4406.8   261.2  4478.9  258.43
  4488.9  254.99  4498.9   253.6  4508.9  256.72  4528.9  259.08  4608.9  259.99
  4777.7  255.91  4790.6  255.84  4839.2  252.67  4870.3  252.25  4897.5  250.16
  4934.4  249.52  4965.5     247  4973.5  241.91    4974  241.41  4980.8  241.91
  4997.6  245.18  5070.5  247.52  5100.5  249.03  5120.5  251.55    5185  254.47
  5230.5  258.44  5240.5  257.29  5250.5  259.17  5270.5   261.2  5300.5  262.84
#Mann= 6 ,-1 , 0
  4247.1     .05       0  4406.8     .12       0  4777.7      .1       0
  4973.5     .05       0  4980.8      .1       0    5185     .07       0
Bank Sta=4973.5,4980.8
XS Rating Curve= 0 ,0
Exp/Cntr=0.3,0.1

Type RM Length L Ch R = 1 ,11473   ,451,451,451
BEGIN DESCRIPTION:
FREEMAN CREEK 23.0
END DESCRIPTION:
XS GIS Cut Line= 4
      2494465.35     13698529.23        2495025.       13698075.
        2495125.       13697825.      2495324.97     13697675.03
#Sta/Elev= 30
  4010.2   275.7  4011.1   275.7  4098.8  276.71  4218.8  275.46  4268.3  276.89
  4426.5  273.03    4464  272.27    4686  265.08  4755.3  263.57  4784.8   258.7
  4806.4  250.72  4829.3  243.98  4877.7  243.68  4914.1  245.15  4931.6  244.41
    4937   239.6  4955.8   240.1  4956.6   238.9  4957.1   238.4  4965.7   238.9
  4985.4  239.55  4990.8  242.05  5003.4  240.74  5007.5   244.4  5013.8  243.24
  5022.1  245.54  5063.8  250.12  5100.2  252.14  5215.1  254.79  5250.2  255.65
#Mann= 9 ,-1 , 0
  4010.2    .035       0  4011.1     .07       0  4426.5     .05       0
    4464     .07       0    4686     .12       0  4755.3      .1       0
  4956.6     .05       0  4965.7      .1       0  5215.1     .12       0
Bank Sta=4956.6,4965.7
XS Rating Curve= 0 ,0
Exp/Cntr=0.3,0.1

Type RM Length L Ch R = 1 ,11022   ,468,468,468
BEGIN DESCRIPTION:
FREEMAN CREEK 22.0
END DESCRIPTION:
XS GIS Cut Line= 4
      2495089.67     13698410.33        2495275.       13698225.
        2495375.       13698125.      2495474.99     13697725.03
#Sta/Elev= 30
  4596.5  264.06  4717.2  260.07  4767.6  261.23    4802  262.42  4844.5  259.39
  4855.1   257.4  4862.1   257.4    4901  253.51  4929.3  249.45  4943.4  243.81
  4957.6  242.69  4971.7  242.98  5002.6  240.88  5005.7  238.15  5006.2  237.65
  5014.9  238.15  5023.2  238.49  5030.9  243.92  5051.6  244.07  5082.5  246.49
    5134  246.85    5183  249.32  5188.1  248.85  5224.2  251.46  5229.4  250.75
  5257.7  252.75  5278.3  252.93  5353.1  256.16  5366.8  257.46  5412.3  259.33
#Mann= 5 ,-1 , 0
  4596.5     .12       0  4767.6      .1       0  5005.7     .05       0
  5014.9      .1       0  5366.8     .12       0
Bank Sta=5005.7,5014.9
XS Rating Curve= 0 ,0
Exp/Cntr=0.3,0.1

Type RM Length L Ch R = 1 ,10554   ,500,500,500
BEGIN DESCRIPTION:
FREEMAN CREEK 21.0
END DESCRIPTION:
XS GIS Cut Line= 4
      2495464.79     13698538.62        2495625.       13698325.
        2495775.       13698125.      2495825.01     13697824.96
#Sta/Elev= 30
    4483  261.59  4542.7  259.49  4664.1   257.3  4742.7  255.65    4800  251.93
  4836.5  248.12  4871.9  241.79  4907.3  241.15  4913.6     239  4921.9  239.21
  4928.1  240.33  4936.5  238.31  4942.7  239.67    4950  239.91  4963.6  238.55
  4967.1  235.59  4967.6  235.09  4976.6  235.59  4992.7  237.64  4996.9  242.07
    5033  242.45  5060.8  245.27  5093.8  245.24  5184.3  250.31  5210.4  252.41
  5220.8  252.09  5253.5   253.9  5263.6  254.91  5271.2  257.06  5304.2  259.31
#Mann= 6 ,-1 , 0
    4483     .12       0  4664.1      .1       0  4967.1     .05       0
  4976.6      .1       0  5184.3     .07       0  5220.8      .1       0
Bank Sta=4967.1,4976.6
XS Rating Curve= 0 ,0
Exp/Cntr=0.3,0.1

Type RM Length L Ch R = 1 ,10054   ,468,468,468
BEGIN DESCRIPTION:
FREEMAN CREEK 20.0
END DESCRIPTION:
XS GIS Cut Line= 4
      2496127.92     13698713.31        2496175.       13698525.
        2496275.       13698125.        2496275.     13697975.02
#Sta/Elev= 30
  4397.5  258.39  4444.7  256.29  4449.9  257.07  4467.9   255.5  4478.2  255.22
    4486  254.14  4519.8  253.07  4567.7  251.11  4581.3  250.23    4589  249.03
  4614.8  248.48  4632.8  247.06    4656   248.2  4711.5  246.28  4828.7  242.94
  4849.3  240.99  4880.2  239.61  4944.6  240.94    4973  239.34  4980.7  234.41
  4985.9  234.13  4988.8  233.29  4989.3  232.79  4997.9  232.79  4998.4  233.29
  5001.3  242.03  5033.9   242.1  5093.9  247.55  5139.8  251.03  5153.9  252.64
#Mann= 7 ,-1 , 0
  4397.5     .07       0  4519.8      .1       0  4567.7     .07       0
  4711.5      .1       0  4988.8     .05       0  4998.4      .1       0
  5139.8     .12       0
Bank Sta=4988.8,4998.4
XS Rating Curve= 0 ,0
Exp/Cntr=0.3,0.1

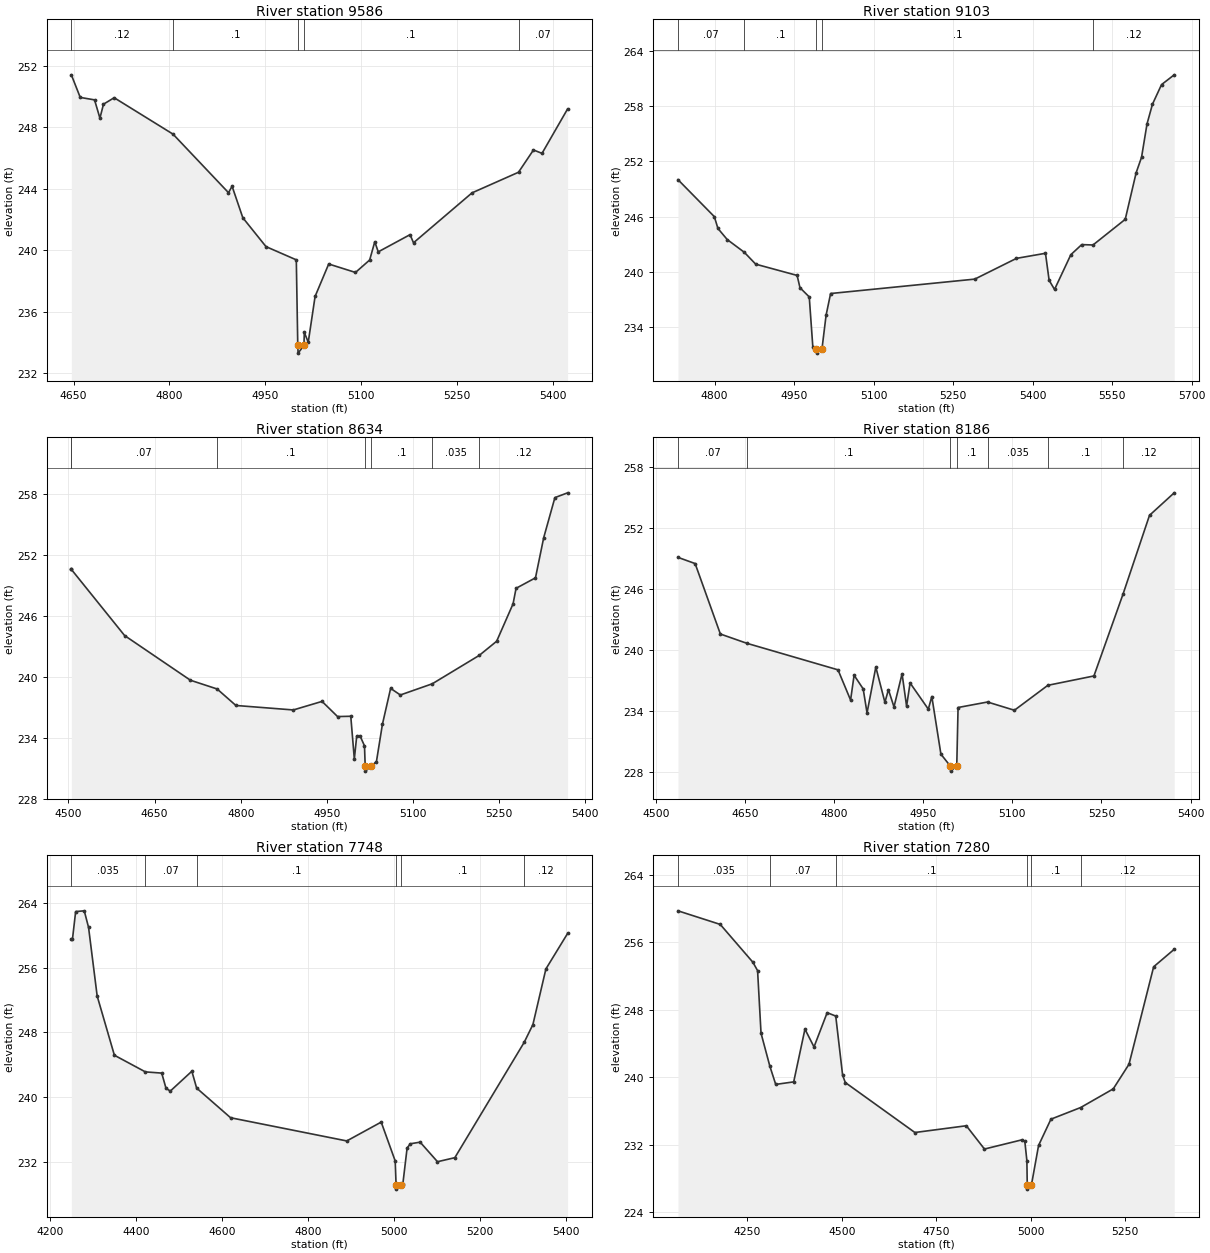
Type RM Length L Ch R = 1 ,9586    ,483,483,483
BEGIN DESCRIPTION:
FREEMAN CREEK 19.0
END DESCRIPTION:
XS GIS Cut Line= 4
      2496831.23     13698637.47        2496775.       13698525.
        2496675.       13698325.      2496525.02     13697925.04
#Sta/Elev= 30
  4646.6  251.41  4660.5  249.94  4682.9  249.78  4691.3  248.59  4696.9   249.5
  4713.6  249.92  4805.7  247.55  4892.5  243.74  4898.1  244.16  4914.9  242.11
  4951.2  240.23  4998.6  239.37  5000.9   233.8  5001.4   233.3  5010.6   233.8
  5011.1  234.65  5017.3  234.01    5028  236.99  5049.3   239.1  5091.2  238.55
  5113.4  239.36  5121.4  240.55  5126.8  239.89  5176.6  241.01    5182  240.48
  5273.6  243.73  5346.3  245.07  5369.7  246.52  5383.1   246.3  5423.1  249.19
#Mann= 5 ,-1 , 0
  4646.6     .12       0  4805.7      .1       0  5000.9     .05       0
  5010.6      .1       0  5346.3     .07       0
Bank Sta=5000.9,5010.6
XS Rating Curve= 0 ,0
Exp/Cntr=0.3,0.1

Type RM Length L Ch R = 1 ,9103    ,469,469,469
BEGIN DESCRIPTION:
FREEMAN CREEK 18.0
END DESCRIPTION:
XS GIS Cut Line= 3
      2497025.01     13698574.97        2497125.       13698325.
        2496975.     13697675.01
#Sta/Elev= 30
  4730.8  250.02  4799.4  246.01  4806.2  244.73  4823.7  243.53  4855.9  242.15
  4877.5  240.86  4955.6  239.64    4961  238.31  4978.5  237.31  4985.2  231.93
    4992  231.72  4992.5  231.22  5002.6  231.72  5010.3  235.34  5018.8  237.68
  5290.8  239.24  5369.5  241.49  5424.2  242.04  5431.1  239.11  5441.3  238.12
  5472.1  241.89  5492.6  242.98  5513.9  242.94  5574.7  245.72  5595.3  250.77
  5605.5  252.45  5615.8  256.06  5626.1   258.2  5643.2  260.32  5667.1  261.38
#Mann= 5 ,-1 , 0
  4730.8     .07       0  4855.9      .1       0    4992     .05       0
  5002.6      .1       0  5513.9     .12       0
Bank Sta=4992,5002.6
XS Rating Curve= 0 ,0
Exp/Cntr=0.3,0.1

Type RM Length L Ch R = 1 ,8634    ,448,448,448
BEGIN DESCRIPTION:
FREEMAN CREEK 17.0
END DESCRIPTION:
XS GIS Cut Line= 3
        2497225.       13698625.        2497525.       13698225.
        2497625.       13697875.
#Sta/Elev= 30
  4505.1  250.54  4505.2  250.54  4597.8  244.05  4712.4  239.66  4758.9   238.8
  4791.6  237.18  4891.6  236.74  4941.6  237.58  4968.6  236.09  4991.6  236.12
  4997.8  231.92    5002   234.2  5007.7   234.2  5015.5  233.21  5016.7  231.23
  5017.2  230.73  5027.3  231.23  5036.3  231.67  5046.7  235.33    5061  238.86
  5077.9  238.21  5133.5  239.31  5215.3   242.1  5245.6  243.49  5274.2  247.17
  5279.4  248.69  5313.2  249.72  5327.5  253.66    5347   257.6  5369.1  258.07
#Mann= 7 ,-1 , 0
  4505.1    .035       0  4505.2     .07       0  4758.9      .1       0
  5016.7     .05       0  5027.3      .1       0  5133.5    .035       0
  5215.3     .12       0
Bank Sta=5016.7,5027.3
XS Rating Curve= 0 ,0
Exp/Cntr=0.3,0.1

Type RM Length L Ch R = 1 ,8186    ,438,438,438
BEGIN DESCRIPTION:
FREEMAN CREEK 16.0
END DESCRIPTION:
XS GIS Cut Line= 3
      2497524.99     13698775.02        2497775.       13698375.
      2497874.99     13698025.03
#Sta/Elev= 30
  4536.8  249.12  4565.7  248.51  4608.2  241.59  4652.7  240.68  4806.3  238.07
  4827.5   235.1  4833.4  237.54  4848.7   236.2  4855.2  233.84    4870  238.34
  4885.3  234.88  4891.2  236.12  4900.6  234.43  4914.2  237.68  4921.8   234.5
  4927.7  236.78  4958.4  234.21  4964.3  235.45  4979.6  229.79  4995.4  228.62
  4995.9  228.12  5006.3  228.62  5008.5  234.37  5058.1  234.91  5103.4   234.1
  5159.7  236.55  5237.3  237.47  5286.5  245.54  5330.9  253.25  5372.5  255.46
#Mann= 7 ,-1 , 0
  4536.8     .07       0  4652.7      .1       0  4995.4     .05       0
  5006.3      .1       0  5058.1    .035       0  5159.7      .1       0
  5286.5     .12       0
Bank Sta=4995.4,5006.3
XS Rating Curve= 0 ,0
Exp/Cntr=0.3,0.1

Type RM Length L Ch R = 1 ,7748    ,468,468,468
BEGIN DESCRIPTION:
FREEMAN CREEK 15.0
END DESCRIPTION:
XS GIS Cut Line= 3
        2498175.       13699125.        2498175.       13698375.
        2498125.     13697975.02
#Sta/Elev= 30
  4250.1  259.48  4252.6  259.48  4260.1  262.93  4280.1  263.02  4290.1  260.96
  4310.1  252.48  4350.1  245.16  4422.1   243.1  4460.1  242.95  4470.1  241.06
  4480.1  240.73  4530.1  243.18  4541.2   241.1  4620.1  237.43  4890.1  234.56
  4970.1  236.89  5002.6  232.09  5004.7   229.1  5005.2   228.6  5015.6   229.1
  5020.3   229.2  5030.3  233.69  5037.9  234.21  5060.6  234.41  5100.9  231.99
  5141.2  232.49  5302.4  246.76  5322.6  248.95  5352.8  255.83  5403.2  260.22
#Mann= 6 ,-1 , 0
  4250.1    .035       0  4422.1     .07       0  4541.2      .1       0
  5004.7     .05       0  5015.6      .1       0  5302.4     .12       0
Bank Sta=5004.7,5015.6
XS Rating Curve= 0 ,0
Exp/Cntr=0.3,0.1

Type RM Length L Ch R = 1 ,7280    ,416,416,416
BEGIN DESCRIPTION:
FREEMAN CREEK 14.0
END DESCRIPTION:
XS GIS Cut Line= 3
      2498221.56     13699238.54        2498575.       13698375.
      2498725.02     13698024.96
#Sta/Elev= 30
  4066.3  259.74  4178.2  258.13  4264.6  253.65  4277.1  252.65  4286.2  245.24
  4309.5  241.34  4325.1  239.17  4372.7  239.47  4402.5  245.72  4426.5  243.61
  4461.3  247.67    4484  247.27  4502.3  240.24  4509.4  239.39  4693.6  233.47
  4829.8  234.27  4877.8  231.51  4977.8  232.61  4984.7  232.41  4990.1  230.14
  4991.1  227.26  4991.6  226.76  5002.2  227.26  5021.1  231.94  5053.8  235.05
  5132.5  236.43  5218.8  238.64  5260.5  241.56  5325.8  253.11  5380.2  255.18
#Mann= 6 ,-1 , 0
  4066.3    .035       0  4309.5     .07       0    4484      .1       0
  4991.1     .05       0  5002.2      .1       0  5132.5     .12       0
Bank Sta=4991.1,5002.2
XS Rating Curve= 0 ,0
Exp/Cntr=0.3,0.1

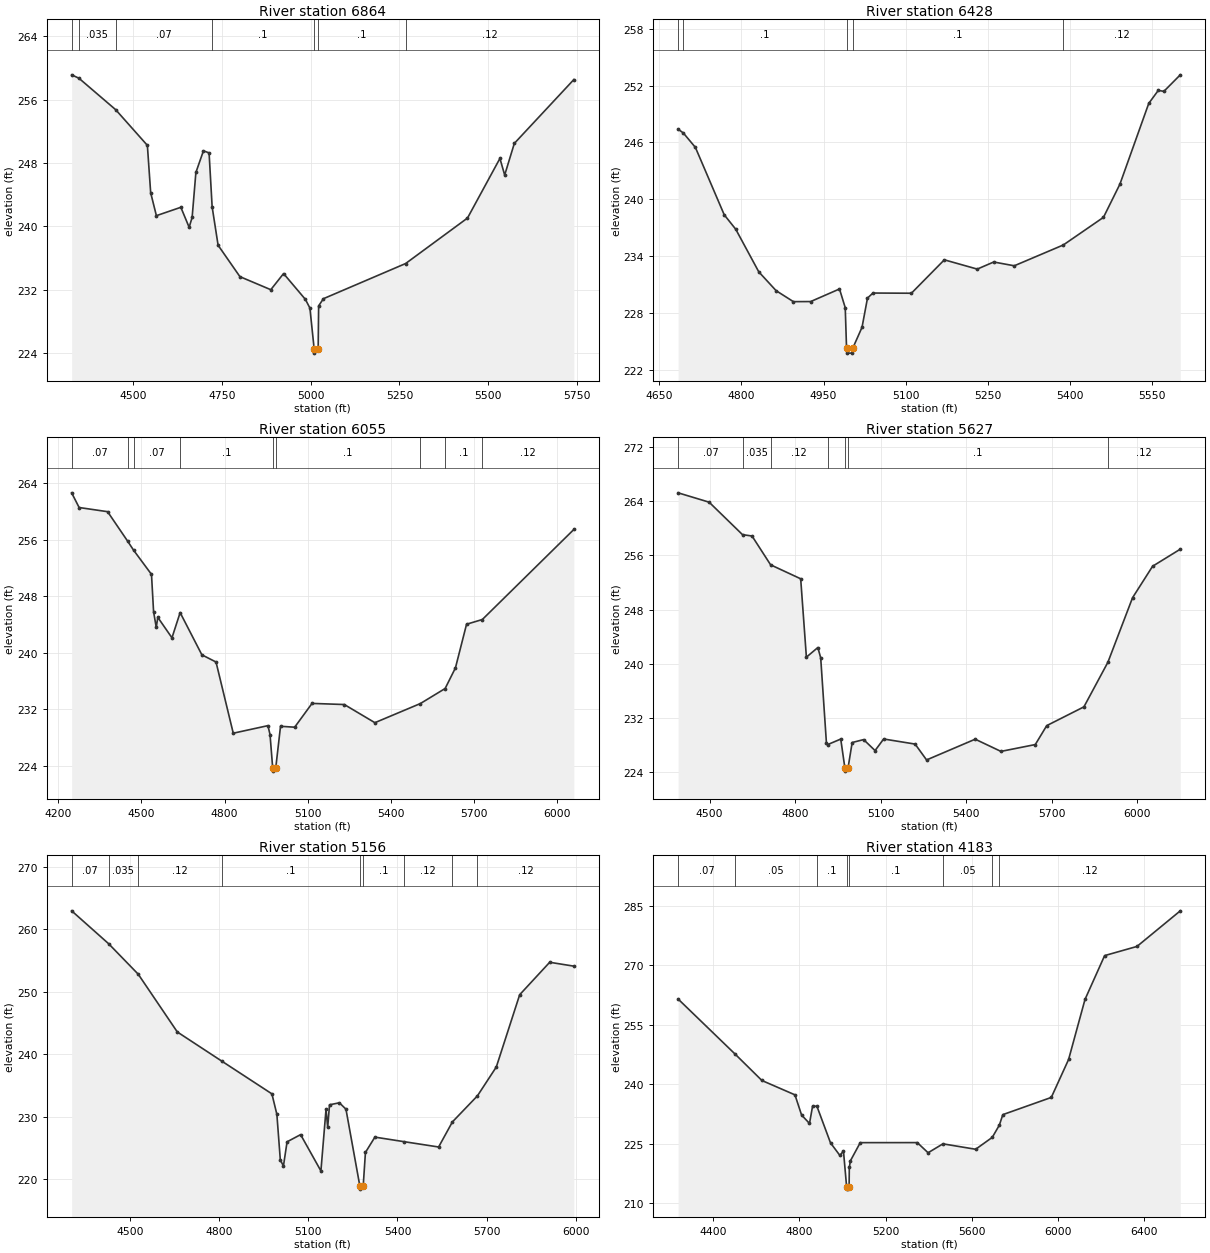
Type RM Length L Ch R = 1 ,6864    ,436,436,436
BEGIN DESCRIPTION:
FREEMAN CREEK 13.0
END DESCRIPTION:
XS GIS Cut Line= 3
      2498549.37     13699254.62        2498775.       13698625.
        2498904.     13697889.86
#Sta/Elev= 30
  4326.2  259.15  4346.7  258.72  4450.3  254.74  4539.6  250.23  4548.9  244.24
    4565  241.34  4633.9   242.4  4657.3  239.87  4665.7  241.11  4676.3   246.8
  4697.6  249.54  4713.5  249.28  4722.1  242.46  4738.9   237.6  4800.4  233.63
  4887.4  231.98  4923.4  234.02    4985  230.75  4997.6  229.66  5009.7  224.46
  5010.2  223.96  5020.9  224.46  5022.2  229.93  5035.6  230.84  5267.4  235.29
  5441.7  241.04  5533.1  248.58  5546.5  246.48  5573.7  250.48  5741.4  258.55
#Mann= 7 ,-1 , 0
  4326.2     .07       0  4346.7    .035       0  4450.3     .07       0
  4722.1      .1       0  5009.7     .05       0  5020.9      .1       0
  5267.4     .12       0
Bank Sta=5009.7,5020.9
XS Rating Curve= 0 ,0
Exp/Cntr=0.3,0.1

Type RM Length L Ch R = 1 ,6428    ,373,373,373
BEGIN DESCRIPTION:
FREEMAN CREEK 12.0
END DESCRIPTION:
XS GIS Cut Line= 3
      2499025.01     13699074.96        2499125.       13698775.
        2499075.     13698174.97
#Sta/Elev= 30
  4684.1  247.41  4693.7     247  4715.7  245.48  4768.4  238.36  4789.5  236.83
  4831.6  232.33  4863.3  230.34  4894.9  229.18  4926.5  229.19  4979.2  230.52
  4989.7  228.54  4992.1  224.24  4992.6  223.74  5002.8  223.74  5003.3  224.24
  5020.4  226.47  5030.4  229.56  5040.4  230.09  5110.7  230.07  5170.9   233.6
  5231.1  232.62  5261.2  233.37  5298.8  232.97  5388.5  235.17  5461.9  238.09
    5492   241.6  5544.7  250.13  5562.2  251.51  5572.3   251.4  5602.4  253.15
#Mann= 5 ,-1 , 0
  4684.1     .07       0  4693.7      .1       0  4992.1     .05       0
  5003.3      .1       0  5388.5     .12       0
Bank Sta=4992.1,5003.3
XS Rating Curve= 0 ,0
Exp/Cntr=0.3,0.1

Type RM Length L Ch R = 1 ,6055    ,428,428,428
BEGIN DESCRIPTION:
X19219
END DESCRIPTION:
XS GIS Cut Line= 3
      2499097.46     13699652.34      2499484.38     13698835.51
      2499554.13     13697928.73
#Sta/Elev= 30
  4247.8  262.63  4274.8  260.55  4377.6  259.96  4449.7   255.8  4471.4  254.51
  4536.1  251.08  4543.6  245.81  4553.3  243.57  4558.8     245    4610   242.1
  4639.5  245.67    4718  239.69  4769.1  238.67  4831.3  228.59  4956.5  229.66
  4964.1   228.4  4973.6  223.72  4974.1  223.22  4984.9  223.72    5002  229.57
  5053.1  229.44  5115.8  232.81  5232.4  232.65  5342.7  230.08    5507  232.79
  5596.4  234.92  5633.6  237.84  5673.7  244.02  5730.7  244.69  6061.1  257.44
#Mann= 9 ,-1 , 0
  4247.8     .07       0  4449.7    .035       0  4471.4     .07       0
  4639.5      .1       0  4973.6     .05       0  4984.9      .1       0
    5507     .12       0  5596.4      .1       0  5730.7     .12       0
Bank Sta=4973.6,4984.9
XS Rating Curve= 0 ,0
Exp/Cntr=0.3,0.1

Type RM Length L Ch R = 1 ,5627    ,471,471,471
BEGIN DESCRIPTION:
X19218
END DESCRIPTION:
XS GIS Cut Line= 2
      2499564.98      13699883.4      2499715.28     13698128.12
#Sta/Elev= 30
  4389.5  265.22  4498.3  263.84  4615.4  259.05  4648.8  258.85    4714   254.6
  4819.5  252.54  4839.5  240.98  4879.7   242.4  4889.7  240.88  4909.8  228.31
  4914.5  228.09    4960   228.9  4974.4  224.67  4974.9  224.17  4985.7  224.67
  5000.1  228.39  5040.3  228.82  5080.4   227.2  5110.5  228.91  5220.9  228.16
  5261.1  225.82  5431.7  228.88    5522  227.08  5642.5  228.09  5682.6  230.88
  5813.1  233.65  5897.2  240.23  5983.7  249.75    6054  254.39  6151.2  256.91
#Mann= 7 ,-1 , 0
  4389.5     .07       0  4615.4    .035       0    4714     .12       0
  4914.5      .1       0  4974.4     .05       0  4985.7      .1       0
  5897.2     .12       0
Bank Sta=4974.4,4985.7
XS Rating Curve= 0 ,0
Exp/Cntr=0.3,0.1

Type RM Length L Ch R = 1 ,5156    ,973,973,973
BEGIN DESCRIPTION:
X19217
END DESCRIPTION:
XS GIS Cut Line= 4
      2500161.47     13699797.44       2500091.6     13699249.29
      2499903.52     13698851.64      2499763.89     13698169.56
#Sta/Elev= 30
  4304.4  262.97  4428.7  257.71  4528.3  252.83  4659.7  243.59  4808.5  238.95
  4977.8  233.69  4994.5  230.41  5006.1  223.11  5016.6  222.16  5028.8  226.02
  5074.3  227.17  5142.6  221.36  5159.8  231.23  5165.4  228.34  5171.5  231.94
  5204.7  232.26  5226.8  231.24  5273.5  218.95    5274  218.45  5284.8  218.95
  5292.3  224.32  5324.1  226.77  5421.1  226.05  5538.4  225.19  5584.7   229.2
  5668.9  233.37  5732.4  237.99    5811  249.55  5911.9  254.74  5993.1  254.12
#Mann= 9 ,-1 , 0
  4304.4     .07       0  4428.7    .035       0  4528.3     .12       0
  4808.5      .1       0  5273.5     .05       0  5284.8      .1       0
  5421.1     .12       0  5584.7      .1       0  5668.9     .12       0
Bank Sta=5273.5,5284.8
XS Rating Curve= 0 ,0
Exp/Cntr=0.3,0.1

Type RM Length L Ch R = 1 ,4183    ,1068,1068,1068
BEGIN DESCRIPTION:
X19216
END DESCRIPTION:
XS GIS Cut Line= 4
      2500258.19     13699765.13      2500440.89     13698937.61
      2500349.54     13697948.86      2500139.97     13697502.85
#Sta/Elev= 30
  4236.3  261.54  4500.5  247.69  4625.6     241  4779.2  237.38  4809.9  232.29
  4846.7  230.17  4861.1  234.54  4881.2   234.5  4944.3  225.28    4988  222.09
  5004.5  223.24  5019.3  214.11  5019.8  213.61  5030.7  214.11  5031.7   219.1
  5036.8  220.75  5082.5  225.33  5347.5  225.34  5397.7  222.78  5466.7  225.03
  5618.6  223.66  5695.9  226.66  5728.9  229.76  5744.9  232.39  5970.1  236.73
  6050.5   246.3  6126.7  261.44  6217.9  272.49  6368.2   274.8  6569.5  283.78
#Mann= 8 ,-1 , 0
  4236.3     .07       0  4500.5     .05       0  4881.2      .1       0
  5019.3     .05       0  5030.7      .1       0  5466.7     .05       0
  5695.9      .1       0  5728.9     .12       0
Bank Sta=5019.3,5030.7
XS Rating Curve= 0 ,0
Exp/Cntr=0.3,0.1

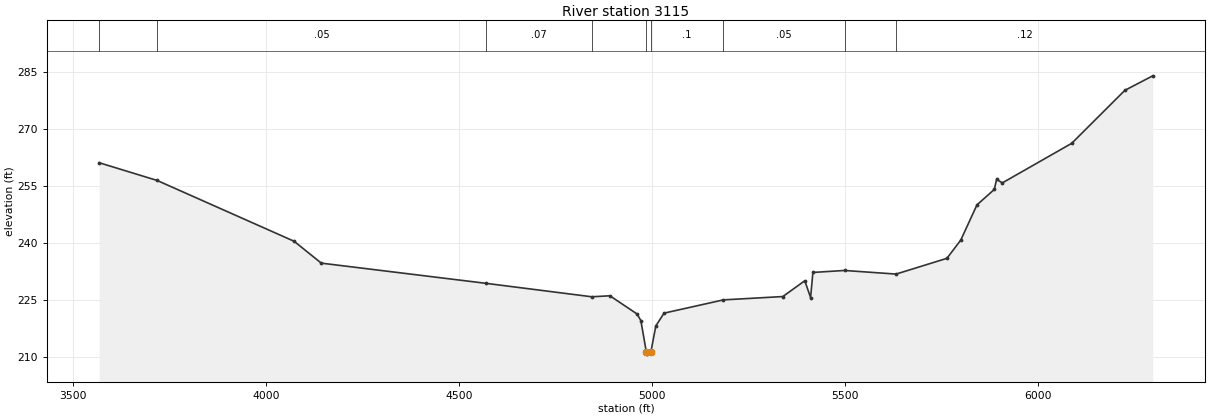
Type RM Length L Ch R = 1 ,3115    ,0,0,0
BEGIN DESCRIPTION:
X19215
END DESCRIPTION:
XS GIS Cut Line= 4
      2500311.96     13699765.13      2500860.04     13699265.41
      2500811.68     13698416.37      2500172.23       13697476.
#Sta/Elev= 30
  3567.6  261.13  3717.5  256.47  4072.4  240.45    4143  234.68  4570.5  229.35
  4843.6  225.82  4890.6  226.08  4960.8   221.3  4970.8  219.56  4985.1  211.21
  4985.6  210.71  4996.6  211.21  5009.6  218.15  5030.9  221.51  5184.6     225
  5338.6  225.88  5395.5  230.04  5410.5  225.61  5416.5  232.23  5498.4  232.75
    5632   231.8  5763.7  235.95  5799.6  240.76  5841.6  250.04  5886.4  254.09
  5892.4  256.74  5907.4  255.83    6087  266.25  6224.6   280.2  6296.9  284.03
#Mann= 9 ,-1 , 0
  3567.6     .07       0  3717.5     .05       0  4570.5     .07       0
  4843.6      .1       0  4985.1     .05       0  4996.6      .1       0
  5184.6     .05       0  5498.4      .1       0    5632     .12       0
Bank Sta=4985.1,4996.6
XS Rating Curve= 0 ,0
Exp/Cntr=0.3,0.1

Chan Stop Cuts=-1
Use User Specified Reach Order=0
Composite Channel Slope=5