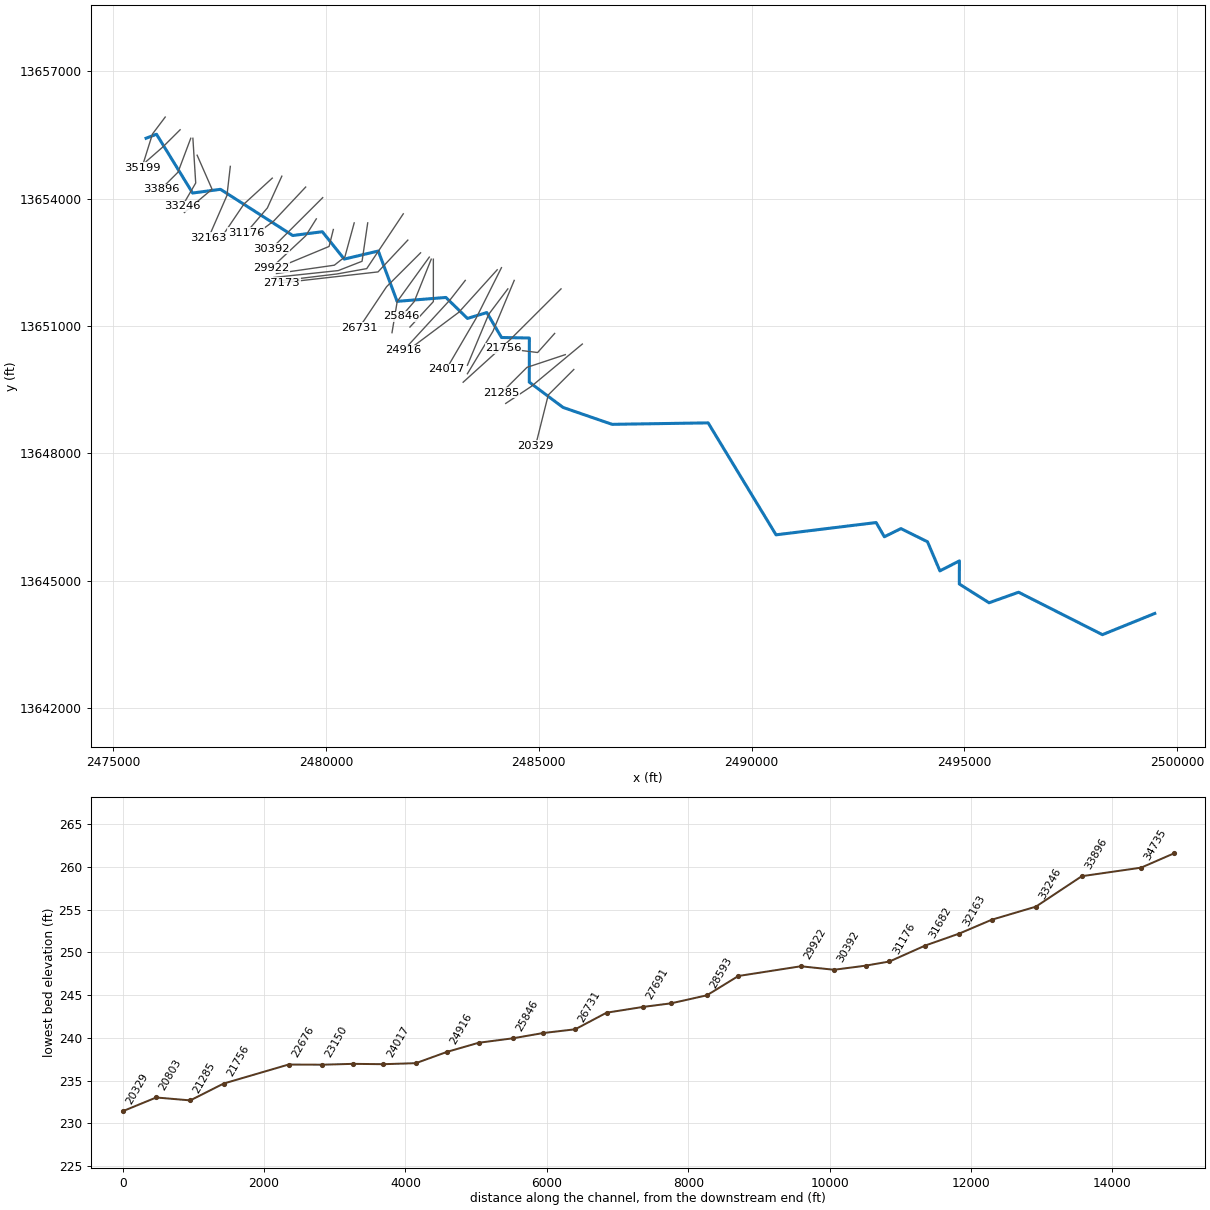
--- FULCHER CREEK.prj (project) ---

Proj Title=FULCHER CREEK Base Level Engineering
Current Plan=p01
Default Exp/Contr=0.3,0.1
English Units
Geom File=g01
Flow File=f01
Plan File=p01
Y Axis Title=Elevation
X Axis Title(PF)=Main Channel Distance
X Axis Title(XS)=Station
BEGIN DESCRIPTION:
FULCHER CREEK
END DESCRIPTION:
DSS Export Rating Curves= 0
DSS Export Rating Curve Sorted= 0
DSS Export Volume Flow Curves= 0
DXF OffsetX= 0
DXF OffsetY= 0
DXF ScaleX= 1
DXF ScaleY= 10

--- FULCHER CREEK.p01 (plan) ---

Plan Title=Multiple Run
Short Identifier=Multiple
Geom File=g01
Flow File=f01
Subcritical Flow
K Sum by GR= 0
Std Step Tol= 0.01
Critical Tol= 0.01
Num of Std Step Trials= 20
Max Error Tol= 0.3
Flow Tol Ratio= 0.001
Split Flow NTrial= 30
Split Flow Tol= 0.02
Split Flow Ratio= 0.02
Log Output Level= 0
Friction Slope Method= 1
Unsteady Friction Slope Method= 2
Unsteady Bridges Friction Slope Method= 1
Parabolic Critical Depth
Global Vel Dist=  1 , 1 , 1
Global Log Level= 0
CheckData=True
Encroach Param= -1, 0, 0, 0
BEGIN DESCRIPTION:
Multiple Run
END DESCRIPTION:

--- FULCHER CREEK.f01 (steady flow) ---

Flow Title=Multiple
Number of Profiles=7
Profile Names=10-year,25-year,50-year,1pct_min,100-year,1pct_plu,500-year
River Rch & RM= FULCHER CREEK,Reach-1,35199
     855    1396    1891    1240    2474    4936    4193
River Rch & RM= FULCHER CREEK,Reach-1,32622
    1125    1863    2547    1683    3358    6701    5785
River Rch & RM= FULCHER CREEK,Reach-1,31682
    1572    2635    3632    2416    4821    9618    8419
River Rch & RM= FULCHER CREEK,Reach-1,26731
    2279    3873    5386    3610    7204   14373   12777
River Rch & RM= FULCHER CREEK,Reach-1,24017
    2244    3790    5248    3502    6988   13942   12278
River Rch & RM= FULCHER CREEK,Reach-1,20329
    2274    3834    5302    3532    7048   14062   12345
River Rch & RM= FULCHER CREEK,Reach-1,17187
    3114    5303    7383    4947    9871   19695   17492
River Rch & RM= FULCHER CREEK,Reach-1,8369
    3347    5713    7967    5346   10667   21283   18955
River Rch & RM= FULCHER CREEK,Reach-1,3753
    3460    5913    8253    5542   11059   22065   19682
Boundary for River Rch & Prof#=FULCHER CREEK,Reach-1,1
Up Type=0
Dn Type=3
Dn Slope=0.005
Boundary for River Rch & Prof#=FULCHER CREEK,Reach-1,2
Up Type=0
Dn Type=3
Dn Slope=0.005
Boundary for River Rch & Prof#=FULCHER CREEK,Reach-1,3
Up Type=0
Dn Type=3
Dn Slope=0.005
Boundary for River Rch & Prof#=FULCHER CREEK,Reach-1,4
Up Type=0
Dn Type=3
Dn Slope=0.005
Boundary for River Rch & Prof#=FULCHER CREEK,Reach-1,5
Up Type=0
Dn Type=3
Dn Slope=0.005
Boundary for River Rch & Prof#=FULCHER CREEK,Reach-1,6
Up Type=0
Dn Type=3
Dn Slope=0.005
Boundary for River Rch & Prof#=FULCHER CREEK,Reach-1,7
Up Type=0
Dn Type=3
Dn Slope=0.005

--- FULCHER CREEK.g01 (geometry) ---

Geom Title=Existing Conditions
Program Version=4.10

River Reach=FULCHER CREEK   ,Reach-1
Reach XY= 30
        2475775.       13655425.      2476019.89     13655520.05
      2476868.45     13654134.24      2477523.78     13654221.56
      2479221.59     13653132.81      2479916.66     13653222.03
      2480430.85     13652577.06      2481231.52     13652767.33
       2481672.7     13651580.83      2482819.03     13651672.83
      2483326.36     13651178.29      2483781.07     13651316.89
      2484126.56     13650728.76      2484781.17     13650717.24
      2484778.76     13649676.56      2485572.55     13649080.47
      2486724.91     13648682.28      2488981.06     13648716.86
      2490576.28     13646078.37      2492928.17     13646367.49
       2493121.6     13646032.41      2493509.98     13646224.68
      2494135.18     13645914.68       2494426.5     13645228.47
      2494885.08     13645463.93      2494882.76     13644918.83
      2495581.12     13644476.76        2496275.       13644725.
      2498245.03     13643725.07        2499475.       13644225.

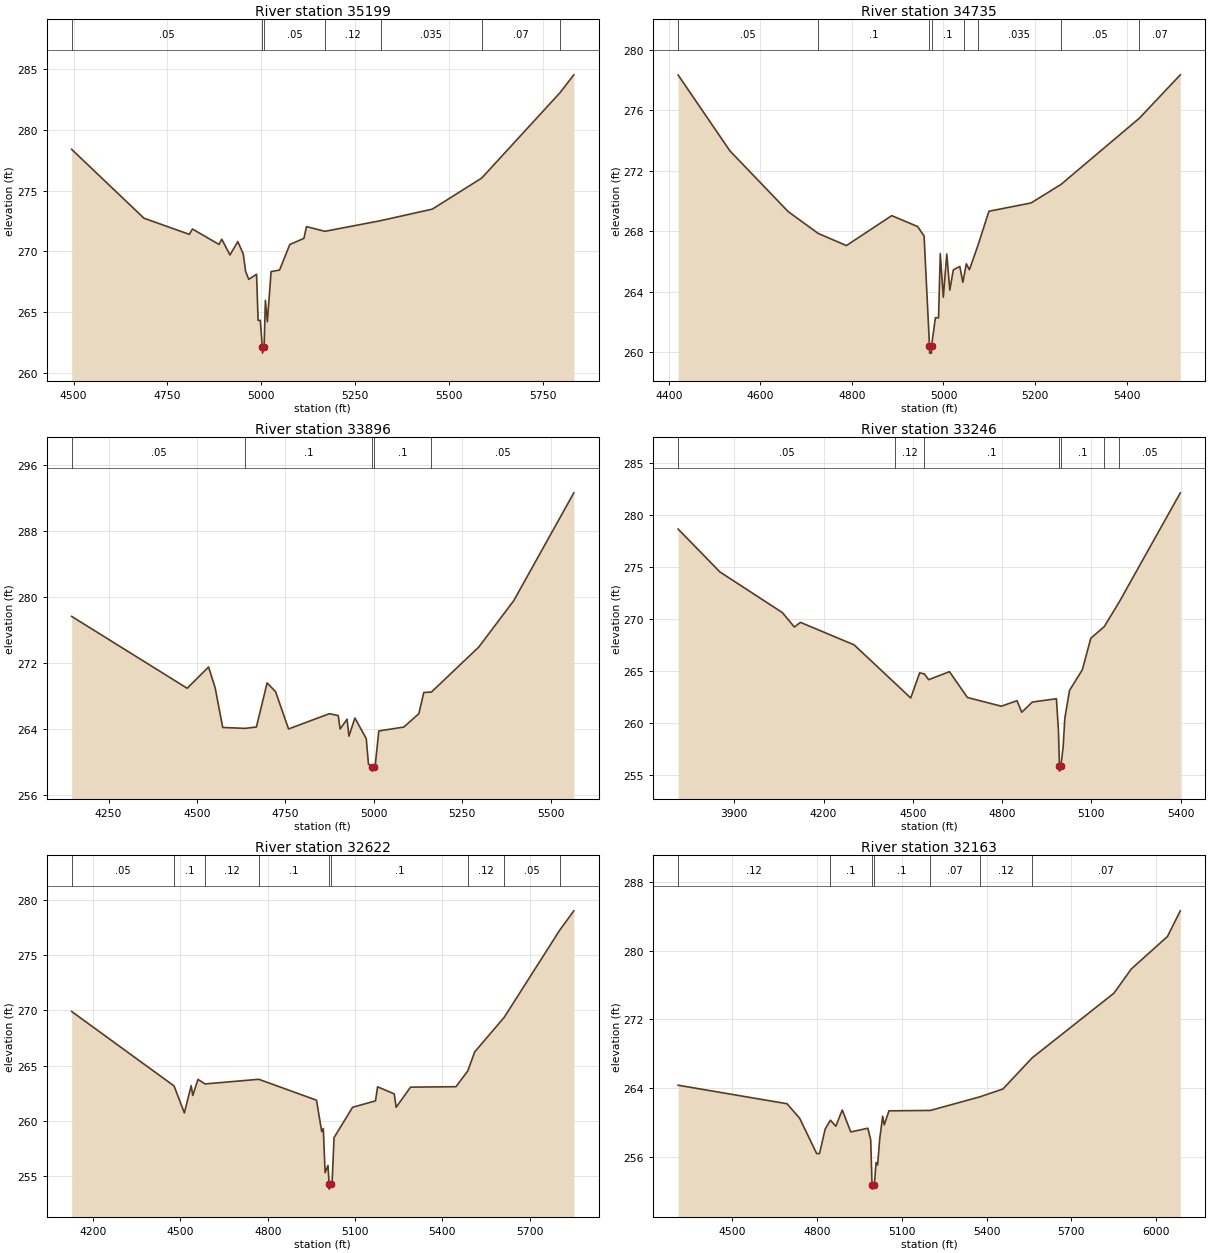
Type RM Length L Ch R = 1 ,35199   ,464,464,464
BEGIN DESCRIPTION:
FULCHER CREEK 56.0
END DESCRIPTION:
XS GIS Cut Line= 3
        2476225.       13655925.        2475925.       13655525.
      2475675.01     13654725.05
#Sta/Elev= 30
  4494.8   278.4  4687.5  272.72  4808.3  271.39  4816.7  271.83  4887.5  270.56
  4894.8  270.99  4916.7  269.69  4937.5  270.79  4952.1  269.78  4958.3  268.35
  4966.7  267.68  4987.5   268.1  4991.7   264.3  4997.4   264.3    5003   262.1
  5003.3   261.6  5007.6   262.1    5011  265.95  5016.3  264.19  5026.2  268.32
  5048.8  268.45    5076  270.55  5113.7  271.06  5120.5  272.03  5169.5  271.64
  5318.3  272.52  5455.8  273.47  5587.4  276.03  5795.6  283.05  5832.9  284.54
#Mann= 7 ,-1 , 0
  4494.8     .05       0    5003     .05       0  5007.6     .05       0
  5169.5     .12       0  5318.3    .035       0  5587.4     .07       0
  5795.6     .05       0
Bank Sta=5003,5007.6
XS Rating Curve= 0 ,0
Exp/Cntr=0.3,0.1

Type RM Length L Ch R = 1 ,34735   ,839,839,839
BEGIN DESCRIPTION:
FULCHER CREEK 55.0
END DESCRIPTION:
XS GIS Cut Line= 3
      2476574.97     13655624.97        2476175.       13655225.
      2475774.97     13654874.97
#Sta/Elev= 30
  4420.2  278.34  4533.3  273.32  4660.6   269.3  4726.4  267.85  4787.9  267.05
  4886.9  269.03  4943.4  268.31  4957.6  267.68  4969.4  260.43  4969.7  259.93
  4973.7  259.93    4974  260.43  4982.3  262.27  4989.2  262.27    4993  266.52
  4999.6  263.63  5007.2  266.49  5013.8   264.1  5021.4  265.44  5035.7  265.67
  5042.3  264.62  5045.3   265.1  5049.9  265.84  5056.6  265.45  5074.5  266.99
  5099.3  269.32  5191.3  269.87  5256.5  271.09    5428  275.48  5517.4  278.35
#Mann= 8 ,-1 , 0
  4420.2     .05       0  4726.4      .1       0  4969.4     .05       0
    4974      .1       0  5045.3     .12       0  5074.5    .035       0
  5256.5     .05       0    5428     .07       0
Bank Sta=4969.4,4974
XS Rating Curve= 0 ,0
Exp/Cntr=0.3,0.1

Type RM Length L Ch R = 1 ,33896   ,650,650,650
BEGIN DESCRIPTION:
FULCHER CREEK 54.0
END DESCRIPTION:
XS GIS Cut Line= 3
      2476825.02     13655425.04        2476525.       13654625.
      2476125.02     13654225.02
#Sta/Elev= 30
  4145.6  277.68  4472.3  268.97  4532.8  271.55  4551.5  269.01  4572.8  264.22
  4636.1  264.11  4668.1  264.28  4698.3  269.62  4722.4  268.55  4758.9  264.04
  4874.6  265.89  4899.5  265.66  4904.8  264.04  4924.4  265.22  4929.7  263.17
  4946.6  265.36  4978.7  262.87  4984.9   259.8    4995  259.43  4995.4  258.93
  4999.7  259.43  5003.6  259.43  5014.2   263.8  5084.9  264.27  5127.3  265.88
  5141.5  268.46  5162.9  268.51    5297  273.97    5396   279.6  5565.7  292.65
#Mann= 5 ,-1 , 0
  4145.6     .05       0  4636.1      .1       0    4995     .05       0
  4999.7      .1       0  5162.9     .05       0
Bank Sta=4995,4999.7
XS Rating Curve= 0 ,0
Exp/Cntr=0.3,0.1

Type RM Length L Ch R = 1 ,33246   ,624,624,624
BEGIN DESCRIPTION:
FULCHER CREEK 53.0
END DESCRIPTION:
XS GIS Cut Line= 3
        2476875.     13655425.01      2476941.41      13654370.2
      2476624.98     13653824.97
#Sta/Elev= 30
  3711.3  278.63  3851.6  274.51    4062  270.59  4102.1  269.21  4122.1  269.66
  4302.5   267.5  4440.5   263.8  4492.9  262.39  4522.9  264.81    4539   264.7
    4553  264.15  4623.1  264.92  4683.2  262.44  4797.3   261.6    4850  262.13
  4865.8  261.02  4901.4     262  4982.3  262.32  4989.1   259.3  4992.6  255.86
  4992.9  255.36  4997.3  255.86  5004.9  257.66  5010.7  260.46  5026.4  263.12
  5069.4   265.1  5097.9  268.13  5143.4  269.26  5193.6  271.63  5398.6  282.11
#Mann= 7 ,-1 , 0
  3711.3     .05       0  4440.5     .12       0    4539      .1       0
  4992.6     .05       0  4997.3      .1       0  5143.4     .07       0
  5193.6     .05       0
Bank Sta=4992.6,4997.3
XS Rating Curve= 0 ,0
Exp/Cntr=0.3,0.1

Type RM Length L Ch R = 1 ,32622   ,459,459,459
BEGIN DESCRIPTION:
FULCHER CREEK 52.0
END DESCRIPTION:
XS GIS Cut Line= 3
      2476974.98     13655025.03        2477325.       13654225.
      2476675.02     13653675.01
#Sta/Elev= 30
  4126.7  269.89  4478.4  263.16  4513.8  260.72  4537.2  263.18  4542.7   262.3
  4560.6  263.75  4584.6  263.34  4769.4  263.76  4967.6  261.87  4985.5  259.03
    4991  259.31  4997.2  255.32  5007.1  255.97  5010.8  254.33  5011.2  253.83
  5016.5  254.33  5021.4  254.56  5027.9  258.49  5091.6  261.23  5170.2  261.81
  5177.4  263.08  5234.6  262.44  5241.1  261.23  5290.5  263.05  5446.5  263.09
  5487.3  264.52  5510.8  266.23  5612.2  269.36  5802.9  277.24  5851.4  278.99
#Mann= 9 ,-1 , 0
  4126.7     .05       0  4478.4      .1       0  4584.6     .12       0
  4769.4      .1       0  5010.8     .05       0  5016.5      .1       0
  5487.3     .12       0  5612.2     .05       0  5802.9     .07       0
Bank Sta=5010.8,5016.5
XS Rating Curve= 0 ,0
Exp/Cntr=0.3,0.1

Type RM Length L Ch R = 1 ,32163   ,481,481,481
BEGIN DESCRIPTION:
FULCHER CREEK 51.0
END DESCRIPTION:
XS GIS Cut Line= 3
      2477754.24     13654762.22        2477675.       13654075.
      2477241.43     13653079.49
#Sta/Elev= 30
  4308.1  264.33  4693.6  262.17  4738.1  260.49  4798.5  256.36  4808.6  256.36
  4828.7  259.22  4847.2  260.25  4866.4  259.55  4889.1  261.44  4919.3  258.88
  4979.7  259.31  4989.8  257.96  4994.5  252.71    4995  252.21  5000.2  252.71
  5002.6  252.71  5008.9  255.32  5014.3  255.03  5021.7  258.08  5032.3  260.71
  5037.7   259.7  5054.4  261.34  5201.3  261.39  5376.8  262.98  5457.9  263.89
  5560.9  267.51  5850.6  275.06  5912.3  277.89  6040.4  281.68  6085.7  284.67
#Mann= 7 ,-1 , 0
  4308.1     .12       0  4847.2      .1       0  4994.5     .05       0
  5000.2      .1       0  5201.3     .07       0  5376.8     .12       0
  5560.9     .07       0
Bank Sta=4994.5,5000.2
XS Rating Curve= 0 ,0
Exp/Cntr=0.3,0.1

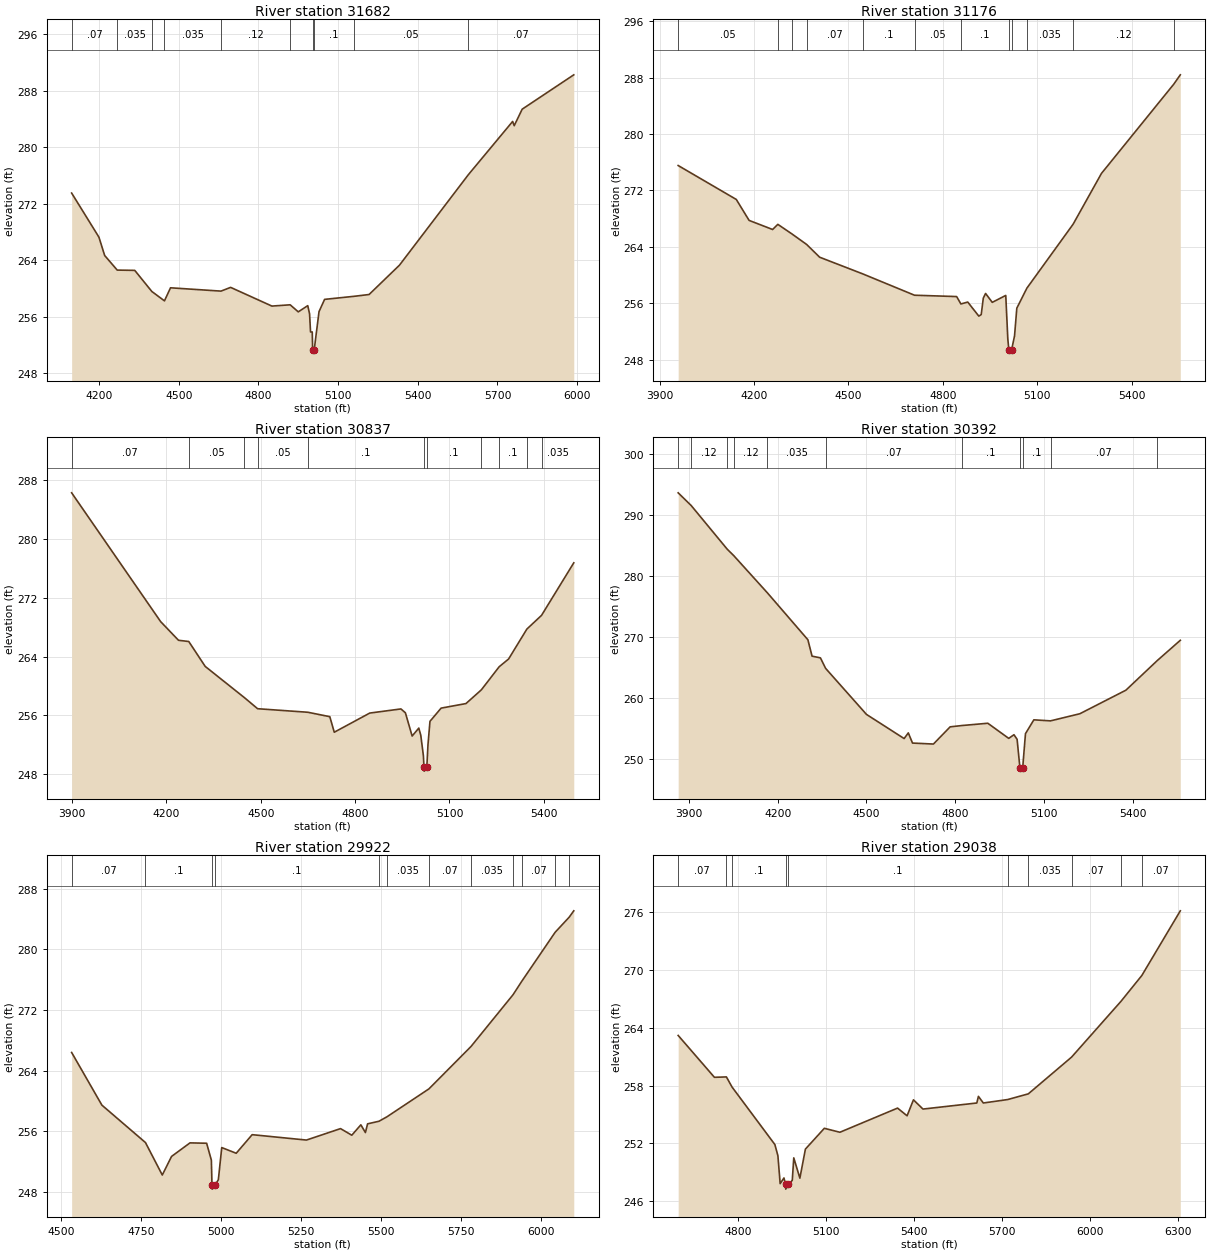
Type RM Length L Ch R = 1 ,31682   ,506,506,506
BEGIN DESCRIPTION:
FULCHER CREEK 50.0
END DESCRIPTION:
XS GIS Cut Line= 3
        2478740.     13654485.49        2478075.       13653875.
      2477523.62      13653055.8
#Sta/Elev= 30
    4097   273.5  4199.7  267.25  4221.3  264.65  4268.6  262.58  4334.6  262.54
  4398.8  259.55  4446.4  258.22  4469.2  260.07  4659.2   259.6  4695.4  260.13
  4850.8  257.48  4919.6  257.66  4950.1  256.66  4985.8  257.54  4992.6  256.39
  4996.3  253.81  5002.7  253.81  5004.2  251.31  5004.7  250.81  5010.2  251.31
  5028.2  256.69  5049.2  258.43  5159.4  258.86  5216.7  259.12  5331.1  263.28
  5590.5  276.11    5757  283.65    5763  283.05    5793  285.39  5987.2  290.26
#Mann= 10 ,-1 , 0
    4097     .07       0  4268.6    .035       0  4398.8     .07       0
  4446.4    .035       0  4659.2     .12       0  4919.6      .1       0
  5004.2     .05       0  5010.2      .1       0  5159.4     .05       0
  5590.5     .07       0
Bank Sta=5004.2,5010.2
XS Rating Curve= 0 ,0
Exp/Cntr=0.3,0.1

Type RM Length L Ch R = 1 ,31176   ,339,339,339
BEGIN DESCRIPTION:
X19221
END DESCRIPTION:
XS GIS Cut Line= 3
      2478964.82     13654531.59      2478624.71     13653782.19
      2478123.18      13653194.2
#Sta/Elev= 30
  3959.3  275.54    4144  270.73  4184.7  267.76  4259.4  266.47    4276   267.2
  4321.5  265.82  4367.8  264.34  4408.9  262.54  4545.6  260.18  4710.4  257.15
  4844.3  256.96  4857.8  255.91  4879.6  256.18  4914.7  254.19  4922.4   254.4
    4929  256.74  4936.3   257.4  4957.5  256.14  5000.4  257.12  5006.9  250.97
  5010.1  249.44  5010.6  248.94  5019.1  249.44  5028.3  251.39  5035.5  255.31
  5067.5  258.15  5214.3  267.21  5304.5  274.42  5534.6  287.09  5555.1   288.4
#Mann= 12 ,-1 , 0
  3959.3     .05       0    4276     .07       0  4321.5     .05       0
  4367.8     .07       0  4545.6      .1       0  4710.4     .05       0
  4857.8      .1       0  5010.1     .05       0  5019.1      .1       0
  5067.5    .035       0  5214.3     .12       0  5534.6     .07       0
Bank Sta=5010.1,5019.1
XS Rating Curve= 0 ,0
Exp/Cntr=0.3,0.1

Type RM Length L Ch R = 1 ,30837   ,445,445,445
BEGIN DESCRIPTION:
FULCHER CREEK 49.0
END DESCRIPTION:
XS GIS Cut Line= 3
      2479524.97     13654274.97        2478775.       13653475.
      2478375.03     13653175.03
#Sta/Elev= 30
  3898.7  286.22  4181.7  268.74  4238.4  266.21  4271.1  266.04  4323.4  262.66
  4448.1  258.42    4490  256.92  4649.4  256.44  4719.5  255.84  4733.7  253.73
  4846.5  256.33  4945.7  256.89  4959.8  256.37  4981.3  253.21  5002.5  254.29
  5008.8  253.31  5017.1  250.53  5018.9  248.95  5019.4  248.45  5027.9  248.95
  5031.7  252.07    5038  255.21  5073.4     257  5152.5  257.62  5201.5  259.49
  5257.9  262.61    5288  263.67  5346.1  267.73  5392.7  269.59  5495.2  276.72
#Mann= 11 ,-1 , 0
  3898.7     .07       0  4271.1     .05       0  4448.1    .035       0
    4490     .05       0  4649.4      .1       0  5018.9     .05       0
  5027.9      .1       0  5201.5     .12       0  5257.9      .1       0
  5346.1     .12       0  5392.7    .035       0
Bank Sta=5018.9,5027.9
XS Rating Curve= 0 ,0
Exp/Cntr=0.3,0.1

Type RM Length L Ch R = 1 ,30392   ,470,470,470
BEGIN DESCRIPTION:
FULCHER CREEK 48.0
END DESCRIPTION:
XS GIS Cut Line= 3
        2479925.       13654025.        2479125.       13653225.
      2478724.97     13652824.97
#Sta/Elev= 30
  3863.8   293.6  3907.9  291.51  4029.9  284.34  4051.3  283.32  4165.2  277.21
  4302.2  269.51  4316.3  266.82  4344.6  266.54  4362.1  264.82  4500.2  257.27
  4627.5  253.31  4641.6  254.24  4655.8  252.57  4726.5  252.41    4783  255.23
  4821.8  255.44  4910.3  255.82    4981  253.34  4998.7  253.94  5009.3  253.19
  5018.9  248.47  5019.4  247.97  5028.1  248.47  5037.6  254.11  5065.9  256.38
  5122.2  256.21  5221.4  257.38    5377  261.24  5483.3  266.11  5560.9  269.42
#Mann= 11 ,-1 , 0
  3863.8     .07       0  3907.9     .12       0  4029.9     .07       0
  4051.3     .12       0  4165.2    .035       0  4362.1     .07       0
  4821.8      .1       0  5018.9     .05       0  5028.1      .1       0
  5122.2     .07       0  5483.3    .035       0
Bank Sta=5018.9,5028.1
XS Rating Curve= 0 ,0
Exp/Cntr=0.3,0.1

Type RM Length L Ch R = 1 ,29922   ,884,884,884
BEGIN DESCRIPTION:
FULCHER CREEK 47.0
END DESCRIPTION:
XS GIS Cut Line= 3
      2479775.03     13653525.04        2479525.       13653125.
      2478725.02     13652375.02
#Sta/Elev= 30
  4532.9   266.4  4627.3  259.46  4763.5  254.52    4816  250.24  4844.9  252.69
  4902.6  254.48  4954.5  254.43  4969.3   252.2  4971.2  248.88  4971.7  248.38
  4980.4  248.88  4991.1  249.62  5001.7  253.86  5046.9  253.11  5096.7  255.56
  5266.2  254.85  5372.7  256.36  5407.9  255.49  5436.2  256.86  5450.4  255.84
  5457.2  256.99  5492.7  257.33  5517.4  257.91  5648.8   261.6  5780.2  267.19
  5911.6  274.02  5938.3  275.76    6043  282.25  6086.8  284.24  6101.2  285.08
#Mann= 12 ,-1 , 0
  4532.9     .07       0  4763.5      .1       0  4971.2     .05       0
  4980.4      .1       0  5492.7     .07       0  5517.4    .035       0
  5648.8     .07       0  5780.2    .035       0  5911.6     .12       0
  5938.3     .07       0    6043     .12       0  6086.8     .07       0
Bank Sta=4971.2,4980.4
XS Rating Curve= 0 ,0
Exp/Cntr=0.3,0.1

Type RM Length L Ch R = 1 ,29038   ,445,445,445
BEGIN DESCRIPTION:
FULCHER CREEK 46.0
END DESCRIPTION:
XS GIS Cut Line= 3
      2480174.99     13653274.95        2480075.       13652875.
      2478874.96     13652374.99
#Sta/Elev= 30
  4595.3  263.21  4718.9  258.86  4759.8   258.9    4779  257.85  4925.1  251.87
  4935.4  250.71  4943.1  247.81    4956   248.4  4961.5  247.74    4962  247.24
  4971.1  247.74  4984.4  248.15  4989.5  250.49  5010.3  248.38  5029.2   251.4
  5093.7  253.56  5146.8  253.15  5343.4  255.66  5375.9  254.86  5397.6  256.52
  5430.1  255.56  5613.7  256.19  5619.1  256.88  5635.9  256.19  5719.2  256.55
  5789.3  257.14  5936.9  260.96  6105.4  266.76  6176.4  269.44  6307.6  276.16
#Mann= 10 ,-1 , 0
  4595.3     .07       0  4759.8     .05       0    4779      .1       0
  4961.5     .05       0  4971.1      .1       0  5719.2     .07       0
  5789.3    .035       0  5936.9     .07       0  6105.4    .035       0
  6176.4     .07       0
Bank Sta=4961.5,4971.1
XS Rating Curve= 0 ,0
Exp/Cntr=0.3,0.1

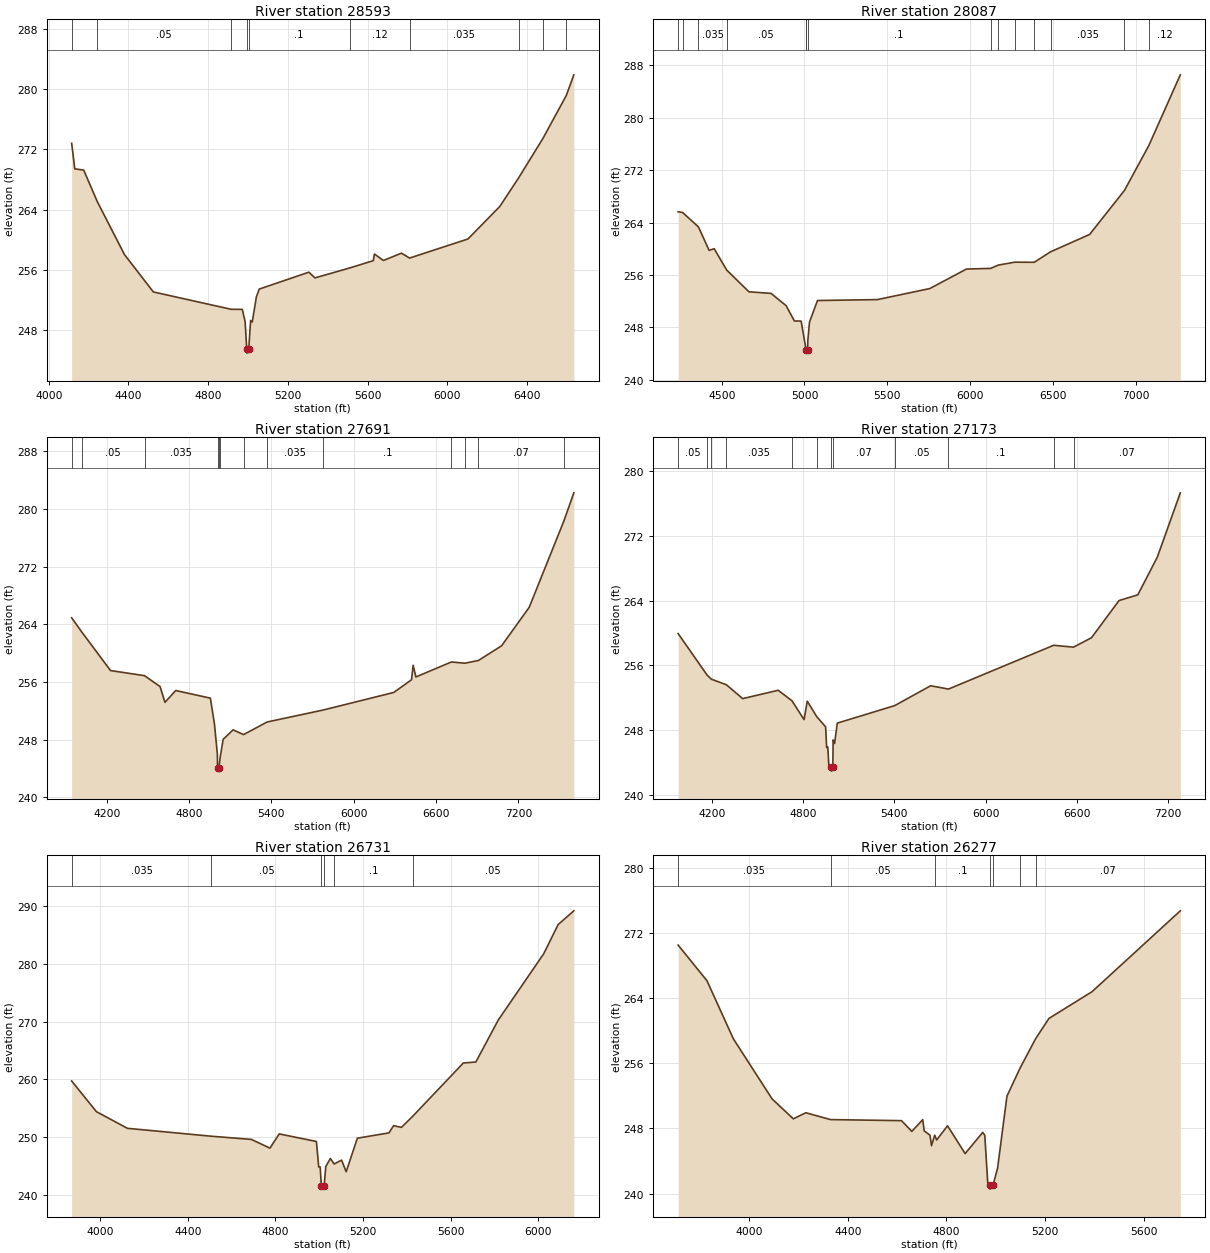
Type RM Length L Ch R = 1 ,28593   ,506,506,506
BEGIN DESCRIPTION:
X19222
END DESCRIPTION:
XS GIS Cut Line= 4
      2480665.41     13653430.51      2480446.37     13652629.25
      2480198.48     13652433.25      2478838.99     13652237.39
#Sta/Elev= 30
  4115.1   272.8  4130.8  269.41  4175.7  269.24  4243.5  265.08    4380  258.05
  4525.1  253.09  4915.8  250.79  4971.7  250.78  4985.7  249.12    4994  245.48
  4994.5  244.98  5003.7  245.48  5013.3  249.31  5021.4   249.1  5042.2  252.44
  5056.6  253.47  5305.7  255.71    5336  254.95  5510.8  256.27    5629  257.24
  5634.6  258.12  5679.5  257.26  5770.4  258.23    5811  257.58  6103.9  260.11
  6263.4  264.41  6358.2  268.21  6479.8  273.42  6597.1  279.11  6635.3  281.87
#Mann= 10 ,-1 , 0
  4115.1    .035       0  4243.5     .05       0  4915.8      .1       0
    4994     .05       0  5003.7      .1       0  5510.8     .12       0
    5811    .035       0  6358.2     .07       0  6479.8     .12       0
  6597.1     .07       0
Bank Sta=4994,5003.7
XS Rating Curve= 0 ,0
Exp/Cntr=0.3,0.1

Type RM Length L Ch R = 1 ,28087   ,396,396,396
BEGIN DESCRIPTION:
X19223
END DESCRIPTION:
XS GIS Cut Line= 4
      2480982.49     13653430.56       2480849.9     13652525.48
      2480290.72     13652306.42      2478780.31       13652145.
#Sta/Elev= 30
  4236.4  265.64  4263.7  265.53  4359.1  263.33  4423.9  259.74  4454.3     260
  4529.7  256.74  4664.5  253.41  4797.9  253.17  4888.8   251.3  4938.9  248.96
  4979.8  248.93  5007.2  244.92    5009  244.54  5009.5  244.04  5018.7  244.54
  5020.2  245.99  5030.3   248.8  5078.6  252.08  5440.7  252.22  5757.4  253.91
  5978.7  256.89  6125.1  256.99  6170.4  257.49  6269.9  257.94  6387.9  257.92
  6486.6  259.52  6722.9  262.18  6933.2   268.9  7080.7  275.77  7270.7  286.57
#Mann= 14 ,-1 , 0
  4236.4    .035       0  4263.7     .05       0  4359.1    .035       0
  4529.7     .05       0  5007.2      .1       0    5009     .05       0
  5018.7      .1       0  6125.1     .12       0  6170.4      .1       0
  6269.9     .12       0  6387.9     .07       0  6486.6    .035       0
  6933.2     .07       0  7080.7     .12       0
Bank Sta=5009,5018.7
XS Rating Curve= 0 ,0
Exp/Cntr=0.3,0.1

Type RM Length L Ch R = 1 ,27691   ,518,518,518
BEGIN DESCRIPTION:
X19224
END DESCRIPTION:
XS GIS Cut Line= 4
      2481818.35      13653643.8      2480959.43     13652352.54
      2480256.13     13652225.72      2478872.57     13652058.54
#Sta/Elev= 30
  3945.1   264.9  4020.5  262.89  4228.5  257.58  4475.9  256.87  4589.2  255.36
  4625.2  253.17  4703.4  254.81  4955.9  253.75  4985.9  250.12    5007  245.94
  5008.1  244.12  5008.6  243.62  5017.9  244.12  5028.6  245.68  5049.1  248.03
  5121.2  249.35  5197.6  248.69  5369.4  250.44  5777.7   252.1  6292.3  254.54
  6421.6   256.3  6433.3  258.31  6453.5  256.69  6711.7  258.77  6810.5   258.6
  6909.3  258.98    7078  261.02  7279.4  266.37  7531.5  278.33  7604.2  282.25
#Mann= 13 ,-1 , 0
  3945.1    .035       0  4020.5     .05       0  4475.9    .035       0
  5008.1    .035       0  5017.9    .035       0  5028.6      .1       0
  5197.6     .07       0  5369.4    .035       0  5777.7      .1       0
  6711.7     .07       0  6810.5     .12       0  6909.3     .07       0
  7531.5     .12       0
Bank Sta=5008.1,5017.9
XS Rating Curve= 0 ,0
Exp/Cntr=0.3,0.1

Type RM Length L Ch R = 1 ,27173   ,442,442,442
BEGIN DESCRIPTION:
FULCHER CREEK 45.0
END DESCRIPTION:
XS GIS Cut Line= 3
      2481924.98     13653024.98        2481225.       13652275.
      2478964.83     13652018.18
#Sta/Elev= 30
  3978.7  259.94  4169.6   254.8  4197.1   254.3  4295.5  253.62    4403   251.9
  4636.5  252.93  4727.2  251.63  4806.5   249.3  4827.5  251.58  4889.2  249.69
  4948.2  248.41    4955  245.84  4962.3  245.93  4969.2   243.7  4985.8  243.44
  4986.3  242.94  4995.6  243.44  4997.5  246.79  5007.1  246.36  5024.7  248.87
  5402.7  251.04  5638.6  253.49  5755.6  253.08    6447  258.49  6577.5  258.26
  6695.4  259.42  6876.6  264.02  6999.9  264.72  7128.2  269.38  7279.3  277.33
#Mann= 12 ,-1 , 0
  3978.7     .05       0  4169.6    .035       0  4197.1     .05       0
  4295.5    .035       0  4727.2     .12       0  4889.2     .07       0
  4985.8    .035       0  4995.6     .07       0  5402.7     .05       0
  5755.6      .1       0    6447     .12       0  6577.5     .07       0
Bank Sta=4985.8,4995.6
XS Rating Curve= 0 ,0
Exp/Cntr=0.3,0.1

Type RM Length L Ch R = 1 ,26731   ,454,454,454
BEGIN DESCRIPTION:
FULCHER CREEK 44.0
END DESCRIPTION:
XS GIS Cut Line= 3
      2482225.01     13652725.01        2481425.       13651925.
      2480781.55     13650958.72
#Sta/Elev= 30
  3869.6  259.73  3982.8  254.41  4124.2  251.53  4507.1  250.16  4689.9  249.61
  4774.7   248.1  4817.1  250.56  4986.8  249.25  4997.4  244.84    5004  244.84
  5009.6   241.5  5010.1     241  5019.4   241.5  5023.5  242.11  5029.5  244.91
  5050.6   246.3  5067.9  245.35  5101.7  246.02  5122.7  244.01  5173.8  249.82
    5318  250.74  5339.1  251.98  5375.1   251.7  5426.1   253.6  5657.6  262.84
  5714.7  263.01  5816.9  270.28  6024.3  281.75  6090.4  286.82  6161.9  289.19
#Mann= 6 ,-1 , 0
  3869.6    .035       0  4507.1     .05       0  5009.6     .05       0
  5019.4     .05       0  5067.9      .1       0  5426.1     .05       0
Bank Sta=5009.6,5019.4
XS Rating Curve= 0 ,0
Exp/Cntr=0.3,0.1

Type RM Length L Ch R = 1 ,26277   ,431,431,431
BEGIN DESCRIPTION:
FULCHER CREEK 43.0
END DESCRIPTION:
XS GIS Cut Line= 3
      2482429.41     13652623.45        2481675.       13651575.
       2481553.2     13650842.21
#Sta/Elev= 30
  3712.8   270.5  3829.8  266.12  3936.6     259  4093.7  251.62  4179.6  249.18
    4230  249.93  4330.4  249.09  4617.8  248.96  4659.6  247.64  4703.7  249.08
  4709.9   247.7  4733.2  247.18  4739.3  245.89  4752.4  247.18  4760.2  246.59
  4804.4  248.33  4875.6  244.92  4946.8  247.52  4955.2  247.16  4967.7  241.11
    4976  241.06  4976.5  240.56  4988.7  241.06    5007  243.12    5045  251.96
  5097.7  255.38  5160.7  258.99  5215.1   261.5  5389.7  264.78  5747.3   274.7
#Mann= 7 ,-1 , 0
  3712.8    .035       0  4330.4     .05       0  4752.4      .1       0
    4976     .05       0  4988.7      .1       0  5097.7     .05       0
  5160.7     .07       0
Bank Sta=4976,4988.7
XS Rating Curve= 0 ,0
Exp/Cntr=0.3,0.1

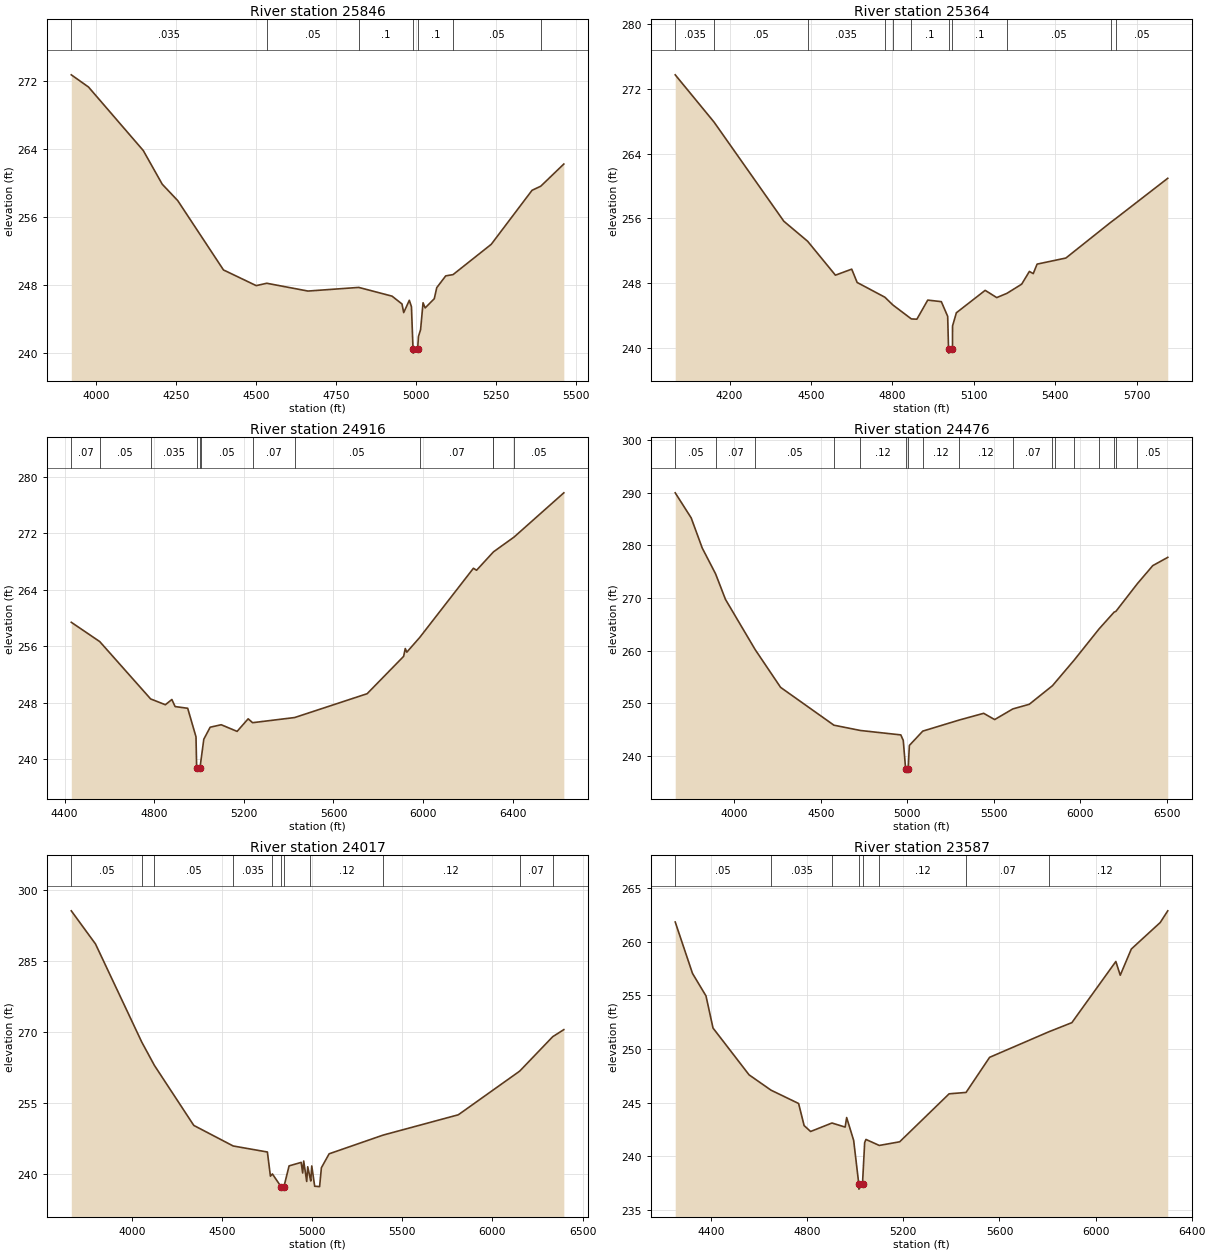
Type RM Length L Ch R = 1 ,25846   ,482,482,482
BEGIN DESCRIPTION:
FULCHER CREEK 42.0
END DESCRIPTION:
XS GIS Cut Line= 3
      2482474.99     13652574.98        2482075.       13651575.
      2481774.99     13651224.99
#Sta/Elev= 30
    3923  272.76  3976.8  271.32  4147.8  263.83    4207  259.86  4255.5  257.92
  4398.2  249.75  4500.5   247.9  4533.3  248.18  4662.1  247.26  4820.6  247.69
  4924.6  246.66  4955.6  245.74    4961  244.72  4978.5  246.17  4985.2  245.41
  4990.1  240.44  4990.6  239.94  5004.5  240.44  5007.1  241.91  5013.7   242.7
  5021.4  245.88    5028  245.27  5056.5  246.36  5064.2  247.66  5092.2  249.05
  5115.1   249.2  5234.3  252.77  5361.7  259.14  5389.1  259.63    5461  262.24
#Mann= 7 ,-1 , 0
    3923    .035       0  4533.3     .05       0  4820.6      .1       0
  4990.1     .05       0  5004.5      .1       0  5115.1     .05       0
  5389.1     .07       0
Bank Sta=4990.1,5004.5
XS Rating Curve= 0 ,0
Exp/Cntr=0.3,0.1

Type RM Length L Ch R = 1 ,25364   ,448,448,448
BEGIN DESCRIPTION:
FULCHER CREEK 41.0
END DESCRIPTION:
XS GIS Cut Line= 3
        2482525.     13652574.99        2482525.       13651575.
      2481975.02     13650975.02
#Sta/Elev= 30
    4000  273.69    4143  267.87    4400  255.66  4487.5   253.2    4590  249.02
    4650  249.76    4670  248.12  4771.9  246.31  4801.6  245.35  4869.7  243.63
    4890   243.6    4930  245.95    4980  245.76  5003.4  243.95  5006.6  239.92
  5007.1  239.42  5021.1  239.92  5021.3  242.76  5035.4  244.39  5141.5  247.15
  5184.1  246.26  5221.5  246.78  5275.9  247.91  5304.3  249.48  5318.5  249.21
  5332.7  250.38  5438.7  251.13  5604.7  255.55  5624.2  256.04  5813.9  260.95
#Mann= 11 ,-1 , 0
    4000    .035       0    4143     .05       0  4487.5    .035       0
  4771.9     .07       0  4801.6     .05       0  4869.7      .1       0
  5006.6     .05       0  5021.1      .1       0  5221.5     .05       0
  5604.7     .07       0  5624.2     .05       0
Bank Sta=5006.6,5021.1
XS Rating Curve= 0 ,0
Exp/Cntr=0.3,0.1

Type RM Length L Ch R = 1 ,24916   ,440,440,440
BEGIN DESCRIPTION:
FULCHER CREEK 40.0
END DESCRIPTION:
XS GIS Cut Line= 3
      2483274.98     13652074.97        2482925.       13651625.
      2481825.02     13650425.02
#Sta/Elev= 30
    4430   259.4    4557  256.67  4784.1  248.56  4849.8  247.74  4878.8  248.48
  4893.3  247.48  4949.4  247.24  4986.5   243.2  4989.4  238.85  4989.9  238.35
  5004.4  238.85  5010.6  240.32  5021.3  242.86  5049.7  244.56    5099  244.91
  5169.9  243.97  5219.3  245.75    5239   245.2  5426.9  245.93  5750.2   249.3
    5913  254.58  5920.4  255.69  5927.1  255.17  5984.7  257.25  6224.4  267.04
  6238.5  266.76  6313.3  269.34  6313.8  269.36  6405.7  271.45  6627.9  277.71
#Mann= 12 ,-1 , 0
    4430     .07       0    4557     .05       0  4784.1    .035       0
  4989.4    .035       0  5004.4    .035       0  5010.6     .05       0
    5239     .07       0  5426.9     .05       0  5984.7     .07       0
  6313.3     .12       0  6313.8     .07       0  6405.7     .05       0
Bank Sta=4989.4,5004.4
XS Rating Curve= 0 ,0
Exp/Cntr=0.3,0.1

Type RM Length L Ch R = 1 ,24476   ,459,459,459
BEGIN DESCRIPTION:
FULCHER CREEK 39.0
END DESCRIPTION:
XS GIS Cut Line= 3
      2484025.03     13652325.03        2483125.       13651325.
        2481925.       13650425.
#Sta/Elev= 30
  3659.1  290.03  3751.4  285.25    3815  279.53  3892.3   274.6  3949.5  269.73
  4121.2  260.16  4267.9  252.98  4575.9  245.78  4728.9  244.77  4962.3  243.93
  4976.5  242.88  4989.9  237.53  4990.4  237.03  5004.9  237.53  5011.8  241.92
  5089.2  244.65  5299.7  246.76    5441  248.04  5504.5  246.85  5609.2  248.87
  5704.5  249.76  5838.5   253.3  5853.1  253.87  5964.2  258.19  6108.4  264.14
  6194.4   267.3    6205  267.46  6329.4  272.75    6418  276.17  6504.5  277.74
#Mann= 17 ,-1 , 0
  3659.1     .05       0  3892.3     .07       0  4121.2     .05       0
  4575.9    .035       0  4728.9     .12       0  4989.9     .05       0
  5004.9     .12       0  5089.2     .12       0  5299.7     .12       0
  5609.2     .07       0  5838.5     .05       0  5853.1     .12       0
  5964.2     .07       0  6108.4     .12       0  6194.4     .05       0
    6205     .07       0  6329.4     .05       0
Bank Sta=4989.9,5004.9
XS Rating Curve= 0 ,0
Exp/Cntr=0.3,0.1

Type RM Length L Ch R = 1 ,24017   ,430,430,430
BEGIN DESCRIPTION:
FULCHER CREEK 38.0
END DESCRIPTION:
XS GIS Cut Line= 3
      2484125.01     13652375.02        2483525.       13651175.
        2482825.     13649975.01
#Sta/Elev= 30
  3664.7  295.61  3798.9  288.62  4055.8   267.9  4125.7     263  4343.9  250.35
  4562.3  246.01    4752  244.74  4768.8  239.64  4779.6  240.12  4828.1  237.41
  4828.6  236.91  4843.7  237.41  4872.2  241.81  4939.3  242.55  4947.7  240.31
  4953.3  242.84    4970  238.53  4975.6  241.63  4987.3  239.54  4992.4  238.63
    4998   241.8  5014.2  237.52  5041.5  237.44  5051.4  241.42  5094.4  244.36
  5393.1   248.3  5810.6  252.59  6150.9   261.8  6333.9  269.06  6395.6  270.55
#Mann= 11 ,-1 , 0
  3664.7     .05       0  4055.8     .07       0  4125.7     .05       0
  4562.3    .035       0  4779.6      .1       0  4828.1     .05       0
  4843.7      .1       0  4987.3     .12       0  5393.1     .12       0
  6150.9     .07       0  6333.9     .05       0
Bank Sta=4828.1,4843.7
XS Rating Curve= 0 ,0
Exp/Cntr=0.3,0.1

Type RM Length L Ch R = 1 ,23587   ,437,437,437
BEGIN DESCRIPTION:
FULCHER CREEK 37.0
END DESCRIPTION:
XS GIS Cut Line= 3
        2484275.       13651875.        2483825.       13651275.
        2483325.       13650075.
#Sta/Elev= 30
  4250.5  261.84  4322.4  257.05  4378.6  254.95  4407.8  251.96  4557.8   247.6
  4649.2  246.17    4764  244.93    4787  242.87    4814  242.32  4902.9  243.11
  4957.8  242.73    4964  243.62  4993.2  241.49  5014.4  237.45  5014.9  236.95
    5030  237.45    5039  241.28  5044.4  241.58  5099.8  241.02  5184.7  241.36
  5390.5  245.83    5461  245.96    5559  249.23  5804.5   251.6  5901.3  252.46
  6084.4  258.16  6102.8  256.88  6148.8  259.32  6269.1  261.79  6300.5  262.88
#Mann= 9 ,-1 , 0
  4250.5     .05       0  4649.2    .035       0  4902.9      .1       0
  5014.4     .05       0    5030      .1       0  5099.8     .12       0
    5461     .07       0  5804.5     .12       0  6269.1     .07       0
Bank Sta=5014.4,5030
XS Rating Curve= 0 ,0
Exp/Cntr=0.3,0.1

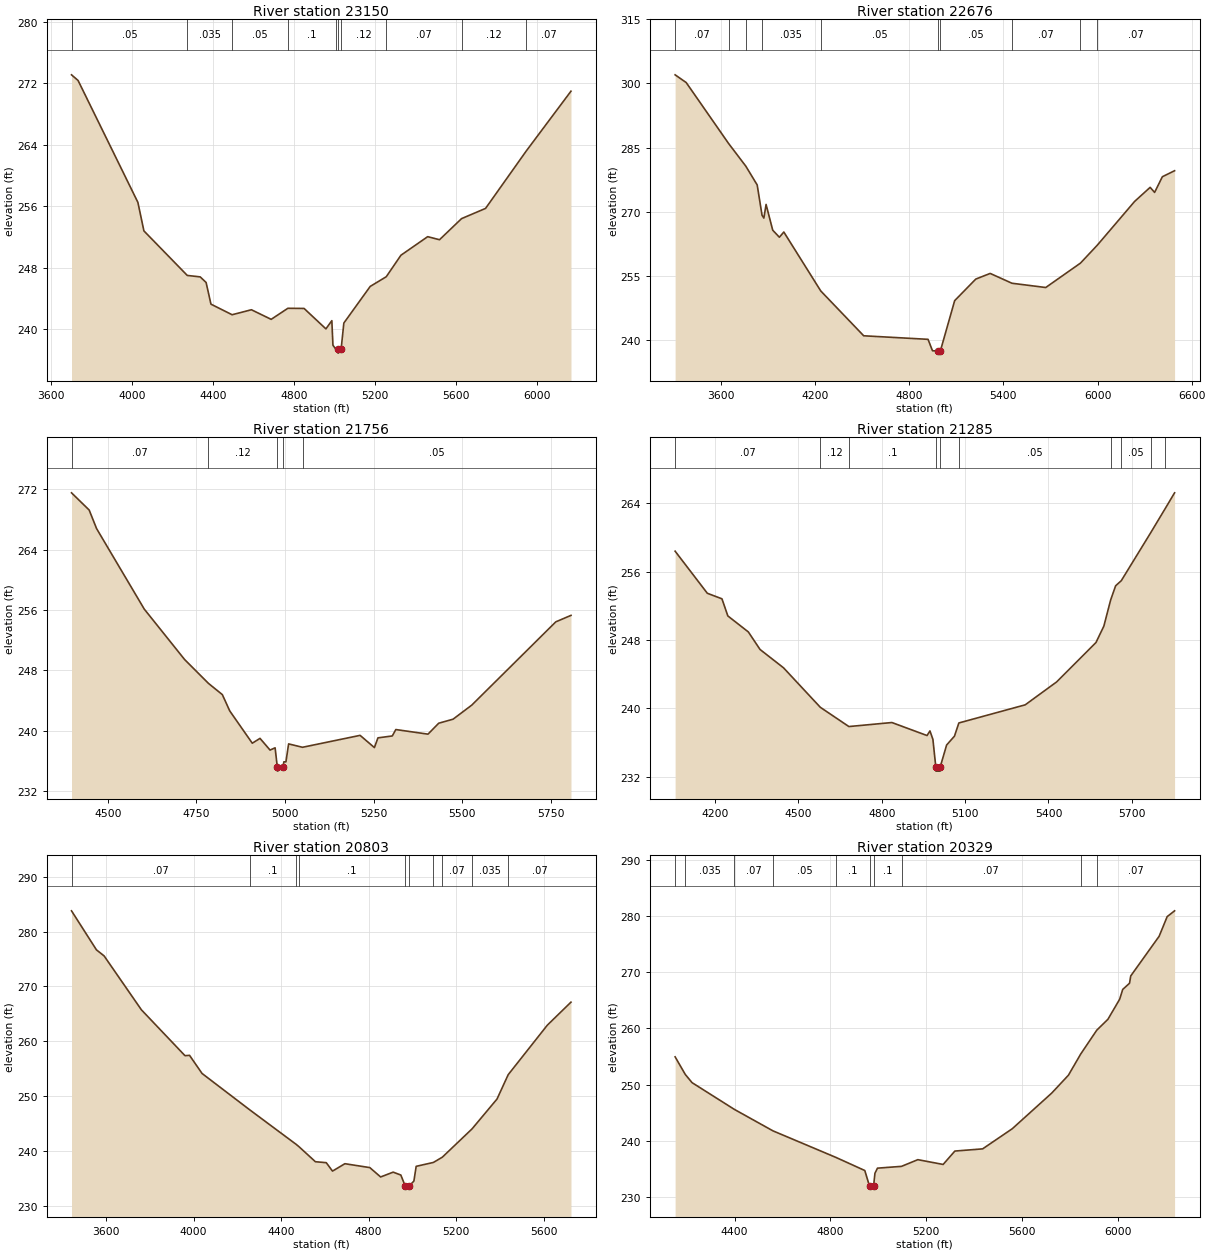
Type RM Length L Ch R = 1 ,23150   ,474,474,474
BEGIN DESCRIPTION:
FULCHER CREEK 36.0
END DESCRIPTION:
XS GIS Cut Line= 3
        2484425.     13652074.99        2483925.       13650875.
      2483324.99     13649874.99
#Sta/Elev= 30
  3699.7   273.1  3732.2  272.36  4027.4  256.49  4057.2  252.77  4271.3  246.97
  4335.1  246.78  4364.3  246.05  4388.2  243.23  4492.7  241.85    4588   242.5
  4685.5  241.25    4768  242.69    4848  242.67  4955.8  240.01  4985.1  241.08
  4990.5  237.88    5004  237.39  5015.2  237.35  5015.7  236.85  5030.8  237.35
  5044.4  240.77  5174.6  245.54  5253.8   246.8  5326.2   249.6  5458.4  252.02
  5516.7  251.62  5625.6  254.37  5744.1   255.7  5944.8  263.17  6165.9  270.97
#Mann= 10 ,-1 , 0
  3699.7     .05       0  4271.3    .035       0  4492.7     .05       0
    4768      .1       0    5004     .12       0  5015.2     .05       0
  5030.8     .12       0  5253.8     .07       0  5625.6     .12       0
  5944.8     .07       0
Bank Sta=5015.2,5030.8
XS Rating Curve= 0 ,0
Exp/Cntr=0.3,0.1

Type RM Length L Ch R = 1 ,22676   ,920,920,920
BEGIN DESCRIPTION:
FULCHER CREEK 35.0
END DESCRIPTION:
XS GIS Cut Line= 3
      2485524.99     13651874.99        2484325.       13650675.
      2483225.03     13649675.03
#Sta/Elev= 30
  3307.6  302.02  3378.3  300.21    3648  285.97  3758.4  280.63  3830.8  276.24
  3861.7  269.15  3873.3  268.48  3887.4  271.68  3929.8  265.65  3972.3     264
  4000.5  265.22  4236.3  251.41  4509.7  240.93  4919.8   240.1  4948.1  237.43
  4982.6  237.37  4983.1  236.87  4998.3  237.37  5089.4  249.15  5223.9   254.2
  5315.8  255.53  5454.5  253.23  5669.9  252.23  5891.3  257.94  5998.8  262.15
  6236.2  272.37  6335.5  275.68  6363.9  274.49  6413.2  278.16  6491.2  279.57
#Mann= 10 ,-1 , 0
  3307.6     .07       0    3648     .05       0  3758.4     .07       0
  3861.7    .035       0  4236.3     .05       0  4982.6     .05       0
  4998.3     .05       0  5454.5     .07       0  5891.3     .12       0
  5998.8     .07       0
Bank Sta=4982.6,4998.3
XS Rating Curve= 0 ,0
Exp/Cntr=0.3,0.1

Type RM Length L Ch R = 1 ,21756   ,471,471,471
BEGIN DESCRIPTION:
FULCHER CREEK 34.0
END DESCRIPTION:
XS GIS Cut Line= 3
      2485375.03     13650825.03        2484975.       13650375.
      2484174.95     13650475.01
#Sta/Elev= 30
  4397.9  271.52  4447.7  269.24  4468.6  266.78  4603.2   256.1    4717  249.42
    4784  246.27  4823.2  244.78  4844.1  242.62  4907.6  238.34  4929.4  238.98
  4957.8  237.43    4972  237.73  4978.3  235.14  4978.8  234.64  4994.2  235.14
  4996.7  235.87  5002.5  235.87  5010.1  238.25  5049.3   237.8  5211.7  239.38
    5252  237.76    5262  239.05  5302.4   239.3  5312.4  240.15  5403.1  239.54
  5433.4  240.99  5473.7  241.52  5526.6  243.39  5763.4  254.42  5806.3  255.28
#Mann= 5 ,-1 , 0
  4397.9     .07       0    4784     .12       0  4978.3     .05       0
  4994.2     .12       0  5049.3     .05       0
Bank Sta=4978.3,4994.2
XS Rating Curve= 0 ,0
Exp/Cntr=0.3,0.1

Type RM Length L Ch R = 1 ,21285   ,482,482,482
BEGIN DESCRIPTION:
FULCHER CREEK 33.0
END DESCRIPTION:
XS GIS Cut Line= 3
      2485624.96     13650324.99        2484725.       13650025.
      2484124.98     13649424.98
#Sta/Elev= 30
  4056.7  258.38  4172.6  253.46  4225.3  252.81  4246.4  250.81  4320.2  248.94
  4362.3  246.89  4446.7  244.75  4579.2  240.13    4682  237.88  4836.7  238.35
  4963.2  236.83  4973.7  237.37  4984.3  236.38  4994.7  233.17  4995.2  232.67
  5010.2  232.67  5010.7  233.17  5033.6  235.72  5061.9  236.76  5077.7   238.3
  5316.5  240.42  5429.6   243.1    5571   247.7  5599.3  249.61  5623.9  252.68
  5641.7  254.33  5662.1  254.93  5767.3   260.5  5821.1  263.41  5853.9   265.2
#Mann= 10 ,-1 , 0
  4056.7     .07       0  4579.2     .12       0    4682      .1       0
  4994.7     .05       0  5010.7      .1       0  5077.7     .05       0
  5623.9     .07       0  5662.1     .05       0  5767.3     .07       0
  5821.1     .12       0
Bank Sta=4994.7,5010.7
XS Rating Curve= 0 ,0
Exp/Cntr=0.3,0.1

Type RM Length L Ch R = 1 ,20803   ,474,474,474
BEGIN DESCRIPTION:
FULCHER CREEK 32.0
END DESCRIPTION:
XS GIS Cut Line= 3
      2486024.98     13650574.98        2484825.       13649575.
      2484225.03     13649175.02
#Sta/Elev= 30
  3442.4  283.81  3556.3  276.69  3591.4  275.58  3761.9  265.74  3961.1  257.37
  3981.9  257.43  4039.2  254.12  4258.2  247.45  4468.4  241.21  4481.5  240.78
  4557.3  238.01  4606.8  237.84  4635.4   236.3    4692  237.65  4805.9  236.94
  4855.4  235.23  4912.7  236.11  4947.8  235.58  4968.4  233.51  4968.9  233.01
  4984.4  233.51  5007.4  234.48  5017.9  237.17  5096.6  237.88  5137.4  238.84
  5273.1     244  5387.5  249.46  5438.5   253.9  5617.4  262.94  5725.5  267.14
#Mann= 10 ,-1 , 0
  3442.4     .07       0  4258.2      .1       0  4468.4     .07       0
  4481.5      .1       0  4968.4     .05       0  4984.4      .1       0
  5096.6     .05       0  5137.4     .07       0  5273.1    .035       0
  5438.5     .07       0
Bank Sta=4968.4,4984.4
XS Rating Curve= 0 ,0
Exp/Cntr=0.3,0.1

Type RM Length L Ch R = 1 ,20329   ,470,470,470
BEGIN DESCRIPTION:
FULCHER CREEK 31.0
END DESCRIPTION:
XS GIS Cut Line= 3
      2485825.01     13649975.01        2485225.       13649375.
      2484924.99     13648174.98
#Sta/Elev= 30
  4151.5  254.93  4193.8  251.81  4222.2  250.34  4399.4  245.57  4559.8  241.77
    4823  237.04  4943.5  234.71  4963.5   231.9    4964   231.4    4980   231.9
  4985.9  234.22  4996.5  235.13  5096.9  235.45    5165  236.64  5270.6  235.79
  5319.6  238.17  5435.5  238.56  5559.2  242.14  5724.2  248.49  5793.7  251.66
  5845.5  255.46  5912.1  259.67  5958.7  261.61  6007.6  265.17  6020.5  266.92
  6048.9  268.02    6054  269.32  6172.6  276.38  6206.1  279.87    6237   280.9
#Mann= 10 ,-1 , 0
  4151.5     .07       0  4193.8    .035       0  4399.4     .07       0
  4559.8     .05       0    4823      .1       0  4963.5     .05       0
    4980      .1       0  5096.9     .07       0  5845.5    .035       0
  5912.1     .07       0
Bank Sta=4963.5,4980
XS Rating Curve= 0 ,0
Exp/Cntr=0.3,0.1