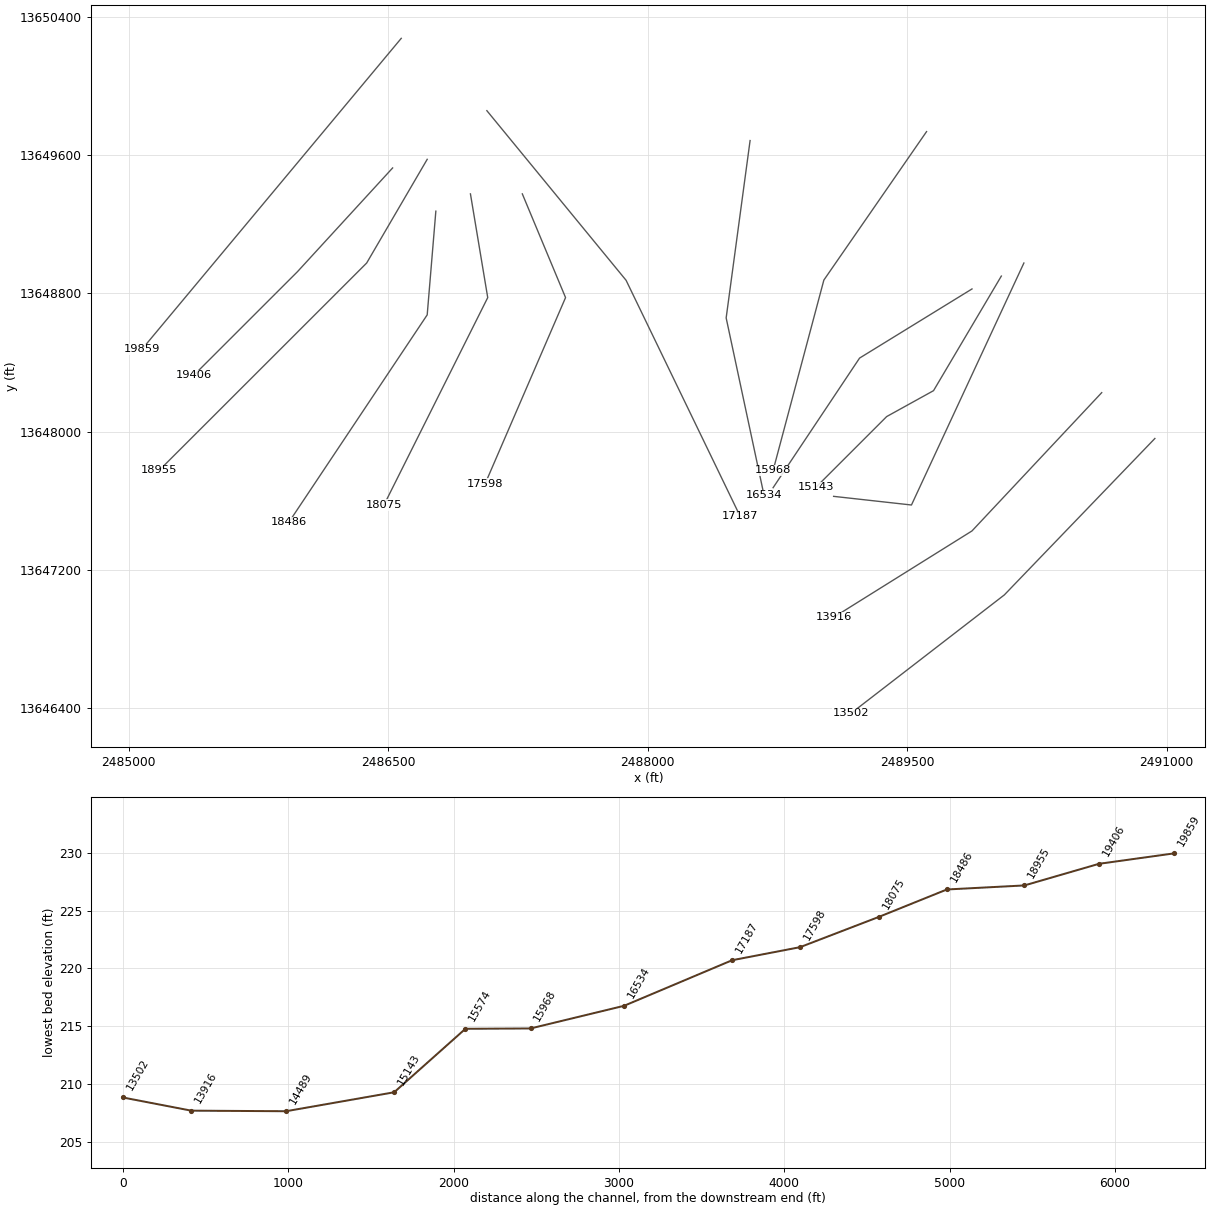
HEC-RAS study FULCHER CREEK.prj: FULCHER CREEK Base Level Engineering

--- FULCHER CREEK.g01 (geometry) --- (continued)

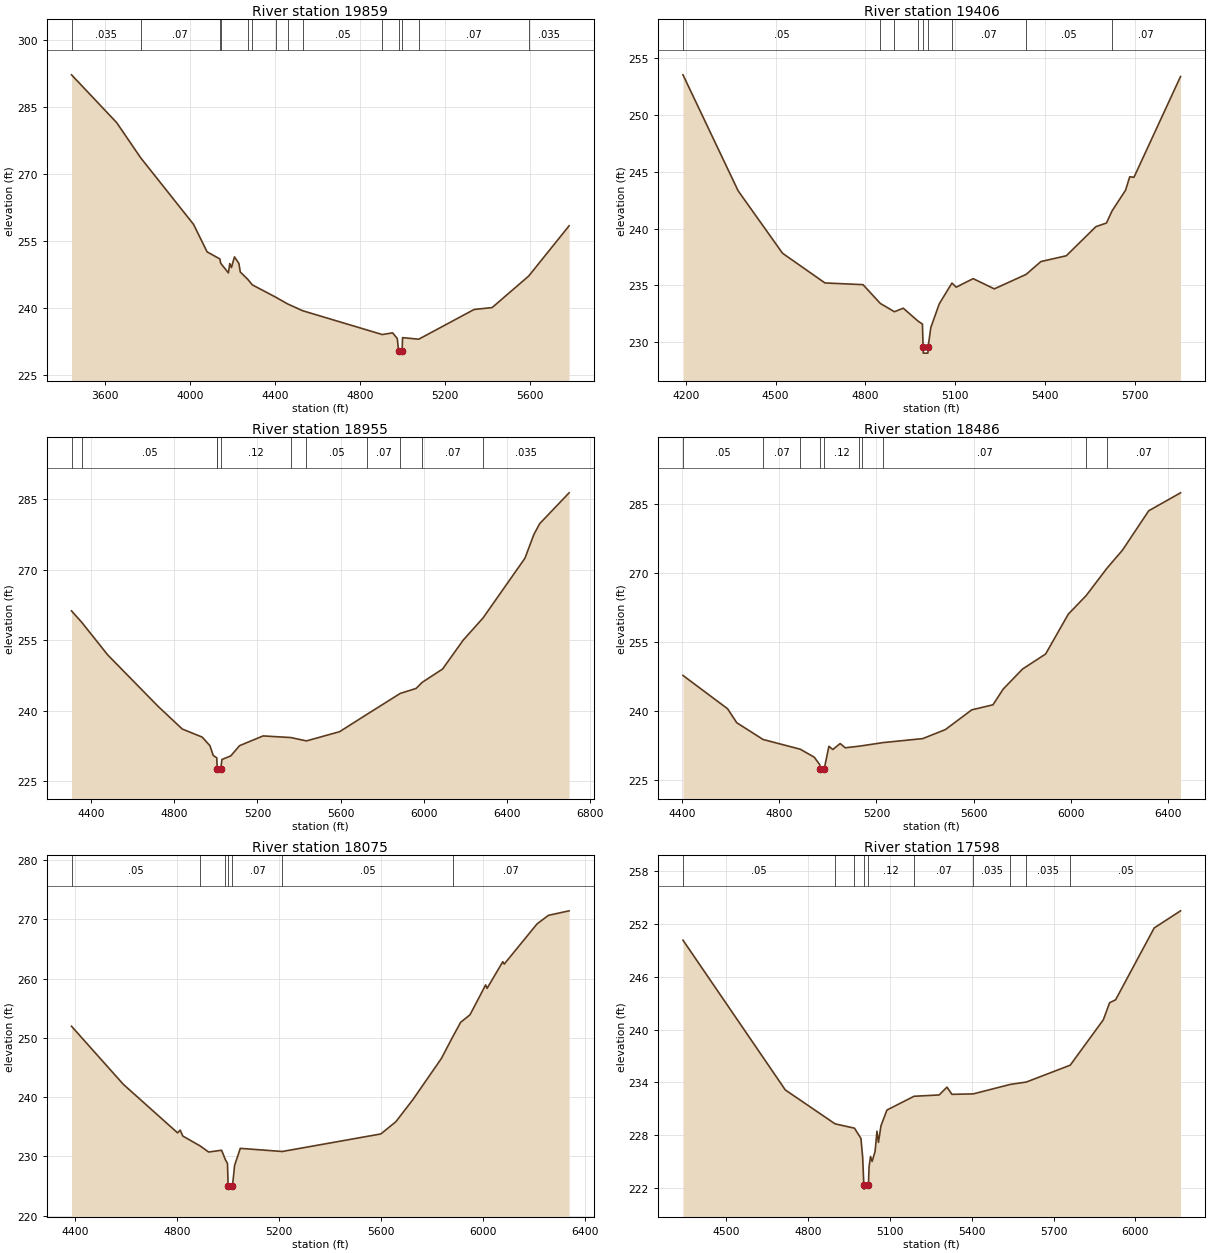
Type RM Length L Ch R = 1 ,19859   ,453,453,453
BEGIN DESCRIPTION:
FULCHER CREEK 30.0
END DESCRIPTION:
XS GIS Cut Line= 3
      2486574.97     13650274.97        2485575.       13649075.
      2485075.02     13648475.02
#Sta/Elev= 30
  3442.1  292.28  3654.9  281.56  3767.5  273.71  4016.8  258.78  4080.5  252.63
  4140.6  251.04  4144.5  250.08  4180.8  247.92  4187.3  250.01  4195.1  249.12
  4209.4  251.51  4230.2  250.03  4236.7  248.12  4271.9  246.48  4293.2  245.25
  4403.2  242.49  4459.8  240.97  4530.2  239.45  4905.3  234.11    4954  234.49
  4976.1  233.21  4982.1  230.45  4982.6  229.95  4998.7  230.45  5000.9  233.42
    5077  233.07    5338  239.73  5422.6  240.15  5594.8  247.21  5785.1  258.47
#Mann= 14 ,-1 , 0
  3442.1    .035       0  3767.5     .07       0  4140.6     .12       0
  4144.5     .07       0  4271.9     .05       0  4293.2     .07       0
  4403.2     .05       0  4459.8     .07       0  4530.2     .05       0
  4905.3      .1       0  4982.1     .05       0  4998.7      .1       0
    5077     .07       0  5594.8    .035       0
Bank Sta=4982.1,4998.7
XS Rating Curve= 0 ,0
Exp/Cntr=0.3,0.1

Type RM Length L Ch R = 1 ,19406   ,451,451,451
BEGIN DESCRIPTION:
FULCHER CREEK 29.0
END DESCRIPTION:
XS GIS Cut Line= 3
      2486525.03     13649525.03        2485975.       13648925.
      2485375.01     13648325.01
#Sta/Elev= 30
  4190.7  253.52  4374.8  243.33  4523.4  237.83  4665.2  235.22  4792.3  235.07
    4850  233.42  4897.2  232.69  4926.7     233  4975.4  231.88  4990.8   231.6
    4993  229.55  4993.5  229.05  5009.1  229.05  5009.6  229.55  5018.8   231.3
  5047.1  233.39  5089.4  235.21  5103.7  234.85  5160.2   235.6    5231   234.7
  5337.1  235.97  5386.5   237.1  5471.4  237.61  5570.4  240.17  5605.7  240.49
  5624.3  241.55  5669.4  243.37  5683.5  244.56  5697.6  244.51  5853.2  253.37
#Mann= 9 ,-1 , 0
  4190.7     .05       0    4850     .12       0  4897.2      .1       0
  4975.4     .12       0    4993     .05       0  5009.6     .12       0
  5089.4     .07       0  5337.1     .05       0  5624.3     .07       0
Bank Sta=4993,5009.6
XS Rating Curve= 0 ,0
Exp/Cntr=0.3,0.1

Type RM Length L Ch R = 1 ,18955   ,469,469,469
BEGIN DESCRIPTION:
FULCHER CREEK 28.0
END DESCRIPTION:
XS GIS Cut Line= 3
        2486725.     13649574.99        2486375.       13648975.
      2485174.98     13647774.98
#Sta/Elev= 30
  4306.4  261.26  4356.5  258.78  4480.5  251.89  4723.2  240.93  4838.9  236.13
  4934.4  234.42  4971.7  232.59  4987.4  230.52  5004.5  230.01  5006.8  227.68
  5007.3  227.18  5023.5  227.68  5029.3  229.65  5071.7  230.42  5114.2   232.6
  5227.3  234.67  5360.7  234.32  5435.7  233.61    5595  235.57  5728.5  239.32
  5886.9  243.72  5962.7  244.77  5991.4  246.05    6090   248.9    6189  255.04
  6284.5  259.77  6485.9  272.47  6528.4  277.48  6556.7  279.82  6698.1  286.38
#Mann= 11 ,-1 , 0
  4306.4     .07       0  4356.5     .05       0  5004.5     .12       0
  5006.8     .05       0  5023.5     .12       0  5360.7     .07       0
  5435.7     .05       0  5728.5     .07       0  5886.9     .05       0
  5991.4     .07       0  6284.5    .035       0
Bank Sta=5006.8,5023.5
XS Rating Curve= 0 ,0
Exp/Cntr=0.3,0.1

Type RM Length L Ch R = 1 ,18486   ,411,411,411
BEGIN DESCRIPTION:
FULCHER CREEK 27.0
END DESCRIPTION:
XS GIS Cut Line= 3
        2486775.     13649275.05        2486725.       13648675.
      2485925.03     13647475.04
#Sta/Elev= 30
  4405.3  247.63  4588.5  240.39  4626.1  237.36  4734.4  233.71  4887.3  231.59
  4944.7  229.86  4967.3  228.23  4968.9  227.33  4969.4  226.83  4985.7  227.33
  5004.9  232.23  5020.9  231.53    5051  232.83    5072   231.9  5126.7  232.24
  5141.7  232.35  5228.6  233.04  5390.5   233.9  5483.7  235.87  5591.8  240.15
    5679  241.25    5721  244.67  5800.6  249.03  5895.3  252.29  5988.4  260.95
  6061.8  264.99  6148.2     271  6210.8  274.85  6318.9  283.43  6449.6  287.33
#Mann= 10 ,-1 , 0
  4405.3     .05       0  4734.4     .07       0  4887.3     .12       0
  4968.9     .05       0  4985.7     .12       0  5126.7     .05       0
  5141.7     .12       0  5228.6     .07       0  6061.8    .035       0
  6148.2     .07       0
Bank Sta=4968.9,4985.7
XS Rating Curve= 0 ,0
Exp/Cntr=0.3,0.1

Type RM Length L Ch R = 1 ,18075   ,477,477,477
BEGIN DESCRIPTION:
FULCHER CREEK 26.0
END DESCRIPTION:
XS GIS Cut Line= 3
        2486975.     13649375.02        2487075.       13648775.
      2486475.02     13647575.04
#Sta/Elev= 30
  4387.5  251.94  4590.3  242.15  4803.2  233.95  4813.3  234.42  4823.5  233.42
  4891.1  231.76  4924.8  230.72  4975.5  231.02  4990.5  229.42  4998.6  228.79
  5001.3  224.96  5001.8  224.46  5018.2  224.96  5026.5  228.47  5048.9  231.34
  5213.3  230.81  5599.5  233.77  5658.2  235.82  5725.3  239.57  5837.1  246.52
  5880.7  250.11  5912.6  252.62  5948.9  253.87  6010.4  258.92    6016  258.34
  6077.5  262.83  6083.1  262.43  6211.7  269.21  6256.4  270.66  6337.4  271.42
#Mann= 7 ,-1 , 0
  4387.5     .05       0  4891.1     .12       0  4990.5     .07       0
  5001.3     .05       0  5018.2     .07       0  5213.3     .05       0
  5880.7     .07       0
Bank Sta=5001.3,5018.2
XS Rating Curve= 0 ,0
Exp/Cntr=0.3,0.1

Type RM Length L Ch R = 1 ,17598   ,411,411,411
BEGIN DESCRIPTION:
FULCHER CREEK 25.0
END DESCRIPTION:
XS GIS Cut Line= 3
        2487275.     13649374.99        2487525.       13648775.
      2487059.25     13647696.35
#Sta/Elev= 30
  4340.8  250.18  4716.2  233.13  4898.7  229.27  4969.8  228.78  4993.5  227.61
  4999.8  225.48  5004.1  222.34  5004.6  221.84    5021  222.34  5023.3  224.37
  5028.8  225.56  5034.4  224.99  5045.3  226.12  5052.3  228.43  5057.7  227.16
    5067  229.05  5088.8  230.84  5188.2  232.41  5280.2  232.56  5309.1  233.45
  5327.2  232.63  5405.4  232.68  5541.2  233.76  5600.1  234.03  5761.1  235.95
  5882.4  241.11  5905.7  243.06  5927.5  243.39  6069.1  251.57  6165.7  253.52
#Mann= 10 ,-1 , 0
  4340.8     .05       0  4898.7     .07       0  4969.8     .12       0
  5004.1     .05       0    5021     .12       0  5188.2     .07       0
  5405.4    .035       0  5541.2     .05       0  5600.1    .035       0
  5761.1     .05       0
Bank Sta=5004.1,5021
XS Rating Curve= 0 ,0
Exp/Cntr=0.3,0.1

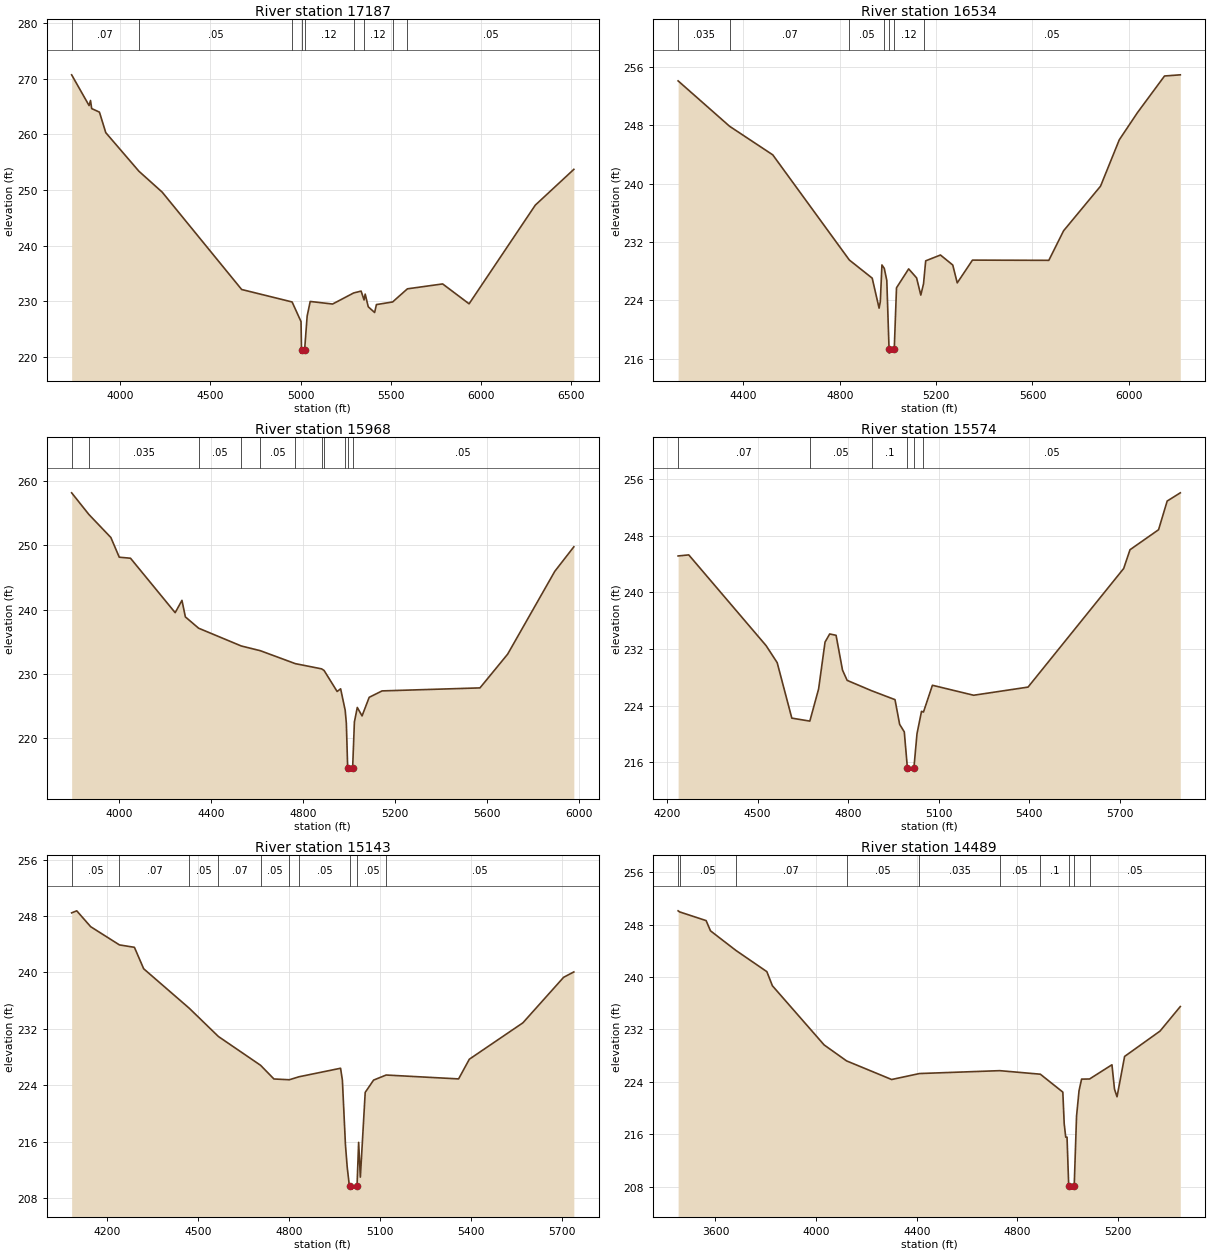
Type RM Length L Ch R = 1 ,17187   ,653,653,653
BEGIN DESCRIPTION:
FULCHER CREEK 24.0
END DESCRIPTION:
XS GIS Cut Line= 3
      2487070.04     13649856.41        2487875.       13648875.
      2488534.27     13647510.19
#Sta/Elev= 30
  3730.7   270.7  3827.4  265.18  3835.3  266.09  3841.7  264.64  3884.8     264
    3920  260.31  4103.9  253.38  4232.8  249.63  4673.5  232.14  4953.3   229.9
  5002.8  226.37  5005.6  221.21  5006.1  220.71  5022.5  221.21  5036.7  227.36
  5053.7  229.99  5177.8  229.53  5294.8  231.52    5336  231.85  5352.4  230.26
  5358.6  231.31  5375.7  229.03  5410.9  228.01  5420.9  229.43  5510.6   229.9
  5592.7  232.26  5788.1  233.14  5934.8  229.57  6301.9  247.29  6515.7  253.72
#Mann= 9 ,-1 , 0
  3730.7     .07       0  4103.9     .05       0  4953.3     .12       0
  5005.6     .05       0  5022.5     .12       0  5294.8    .035       0
  5352.4     .12       0  5510.6    .035       0  5592.7     .05       0
Bank Sta=5005.6,5022.5
XS Rating Curve= 0 ,0
Exp/Cntr=0.3,0.1

Type RM Length L Ch R = 1 ,16534   ,566,566,566
BEGIN DESCRIPTION:
X19225
END DESCRIPTION:
XS GIS Cut Line= 3
      2488591.94     13649683.49      2488453.58     13648657.35
      2488672.65      13647631.2
#Sta/Elev= 30
  4128.9  254.06  4342.7  247.84  4521.8  243.93  4839.8  229.52  4934.6  227.04
  4963.2  222.93  4968.3  223.82    4975  228.85  4984.7  228.38  4995.2  226.73
  5004.6  217.27  5005.1  216.77  5026.1  217.27  5035.5  225.72    5086  228.31
  5118.8  227.08  5136.4  224.72  5147.7  226.27  5156.6  229.41  5217.9  230.21
    5269  228.84  5287.6  226.39  5350.8  229.51  5667.8  229.48  5729.1  233.53
  5882.5  239.64  5960.3  245.99  6035.9  249.72  6148.1  254.73  6213.6  254.89
#Mann= 7 ,-1 , 0
  4128.9    .035       0  4342.7     .07       0  4839.8     .05       0
  4984.7     .12       0  5004.6     .05       0  5026.1     .12       0
  5147.7     .05       0
Bank Sta=5004.6,5026.1
XS Rating Curve= 0 ,0
Exp/Cntr=0.3,0.1

Type RM Length L Ch R = 1 ,15968   ,394,394,394
BEGIN DESCRIPTION:
FULCHER CREEK 23.0
END DESCRIPTION:
XS GIS Cut Line= 3
      2489612.28     13649735.33      2489018.52     13648876.41
      2488725.01     13647775.02
#Sta/Elev= 30
  3793.4  258.21  3868.5  254.83    3964  251.24  4000.5  248.17  4049.4  248.01
  4243.6  239.52  4273.1  241.44    4288  238.86  4345.5   237.1  4530.9  234.33
  4613.9  233.59  4766.3  231.57  4880.3  230.76  4891.2  230.51    4948  227.23
  4963.2  227.65  4983.1  224.28  4988.1  222.25  4993.8  215.31  4994.3  214.81
  5015.4  215.31  5023.1  222.48  5035.7  224.74  5056.4  223.42  5087.4  226.32
  5143.4  227.32  5569.2  227.79  5689.5  233.05  5894.6  245.97  5977.4  249.79
#Mann= 11 ,-1 , 0
  3793.4     .05       0  3868.5    .035       0  4345.5     .05       0
  4530.9     .12       0  4613.9     .05       0  4766.3     .12       0
  4880.3     .05       0  4891.2     .12       0  4983.1     .05       0
  4993.8     .05       0  5015.4     .05       0
Bank Sta=4993.8,5015.4
XS Rating Curve= 0 ,0
Exp/Cntr=0.3,0.1

Type RM Length L Ch R = 1 ,15574   ,431,431,431
BEGIN DESCRIPTION:
FULCHER CREEK 22.0
END DESCRIPTION:
XS GIS Cut Line= 3
      2489875.03     13648825.02        2489225.       13648425.
      2488725.02     13647675.04
#Sta/Elev= 30
  4236.7  245.15    4272   245.3  4528.4  232.49  4565.1  230.09  4613.6  222.26
  4673.3  221.84  4702.4  226.38  4723.7  232.99  4739.1  234.14  4760.3  233.95
  4781.6  229.04    4797  227.59  4877.9  226.13  4955.6  224.87    4971  221.38
  4986.4  220.32  4996.6  215.28  4997.1  214.78  5018.4  215.28  5028.5  220.05
  5043.5  223.22    5050  223.12  5079.6   226.9  5216.3  225.49  5396.6  226.64
  5713.6  243.38  5734.6  246.03  5829.2  248.85  5857.8   252.9  5901.3  254.06
#Mann= 6 ,-1 , 0
  4236.7     .07       0  4673.3     .05       0  4877.9      .1       0
  4996.6     .05       0  5018.4      .1       0    5050     .05       0
Bank Sta=4996.6,5018.4
XS Rating Curve= 0 ,0
Exp/Cntr=0.3,0.1

Type RM Length L Ch R = 1 ,15143   ,654,654,654
BEGIN DESCRIPTION:
X19226
END DESCRIPTION:
XS GIS Cut Line= 4
      2490044.66     13648899.49      2489652.64     13648236.52
       2489381.7     13648086.64      2488973.73     13647678.66
#Sta/Elev= 30
  4082.8  248.44  4099.6  248.73  4145.6  246.48  4240.5   243.9  4289.9  243.56
  4320.4  240.52  4470.9  234.92    4567  230.92  4706.1  226.84  4750.2   224.9
    4801  224.79  4832.6  225.21    4970  226.42    4976  224.74  4986.1  215.58
  4991.8  212.46  4998.9   209.8  5002.6  209.79  5003.1  209.29  5024.4  209.79
  5029.6  215.92  5035.3  210.99  5051.3     223  5078.9  224.74  5120.4  225.46
  5359.4  224.91  5394.8   227.7  5571.6  232.86  5705.9  239.31  5739.6  240.07
#Mann= 10 ,-1 , 0
  4082.8     .05       0  4240.5     .07       0  4470.9     .05       0
    4567     .07       0  4706.1     .05       0    4801    .035       0
  4832.6     .05       0  5002.6     .05       0  5024.4     .05       0
  5120.4     .05       0
Bank Sta=5002.6,5024.4
XS Rating Curve= 0 ,0
Exp/Cntr=0.3,0.1

Type RM Length L Ch R = 1 ,14489   ,573,573,573
BEGIN DESCRIPTION:
FULCHER CREEK 21.0
END DESCRIPTION:
XS GIS Cut Line= 3
        2490175.     13648974.99        2489525.       13647575.
      2489074.99       13647625.
#Sta/Elev= 30
  3451.6   250.1    3458  249.93  3562.9  248.61  3580.3  247.05    3681  244.07
  3804.4  240.82  3826.4  238.67  4031.9  229.65  4121.2  227.21  4300.5  224.37
    4411  225.28  4730.2  225.72  4891.5  225.18  4980.9  222.45  4986.4  217.61
  4992.4  215.58  4997.6  215.58  5004.3  208.15  5004.8  207.65  5026.2  208.15
  5035.4  218.76  5045.4  222.68  5055.5  224.43  5087.2  224.45  5176.2  226.62
  5186.3   222.9  5196.4  221.74  5226.5  227.89  5367.4  231.76  5447.9   235.5
#Mann= 10 ,-1 , 0
  3451.6     .07       0    3458     .05       0    3681     .07       0
  4121.2     .05       0    4411    .035       0  4730.2     .05       0
  4891.5      .1       0  5004.3     .05       0  5026.2      .1       0
  5087.2     .05       0
Bank Sta=5004.3,5026.2
XS Rating Curve= 0 ,0
Exp/Cntr=0.3,0.1

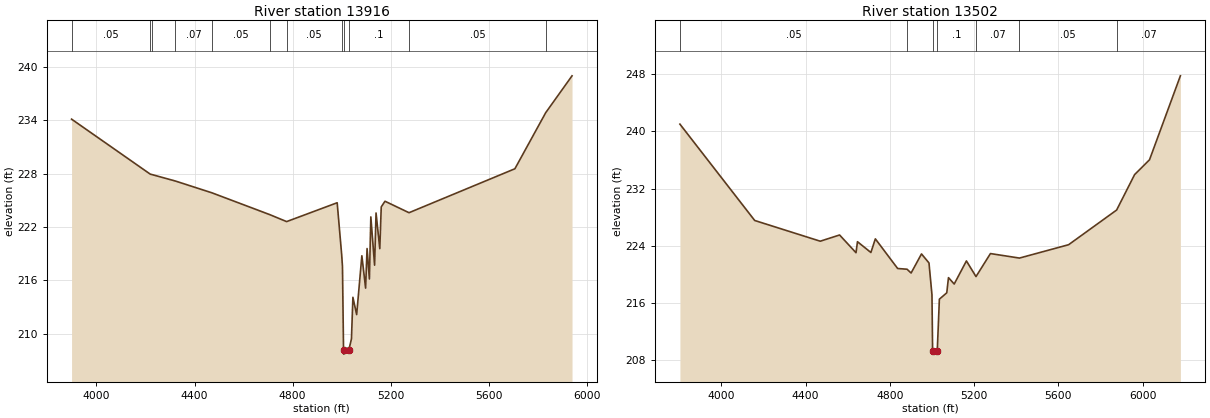
Type RM Length L Ch R = 1 ,13916   ,414,414,414
BEGIN DESCRIPTION:
FULCHER CREEK 20.0
END DESCRIPTION:
XS GIS Cut Line= 3
      2490625.03     13648225.04        2489875.       13647425.
      2489075.03     13646925.02
#Sta/Elev= 30
  3898.7  234.12  4219.8  227.93  4226.2  227.89  4322.1  227.16  4470.4  225.84
    4707  223.38  4775.3   222.6  4981.4  224.72  4999.7  218.89    5003  217.53
  5007.3   208.2  5007.8   207.7  5029.3   208.2  5039.6  209.42  5045.5  214.09
  5060.8  212.14    5082  218.76  5097.3  215.12  5103.2  219.57  5112.7  216.15
  5118.6  223.13  5133.9   217.7  5139.8  223.57  5155.1  219.56    5161  224.25
  5176.3  224.89  5274.2   223.6  5705.8  228.54  5831.5  234.85  5938.7  238.99
#Mann= 12 ,-1 , 0
  3898.7     .05       0  4219.8     .07       0  4226.2     .05       0
  4322.1     .07       0  4470.4     .05       0    4707    .035       0
  4775.3     .05       0  4999.7      .1       0  5007.3     .05       0
  5029.3      .1       0  5274.2     .05       0  5831.5     .07       0
Bank Sta=5007.3,5029.3
XS Rating Curve= 0 ,0
Exp/Cntr=0.3,0.1

Type RM Length L Ch R = 1 ,13502   ,664,664,664
BEGIN DESCRIPTION:
X19227
END DESCRIPTION:
XS GIS Cut Line= 3
      2490932.41     13647959.81      2490061.94     13647054.75
      2489175.01      13646369.4
#Sta/Elev= 30
  3803.3  241.02  4158.4  227.54  4469.7  224.64  4561.5  225.51  4639.5  223.03
  4646.4  224.57  4710.2  223.06  4731.3  224.97  4837.3  220.82  4881.8  220.72
  4901.1  220.19  4950.5  222.86    4986   221.6  5000.2  217.14  5003.2  209.34
  5003.7  208.84  5025.4  209.34  5035.4  216.53  5070.5  217.42  5078.6  219.54
  5105.8  218.65  5163.8  221.88  5209.3  219.69  5277.9  222.91  5415.6  222.28
  5649.1  224.15  5877.1     229  5962.5  233.96  6033.2  236.03  6179.9  247.78
#Mann= 7 ,-1 , 0
  3803.3     .05       0  4881.8      .1       0  5003.2     .05       0
  5025.4      .1       0  5209.3     .07       0  5415.6     .05       0
  5877.1     .07       0
Bank Sta=5003.2,5025.4
XS Rating Curve= 0 ,0
Exp/Cntr=0.3,0.1