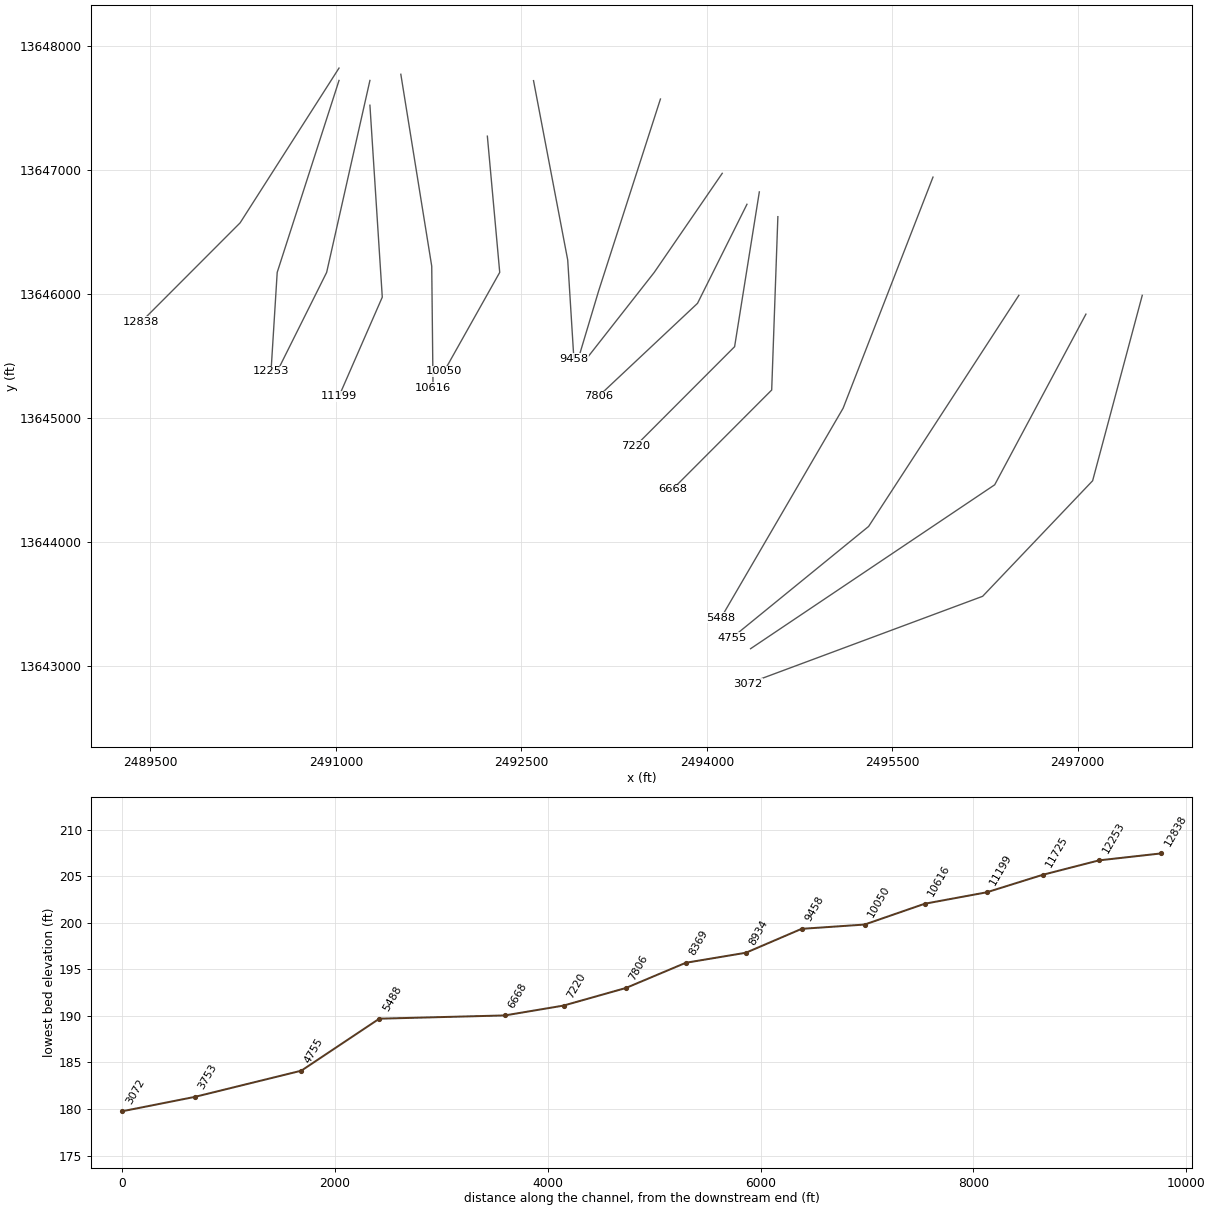
HEC-RAS study FULCHER CREEK.prj: FULCHER CREEK Base Level Engineering

--- FULCHER CREEK.g01 (geometry) --- (continued)

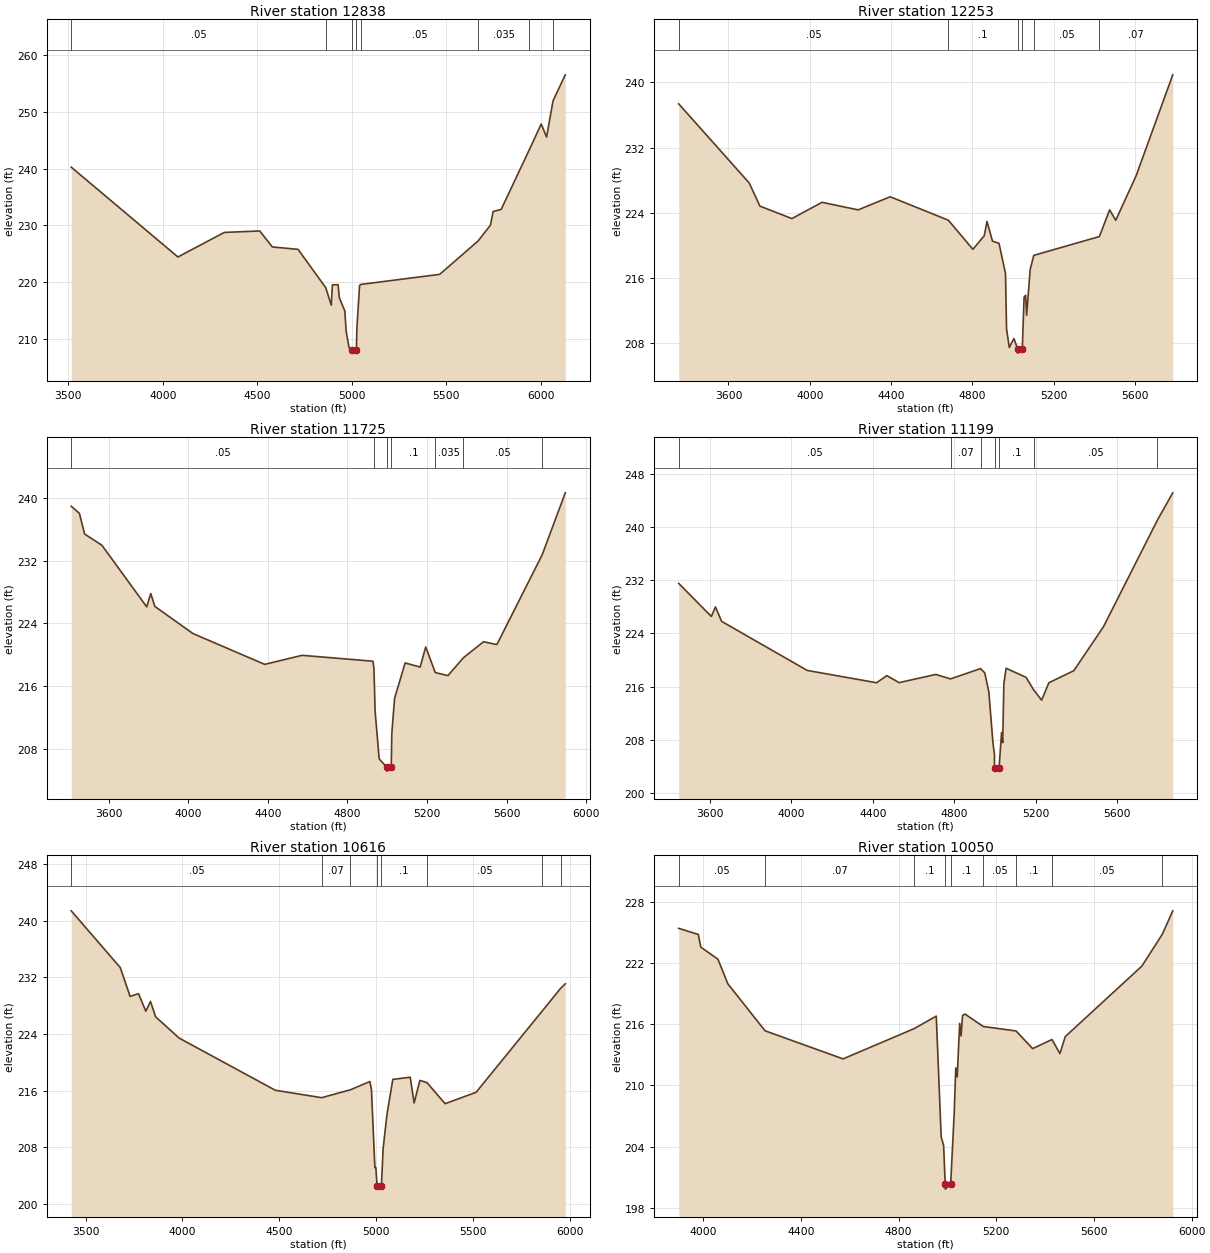
Type RM Length L Ch R = 1 ,12838   ,585,585,585
BEGIN DESCRIPTION:
FULCHER CREEK 19.0
END DESCRIPTION:
XS GIS Cut Line= 3
      2491024.98     13647824.97        2490225.       13646575.
      2489425.01     13645775.01
#Sta/Elev= 30
  3515.5  240.27  4080.3  224.43  4325.6  228.76  4513.3  229.02  4580.1   226.2
  4716.3  225.78    4863  219.01  4892.1  215.94  4898.1  219.53  4928.3  219.54
  4934.4  217.27  4963.9  214.91  4970.8  211.36    4986  208.47  5002.5  207.98
    5003  207.48  5024.8  207.98  5027.8  211.93    5042  219.43  5049.7   219.6
  5466.2  221.37  5669.7  227.27  5734.9  230.05  5749.1  232.45  5791.5  232.82
  5940.5  243.34  6003.6  247.88  6031.9  245.58  6066.2  251.98  6130.9  256.55
#Mann= 8 ,-1 , 0
  3515.5     .05       0    4863      .1       0  5002.5     .05       0
  5024.8      .1       0  5049.7     .05       0  5669.7    .035       0
  5940.5     .07       0  6066.2    .035       0
Bank Sta=5002.5,5024.8
XS Rating Curve= 0 ,0
Exp/Cntr=0.3,0.1

Type RM Length L Ch R = 1 ,12253   ,528,528,528
BEGIN DESCRIPTION:
FULCHER CREEK 18.0
END DESCRIPTION:
XS GIS Cut Line= 3
        2491025.     13647725.01        2490525.       13646175.
        2490475.     13645375.02
#Sta/Elev= 30
  3355.5  237.37  3702.5  227.64  3754.8   224.8  3912.4  223.27  4060.3  225.27
  4238.1  224.34  4395.7  225.95  4681.7  223.07  4802.6  219.49  4858.1  221.15
    4872  222.92  4898.8   220.5  4930.8  220.23  4962.9  216.53  4968.1  209.71
  4981.5  207.43  5004.2  208.52  5023.1  207.23  5023.6  206.73  5045.5  207.23
  5054.3   213.6  5061.8  213.84  5066.8  211.39  5084.4  217.02  5102.1  218.75
  5424.7  221.06  5475.1  224.34  5505.2  223.06  5605.4  228.53  5785.7  240.94
#Mann= 6 ,-1 , 0
  3355.5     .05       0  4681.7      .1       0  5023.1     .05       0
  5045.5      .1       0  5102.1     .05       0  5424.7     .07       0
Bank Sta=5023.1,5045.5
XS Rating Curve= 0 ,0
Exp/Cntr=0.3,0.1

Type RM Length L Ch R = 1 ,11725   ,526,526,526
BEGIN DESCRIPTION:
FULCHER CREEK 17.0
END DESCRIPTION:
XS GIS Cut Line= 3
        2491275.     13647725.02        2490925.       13646175.
      2490524.99     13645374.98
#Sta/Elev= 30
  3411.3  238.92  3452.3  238.02  3478.7  235.38  3565.1  233.96  3790.6  226.11
  3811.1   227.8  3831.6  226.16  4022.8  222.71  4383.8  218.78    4572  219.93
  4927.9  219.18    4933  218.28  4935.6  215.84  4938.8  212.84  4959.3  206.74
  4997.5  205.68    4998  205.18  5019.9  205.68  5022.7  209.96  5036.7  214.45
  5089.8  218.96  5165.3  218.44  5193.2  220.99  5241.5  217.73    5305  217.35
  5382.6  219.62  5483.9  221.66    5551   221.3  5778.6  232.73  5894.8  240.63
#Mann= 7 ,-1 , 0
  3411.3     .05       0  4935.6      .1       0  4997.5     .05       0
  5019.9      .1       0  5241.5    .035       0  5382.6     .05       0
  5778.6     .07       0
Bank Sta=4997.5,5019.9
XS Rating Curve= 0 ,0
Exp/Cntr=0.3,0.1

Type RM Length L Ch R = 1 ,11199   ,583,583,583
BEGIN DESCRIPTION:
FULCHER CREEK 16.0
END DESCRIPTION:
XS GIS Cut Line= 3
        2491275.     13647524.98        2491375.       13645975.
      2491025.01     13645175.02
#Sta/Elev= 30
  3446.7  231.51    3607  226.54  3627.1  227.98  3657.1  225.81    4078  218.43
  4418.7  216.58  4468.8  217.65  4528.9   216.6  4709.3  217.83  4781.6  217.16
  4929.2  218.71  4949.8  218.05  4969.8  215.21  4989.9  207.56  4997.4  205.79
  4997.7   203.8  4998.2   203.3  5020.1   203.8  5032.3  209.12  5037.7  207.58
  5043.6  216.46  5054.5  218.76  5152.7  217.39  5189.4  215.53  5229.1  213.97
  5264.6  216.58    5387  218.39  5532.8     225  5797.7  241.02  5873.1  245.12
#Mann= 7 ,-1 , 0
  3446.7     .05       0  4781.6     .07       0  4929.2      .1       0
  4997.7     .05       0  5020.1      .1       0  5189.4     .05       0
  5797.7     .07       0
Bank Sta=4997.7,5020.1
XS Rating Curve= 0 ,0
Exp/Cntr=0.3,0.1

Type RM Length L Ch R = 1 ,10616   ,566,566,566
BEGIN DESCRIPTION:
FULCHER CREEK 15.0
END DESCRIPTION:
XS GIS Cut Line= 3
      2491525.01     13647774.97        2491775.       13646225.
       2491785.6     13645244.66
#Sta/Elev= 30
    3426  241.39  3679.2  233.37  3729.8   229.3  3773.4  229.68  3810.9  227.21
  3835.2  228.59  3861.5  226.42  3983.1  223.41  4479.4  216.04  4718.5  214.99
  4867.4  216.11  4967.6  217.27  4975.7  216.16  4993.5  205.11  4998.5  205.11
  5004.8  202.57  5005.3  202.07  5027.2  202.57    5036  207.79    5056  212.64
    5086  217.57    5176  217.88    5196  214.24    5226  217.43  5262.4  217.12
    5356  214.14    5516  215.75  5857.9  227.25  5951.8  230.42  5976.4  231.08
#Mann= 8 ,-1 , 0
    3426     .05       0  4718.5     .07       0  4867.4      .1       0
  5004.8     .05       0  5027.2      .1       0  5262.4     .05       0
  5857.9     .07       0  5951.8    .035       0
Bank Sta=5004.8,5027.2
XS Rating Curve= 0 ,0
Exp/Cntr=0.3,0.1

Type RM Length L Ch R = 1 ,10050   ,592,592,592
BEGIN DESCRIPTION:
FULCHER CREEK 14.0
END DESCRIPTION:
XS GIS Cut Line= 3
        2492225.     13647274.97        2492325.       13646175.
      2491874.99     13645374.99
#Sta/Elev= 30
  3900.3  225.42  3980.6  224.82  3990.6  223.58  4060.9  222.39  4101.1  219.99
  4253.6  215.37    4573  212.61  4864.1  215.58  4954.6  216.81  4974.7  204.95
  4984.7  204.11  4991.1  200.33  4991.6  199.83  5013.5  200.33  5027.8  207.18
  5034.4  211.72  5040.2  210.84  5050.4   216.1  5056.1  214.86  5062.2  216.87
  5072.1  217.01  5146.8  215.79  5281.3  215.35    5349  213.62  5428.2  214.51
  5460.9  213.13  5482.6   214.8  5796.5  221.72  5879.8  224.84  5922.7  227.14
#Mann= 9 ,-1 , 0
  3900.3     .05       0  4253.6     .07       0  4864.1      .1       0
  4991.1     .05       0  5013.5      .1       0  5146.8     .05       0
  5281.3      .1       0  5428.2     .05       0  5879.8     .07       0
Bank Sta=4991.1,5013.5
XS Rating Curve= 0 ,0
Exp/Cntr=0.3,0.1

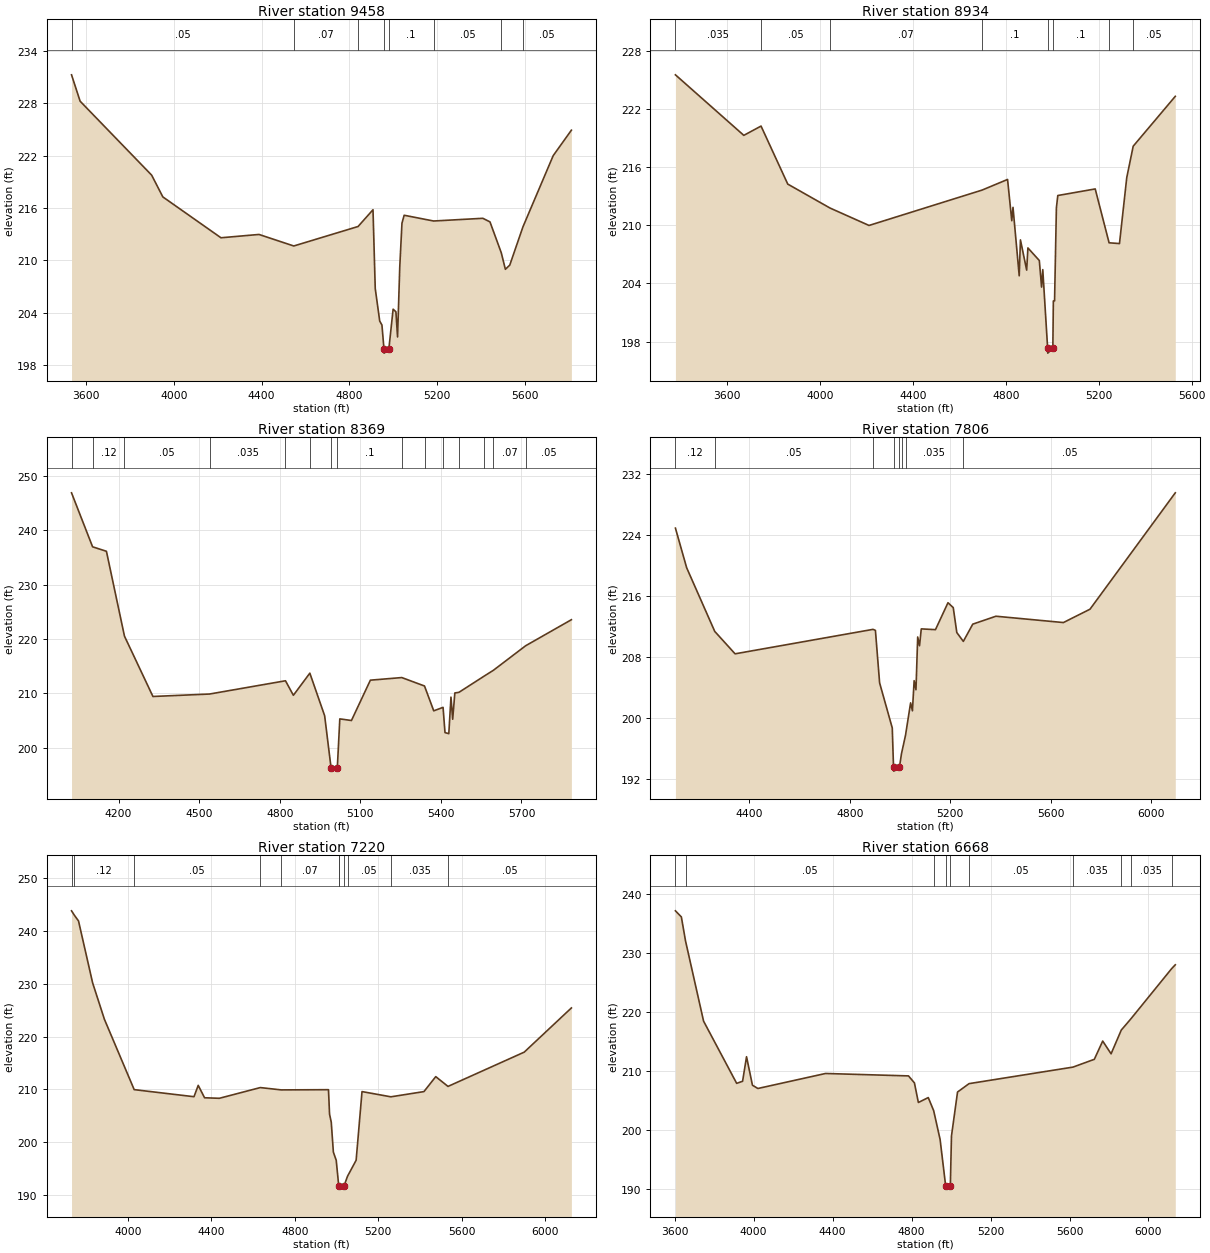
Type RM Length L Ch R = 1 ,9458    ,524,524,524
BEGIN DESCRIPTION:
FULCHER CREEK 13.0
END DESCRIPTION:
XS GIS Cut Line= 3
      2492598.42     13647723.45        2492875.       13646275.
        2492925.     13645474.98
#Sta/Elev= 30
  3534.8  231.24  3573.9  228.22  3899.7  219.75  3950.6  217.26  4215.3  212.58
  4388.4  212.96  4546.9  211.64  4839.6  213.87  4907.6  215.79  4917.8  206.77
  4938.2  203.04  4948.3  202.59  4957.5  199.87    4958  199.37  4979.9  199.87
  4999.2   204.4  5011.9  204.11  5019.4  201.22  5029.5  209.26  5039.5  214.25
  5049.5  215.16  5183.5   214.5  5407.7  214.81  5440.3   214.4  5491.8  210.86
  5510.4  208.97  5530.4  209.45  5590.4  213.83  5728.3  221.99    5811   224.9
#Mann= 8 ,-1 , 0
  3534.8     .05       0  4546.9     .07       0  4839.6      .1       0
  4957.5     .05       0  4979.9      .1       0  5183.5     .05       0
  5491.8     .12       0  5590.4     .05       0
Bank Sta=4957.5,4979.9
XS Rating Curve= 0 ,0
Exp/Cntr=0.3,0.1

Type RM Length L Ch R = 1 ,8934    ,565,565,565
BEGIN DESCRIPTION:
FULCHER CREEK 12.0
END DESCRIPTION:
XS GIS Cut Line= 3
      2493624.99     13647574.97        2493125.       13646025.
      2492975.01     13645525.03
#Sta/Elev= 30
    3379  225.53  3673.2  219.28  3747.3  220.24  3862.3  214.25    4044  211.78
  4211.9  209.98  4698.2  213.63    4808  214.73  4826.1  210.47  4831.4  211.85
  4858.1  204.78  4863.4  208.49  4890.2  205.37  4895.5  207.66  4944.6  206.36
  4954.3  203.62  4959.5  205.42  4980.4   197.3  4980.9   196.8  5002.8   197.3
    5005  202.19  5010.2  202.19  5018.1   211.8  5024.1  213.07  5185.1  213.75
  5244.8  208.19  5289.5  208.11  5320.8  214.92  5348.5  218.16  5529.6  223.31
#Mann= 8 ,-1 , 0
    3379    .035       0  3747.3     .05       0    4044     .07       0
  4698.2      .1       0  4980.4     .05       0  5002.8      .1       0
  5244.8     .12       0  5348.5     .05       0
Bank Sta=4980.4,5002.8
XS Rating Curve= 0 ,0
Exp/Cntr=0.3,0.1

Type RM Length L Ch R = 1 ,8369    ,563,563,563
BEGIN DESCRIPTION:
FULCHER CREEK 11.0
END DESCRIPTION:
XS GIS Cut Line= 3
        2494125.       13646975.        2493575.       13646175.
      2493024.97     13645474.96
#Sta/Elev= 30
  4024.8  246.91  4103.2  236.98  4154.7  236.16  4221.9  220.55  4327.9  209.45
  4538.7   209.9  4821.4  212.34  4850.8  209.67  4912.1  213.74  4967.2  205.91
  4991.4  196.22  4991.9  195.72  5014.3  196.22  5023.7  205.33    5067  205.03
  5137.5  212.45  5254.4  212.93    5339  211.38  5373.4  206.81  5408.1  207.45
  5415.3  202.81  5429.5  202.61  5437.6  209.33  5443.9  205.26    5452   210.1
  5467.1  210.21  5561.9  213.22  5595.3  214.26  5715.6  218.78  5885.9  223.57
#Mann= 15 ,-1 , 0
  4024.8     .07       0  4103.2     .12       0  4221.9     .05       0
  4538.7    .035       0  4821.4     .07       0  4912.1      .1       0
  4991.4     .05       0  5014.3      .1       0  5254.4     .05       0
    5339     .07       0  5408.1     .05       0  5467.1     .07       0
  5561.9     .12       0  5595.3     .07       0  5715.6     .05       0
Bank Sta=4991.4,5014.3
XS Rating Curve= 0 ,0
Exp/Cntr=0.3,0.1

Type RM Length L Ch R = 1 ,7806    ,586,586,586
BEGIN DESCRIPTION:
FULCHER CREEK 10.0
END DESCRIPTION:
XS GIS Cut Line= 3
      2494324.99     13646724.98        2493925.       13645925.
      2493124.99     13645174.99
#Sta/Elev= 30
  4105.6  224.87  4150.3  219.68  4262.2  211.33  4343.2  208.39  4892.9   211.6
  4902.2  211.46  4918.9  204.58  4969.3  198.67  4974.3  193.51  4974.8  193.01
  4997.8  193.51  5006.1  195.31  5022.1  197.72  5042.3  201.96  5049.6  200.92
  5056.4  204.87  5063.7  203.68  5070.6   210.6  5077.9  209.45  5084.8  211.66
  5141.4  211.56  5191.2  215.09  5212.2  214.45  5226.4  211.18  5252.4  210.02
  5289.9  212.28  5382.2  213.32  5650.9  212.49  5756.9  214.24  6096.6   229.5
#Mann= 8 ,-1 , 0
  4105.6     .12       0  4262.2     .05       0  4892.9     .12       0
  4974.3     .05       0  4997.8     .12       0  5006.1      .1       0
  5022.1    .035       0  5252.4     .05       0
Bank Sta=4974.3,4997.8
XS Rating Curve= 0 ,0
Exp/Cntr=0.3,0.1

Type RM Length L Ch R = 1 ,7220    ,552,552,552
BEGIN DESCRIPTION:
FULCHER CREEK 9.0
END DESCRIPTION:
XS GIS Cut Line= 3
      2494424.99     13646824.96        2494225.       13645575.
      2493425.02     13644775.02
#Sta/Elev= 30
  3729.6  243.82  3743.5  242.97  3763.1   241.9  3830.8  230.17  3887.2  223.29
  4030.1  209.96  4316.9  208.62  4337.2  210.77  4367.6  208.42  4438.5  208.32
  4634.9  210.35  4735.1  209.91  4961.9  209.95    4967  205.31  4975.2  203.79
  4985.3  198.13    4999  196.58  5011.2  191.68    5012  191.62  5012.5  191.12
  5035.5  191.62  5053.1  193.55  5094.5  196.59  5122.7  209.59  5261.1   208.6
  5419.7  209.59  5476.3  212.42  5535.1  210.57  5900.6  217.06  6126.8  225.43
#Mann= 11 ,-1 , 0
  3729.6     .07       0  3743.5     .12       0  4030.1     .05       0
  4634.9     .12       0  4735.1     .07       0  5011.2      .1       0
    5012     .05       0  5035.5      .1       0  5053.1     .05       0
  5261.1    .035       0  5535.1     .05       0
Bank Sta=5012,5035.5
XS Rating Curve= 0 ,0
Exp/Cntr=0.3,0.1

Type RM Length L Ch R = 1 ,6668    ,1180,1180,1180
BEGIN DESCRIPTION:
FULCHER CREEK 8.0
END DESCRIPTION:
XS GIS Cut Line= 3
        2494575.     13646624.96        2494525.       13645225.
      2493725.02     13644425.02
#Sta/Elev= 30
  3603.7  237.18  3633.7  236.15  3654.8  232.09  3746.3   218.5  3913.9  207.97
  3943.9  208.32  3963.9  212.48  3993.9  207.65  4021.4   207.1  4364.1  209.64
  4784.4  209.23  4814.4  208.05  4834.4  204.73  4884.5  205.56  4911.8  203.36
  4944.5  198.47  4972.8  190.56  4973.3  190.06  4996.3  190.56  5002.1  199.06
  5032.8   206.5  5091.1  207.92  5617.7  210.72  5725.8  212.04  5768.2  215.13
  5810.7  212.97  5862.3  216.99  5911.2   218.9  6117.4  227.39  6135.9  228.04
#Mann= 10 ,-1 , 0
  3603.7     .12       0  3654.8     .05       0  4911.8     .07       0
  4972.8     .05       0  4996.3     .07       0  5091.1     .05       0
  5617.7    .035       0  5862.3     .05       0  5911.2    .035       0
  6117.4     .05       0
Bank Sta=4972.8,4996.3
XS Rating Curve= 0 ,0
Exp/Cntr=0.3,0.1

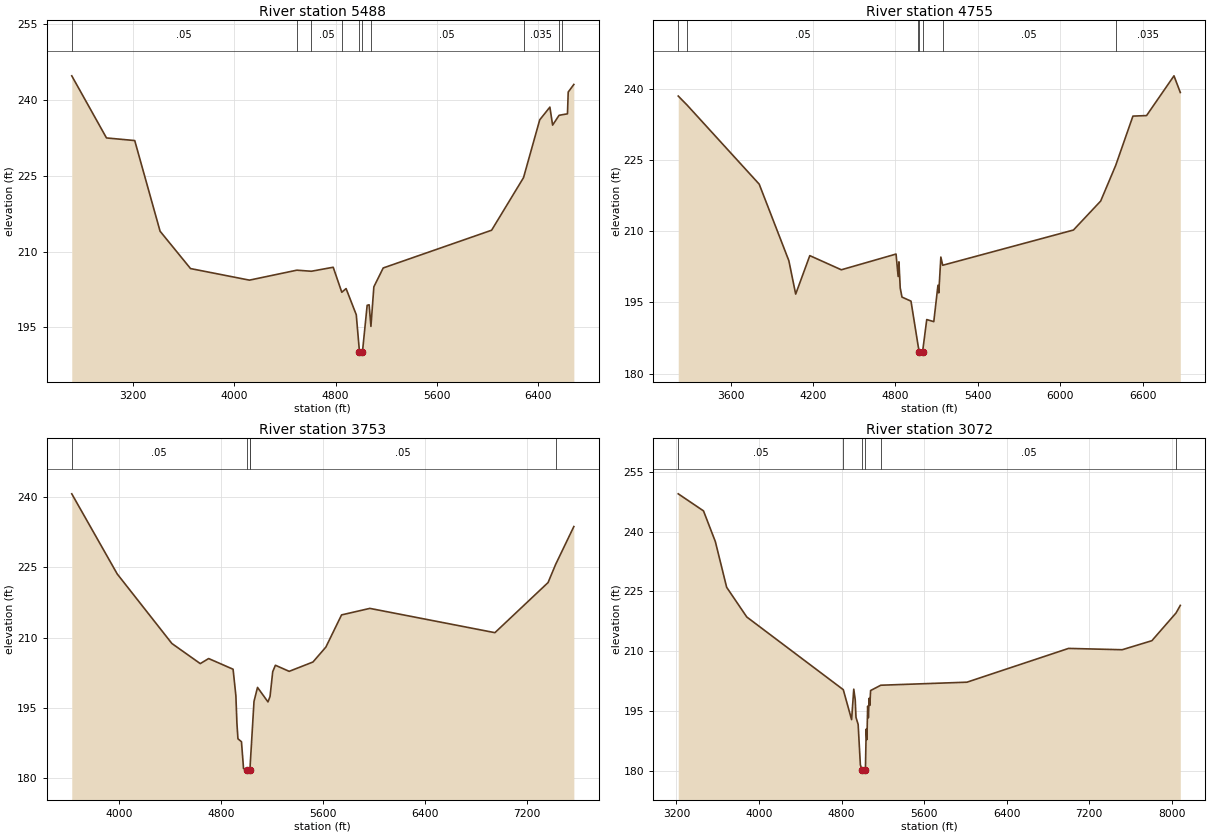
Type RM Length L Ch R = 1 ,5488    ,733,733,733
BEGIN DESCRIPTION:
FULCHER CREEK 7.0
END DESCRIPTION:
XS GIS Cut Line= 3
      2495829.81     13646944.44      2495102.83     13645078.16
      2494115.43     13643385.48
#Sta/Elev= 30
  2718.4  244.78  2992.4  232.49  3215.3  231.97  3415.4  214.03  3655.7  206.64
  4120.6  204.35  4494.6  206.32  4609.3  206.11  4781.7   206.9  4849.5  201.95
  4883.4  202.68  4963.7  197.51  4988.9  190.21  4989.4  189.71  5012.8  190.21
  5049.7  199.37  5065.4  199.47  5079.4   195.2  5102.6  203.03  5176.4  206.76
    6032  214.23  6283.7  224.63  6411.6  236.07  6491.8  238.59  6513.3  235.03
  6564.2  236.96  6588.8  237.08  6630.7  237.26  6636.5  241.57  6680.9  243.07
#Mann= 10 ,-1 , 0
  2718.4     .05       0  4494.6     .07       0  4609.3     .05       0
  4849.5     .12       0  4988.9     .05       0  5012.8     .12       0
  5079.4     .05       0  6283.7    .035       0  6564.2     .07       0
  6588.8     .05       0
Bank Sta=4988.9,5012.8
XS Rating Curve= 0 ,0
Exp/Cntr=0.3,0.1

Type RM Length L Ch R = 1 ,4755    ,1002,1002,1002
BEGIN DESCRIPTION:
FULCHER CREEK 6.0
END DESCRIPTION:
XS GIS Cut Line= 3
      2496524.26     13645989.61      2495308.99      13644123.3
      2494202.22     13643222.69
#Sta/Elev= 30
  3219.2  238.46  3283.1  236.58  3808.5  219.91  4024.2   203.8    4074  196.76
  4176.7  204.86  4406.1  201.88  4804.4  205.19  4819.6  200.47  4825.5  203.55
  4834.7  198.06  4847.6  196.13  4913.1  195.28  4965.2  185.87  4973.6  184.62
  4974.1  184.12  4997.6  184.62  5027.8   191.4  5079.1  190.96  5109.4  198.62
  5115.4  197.01  5130.5  204.56  5143.9  202.83  6095.4  210.25  6293.6  216.35
    6403  223.86  6528.4  234.24  6627.5  234.35  6827.2  242.72  6873.2  239.21
#Mann= 7 ,-1 , 0
  3219.2    .035       0  3283.1     .05       0  4965.2      .1       0
  4973.6     .05       0  4997.6      .1       0  5143.9     .05       0
    6403    .035       0
Bank Sta=4973.6,4997.6
XS Rating Curve= 0 ,0
Exp/Cntr=0.3,0.1

Type RM Length L Ch R = 1 ,3753    ,681,681,681
BEGIN DESCRIPTION:
FULCHER CREEK 5.0
END DESCRIPTION:
XS GIS Cut Line= 3
      2497066.82     13645837.73      2496328.96     13644459.67
      2494354.15      13643135.9
#Sta/Elev= 30
    3630  240.67  3986.9  223.57  4415.8  208.74  4638.6  204.45  4704.4  205.53
  4896.1  203.25  4918.1  197.59  4926.2  191.72  4934.3  188.41  4961.9  187.79
  4978.2  182.07  5004.1   181.8  5004.6   181.3  5028.6   181.8  5030.4  182.82
  5060.3  196.38  5087.9  199.37  5169.9  196.28  5186.2  197.44  5207.2  202.73
  5228.3   204.1  5336.3   202.8    5523  204.79  5624.5  207.98  5747.5  214.84
  5969.6  216.23  6951.1  211.05  7368.3  221.74  7427.5   225.6  7570.6  233.69
#Mann= 5 ,-1 , 0
    3630     .05       0  5004.1     .05       0  5028.6     .05       0
  5030.4     .05       0  7427.5    .035       0
Bank Sta=5004.1,5028.6
XS Rating Curve= 0 ,0
Exp/Cntr=0.3,0.1

Type RM Length L Ch R = 1 ,3072    ,0,0,0
BEGIN DESCRIPTION:
FULCHER CREEK 4.0
END DESCRIPTION:
XS GIS Cut Line= 4
      2497522.54     13645989.62      2497121.06     13644492.23
       2496231.3     13643559.07       2494332.4     13642853.76
#Sta/Elev= 30
  3217.7  249.45  3462.5  245.18  3577.3  237.49    3687  226.04  3881.9  218.61
    4817  200.41  4897.7   192.9  4918.7  200.54  4932.9  197.83  4940.1  193.49
  4961.2  191.69  4982.6  181.61  4998.6  180.26  4999.1  179.76  5023.2  180.26
    5032  180.79  5039.2  190.53  5046.1  187.91  5053.4  196.29  5060.3  193.37
  5067.5  198.24  5074.4  196.48  5081.7  200.19  5180.6  201.52  6015.2  202.28
    7000  210.74  7519.8  210.41  7807.4  212.67  8041.6  219.61    8083  221.51
#Mann= 6 ,-1 , 0
  3217.7     .05       0    4817      .1       0  4998.6     .05       0
  5023.2      .1       0  5180.6     .05       0  8041.6    .035       0
Bank Sta=4998.6,5023.2
XS Rating Curve= 0 ,0
Exp/Cntr=0.3,0.1

Chan Stop Cuts=-1
Use User Specified Reach Order=0
Composite Channel Slope=5