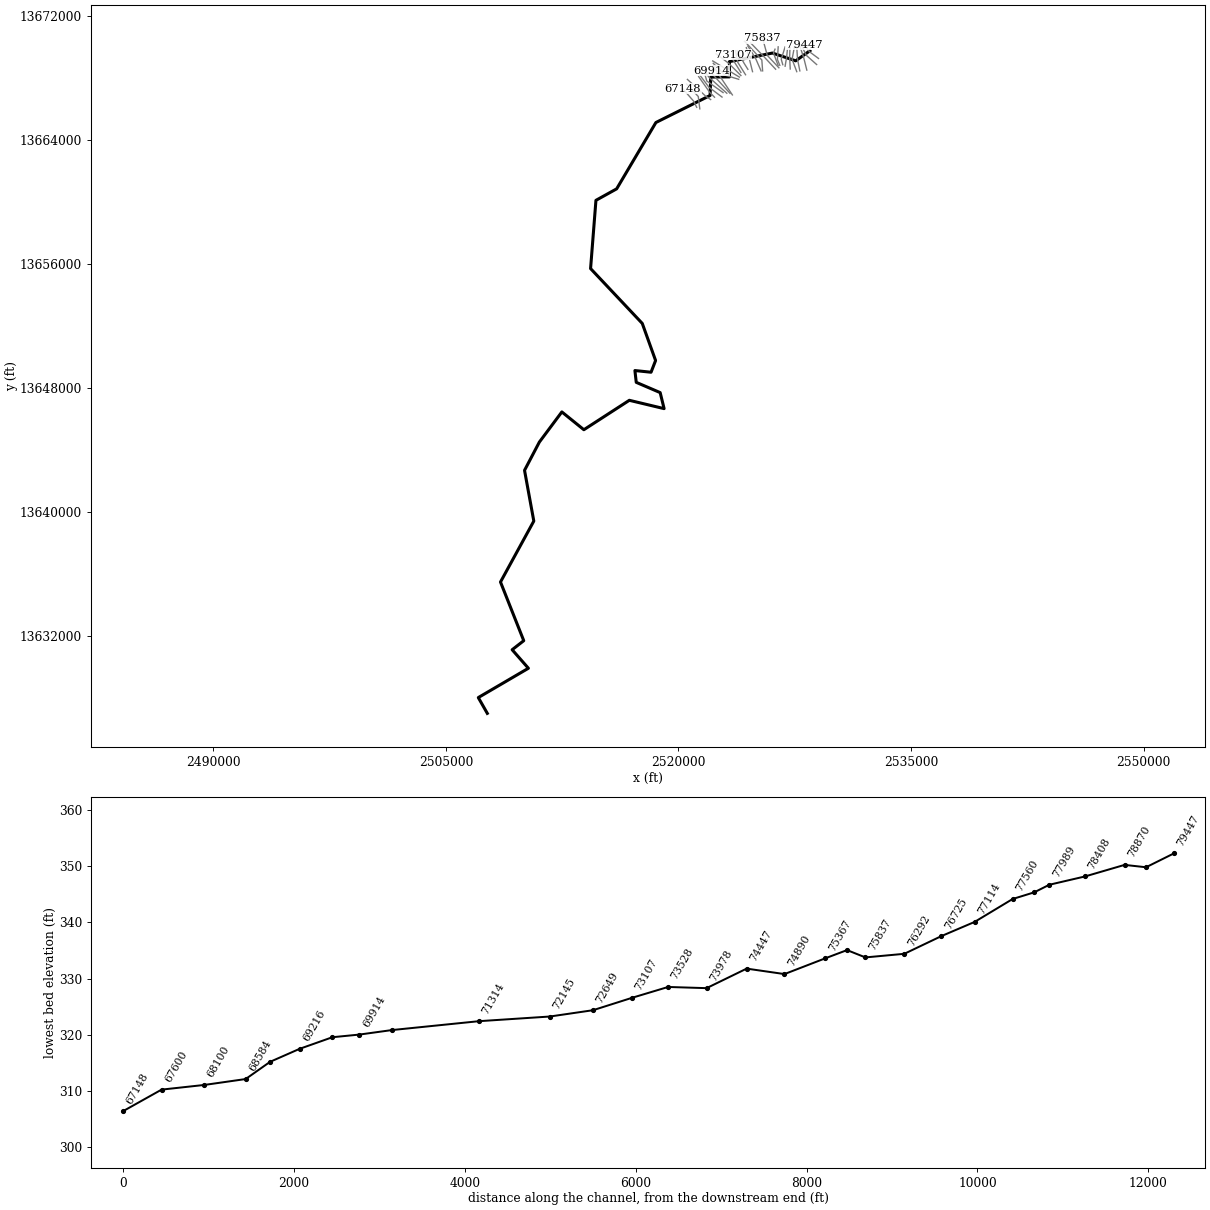
--- MCCOY CREEK.prj (project) ---

Proj Title=MCCOY CREEK Base Level Engineering
Current Plan=p01
Default Exp/Contr=0.3,0.1
English Units
Geom File=g01
Flow File=f01
Plan File=p01
Y Axis Title=Elevation
X Axis Title(PF)=Main Channel Distance
X Axis Title(XS)=Station
BEGIN DESCRIPTION:
MCCOY CREEK
END DESCRIPTION:
DSS Export Rating Curves= 0
DSS Export Rating Curve Sorted= 0
DSS Export Volume Flow Curves= 0
DXF OffsetX= 0
DXF OffsetY= 0
DXF ScaleX= 1
DXF ScaleY= 10

--- MCCOY CREEK.p01 (plan) ---

Plan Title=Multiple Run
Short Identifier=Multiple
Geom File=g01
Flow File=f01
Subcritical Flow
K Sum by GR= 0
Std Step Tol= 0.01
Critical Tol= 0.01
Num of Std Step Trials= 20
Max Error Tol= 0.3
Flow Tol Ratio= 0.001
Split Flow NTrial= 30
Split Flow Tol= 0.02
Split Flow Ratio= 0.02
Log Output Level= 0
Friction Slope Method= 1
Unsteady Friction Slope Method= 2
Unsteady Bridges Friction Slope Method= 1
Parabolic Critical Depth
Global Vel Dist=  1 , 1 , 1
Global Log Level= 0
CheckData=True
Encroach Param= -1, 0, 0, 0
BEGIN DESCRIPTION:
Multiple Run
END DESCRIPTION:

--- MCCOY CREEK.f01 (steady flow) ---

Flow Title=Multiple
Number of Profiles=7
Profile Names=10-year,25-year,50-year,1pct_min,100-year,1pct_plu,500-year
River Rch & RM= MCCOY CREEK,Reach-1,79447
     719    1159    1557    1013    2022    4035    3374
River Rch & RM= MCCOY CREEK,Reach-1,78870
    1151    1901    2596    1714    3419    6823    5875
River Rch & RM= MCCOY CREEK,Reach-1,74890
    1327    2203    3017    1996    3982    7946    6874
River Rch & RM= MCCOY CREEK,Reach-1,72145
    1518    2523    3457    2287    4562    9103    7872
River Rch & RM= MCCOY CREEK,Reach-1,67600
    1764    2948    4055    2691    5369   10713    9325
River Rch & RM= MCCOY CREEK,Reach-1,63096
    1938    3243    4462    2960    5907   11786   10257
River Rch & RM= MCCOY CREEK,Reach-1,57621
    1929    3226    4436    2942    5869   11711   10180
River Rch & RM= MCCOY CREEK,Reach-1,57150
    2344    3944    5447    3624    7231   14429   12631
River Rch & RM= MCCOY CREEK,Reach-1,49544
    2332    3917    5404    3592    7167   14299   12490
River Rch & RM= MCCOY CREEK,Reach-1,49224
    2520    4246    5870    3910    7801   15564   13648
River Rch & RM= MCCOY CREEK,Reach-1,46878
    2611    4410    6108    4074    8129   16219   14267
River Rch & RM= MCCOY CREEK,Reach-1,44204
    2871    4865    6753    4513    9005   17967   15868
River Rch & RM= MCCOY CREEK,Reach-1,35705
    5487    9519   13427    9107   18171   36257   32968
River Rch & RM= MCCOY CREEK,Reach-1,31852
    5567    9661   13630    9246   18448   36809   33479
River Rch & RM= MCCOY CREEK,Reach-1,27766
    5621    9725   13692    9267   18490   36893   33400
River Rch & RM= MCCOY CREEK,Reach-1,17891
    5721    9899   13938    9434   18823   37557   34003
River Rch & RM= MCCOY CREEK,Reach-1,15598
    5742    9952   14024    9499   18953   37816   34299
River Rch & RM= MCCOY CREEK,Reach-1,12860
    5881   10203   14387    9751   19455   38818   35249
River Rch & RM= MCCOY CREEK,Reach-1,10272
    5858   10142   14281    9664   19282   38474   34831
River Rch & RM= MCCOY CREEK,Reach-1,1460
    6039   10471   14761    9999   19951   39807   36112
Boundary for River Rch & Prof#=MCCOY CREEK,Reach-1,1
Up Type=0
Dn Type=3
Dn Slope=0.001
Boundary for River Rch & Prof#=MCCOY CREEK,Reach-1,2
Up Type=0
Dn Type=3
Dn Slope=0.001
Boundary for River Rch & Prof#=MCCOY CREEK,Reach-1,3
Up Type=0
Dn Type=3
Dn Slope=0.001
Boundary for River Rch & Prof#=MCCOY CREEK,Reach-1,4
Up Type=0
Dn Type=3
Dn Slope=0.001
Boundary for River Rch & Prof#=MCCOY CREEK,Reach-1,5
Up Type=0
Dn Type=3
Dn Slope=0.001
Boundary for River Rch & Prof#=MCCOY CREEK,Reach-1,6
Up Type=0
Dn Type=3
Dn Slope=0.001
Boundary for River Rch & Prof#=MCCOY CREEK,Reach-1,7
Up Type=0
Dn Type=3
Dn Slope=0.001

--- MCCOY CREEK.g01 (geometry) ---

Geom Title=Existing Conditions
Program Version=4.10

River Reach=MCCOY CREEK     ,Reach-1
Reach XY= 30
        2528475.       13669775.      2527559.66     13669124.96
      2526059.84     13669625.47      2523283.32     13669072.03
      2523288.82     13668088.23      2522080.52     13668077.43
       2522038.8     13666888.26      2518544.59     13665145.21
      2516014.25     13660865.29      2514678.46      13660123.5
      2514332.82     13655721.59      2517665.89     13652181.73
      2518524.61     13649790.16      2518231.95     13649033.84
       2517191.1     13649142.18      2517277.24     13648380.93
      2518819.56     13647719.83      2519074.02     13646685.26
      2516830.97     13647222.86      2513900.09     13645324.79
      2512480.93     13646472.76      2511030.46     13644527.45
      2510074.72     13642704.82      2510672.74     13639430.94
      2508524.76     13635500.08      2510023.96     13631714.57
      2509276.96     13631130.88      2510323.81      13629935.5
      2507094.21       13628045.        2507675.       13627025.

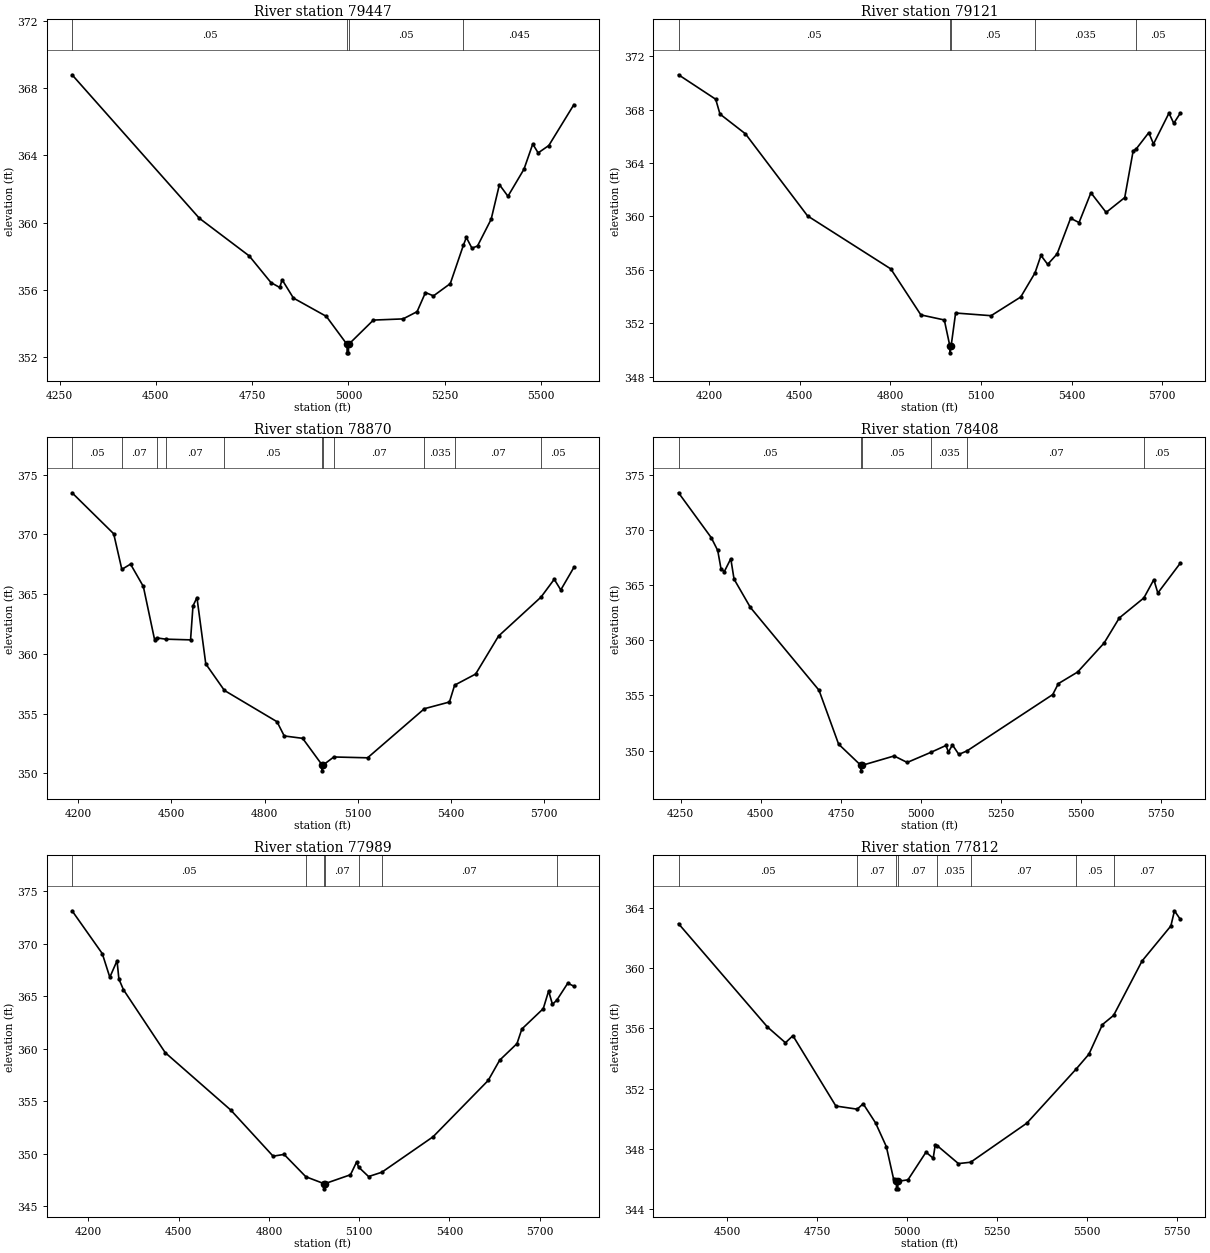
Type RM Length L Ch R = 1 ,79447   ,326,326,326
BEGIN DESCRIPTION:
B19372
END DESCRIPTION:
XS GIS Cut Line= 3
      2529029.52     13669276.11      2528450.97     13669705.89
      2528098.32     13670168.75
#Sta/Elev= 30
  4282.5   368.8  4612.9  360.26  4742.3  358.02  4798.9  356.43  4821.6  356.14
  4827.8   356.6  4857.1  355.51  4942.6  354.42  4996.3  352.75  4996.5  352.25
    5000  352.25  5000.3  352.75  5064.7   354.2  5141.7  354.27  5178.1   354.7
  5199.9  355.84  5220.7  355.64  5264.3  356.37  5298.1  358.64    5306  359.12
  5320.5  358.48    5335  358.61  5370.4   360.2  5391.8  362.26    5414  361.57
  5455.6  363.18  5478.4  364.68  5492.4  364.15  5520.1  364.59  5585.1  367.02
#Mann= 4 ,-1 , 0
  4282.5     .05       0  4996.3     .05       0  5000.3     .05       0
  5298.1    .045       0
Bank Sta=4996.3,5000.3
XS Rating Curve= 0 ,0
Exp/Cntr=0.3,0.1

Type RM Length L Ch R = 1 ,79121   ,251,251,251
BEGIN DESCRIPTION:
MCCOY CREEK 117.0
END DESCRIPTION:
XS GIS Cut Line= 3
      2528908.29      13668884.9      2528241.58     13669479.97
      2527899.99     13670168.66
#Sta/Elev= 30
  4098.1   370.6  4221.2  368.77  4235.4  367.66  4319.8  366.18  4525.5  360.04
  4801.4  356.07  4900.9  352.63  4978.6  352.25  4997.1  350.29  4997.4  349.79
  5001.1  350.29    5016  352.77  5133.6  352.57  5231.8  353.97    5279  355.77
  5298.8  357.08  5321.1  356.41  5352.2  357.19    5397  359.86    5425  359.54
  5464.3  361.77  5514.7   360.3  5576.3  361.41  5604.3  364.91  5613.3  365.02
    5656  366.27  5671.6  365.42  5722.9  367.73  5738.8  366.97  5760.5  367.73
#Mann= 5 ,-1 , 0
  4098.1     .05       0  4997.1     .05       0  5001.1     .05       0
    5279    .035       0  5613.3     .05       0
Bank Sta=4997.1,5001.1
XS Rating Curve= 0 ,0
Exp/Cntr=0.3,0.1

Type RM Length L Ch R = 1 ,78870   ,462,462,462
BEGIN DESCRIPTION:
MCCOY CREEK 116.0
END DESCRIPTION:
XS GIS Cut Line= 3
      2528275.01     13668524.96        2528075.       13669325.
      2527825.01     13670074.97
#Sta/Elev= 30
    4180  373.48    4314  370.05  4340.2  367.07  4368.2  367.51  4409.4  365.64
  4445.5   361.2  4452.1  361.34  4481.1  361.23  4561.4  361.17  4569.2  364.01
    4582  364.71  4610.4  359.16  4670.3  356.94  4839.7  354.32  4862.9  353.13
  4922.2  352.93  4984.6  350.71  4984.9  350.21  4988.7  350.71  5022.6  351.37
  5131.2   351.3  5314.1  355.41  5394.7  355.97  5411.4  357.38    5479  358.31
  5552.8  361.49  5689.5  364.75    5732  366.24  5753.1  365.35  5795.2  367.23
#Mann= 11 ,-1 , 0
    4180     .05       0  4340.2     .07       0  4452.1     .05       0
  4481.1     .07       0  4670.3     .05       0  4984.6     .05       0
  4988.7     .05       0  5022.6     .07       0  5314.1    .035       0
  5411.4     .07       0  5689.5     .05       0
Bank Sta=4984.6,4988.7
XS Rating Curve= 0 ,0
Exp/Cntr=0.3,0.1

Type RM Length L Ch R = 1 ,78408   ,419,419,419
BEGIN DESCRIPTION:
MCCOY CREEK 115.0
END DESCRIPTION:
XS GIS Cut Line= 3
      2527824.99     13668475.04        2527675.       13669225.
        2527625.     13670025.03
#Sta/Elev= 30
  4243.2  373.38  4345.1  369.32  4365.5  368.15  4375.7   366.5  4385.9  366.22
  4406.3   367.4  4416.5  365.55  4467.5  362.98  4681.7  355.47  4742.9  350.58
  4812.2  348.66  4812.4  348.16  4816.3  348.66  4916.2  349.51    4957  348.92
  5030.3  349.83  5078.1  350.46  5085.7  349.86  5098.2  350.51  5118.2  349.65
  5143.8  349.97  5411.3  355.08  5428.8  356.07  5488.9  357.12  5571.6  359.75
  5619.2  362.03  5695.7  363.84  5726.9   365.5  5739.4  364.29  5809.6     367
#Mann= 6 ,-1 , 0
  4243.2     .05       0  4812.2     .05       0  4816.3     .05       0
  5030.3    .035       0  5143.8     .07       0  5695.7     .05       0
Bank Sta=4812.2,4816.3
XS Rating Curve= 0 ,0
Exp/Cntr=0.3,0.1

Type RM Length L Ch R = 1 ,77989   ,177,177,177
BEGIN DESCRIPTION:
MCCOY CREEK 114.0
END DESCRIPTION:
XS GIS Cut Line= 3
      2527624.99     13668425.02        2527325.       13669225.
        2527475.     13670024.98
#Sta/Elev= 30
  4145.6  373.16  4246.1  369.08  4271.1  366.83  4295.1   368.4  4301.3  366.66
  4316.5  365.64  4455.3  359.65  4673.3  354.18    4814  349.79  4850.5  349.96
  4922.9  347.83  4982.7  347.18    4983  346.68  4986.9  347.18  5071.2  348.02
  5091.5  349.23  5098.3  348.75  5131.4  347.85  5175.4  348.26  5345.9  351.64
    5529     357  5567.2  358.93  5624.8  360.51    5641   361.9  5712.2  363.84
    5730  365.52  5742.7  364.25  5757.2  364.65  5793.6  366.26  5813.9  365.98
#Mann= 7 ,-1 , 0
  4145.6     .05       0  4922.9     .07       0  4982.7     .05       0
  4986.9     .07       0  5098.3    .035       0  5175.4     .07       0
  5757.2     .05       0
Bank Sta=4982.7,4986.9
XS Rating Curve= 0 ,0
Exp/Cntr=0.3,0.1

Type RM Length L Ch R = 1 ,77812   ,252,252,252
BEGIN DESCRIPTION:
B19371
END DESCRIPTION:
XS GIS Cut Line= 3
      2527205.65      13668598.3      2527167.08     13669369.77
      2527189.08     13669991.24
#Sta/Elev= 30
  4364.8  362.97  4611.8   356.1  4661.9  355.05  4682.6  355.52    4802  350.84
  4861.3  350.63  4877.8  350.99  4912.2  349.72  4942.2  348.14  4962.2     346
  4970.2  345.83  4970.4  345.33  4974.1  345.33  4974.4  345.83  5002.3  345.93
  5052.4  347.77  5072.4  347.37  5078.1  348.25  5084.2  348.19  5142.5  347.01
  5176.4   347.1  5332.6   349.7    5470  353.31  5505.1  354.29  5542.7  356.26
  5573.7  356.87  5652.8  360.49  5732.8  362.82  5742.8  363.83  5759.1  363.26
#Mann= 8 ,-1 , 0
  4364.8     .05       0  4861.3     .07       0  4970.2     .05       0
  4974.4     .07       0  5084.2    .035       0  5176.4     .07       0
    5470     .05       0  5573.7     .07       0
Bank Sta=4970.2,4974.4
XS Rating Curve= 0 ,0
Exp/Cntr=0.3,0.1

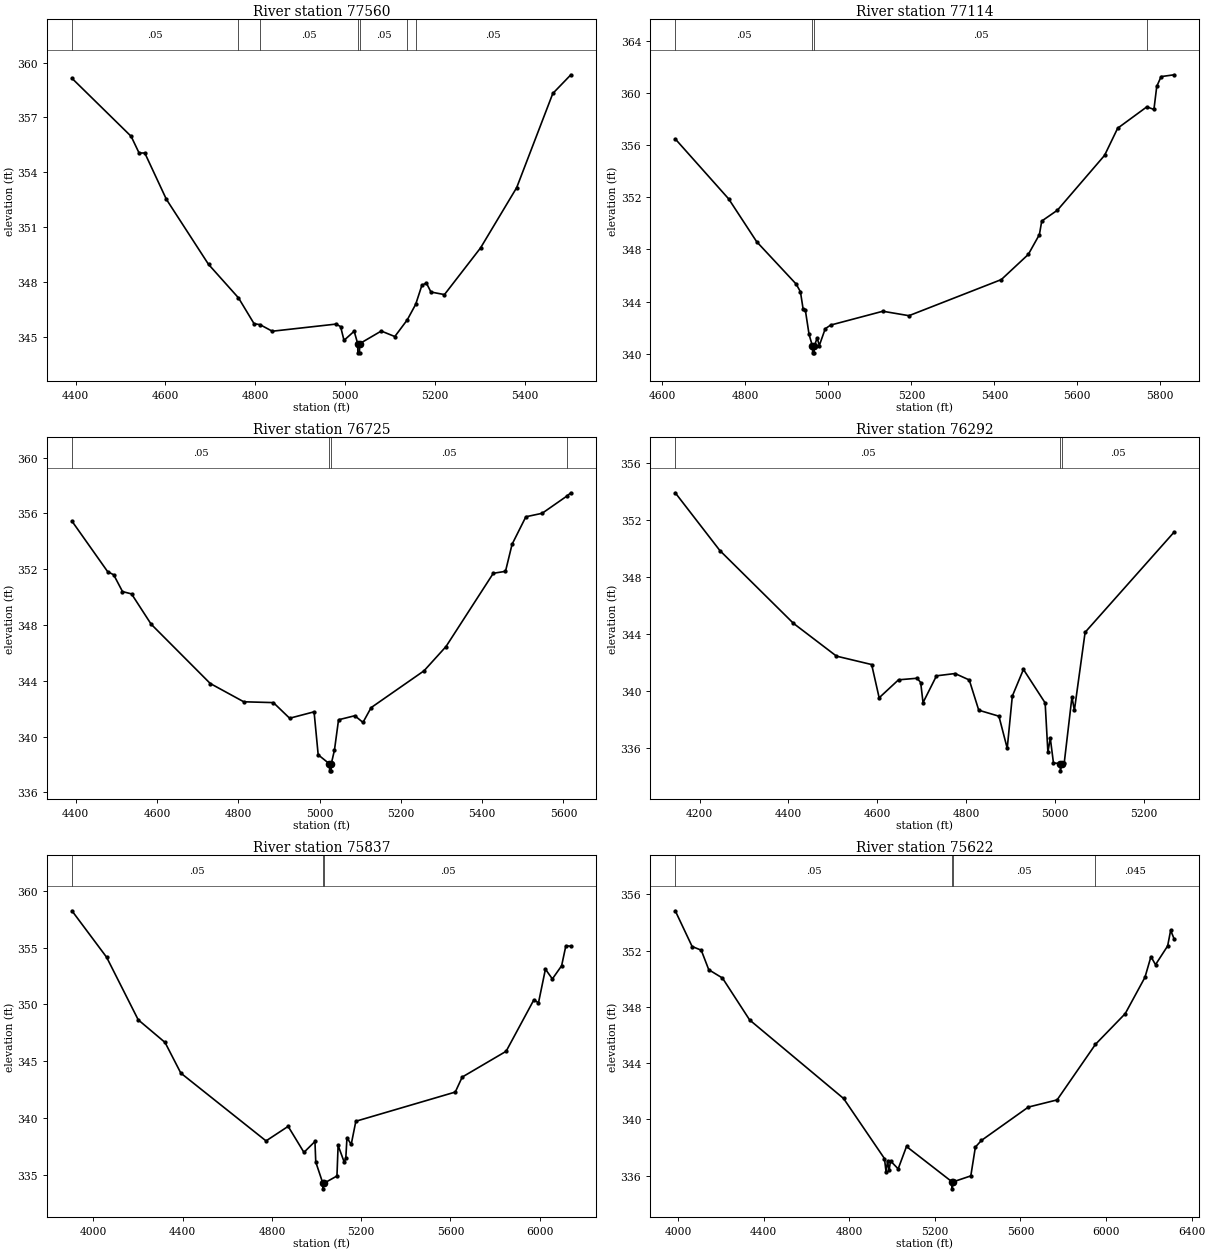
Type RM Length L Ch R = 1 ,77560   ,446,446,446
BEGIN DESCRIPTION:
MCCOY CREEK 113.0
END DESCRIPTION:
XS GIS Cut Line= 3
      2526875.01     13668775.03        2526975.       13669375.
        2527025.     13669874.96
#Sta/Elev= 30
  4391.7  359.14  4523.5  355.97  4541.2  355.06  4553.9  355.06    4602  352.53
  4695.8  348.98  4762.5  347.15  4797.2  345.74  4810.3  345.69  4837.7  345.33
  4979.7  345.72  4989.8  345.58  4997.4  344.83    5020  345.33  5027.9  344.65
  5028.2  344.15  5031.9  344.15  5032.2  344.65  5080.3  345.34  5110.5  345.04
  5138.2  345.95    5157   346.8  5170.8  347.84  5180.8  347.96  5190.9  347.47
    5221  347.33  5301.4  349.88  5381.8  353.17  5462.2  358.31  5502.4  359.33
#Mann= 7 ,-1 , 0
  4391.7     .05       0  4762.5    .035       0  4810.3     .05       0
  5027.9     .05       0  5032.2     .05       0  5138.2    .035       0
    5157     .05       0
Bank Sta=5027.9,5032.2
XS Rating Curve= 0 ,0
Exp/Cntr=0.3,0.1

Type RM Length L Ch R = 1 ,77114   ,389,389,389
BEGIN DESCRIPTION:
MCCOY CREEK 112.0
END DESCRIPTION:
XS GIS Cut Line= 3
        2526725.       13668875.        2526625.       13669225.
      2526875.01     13670025.04
#Sta/Elev= 30
  4631.1  356.48  4759.8  351.88  4827.4  348.59  4922.3  345.35  4932.7  344.76
  4939.2  343.43  4944.4  343.38  4953.5  341.49  4961.8  340.57  4962.1  340.07
  4965.8  340.07  4966.1  340.57    4973  341.22  4978.2  340.63  4992.5  341.92
  5005.6   342.2  5131.3  343.26  5194.2  342.92  5416.8  345.69  5481.8  347.62
  5508.5  349.14  5514.2  350.18  5551.9  351.01  5665.6  355.22  5697.1   357.3
  5767.4  358.94  5784.5  358.74  5791.3  360.51  5801.8  361.26  5833.3   361.4
#Mann= 4 ,-1 , 0
  4631.1     .05       0  4961.8     .05       0  4966.1     .05       0
  5767.4     .07       0
Bank Sta=4961.8,4966.1
XS Rating Curve= 0 ,0
Exp/Cntr=0.3,0.1

Type RM Length L Ch R = 1 ,76725   ,433,433,433
BEGIN DESCRIPTION:
B19370
END DESCRIPTION:
XS GIS Cut Line= 3
      2526533.42     13668829.72      2526379.11     13669209.97
       2526428.7      13670025.5
#Sta/Elev= 30
  4390.8  355.45  4478.6  351.83  4493.6   351.6  4515.2   350.4  4537.5  350.23
  4585.7  348.06  4731.1  343.81  4813.5   342.5  4886.4  342.44  4926.4  341.32
  4986.5  341.78  4996.6   338.7  5024.4  338.05  5024.7  337.55  5028.5  337.55
  5028.8  338.05  5036.6  339.03  5046.7  341.21  5086.7   341.5  5106.8  341.02
  5126.8  342.08    5257  344.72  5311.1  346.46  5427.4  351.71  5457.4  351.85
  5473.6  353.79  5507.5  355.76  5547.6  356.01  5608.7  357.25  5618.2  357.48
#Mann= 4 ,-1 , 0
  4390.8     .05       0  5024.4     .05       0  5028.8     .05       0
  5608.7     .07       0
Bank Sta=5024.4,5028.8
XS Rating Curve= 0 ,0
Exp/Cntr=0.3,0.1

Type RM Length L Ch R = 1 ,76292   ,455,455,455
BEGIN DESCRIPTION:
MCCOY CREEK 111.0
END DESCRIPTION:
XS GIS Cut Line= 3
      2526424.99     13668825.02        2526125.       13669625.
      2526224.99     13669874.97
#Sta/Elev= 30
  4145.1   353.9  4245.6  349.85  4411.2  344.75  4508.2  342.45  4587.4  341.86
  4604.3  339.53  4647.9  340.79  4689.8   340.9  4697.8   340.6  4703.1  339.19
  4733.4  341.07  4775.2  341.23  4807.2  340.78  4828.6  338.66    4874  338.24
  4892.7  335.99  4904.2  339.65  4929.2  341.52  4978.1  339.17  4984.3  335.72
  4989.7   336.7  4996.8  334.97  5012.1  334.91  5012.4  334.41  5016.5  334.91
    5021  334.94  5038.5   339.6  5043.9  338.64  5068.1  344.12  5268.7  351.15
#Mann= 3 ,-1 , 0
  4145.1     .05       0  5012.1     .05       0  5016.5     .05       0
Bank Sta=5012.1,5016.5
XS Rating Curve= 0 ,0
Exp/Cntr=0.3,0.1

Type RM Length L Ch R = 1 ,75837   ,215,215,215
BEGIN DESCRIPTION:
MCCOY CREEK 110.0
END DESCRIPTION:
XS GIS Cut Line= 3
      2526474.98     13668675.02        2525725.       13669475.
      2525425.01     13670574.97
#Sta/Elev= 30
  3903.4  358.25  4058.9  354.16  4200.6  348.65  4320.8  346.66  4391.6  343.96
  4773.6  337.99  4872.7  339.27  4943.5  336.98  4992.9  337.94  4996.5  336.13
  5028.1  334.27  5028.5  333.77    5034  334.27  5091.5   334.9  5096.7  337.59
  5124.3  336.11  5131.2  336.48  5136.4  338.27  5155.4  337.68  5176.2  339.72
  5621.9  342.29    5653  343.61  5849.9  345.88  5974.3  350.41    5995  350.15
  6026.1  353.11  6057.2  352.25  6098.7  353.41  6117.7  355.17  6140.1  355.13
#Mann= 3 ,-1 , 0
  3903.4     .05       0  5028.1     .05       0    5034     .05       0
Bank Sta=5028.1,5034
XS Rating Curve= 0 ,0
Exp/Cntr=0.3,0.1

Type RM Length L Ch R = 1 ,75622   ,255,255,255
BEGIN DESCRIPTION:
B19369
END DESCRIPTION:
XS GIS Cut Line= 3
      2526263.38     13668581.81      2525525.02     13669375.28
      2524659.99     13670273.37
#Sta/Elev= 30
  3987.3  354.83  4066.2  352.29  4108.7  352.03  4143.9  350.64  4207.9  350.05
  4334.9  347.07  4773.7  341.49  4964.7  337.22  4972.1  336.26  4978.9  337.03
  4986.2   336.4  4993.1  337.05  5028.7  336.49  5067.6  338.08  5280.1  335.57
  5280.6  335.07  5286.1  335.57    5368  335.99  5389.4  338.04  5417.7  338.51
  5636.8  340.88  5771.1  341.39  5950.4  345.34  6089.4  347.52  6181.5   350.1
  6209.5  351.57  6230.9     351  6287.5  352.33  6301.6  353.44  6318.1  352.82
#Mann= 4 ,-1 , 0
  3987.3     .05       0  5280.1     .05       0  5286.1     .05       0
  5950.4    .045       0
Bank Sta=5280.1,5286.1
XS Rating Curve= 0 ,0
Exp/Cntr=0.3,0.1

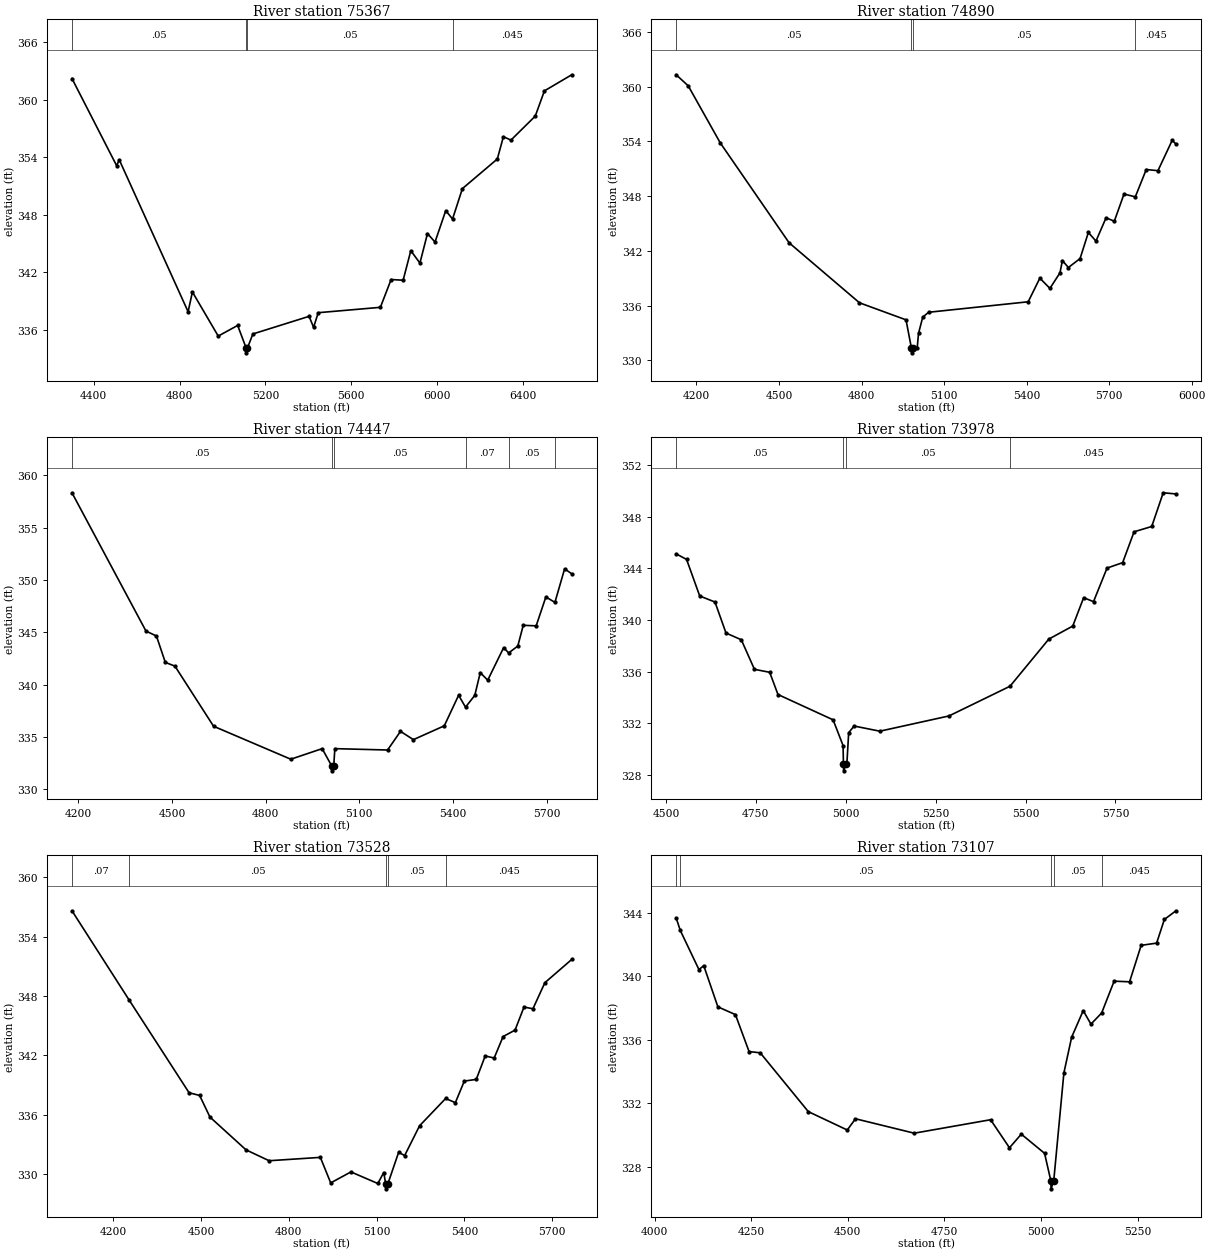
Type RM Length L Ch R = 1 ,75367   ,477,477,477
BEGIN DESCRIPTION:
MCCOY CREEK 109.0
END DESCRIPTION:
XS GIS Cut Line= 3
        2525425.     13668474.96        2525375.       13669175.
      2524275.01     13670374.99
#Sta/Elev= 30
  4298.5  362.24  4506.6  353.15  4519.1  353.75  4839.9   337.9    4860  339.96
  4980.3  335.36  5070.9  336.47  5110.5  334.11    5111  333.61  5116.5  334.11
  5141.8  335.58  5403.9  337.42  5424.9  336.27  5446.5   337.8  5736.3  338.36
  5786.2  341.26  5842.3  341.19  5878.1  344.27  5920.6  342.98  5955.8  346.06
  5990.9  345.17  6040.9  348.45  6072.7  347.58  6118.6  350.75  6281.4  353.84
  6309.7  356.17  6344.9  355.81  6458.3  358.32  6500.9  360.95  6628.2  362.63
#Mann= 4 ,-1 , 0
  4298.5     .05       0  5110.5     .05       0  5116.5     .05       0
  6072.7    .045       0
Bank Sta=5110.5,5116.5
XS Rating Curve= 0 ,0
Exp/Cntr=0.3,0.1

Type RM Length L Ch R = 1 ,74890   ,443,443,443
BEGIN DESCRIPTION:
MCCOY CREEK 108.0
END DESCRIPTION:
XS GIS Cut Line= 3
        2525325.     13668474.99        2524975.       13669275.
      2524475.01     13670074.99
#Sta/Elev= 30
  4126.3  361.31    4170   360.1  4286.5  353.84  4536.8  342.88  4792.5   336.3
  4961.7  334.43  4981.5  331.31    4982  330.81  4988.6  331.31  5002.5  331.38
  5007.2  332.95  5022.5  334.72  5043.7  335.26  5405.8  336.41  5448.2     339
  5484.8  337.88  5521.3  339.58  5530.2  340.93    5552  340.17  5594.4  341.15
  5624.5  344.01  5652.2  343.07  5688.8  345.62  5718.9  345.25  5754.2  348.23
  5795.2  347.92    5835  350.92  5877.5  350.79  5929.4  354.13  5942.9  353.71
#Mann= 4 ,-1 , 0
  4126.3     .05       0  4981.5     .05       0  4988.6     .05       0
  5795.2    .045       0
Bank Sta=4981.5,4988.6
XS Rating Curve= 0 ,0
Exp/Cntr=0.3,0.1

Type RM Length L Ch R = 1 ,74447   ,469,469,469
BEGIN DESCRIPTION:
MCCOY CREEK 107.0
END DESCRIPTION:
XS GIS Cut Line= 3
      2524775.01     13668424.95        2524575.       13669225.
      2524374.99     13669975.02
#Sta/Elev= 30
  4179.5  358.34  4416.6  345.13  4450.1  344.66  4478.5  342.14  4509.4  341.78
  4633.1  336.04  4880.5  332.89    4981   333.9  5010.9  332.28  5011.4  331.78
  5018.1  332.28  5021.6   333.9  5190.5  333.77  5231.9  335.55  5273.3  334.76
  5372.2  336.08  5418.1     339  5440.2  337.86  5469.9  338.99  5487.4  341.16
  5511.3  340.44  5562.4  343.55  5578.4  343.04  5607.7   343.7  5625.1  345.68
  5666.5  345.63  5697.6  348.39  5726.6  347.87  5757.7  351.08  5780.4   350.6
#Mann= 6 ,-1 , 0
  4179.5     .05       0  5010.9     .05       0  5018.1     .05       0
  5440.2     .07       0  5578.4     .05       0  5726.6    .045       0
Bank Sta=5010.9,5018.1
XS Rating Curve= 0 ,0
Exp/Cntr=0.3,0.1

Type RM Length L Ch R = 1 ,73978   ,450,450,450
BEGIN DESCRIPTION:
MCCOY CREEK 106.0
END DESCRIPTION:
XS GIS Cut Line= 3
      2524474.99     13668575.02        2524225.       13668975.
      2523774.98     13669775.04
#Sta/Elev= 30
  4528.5  345.11  4557.4  344.68  4593.9  341.85  4636.4  341.38    4667  338.98
  4709.5  338.46  4746.1  336.17  4788.5  335.94  4811.5  334.22  4964.8  332.26
  4992.5  330.27  4993.6  328.81  4994.1  328.31  5000.9  328.81    5003  328.81
  5008.1  331.26  5023.1  331.78  5094.8  331.38    5287  332.56  5456.7  334.86
  5564.6  338.51  5631.2  339.52  5661.5  341.72  5688.9  341.41  5726.5  344.01
  5769.9  344.43  5801.7  346.82  5850.8  347.23  5882.7  349.84  5918.1  349.75
#Mann= 4 ,-1 , 0
  4528.5     .05       0  4993.6     .05       0  5000.9     .05       0
  5456.7    .045       0
Bank Sta=4993.6,5000.9
XS Rating Curve= 0 ,0
Exp/Cntr=0.3,0.1

Type RM Length L Ch R = 1 ,73528   ,421,421,421
BEGIN DESCRIPTION:
MCCOY CREEK 105.0
END DESCRIPTION:
XS GIS Cut Line= 3
      2524324.99     13668225.02        2523825.       13669025.
      2523675.01     13669774.97
#Sta/Elev= 30
  4058.9  356.62  4254.1  347.61  4459.2  338.23  4495.2  337.96  4530.6  335.77
  4653.8  332.46  4732.8  331.36  4907.9   331.7  4943.3  329.12  5012.5  330.23
  5104.3  329.06  5124.7  330.17  5131.2  329.02  5131.7  328.52  5138.6  329.02
  5175.6  332.22    5196  331.88    5247  334.89  5336.1  337.65  5369.4  337.23
    5400  339.41  5440.8  339.58  5471.4  341.95    5502  341.74  5532.6  343.91
  5573.4  344.56    5604  346.89  5634.6  346.72  5675.3  349.35  5767.1   351.7
#Mann= 5 ,-1 , 0
  4058.9     .07       0  4254.1     .05       0  5131.2     .05       0
  5138.6     .05       0  5336.1    .045       0
Bank Sta=5131.2,5138.6
XS Rating Curve= 0 ,0
Exp/Cntr=0.3,0.1

Type RM Length L Ch R = 1 ,73107   ,458,458,458
BEGIN DESCRIPTION:
MCCOY CREEK 104.0
END DESCRIPTION:
XS GIS Cut Line= 3
      2524024.98     13668375.03        2523525.       13669175.
        2523525.     13669525.03
#Sta/Elev= 30
  4055.9  343.68  4066.5   342.9  4114.8  340.43  4127.2  340.68  4163.8  338.08
  4209.2  337.59  4244.5  335.26  4273.4  335.18  4397.9  331.47  4498.7  330.31
  4519.9  331.02    4672  330.11  4869.6  330.96  4918.5  329.19  4949.1  330.05
  5009.3  328.84  5025.6   327.1  5026.1   326.6    5033   327.1  5059.3  333.91
  5079.3  336.16  5109.3  337.84  5129.3  336.99    5157  337.69  5189.3   339.7
  5229.3  339.66  5259.3  341.96  5299.3   342.1  5319.3  343.59  5349.3  344.14
#Mann= 5 ,-1 , 0
  4055.9     .07       0  4066.5     .05       0  5025.6     .05       0
    5033     .05       0    5157    .045       0
Bank Sta=5025.6,5033
XS Rating Curve= 0 ,0
Exp/Cntr=0.3,0.1

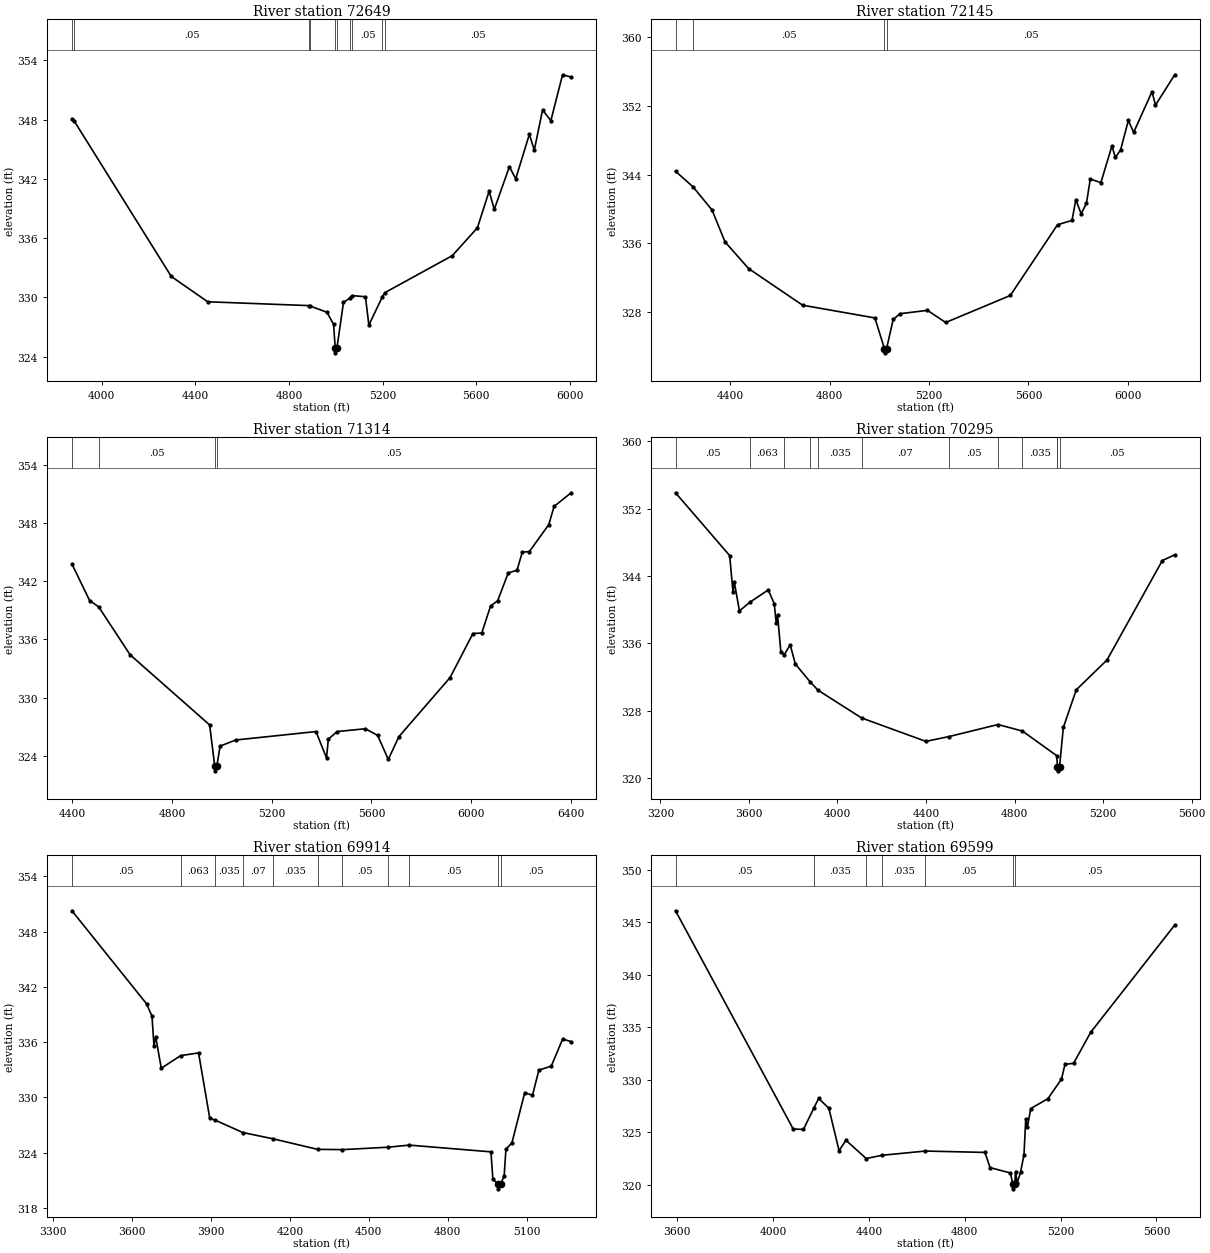
Type RM Length L Ch R = 1 ,72649   ,504,504,504
BEGIN DESCRIPTION:
MCCOY CREEK 103.0
END DESCRIPTION:
XS GIS Cut Line= 3
      2524025.01     13668174.99        2523225.       13668975.
      2522424.99     13669575.01
#Sta/Elev= 30
  3873.6  348.08  3881.9  347.91  4297.9  332.12  4453.4  329.56  4887.3  329.17
  4889.2  329.14  4962.6   328.5  4990.8  327.27  4997.8  324.89  4998.3  324.39
  5005.2  324.89  5033.1   329.5  5059.2  329.91  5071.3  330.18  5126.9  330.07
  5141.4   327.2  5199.5  330.08  5210.3  330.49  5497.7  334.23    5605  337.05
    5655  340.76  5676.9  338.91  5741.4  343.23  5768.5  342.01  5826.9  346.52
  5847.7   344.9  5883.1  348.97  5918.5   347.9  5968.5  352.54    6005  352.31
#Mann= 10 ,-1 , 0
  3873.6     .07       0  3881.9     .05       0  4887.3      .1       0
  4889.2     .05       0  4997.8     .05       0  5005.2     .05       0
  5059.2      .1       0  5071.3     .05       0  5199.5      .1       0
  5210.3     .05       0
Bank Sta=4997.8,5005.2
XS Rating Curve= 0 ,0
Exp/Cntr=0.3,0.1

Type RM Length L Ch R = 1 ,72145   ,831,831,831
BEGIN DESCRIPTION:
B19366
END DESCRIPTION:
XS GIS Cut Line= 2
      2523927.06     13668074.84      2522208.92     13669115.64
#Sta/Elev= 30
  4179.8  344.39  4250.4  342.57  4326.6  339.89  4378.9  336.18    4474  333.07
  4691.2  328.81  4982.1  327.33  5020.4  323.77  5020.9  323.27  5029.1  323.77
  5055.8  327.15  5082.9  327.82  5193.5  328.21  5267.1   326.8    5527  329.94
  5717.1  338.17  5775.3  338.67  5790.8  341.08  5812.1  339.44  5833.4  340.66
  5848.9  343.48  5891.6  343.07    5936  347.34  5949.8  345.99  5971.1  346.89
  6002.1   350.3  6023.5  348.91  6097.2  353.64  6111.3  352.08  6188.6  355.61
#Mann= 4 ,-1 , 0
  4179.8     .07       0  4250.4     .05       0  5020.4     .05       0
  5029.1     .05       0
Bank Sta=5020.4,5029.1
XS Rating Curve= 0 ,0
Exp/Cntr=0.3,0.1

Type RM Length L Ch R = 1 ,71314   ,1019,1019,1019
BEGIN DESCRIPTION:
B19365
END DESCRIPTION:
XS GIS Cut Line= 3
      2523882.99     13667931.58      2523001.32     13668201.59
      2522240.89     13668967.53
#Sta/Elev= 30
  4399.3  343.76  4470.4  339.99  4506.5  339.35  4632.7   334.4  4951.5  327.17
  4971.7  322.94  4972.2  322.44  4980.4  322.94  4993.3  324.99  5056.1  325.62
  5377.8  326.49  5420.2  323.76  5427.2  325.71  5462.6  326.49  5575.8  326.78
  5625.2  326.09  5667.7  323.61  5710.1  325.96  5915.2  332.05  6007.1   336.6
  6042.5  336.65  6077.8  339.44  6106.1  339.97  6148.5  342.84  6183.9  343.13
  6205.1  344.99  6233.4  345.05  6311.2  347.83  6332.4   349.7  6400.7  351.11
#Mann= 4 ,-1 , 0
  4399.3     .07       0  4506.5     .05       0  4971.7     .05       0
  4980.4     .05       0
Bank Sta=4971.7,4980.4
XS Rating Curve= 0 ,0
Exp/Cntr=0.3,0.1

Type RM Length L Ch R = 1 ,70295   ,381,381,381
BEGIN DESCRIPTION:
MCCOY CREEK 102.0
END DESCRIPTION:
XS GIS Cut Line= 3
      2523474.99     13666925.02      2522566.01     13668284.24
      2522251.93     13668818.73
#Sta/Elev= 30
  3268.3  353.88    3513  346.42    3528  342.04    3534  343.26    3557  339.86
  3605.9  340.91  3687.2  342.34  3714.2  340.71  3723.2  338.45  3729.2  339.41
  3744.2  334.94  3760.1  334.67  3786.3  335.83  3809.6  333.55  3876.3  331.43
  3911.8  330.44  4108.9  327.14  4399.1  324.36  4503.9  324.93  4725.2  326.36
  4835.8  325.58  4990.4  322.66  4993.9  321.36  4994.4  320.86  5003.2  321.36
  5020.3  326.01  5078.7  330.48  5217.5  334.02  5467.4  345.83  5523.4  346.51
#Mann= 12 ,-1 , 0
  3268.3     .05       0  3605.9    .063       0  3760.1    .035       0
  3876.3     .07       0  3911.8    .035       0  4108.9     .07       0
  4503.9     .05       0  4725.2     .12       0  4835.8    .035       0
  4990.4     .05       0  4993.9     .05       0  5003.2     .05       0
Bank Sta=4993.9,5003.2
XS Rating Curve= 0 ,0
Exp/Cntr=0.3,0.1

Type RM Length L Ch R = 1 ,69914   ,315,315,315
BEGIN DESCRIPTION:
MCCOY CREEK 101.0
END DESCRIPTION:
XS GIS Cut Line= 3
      2523325.02     13667024.98        2522225.       13668225.
      2522124.99     13668475.02
#Sta/Elev= 30
  3371.7  350.27  3655.1  340.17    3676  338.81  3683.4   335.6  3690.2  336.57
  3711.2  333.16  3784.7  334.53    3853  334.83  3895.6  327.71  3914.9  327.54
  4020.8  326.18  4135.4   325.5  4305.7  324.35  4399.6  324.32  4571.7  324.58
  4654.1  324.81  4964.2  324.08  4971.6   321.1  4991.6  320.56  4992.1  320.06
  5000.9  320.56  5014.4  321.47  5021.2  324.37    5044  325.06  5092.5   330.5
  5122.1  330.23  5146.4  332.96  5193.5  333.39  5236.6  336.33  5268.9  336.06
#Mann= 11 ,-1 , 0
  3371.7     .05       0  3784.7    .063       0  3914.9    .035       0
  4020.8     .07       0  4135.4    .035       0  4305.7     .07       0
  4399.6     .05       0  4571.7    .035       0  4654.1     .05       0
  4991.6     .05       0  5000.9     .05       0
Bank Sta=4991.6,5000.9
XS Rating Curve= 0 ,0
Exp/Cntr=0.3,0.1

Type RM Length L Ch R = 1 ,69599   ,383,383,383
BEGIN DESCRIPTION:
B19368
END DESCRIPTION:
XS GIS Cut Line= 3
      2523117.03     13667033.42       2521970.9     13668058.32
      2521656.82     13668504.65
#Sta/Elev= 30
  3592.9  346.08  4084.1  325.29  4126.7  325.25  4169.5  327.25  4190.2   328.2
  4232.8  327.27  4275.5  323.22  4303.9  324.22  4388.6  322.48    4456  322.79
  4635.5  323.19  4884.1  323.06  4905.8  321.61  4990.8   321.1  4999.7  320.09
  5000.2  319.59  5009.1  320.09  5011.9  321.24  5018.6  320.15  5032.8  321.16
  5047.1  322.83  5054.6  326.25  5061.3  325.46  5075.5  327.24  5147.1  328.18
  5203.7  330.05  5218.5  331.45  5254.2  331.55  5325.6   334.5  5676.2  344.72
#Mann= 7 ,-1 , 0
  3592.9     .05       0  4169.5    .035       0  4388.6     .07       0
    4456    .035       0  4635.5     .05       0  4999.7     .05       0
  5009.1     .05       0
Bank Sta=4999.7,5009.1
XS Rating Curve= 0 ,0
Exp/Cntr=0.3,0.1

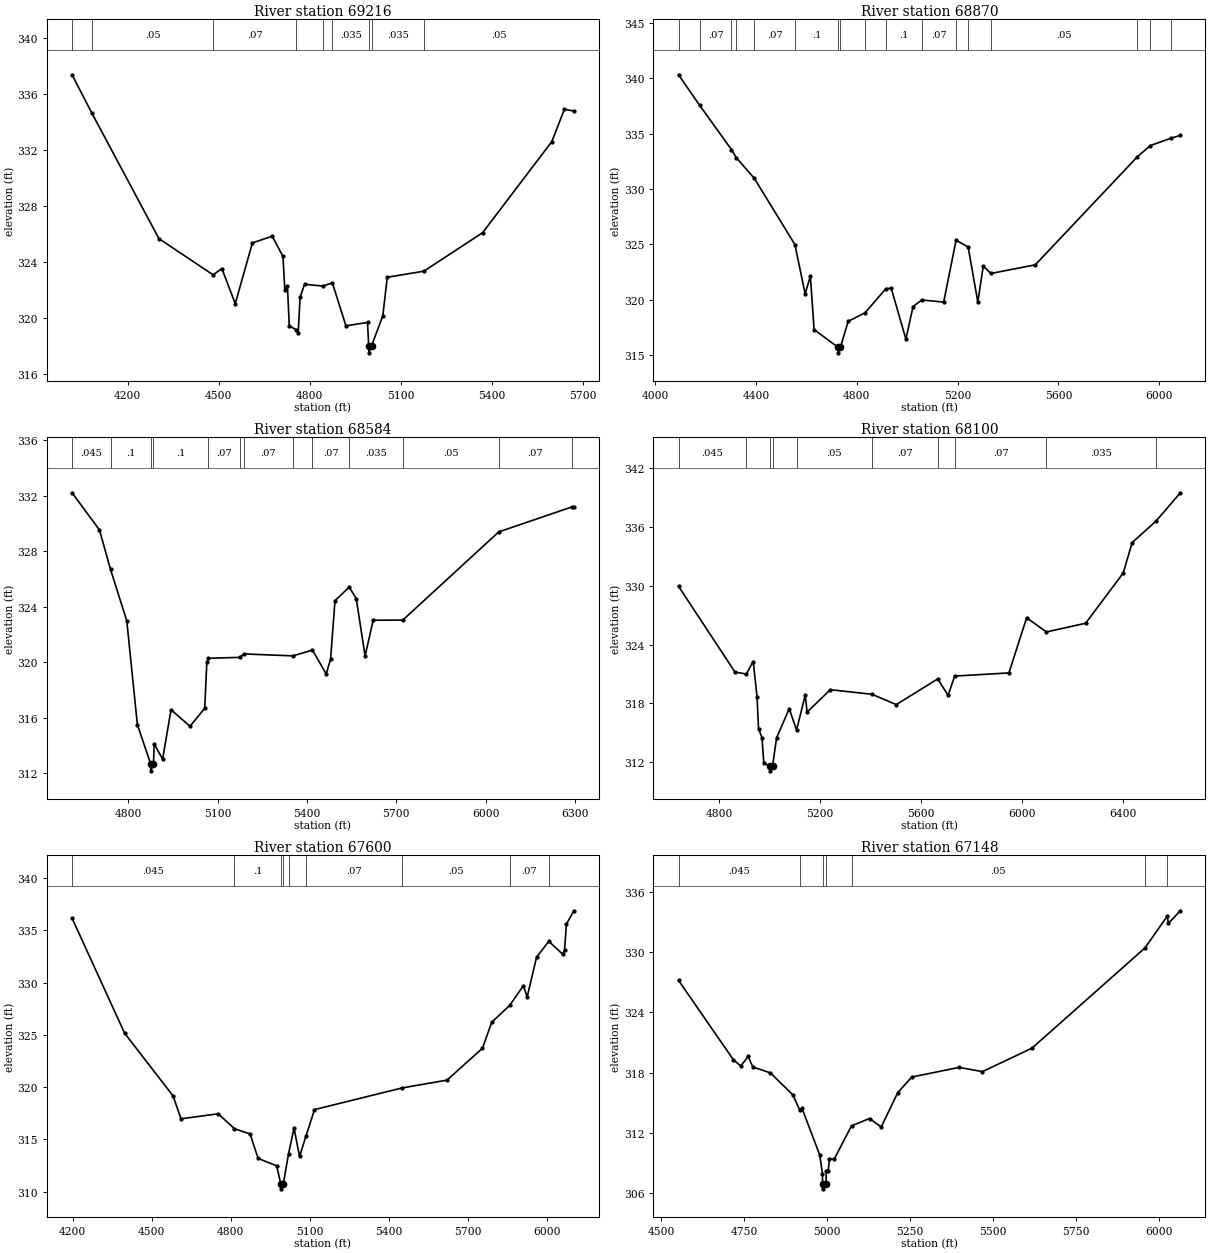
Type RM Length L Ch R = 1 ,69216   ,346,346,346
BEGIN DESCRIPTION:
MCCOY CREEK 100.0
END DESCRIPTION:
XS GIS Cut Line= 3
      2522875.03     13667074.98      2521822.12     13667826.89
      2521725.01     13668174.97
#Sta/Elev= 30
  4016.3  337.39  4080.9  334.68  4302.7  325.69  4481.5   323.1  4510.4  323.55
  4554.6  321.04  4611.1  325.38  4676.3  325.86  4711.9  324.42  4718.1  322.04
  4726.7  322.32  4732.8  319.45  4755.6  319.18  4762.3  318.98  4768.5  321.51
  4783.2  322.43  4843.1   322.3  4874.9  322.53  4919.6  319.46  4990.9   319.7
  4994.7  318.03  4995.2  317.53  5004.1  318.03  5041.3  320.17    5056  322.93
  5176.5  323.36  5370.5  326.11  5598.9  332.62  5640.4  334.93  5671.5   334.8
#Mann= 9 ,-1 , 0
  4016.3     .07       0  4080.9     .05       0  4481.5     .07       0
  4755.6    .035       0  4843.1      .1       0  4874.9    .035       0
  4994.7    .035       0  5004.1    .035       0  5176.5     .05       0
Bank Sta=4994.7,5004.1
XS Rating Curve= 0 ,0
Exp/Cntr=0.3,0.1

Type RM Length L Ch R = 1 ,68870   ,286,286,286
BEGIN DESCRIPTION:
B19367
END DESCRIPTION:
XS GIS Cut Line= 3
      2522808.45     13666785.46      2521959.88     13667424.64
      2521403.34     13668168.53
#Sta/Elev= 30
  4092.4  340.31  4176.6  337.54  4302.5  333.56    4322  332.82  4393.3  330.96
  4554.2  324.99  4594.9  320.54  4615.7  322.14  4630.3  317.32  4725.5  315.72
    4726  315.22    4735  315.72  4765.6  318.06  4832.9  318.84  4914.9     321
  4936.4  321.05  4994.7  316.46  5023.2   319.4  5057.7  319.99  5144.6   319.8
  5193.9  325.38  5241.8  324.77  5280.1  319.81  5301.8  323.05  5331.8  322.38
  5508.1  323.16  5913.2  332.91  5964.6  333.92  6047.4  334.59  6083.8  334.84
#Mann= 17 ,-1 , 0
  4092.4     .05       0  4176.6     .07       0  4302.5      .1       0
    4322     .05       0  4393.3     .07       0  4554.2      .1       0
  4725.5     .05       0    4735      .1       0  4832.9     .07       0
  4914.9      .1       0  5057.7     .07       0  5193.9     .05       0
  5241.8    .035       0  5331.8     .05       0  5913.2     .07       0
  5964.6    .035       0  6047.4     .07       0
Bank Sta=4725.5,4735
XS Rating Curve= 0 ,0
Exp/Cntr=0.3,0.1

Type RM Length L Ch R = 1 ,68584   ,484,484,484
BEGIN DESCRIPTION:
MCCOY CREEK 99.0
END DESCRIPTION:
XS GIS Cut Line= 3
        2522325.       13666775.      2521998.45     13667110.56
      2521299.34     13668106.93
#Sta/Elev= 30
  4610.8  332.21  4702.8  329.53  4739.9  326.69  4794.6  322.97  4830.1   315.5
  4874.7  312.66  4875.2  312.16  4884.2  312.66  4886.6  314.11  4914.9     313
  4943.2  316.57  5006.8  315.37  5056.4  316.67  5063.4  319.99  5068.7  320.28
  5173.8  320.34  5187.9  320.59  5352.3  320.45  5418.3  320.87  5464.3  319.14
  5479.1  320.22  5493.9  324.43  5541.8  325.41  5565.4  324.57    5595  320.44
  5622.1  323.02  5721.6  323.03  6043.9  329.39  6288.3  331.18  6296.2  331.18
#Mann= 13 ,-1 , 0
  4610.8    .045       0  4739.9      .1       0  4874.7     .05       0
  4884.2      .1       0  5068.7     .07       0  5173.8     .05       0
  5187.9     .07       0  5352.3     .05       0  5418.3     .07       0
  5541.8    .035       0  5721.6     .05       0  6043.9     .07       0
  6288.3     .05       0
Bank Sta=4874.7,4884.2
XS Rating Curve= 0 ,0
Exp/Cntr=0.3,0.1

Type RM Length L Ch R = 1 ,68100   ,500,500,500
BEGIN DESCRIPTION:
MCCOY CREEK 98.0
END DESCRIPTION:
XS GIS Cut Line= 3
      2522075.01       13666625.        2521775.       13666825.
      2520575.03     13667924.97
#Sta/Elev= 30
  4639.6  329.94  4863.5  321.18    4908  320.99  4935.6  322.26  4950.6  318.69
  4956.6  315.42  4970.1  314.51  4977.6  311.88  5002.4  311.61  5002.9  311.11
  5012.1  311.61  5028.2  314.48  5078.2  317.44  5107.3  315.27  5141.7  318.84
  5149.1   317.1    5241  319.39    5406  318.92  5502.4  317.87  5666.8  320.49
  5707.7  318.81  5733.9  320.78  5948.8   321.1  6019.1  326.73  6097.2  325.28
  6252.8  326.17  6401.4  331.28  6437.2   334.4  6532.1   336.6    6628  339.48
#Mann= 10 ,-1 , 0
  4639.6    .045       0    4908      .1       0  5002.4     .05       0
  5012.1      .1       0  5107.3     .05       0    5406     .07       0
  5666.8     .05       0  5733.9     .07       0  6097.2    .035       0
  6532.1    .045       0
Bank Sta=5002.4,5012.1
XS Rating Curve= 0 ,0
Exp/Cntr=0.3,0.1

Type RM Length L Ch R = 1 ,67600   ,452,452,452
BEGIN DESCRIPTION:
MCCOY CREEK 97.0
END DESCRIPTION:
XS GIS Cut Line= 3
        2521375.     13666025.03        2521275.       13666825.
      2520524.99     13667625.02
#Sta/Elev= 30
  4198.1  336.17  4397.1  325.18    4581  319.17  4611.3  316.98  4752.3  317.46
    4814  316.03  4873.3  315.53  4903.5  313.19  4974.1  312.48  4989.2  310.78
  4989.7  310.28  4999.2  310.78  5018.9  313.62  5039.7   316.1  5060.7  313.38
  5085.2  315.33  5117.4  317.86  5449.1  319.93    5620  320.68  5754.3  323.73
  5789.5  326.22  5857.3  327.82  5909.7  329.72  5923.8  328.63  5959.5  332.44
  6005.9  333.96  6058.6  332.72  6065.5  333.11  6072.8  335.61  6100.9  336.88
#Mann= 9 ,-1 , 0
  4198.1    .045       0    4814      .1       0  4989.2     .05       0
  4999.2      .1       0  5018.9     .05       0  5085.2     .07       0
  5449.1     .05       0  5857.3     .07       0  6005.9    .035       0
Bank Sta=4989.2,4999.2
XS Rating Curve= 0 ,0
Exp/Cntr=0.3,0.1

Type RM Length L Ch R = 1 ,67148   ,432,432,432
BEGIN DESCRIPTION:
MCCOY CREEK 96.0
END DESCRIPTION:
XS GIS Cut Line= 3
      2521174.99     13666125.03        2520975.       13666525.
        2520275.       13667325.
#Sta/Elev= 30
  4553.1  327.19    4718   319.3  4740.3  318.67  4762.7  319.62  4776.7  318.57
  4829.8  317.98  4896.9   315.8  4917.4  314.32  4924.8  314.45  4977.9  309.82
  4986.3  307.96  4986.5  306.94    4987  306.44  4997.3  306.94  4997.5  308.26
  5003.6  308.26  5007.4  309.43  5021.6   309.4  5073.7  312.71  5127.9  313.44
  5163.1   312.6  5212.9  316.02  5255.1  317.57  5397.5  318.53  5467.7  318.11
  5616.7  320.44  5956.8  330.42  6023.7  333.57  6027.7  332.88  6063.3  334.12
#Mann= 7 ,-1 , 0
  4553.1    .045       0  4917.4      .1       0  4986.5     .05       0
  4997.3      .1       0  5073.7     .05       0  5956.8     .07       0
  6023.7     .05       0
Bank Sta=4986.5,4997.3
XS Rating Curve= 0 ,0
Exp/Cntr=0.3,0.1