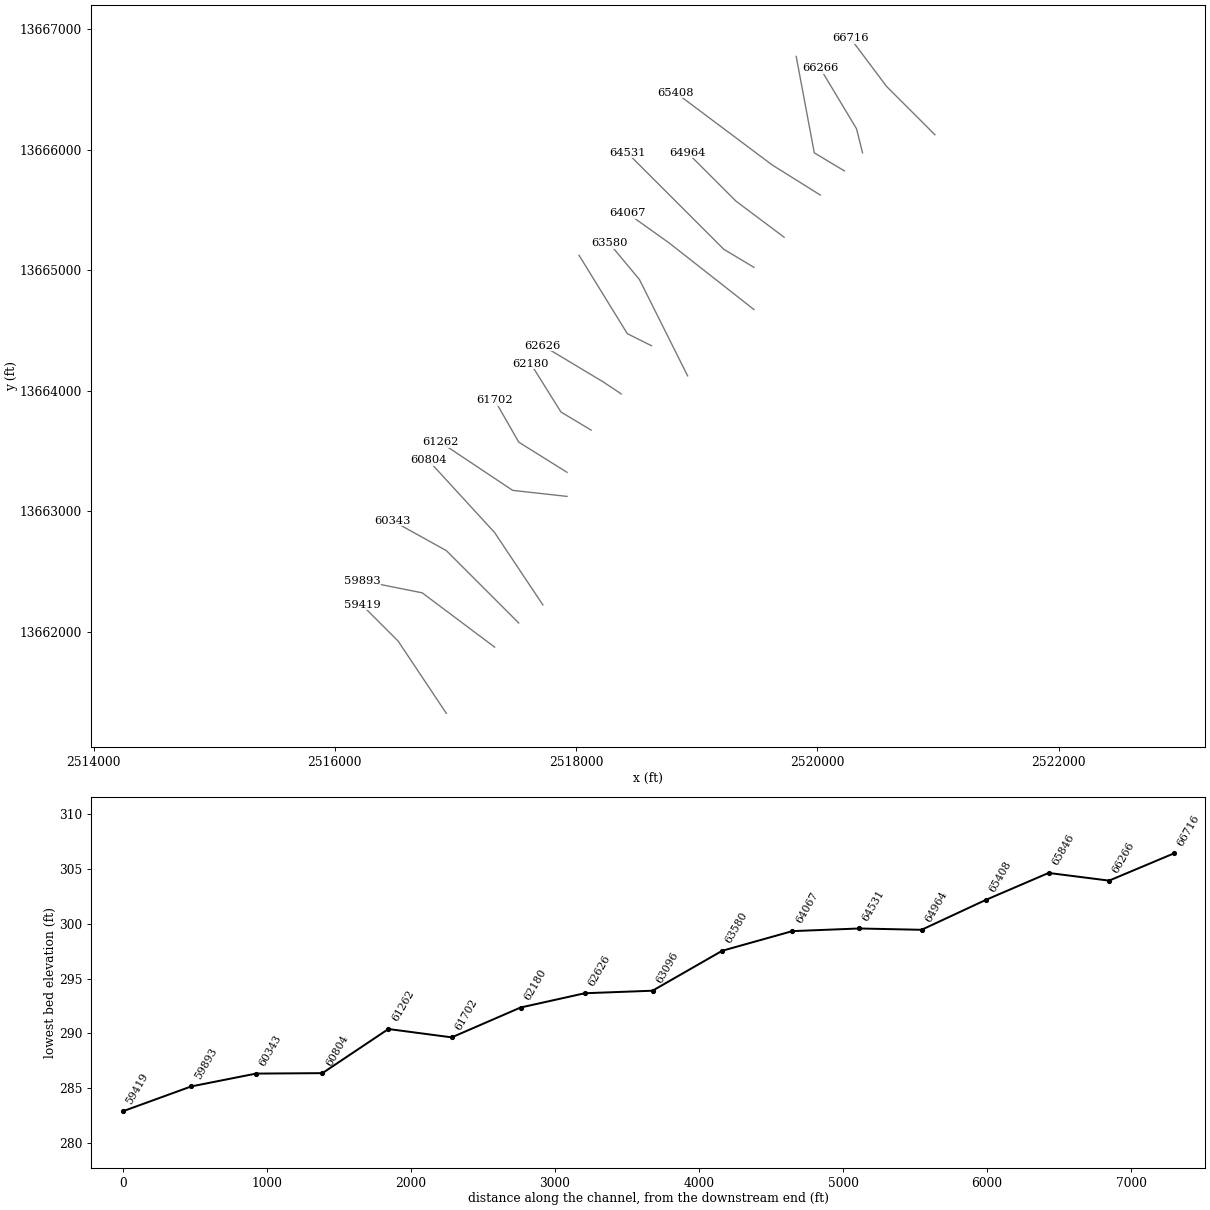
HEC-RAS study MCCOY CREEK.prj: MCCOY CREEK Base Level Engineering

--- MCCOY CREEK.g01 (geometry) --- (continued)

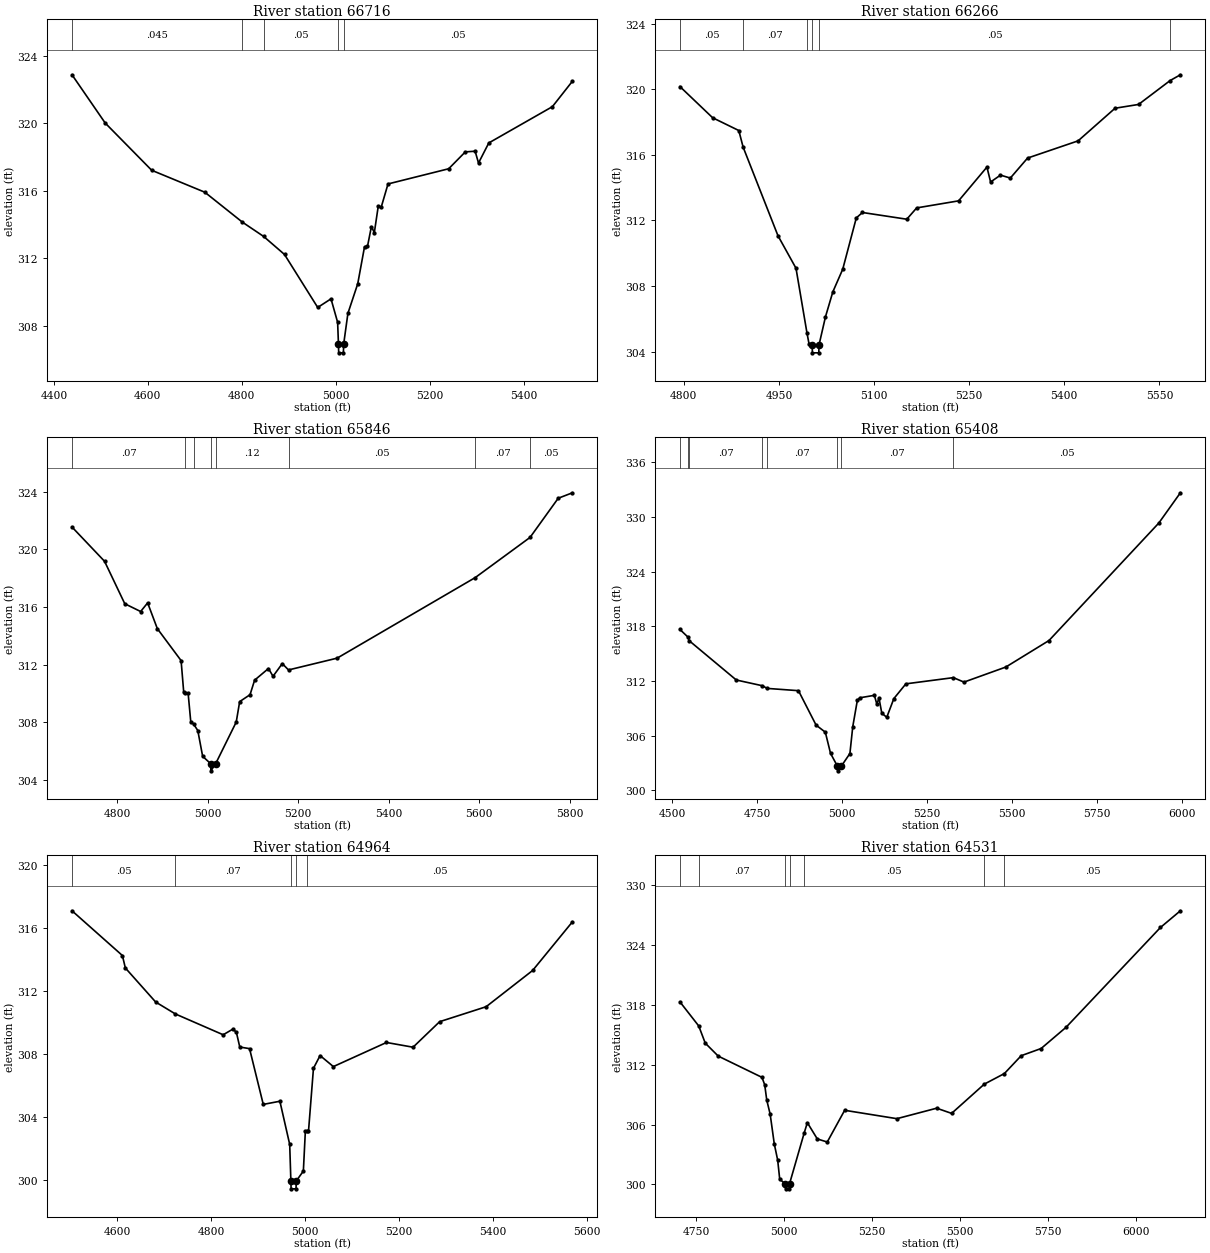
Type RM Length L Ch R = 1 ,66716   ,450,450,450
BEGIN DESCRIPTION:
MCCOY CREEK 95.0
END DESCRIPTION:
XS GIS Cut Line= 3
      2520974.97     13666125.03        2520575.       13666525.
      2520275.03     13666924.96
#Sta/Elev= 30
  4438.6  322.88  4509.3  320.02  4608.3  317.22  4721.4  315.92  4801.2  314.15
  4846.6   313.3  4891.1  312.23  4961.8  309.09  4990.1   309.6  5004.2  308.21
    5006   306.9  5006.5   306.4  5016.5   306.4    5017   306.9  5026.1  308.74
    5047  310.49  5061.5  312.69  5067.8  312.71  5076.1  313.88  5082.4  313.53
  5090.7  315.09    5097  315.03  5111.5  316.41  5240.7  317.31  5276.1  318.31
    5297  318.35  5304.2  317.65  5326.1  318.84  5461.5  320.99  5504.2   322.5
#Mann= 5 ,-1 , 0
  4438.6    .045       0  4801.2      .1       0  4846.6     .05       0
    5006     .05       0    5017     .05       0
Bank Sta=5006,5017
XS Rating Curve= 0 ,0
Exp/Cntr=0.3,0.1

Type RM Length L Ch R = 1 ,66266   ,420,420,420
BEGIN DESCRIPTION:
MCCOY CREEK 94.0
END DESCRIPTION:
XS GIS Cut Line= 3
        2520375.     13665975.01        2520325.       13666175.
      2520025.02     13666674.97
#Sta/Elev= 30
  4793.9  320.16  4845.4  318.26  4886.7  317.48  4893.5  316.47  4948.5  311.06
  4976.9  309.08  4994.3  305.11  4997.5  304.46  5002.3  304.42  5002.8  303.92
  5012.8  303.92  5013.3  304.42  5023.4  306.12    5035  307.64  5050.6  309.02
    5072  312.15  5081.7  312.48  5151.6  312.07  5167.2  312.76  5233.3  313.19
    5278  315.25  5283.8  314.34  5299.4  314.76  5314.9  314.58  5342.1   315.8
  5421.8  316.85  5480.1  318.84  5517.1  319.07    5567  320.53  5583.1  320.88
#Mann= 6 ,-1 , 0
  4793.9     .05       0  4893.5     .07       0  4994.3     .05       0
  5002.3     .05       0  5013.3     .05       0    5567     .07       0
Bank Sta=5002.3,5013.3
XS Rating Curve= 0 ,0
Exp/Cntr=0.3,0.1

Type RM Length L Ch R = 1 ,65846   ,438,438,438
BEGIN DESCRIPTION:
MCCOY CREEK 93.0
END DESCRIPTION:
XS GIS Cut Line= 3
      2520224.99     13665825.01        2519975.       13665975.
      2519824.99     13666775.03
#Sta/Elev= 30
  4700.3  321.56  4772.2  319.18  4816.9  316.23  4851.9  315.69  4867.4  316.29
  4888.8   314.5  4941.3  312.28  4947.1  310.08  4950.4  310.06  4956.8  310.02
  4962.7  308.01  4968.7  307.88  4978.2  307.42  4988.9  305.63  5006.6  305.12
  5007.1  304.62  5017.7  305.12  5063.1  308.01  5070.7  309.43  5093.6  309.91
  5103.7  310.92  5134.3  311.73  5144.4  311.19  5164.8  312.07  5178.6  311.63
    5286  312.45  5591.2  318.05  5712.2  320.84  5774.4  323.56  5805.8  323.94
#Mann= 8 ,-1 , 0
  4700.3     .07       0  4950.4     .05       0  4968.7     .12       0
  5006.6     .05       0  5017.7     .12       0  5178.6     .05       0
  5591.2     .07       0  5712.2     .05       0
Bank Sta=5006.6,5017.7
XS Rating Curve= 0 ,0
Exp/Cntr=0.3,0.1

Type RM Length L Ch R = 1 ,65408   ,444,444,444
BEGIN DESCRIPTION:
MCCOY CREEK 92.0
END DESCRIPTION:
XS GIS Cut Line= 3
      2520025.01     13665624.99        2519625.       13665875.
      2518825.01     13666474.99
#Sta/Elev= 30
  4523.5  317.65  4547.2  316.81  4550.3  316.43  4689.2  312.11    4766  311.48
  4779.8  311.19    4872  310.94  4923.9  307.16    4951  306.39  4966.3  304.07
  4986.7  302.65  4987.2  302.15  4997.8  302.65  5023.3  304.05  5031.7     307
  5045.2  309.89  5052.5  310.16  5095.2  310.43  5102.5  309.47  5108.8  310.13
  5117.1  308.47  5131.7  308.02  5152.5  310.07  5187.9  311.69  5327.5  312.37
  5358.8  311.88  5481.7  313.53  5608.8  316.44  5931.7  329.32  5995.2  332.64
#Mann= 8 ,-1 , 0
  4523.5     .07       0  4547.2     .05       0  4550.3     .07       0
    4766     .05       0  4779.8     .07       0  4986.7     .05       0
  4997.8     .07       0  5327.5     .05       0
Bank Sta=4986.7,4997.8
XS Rating Curve= 0 ,0
Exp/Cntr=0.3,0.1

Type RM Length L Ch R = 1 ,64964   ,433,433,433
BEGIN DESCRIPTION:
MCCOY CREEK 91.0
END DESCRIPTION:
XS GIS Cut Line= 3
      2519725.02     13665274.99        2519325.       13665575.
        2518925.       13665975.
#Sta/Elev= 30
    4504  317.09  4611.3  314.25  4617.6  313.46  4682.1   311.3  4724.2  310.54
  4825.9  309.22  4846.7  309.58    4854  309.38  4861.3  308.44  4882.1  308.34
  4911.3   304.8  4946.7     305  4967.6  302.26  4970.1  299.94  4970.6  299.44
  4981.1  299.44  4981.6  299.94  4996.7  300.57  5000.9  303.08  5003.4  303.08
  5007.6  303.08  5018.2  307.09  5032.3   307.9  5060.6   307.2  5173.7  308.73
  5230.3  308.43  5286.9  310.05  5385.9     311  5484.9   313.3  5569.7  316.39
#Mann= 5 ,-1 , 0
    4504     .05       0  4724.2     .07       0  4970.1     .05       0
  4981.6     .07       0  5003.4     .05       0
Bank Sta=4970.1,4981.6
XS Rating Curve= 0 ,0
Exp/Cntr=0.3,0.1

Type RM Length L Ch R = 1 ,64531   ,464,464,464
BEGIN DESCRIPTION:
MCCOY CREEK 90.0
END DESCRIPTION:
XS GIS Cut Line= 3
      2519474.98     13665025.01        2519225.       13665175.
      2518424.99     13665975.01
#Sta/Elev= 30
  4704.4  318.29  4757.8  315.88  4776.3  314.16  4813.2  312.86  4937.6  310.73
  4945.4  309.98  4951.2  308.45  4960.9  307.04  4972.6  304.06  4982.3  302.43
  4988.1  300.51  5004.3  300.06  5004.8  299.56  5015.4  299.56  5015.9  300.06
    5058   305.2  5066.6  306.19  5094.9  304.56  5123.2  304.25  5172.7  307.43
  5321.2  306.59  5434.3  307.64  5476.8  307.12  5569.7  310.05  5626.8  311.11
  5674.7   312.9  5731.3  313.62    5802  315.74  6070.7  325.75  6127.3  327.42
#Mann= 7 ,-1 , 0
  4704.4     .05       0  4757.8     .07       0  5004.3     .05       0
  5015.9     .07       0    5058     .05       0  5569.7     .12       0
  5626.8     .05       0
Bank Sta=5004.3,5015.9
XS Rating Curve= 0 ,0
Exp/Cntr=0.3,0.1

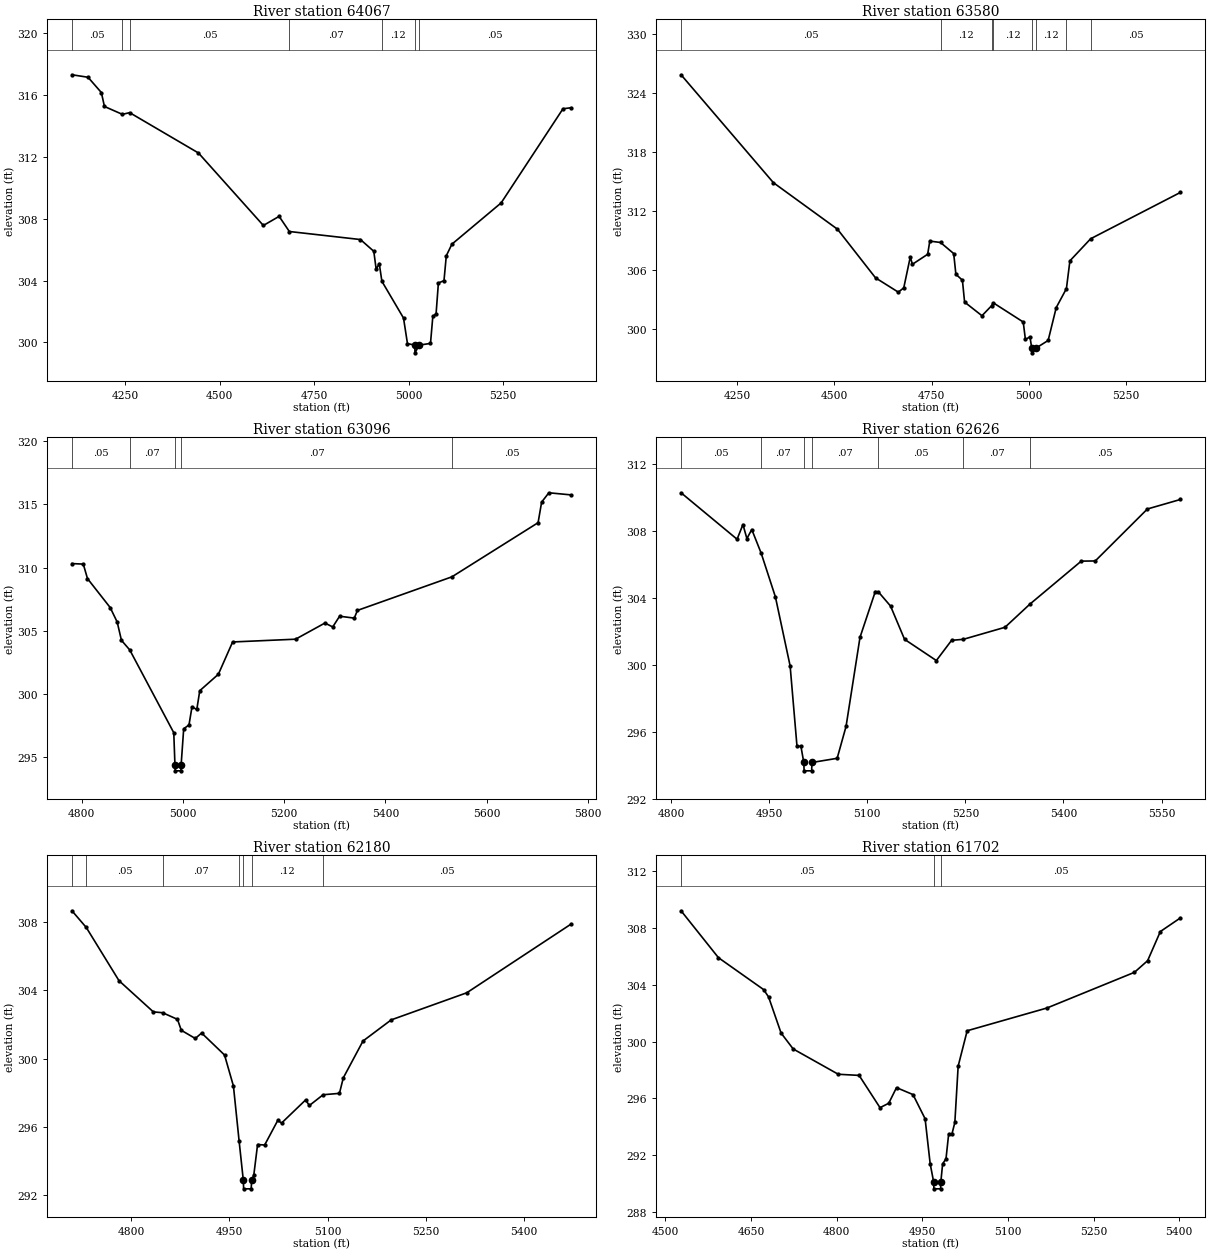
Type RM Length L Ch R = 1 ,64067   ,487,487,487
BEGIN DESCRIPTION:
MCCOY CREEK 89.0
END DESCRIPTION:
XS GIS Cut Line= 3
      2519475.03     13664674.97        2518775.       13665225.
      2518424.99     13665475.01
#Sta/Elev= 30
  4109.7  317.31  4152.2  317.15  4187.5  316.16  4195.6  315.26    4243  314.75
  4262.3  314.86  4444.2  312.25  4615.8  307.56  4657.5  308.15  4684.5  307.17
  4872.5  306.65  4907.8  305.89  4914.1  304.72  4922.2   305.1  4929.2  303.95
  4986.4  301.57  4996.8  299.92  5016.2  299.82  5016.7  299.32  5027.9  299.82
  5057.7  299.93  5063.9  301.68  5072.5  301.85  5078.6  303.84  5093.4  303.99
  5099.5   305.6  5114.3  306.35  5244.5  309.02    5408  315.11  5430.1  315.18
#Mann= 7 ,-1 , 0
  4109.7     .05       0    4243     .07       0  4262.3     .05       0
  4684.5     .07       0  4929.2     .12       0  5016.2     .05       0
  5027.9     .05       0
Bank Sta=5016.2,5027.9
XS Rating Curve= 0 ,0
Exp/Cntr=0.3,0.1

Type RM Length L Ch R = 1 ,63580   ,484,484,484
BEGIN DESCRIPTION:
MCCOY CREEK 88.0
END DESCRIPTION:
XS GIS Cut Line= 3
      2518924.99     13664125.03        2518525.       13664925.
      2518275.01     13665224.99
#Sta/Elev= 30
  4105.6  325.85  4343.2  314.86  4508.1  310.12  4605.9  305.17  4664.6  303.71
  4678.6  304.15  4695.3  307.28  4700.9  306.55  4740.1  307.57  4745.6  308.91
  4773.2  308.77  4807.1  307.64  4812.7  305.53  4829.5  304.93  4835.1   302.7
  4879.8  301.31  4904.4  302.32  4909.1  302.62    4986  300.67  4991.6  298.89
  5003.3  299.16  5007.8  298.03  5008.3  297.53  5019.5  298.03  5050.1  298.79
  5070.9  302.14  5097.1  304.07  5106.1   306.9  5159.5  309.15  5390.5  313.87
#Mann= 8 ,-1 , 0
  4105.6     .05       0  4773.2     .12       0  4904.4     .05       0
  4909.1     .12       0  5007.8     .05       0  5019.5     .12       0
  5097.1     .07       0  5159.5     .05       0
Bank Sta=5007.8,5019.5
XS Rating Curve= 0 ,0
Exp/Cntr=0.3,0.1

Type RM Length L Ch R = 1 ,63096   ,470,470,470
BEGIN DESCRIPTION:
MCCOY CREEK 87.0
END DESCRIPTION:
XS GIS Cut Line= 3
        2518625.       13664375.        2518425.       13664475.
      2518025.01     13665124.98
#Sta/Elev= 30
  4780.6  310.31    4803  310.27  4811.3  309.12  4856.1  306.83    4870  305.68
  4878.4  304.23  4894.8  303.47  4981.8  296.91  4984.1  294.39  4984.6  293.89
  4995.9  293.89  4996.4  294.39  5001.4  297.22  5011.9  297.53  5017.8  298.96
  5027.3  298.75  5033.2  300.24  5069.9  301.54  5098.1   304.1  5222.5  304.32
  5280.5   305.6  5295.9  305.29  5309.5  306.14  5338.5  305.99  5344.7   306.6
  5531.4  309.26  5701.7  313.55  5708.7  315.18    5723  315.92  5767.4  315.75
#Mann= 5 ,-1 , 0
  4780.6     .05       0  4894.8     .07       0  4984.1     .05       0
  4996.4     .07       0  5531.4     .05       0
Bank Sta=4984.1,4996.4
XS Rating Curve= 0 ,0
Exp/Cntr=0.3,0.1

Type RM Length L Ch R = 1 ,62626   ,446,446,446
BEGIN DESCRIPTION:
MCCOY CREEK 86.0
END DESCRIPTION:
XS GIS Cut Line= 3
      2518374.98     13663975.02        2518225.       13664075.
      2517725.04     13664374.98
#Sta/Elev= 30
  4815.5   310.3  4901.1  307.52  4910.1   308.4  4916.1  307.56  4923.6   308.1
    4938  306.68  4959.7  304.07  4982.2  299.94  4992.7  295.13  4998.7  295.13
  5003.1  294.16  5003.6  293.66  5015.1  293.66  5015.6  294.16  5054.1  294.41
  5067.7  296.32    5089  301.65  5112.4  304.39  5117.1  304.37  5135.7  303.52
  5157.1  301.53  5205.7  300.26    5229  301.47  5246.9  301.53  5310.6  302.25
  5348.8  303.64  5427.2  306.21  5448.6  306.22  5528.3  309.33  5578.8   309.9
#Mann= 7 ,-1 , 0
  4815.5     .05       0    4938     .07       0  5003.1     .05       0
  5015.6     .07       0  5117.1     .05       0  5246.9     .07       0
  5348.8     .05       0
Bank Sta=5003.1,5015.6
XS Rating Curve= 0 ,0
Exp/Cntr=0.3,0.1

Type RM Length L Ch R = 1 ,62180   ,478,478,478
BEGIN DESCRIPTION:
MCCOY CREEK 85.0
END DESCRIPTION:
XS GIS Cut Line= 3
      2518124.97     13663675.02        2517875.       13663825.
        2517625.     13664224.99
#Sta/Elev= 30
  4709.3  308.67  4731.2  307.69  4781.2  304.57  4833.7  302.74  4847.9  302.69
  4870.6   302.3  4876.4  301.66  4897.8  301.18  4907.5   301.5  4942.5  300.21
  4956.1  298.39  4964.7  295.19  4971.2  292.86  4971.7  292.36  4983.3  292.36
  4983.8  292.86  4987.2  293.16    4993  294.96  5003.8  294.93  5023.8  296.37
  5029.7  296.22  5066.3  297.57  5072.2  297.25  5093.2  297.88  5118.1  297.96
    5124  298.87  5154.1  301.03  5197.2  302.27  5312.7  303.86  5472.5   307.9
#Mann= 7 ,-1 , 0
  4709.3     .07       0  4731.2     .05       0  4847.9     .07       0
  4964.7     .12       0  4971.2     .05       0  4983.8     .12       0
  5093.2     .05       0
Bank Sta=4971.2,4983.8
XS Rating Curve= 0 ,0
Exp/Cntr=0.3,0.1

Type RM Length L Ch R = 1 ,61702   ,440,440,440
BEGIN DESCRIPTION:
MCCOY CREEK 84.0
END DESCRIPTION:
XS GIS Cut Line= 3
      2517925.03     13663324.98        2517525.       13663575.
      2517325.02     13663924.96
#Sta/Elev= 30
  4527.4   309.2  4592.9   305.9  4671.9  303.66  4680.7  303.14  4702.6   300.6
  4723.8  299.48  4802.8   297.7  4839.3  297.62  4875.9  295.35  4891.2  295.66
  4904.8  296.76  4933.7  296.27  4954.9  294.57  4963.8   291.4  4969.8  290.14
  4970.3  289.64    4982  289.64  4982.5  290.14  4985.6   291.4  4991.5  291.75
  4996.2  293.51    5002  293.51    5007  294.31  5012.8  298.27  5028.6  300.76
  5168.3  302.36  5321.6  304.87  5344.7  305.69    5367  307.74  5402.2   308.7
#Mann= 3 ,-1 , 0
  4527.4     .05       0  4969.8     .05       0  4982.5     .05       0
Bank Sta=4969.8,4982.5
XS Rating Curve= 0 ,0
Exp/Cntr=0.3,0.1

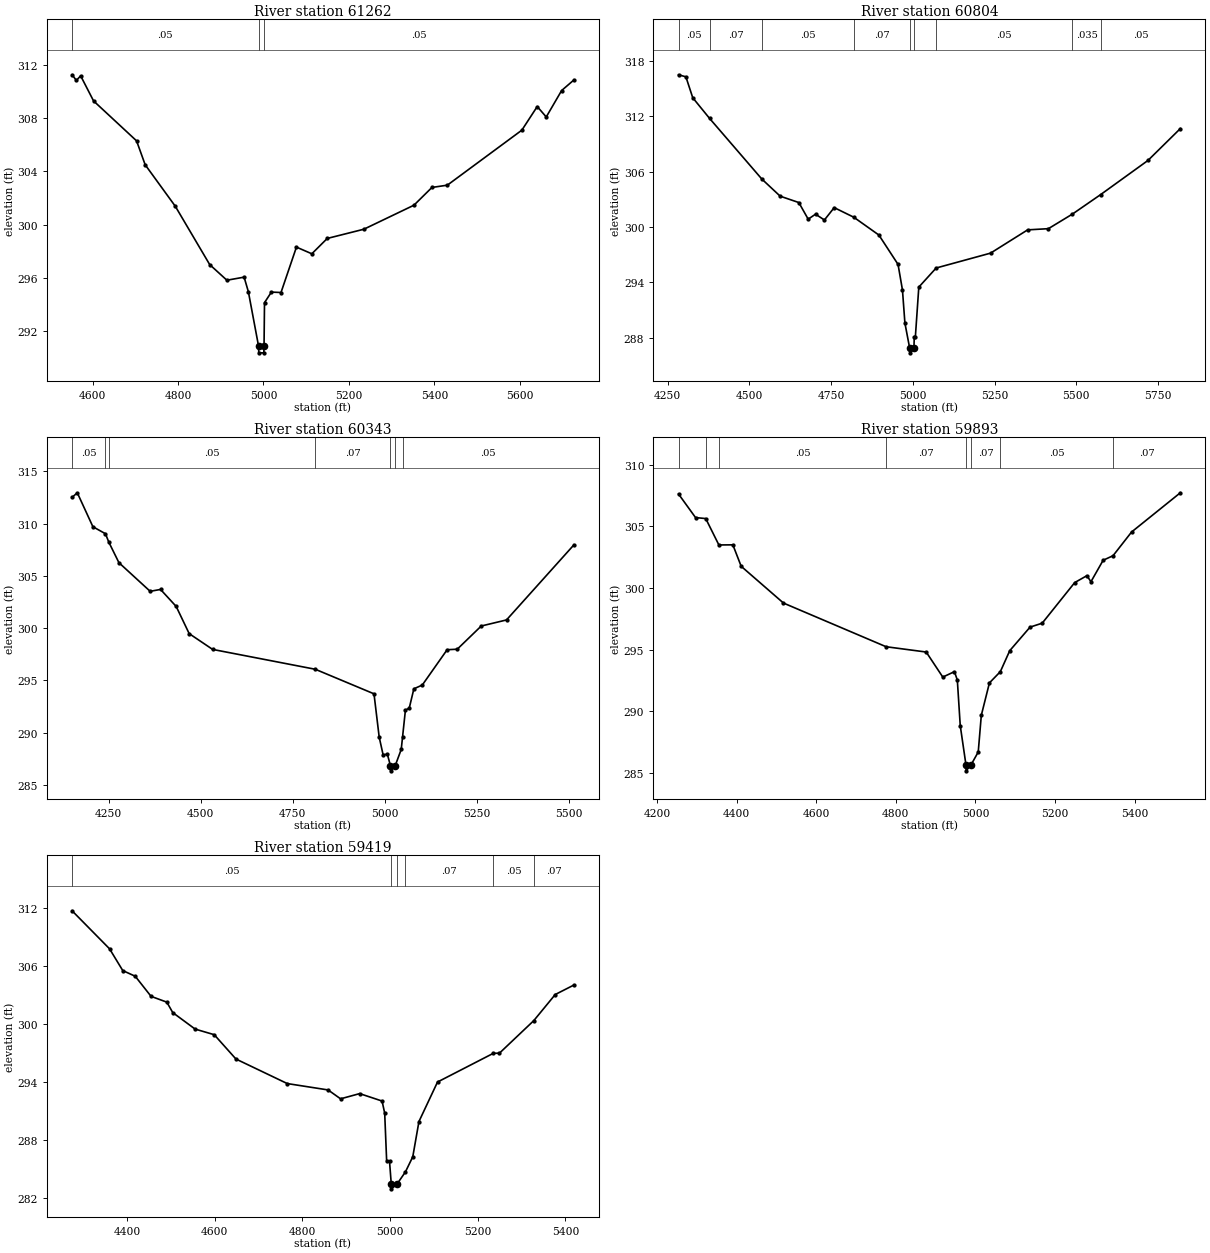
Type RM Length L Ch R = 1 ,61262   ,458,458,458
BEGIN DESCRIPTION:
MCCOY CREEK 83.0
END DESCRIPTION:
XS GIS Cut Line= 3
      2517924.99       13663125.        2517475.       13663175.
      2516874.98     13663575.02
#Sta/Elev= 30
  4552.2  311.23  4562.3  310.81  4572.3  311.15  4602.5  309.27  4703.1  306.28
  4723.2  304.49  4793.7  301.38  4874.2  297.01  4914.4  295.84  4954.7  296.07
  4964.7  294.97  4988.5   290.9    4989   290.4  5000.8   290.4  5001.3   290.9
  5002.4  294.16  5018.5  294.95    5041  294.92  5077.1  298.32  5113.1  297.82
  5149.2  298.97  5234.8  299.66    5352  301.46  5394.1  302.79  5430.1  302.96
  5604.4  307.08  5640.4  308.85  5661.5  308.07  5697.5  310.05  5726.1  310.84
#Mann= 3 ,-1 , 0
  4552.2     .05       0  4988.5     .05       0  5001.3     .05       0
Bank Sta=4988.5,5001.3
XS Rating Curve= 0 ,0
Exp/Cntr=0.3,0.1

Type RM Length L Ch R = 1 ,60804   ,461,461,461
BEGIN DESCRIPTION:
MCCOY CREEK 82.0
END DESCRIPTION:
XS GIS Cut Line= 3
      2517724.98     13662225.03        2517325.       13662825.
      2516775.01     13663424.99
#Sta/Elev= 30
  4283.4   316.5  4305.9  316.28  4326.9  314.01  4378.2  311.78  4538.1  305.21
  4594.3  303.35  4651.4  302.66    4680  300.86  4702.5   301.4  4729.6  300.77
  4759.6  302.11  4819.5  301.07  4896.3  299.14  4954.9  295.96  4968.4  293.19
  4975.9   289.6  4990.5  286.88    4991  286.38  5003.5  286.88  5004.5  288.12
  5007.9  288.12  5018.4   293.5  5071.5  295.57  5237.9  297.18  5351.3   299.7
  5414.8  299.83  5488.3  301.41  5574.6  303.52  5719.4  307.22  5818.4  310.67
#Mann= 9 ,-1 , 0
  4283.4     .05       0  4378.2     .07       0  4538.1     .05       0
  4819.5     .07       0  4990.5     .05       0  5003.5     .07       0
  5071.5     .05       0  5488.3    .035       0  5574.6     .05       0
Bank Sta=4990.5,5003.5
XS Rating Curve= 0 ,0
Exp/Cntr=0.3,0.1

Type RM Length L Ch R = 1 ,60343   ,450,450,450
BEGIN DESCRIPTION:
MCCOY CREEK 81.0
END DESCRIPTION:
XS GIS Cut Line= 3
      2517525.01     13662074.99        2516925.       13662675.
      2516475.03     13662924.99
#Sta/Elev= 30
  4150.6  312.51  4164.8  312.95  4207.2   309.7  4241.3  309.03  4250.5  308.22
  4277.9  306.26  4362.8  303.52    4391   303.7  4433.5  302.07  4468.8  299.47
  4532.5  297.96  4811.4  296.06  4970.9  293.71    4985  289.57  4995.6  287.88
  5007.2  287.93  5015.5  286.84    5016  286.34  5028.6  286.84  5044.9  288.39
  5048.5  289.58  5056.3  292.16  5066.6  292.33  5079.2  294.19  5102.1  294.55
  5169.6  297.93  5197.1  297.98  5262.3   300.2  5330.9  300.78  5513.9  307.96
#Mann= 7 ,-1 , 0
  4150.6     .05       0  4241.3     .07       0  4250.5     .05       0
  4811.4     .07       0  5015.5     .05       0  5028.6     .07       0
  5048.5     .05       0
Bank Sta=5015.5,5028.6
XS Rating Curve= 0 ,0
Exp/Cntr=0.3,0.1

Type RM Length L Ch R = 1 ,59893   ,474,474,474
BEGIN DESCRIPTION:
MCCOY CREEK 80.0
END DESCRIPTION:
XS GIS Cut Line= 3
      2517324.98     13661875.01        2516725.       13662325.
      2516224.98       13662425.
#Sta/Elev= 30
  4254.4  307.61  4297.1   305.7  4322.7  305.62  4355.7  303.48  4390.8  303.49
  4411.7  301.75  4517.9  298.77  4775.6  295.23  4876.3   294.8  4917.9  292.77
  4947.1  293.21  4954.4  292.53  4961.7  288.84    4976  285.67  4976.5  285.17
  4989.1  285.67  5006.9   286.7  5014.6  289.67    5035   292.3  5062.4  293.21
    5086  294.91    5137  296.82  5167.5  297.14  5249.1  300.43  5279.7  300.99
  5289.9   300.5  5320.5  302.24  5345.4  302.61  5391.9  304.53  5514.3  307.71
#Mann= 8 ,-1 , 0
  4254.4     .05       0  4322.7     .07       0  4355.7     .05       0
  4775.6     .07       0    4976     .05       0  4989.1     .07       0
  5062.4     .05       0  5345.4     .07       0
Bank Sta=4976,4989.1
XS Rating Curve= 0 ,0
Exp/Cntr=0.3,0.1

Type RM Length L Ch R = 1 ,59419   ,420,420,420
BEGIN DESCRIPTION:
MCCOY CREEK 79.0
END DESCRIPTION:
XS GIS Cut Line= 3
      2516924.99     13661325.02        2516525.       13661925.
      2516224.97     13662225.03
#Sta/Elev= 30
  4274.1   311.7  4359.7  307.76  4389.8  305.51  4418.3  304.92  4454.4  302.84
  4490.4  302.24  4503.9  301.16    4555  299.45  4598.6  298.87  4648.2  296.35
  4765.3  293.81  4858.5  293.15    4887  292.23  4930.6  292.77  4981.7     292
  4987.7  290.75  4992.2  285.78  4998.7  285.78  5002.7  283.41  5003.2  282.91
    5016  283.41  5035.1  284.67  5051.8  286.23  5065.9  289.88  5108.3  293.97
  5235.6  296.94  5249.7  296.96  5328.1  300.33    5377  303.03  5419.5  304.01
#Mann= 6 ,-1 , 0
  4274.1     .05       0  5002.7     .05       0    5016     .05       0
  5035.1     .07       0  5235.6     .05       0  5328.1     .07       0
Bank Sta=5002.7,5016
XS Rating Curve= 0 ,0
Exp/Cntr=0.3,0.1