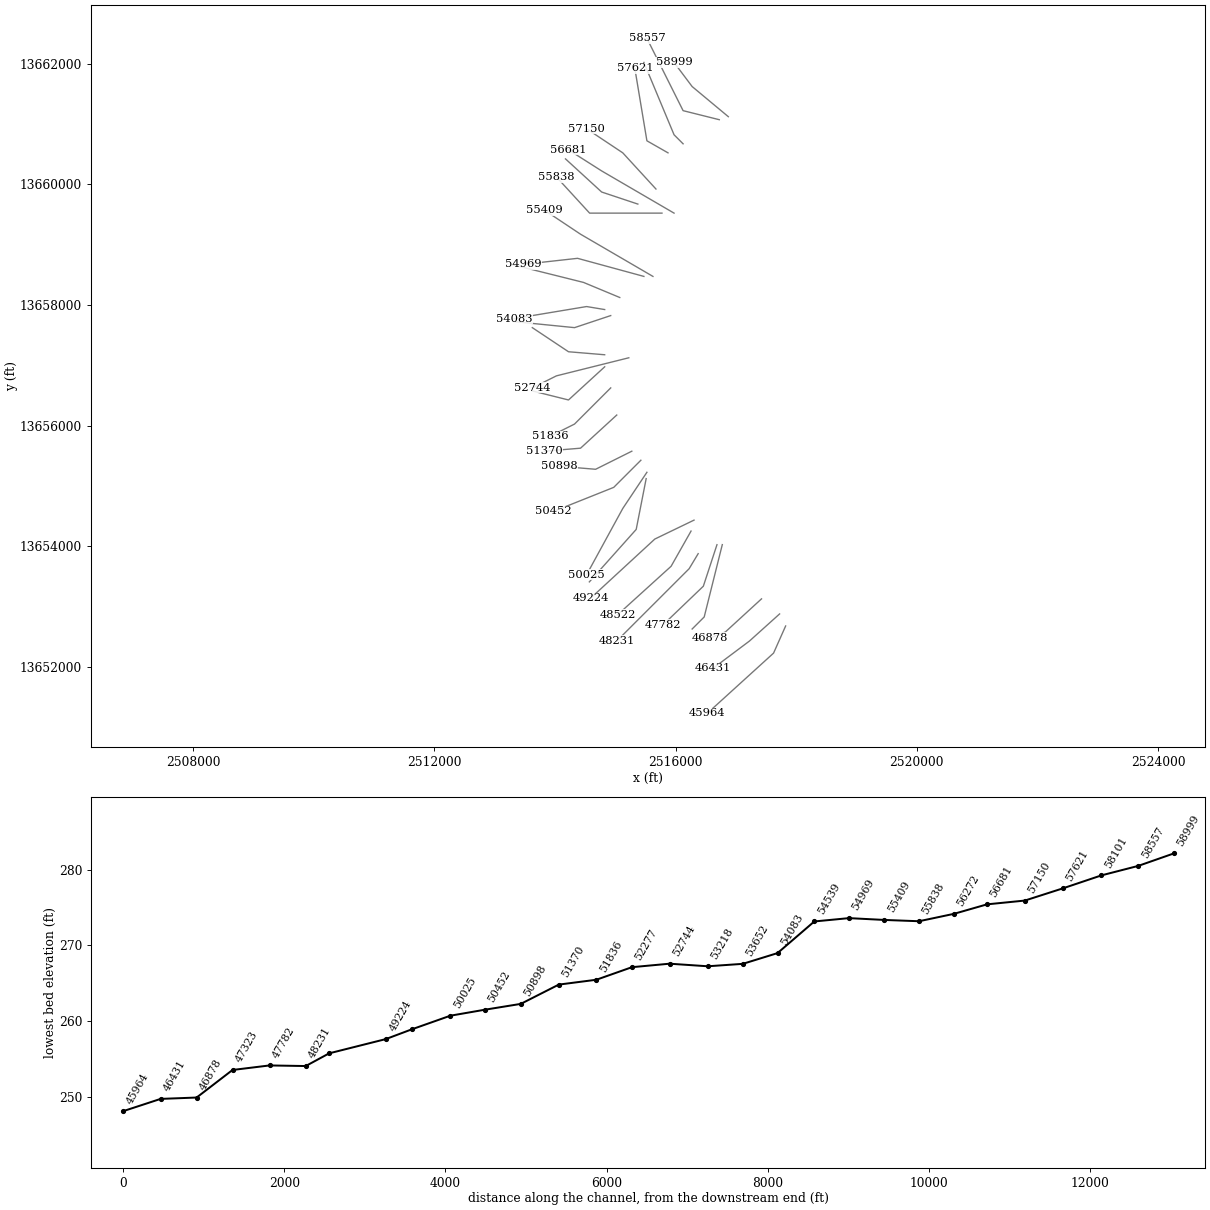
HEC-RAS study MCCOY CREEK.prj: MCCOY CREEK Base Level Engineering

--- MCCOY CREEK.g01 (geometry) --- (continued)

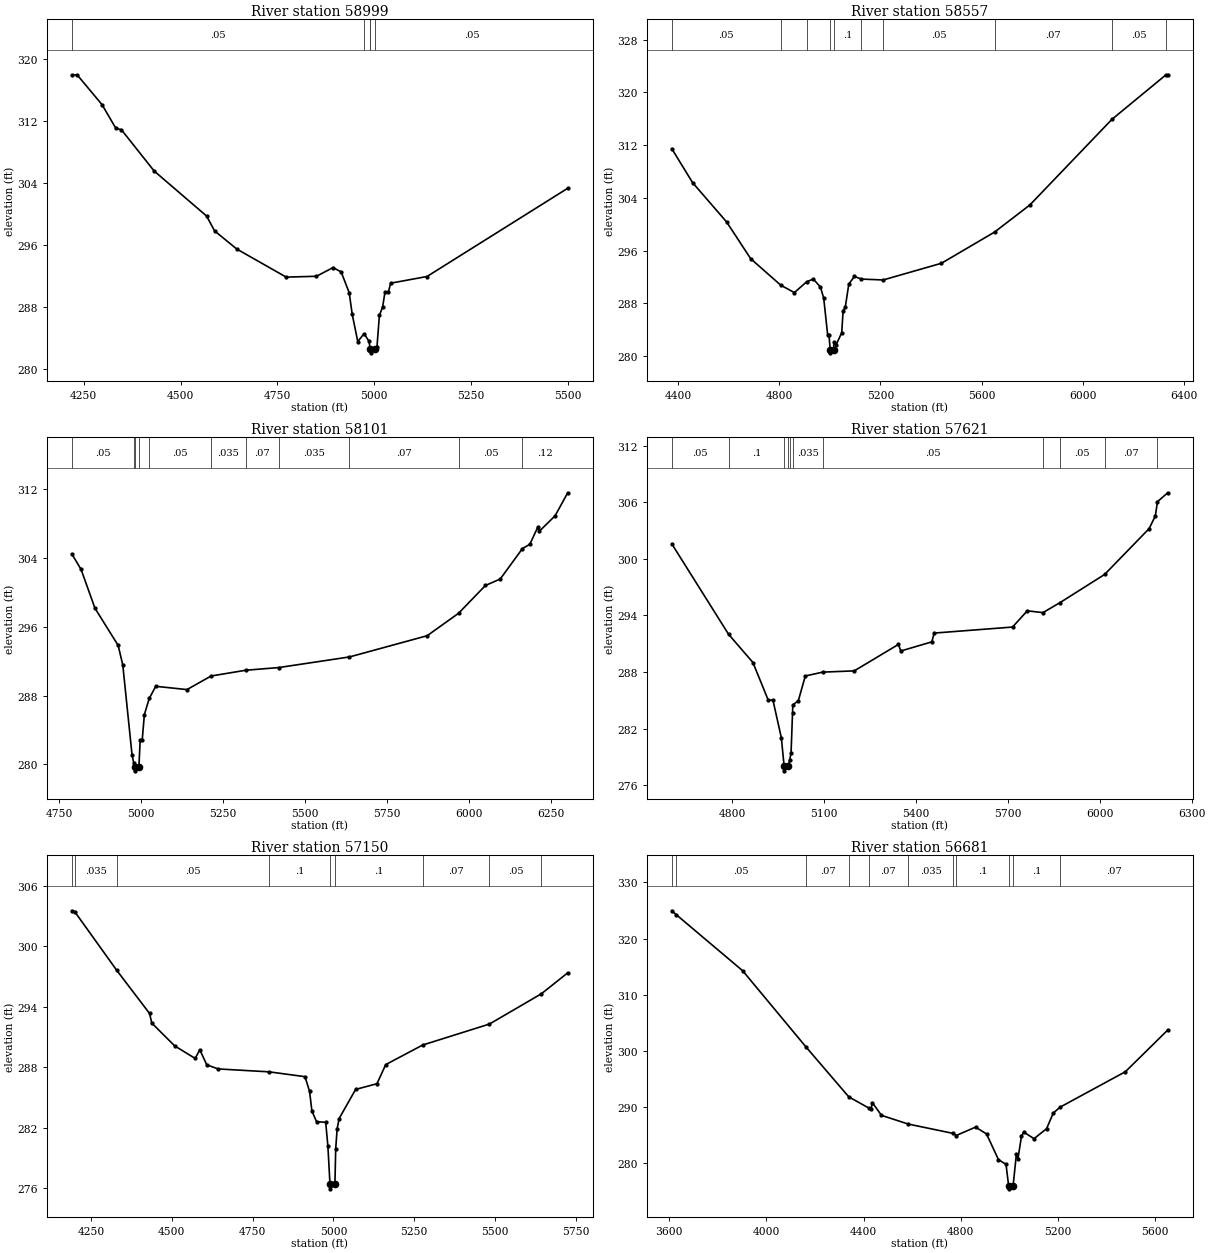
Type RM Length L Ch R = 1 ,58999   ,442,442,442
BEGIN DESCRIPTION:
MCCOY CREEK 78.0
END DESCRIPTION:
XS GIS Cut Line= 3
        2516875.       13661125.        2516275.       13661625.
      2515975.01     13662024.98
#Sta/Elev= 30
    4219  317.86  4232.7  317.91  4297.1  314.07  4332.9  311.02  4347.2  310.84
  4431.8  305.53  4567.2  299.74    4588  297.82  4645.3  295.49  4772.9  291.88
    4851  291.99  4893.9  293.11  4914.8  292.55  4935.6  289.87  4943.4  287.09
  4957.7  283.59    4974  284.61  4986.4  283.65    4990  282.67  4990.1  282.64
  4990.6  282.14  5003.4  282.64  5007.3   282.9  5013.6  286.96  5021.9  288.04
  5028.1  289.98  5036.5  289.93  5042.7   291.1  5136.5  291.96    5500  303.31
#Mann= 5 ,-1 , 0
    4219     .05       0    4974     .07       0    4990     .05       0
  4990.1     .05       0  5003.4     .05       0
Bank Sta=4990.1,5003.4
XS Rating Curve= 0 ,0
Exp/Cntr=0.3,0.1

Type RM Length L Ch R = 1 ,58557   ,456,456,456
BEGIN DESCRIPTION:
MCCOY CREEK 77.0
END DESCRIPTION:
XS GIS Cut Line= 3
      2516724.97     13661075.01        2516125.       13661225.
      2515524.99     13662425.02
#Sta/Elev= 30
  4375.2  311.46  4457.6   306.3  4591.6  300.36    4687  294.77    4806  290.75
  4859.6  289.63  4908.1  291.27  4934.4  291.69  4962.7  290.47  4975.6  288.78
  4991.1  283.23  4996.4  283.23    5001  280.99  5001.5  280.49  5014.3  280.99
    5016  282.13  5024.4  281.69  5046.7  283.54  5052.3  286.89  5060.7  287.38
  5074.7  290.92  5097.1  292.08  5124.1  291.68  5210.7  291.55  5440.8  294.08
  5650.7  298.81  5790.2  302.92  6114.8  315.92  6327.2  322.64  6335.3  322.68
#Mann= 10 ,-1 , 0
  4375.2     .05       0    4806     .07       0  4908.1      .1       0
    5001     .05       0  5014.3      .1       0  5124.1     .07       0
  5210.7     .05       0  5650.7     .07       0  6114.8     .05       0
  6327.2     .07       0
Bank Sta=5001,5014.3
XS Rating Curve= 0 ,0
Exp/Cntr=0.3,0.1

Type RM Length L Ch R = 1 ,58101   ,480,480,480
BEGIN DESCRIPTION:
MCCOY CREEK 76.0
END DESCRIPTION:
XS GIS Cut Line= 3
      2516124.98     13660675.02        2515975.       13660825.
        2515475.       13662025.
#Sta/Elev= 30
  4788.4   304.5  4816.7  302.69  4859.1  298.17  4929.8  293.84  4943.9  291.57
  4972.2  281.08  4977.7   280.1  4979.7  279.74  4980.2  279.24  4993.1  279.74
    4997  282.84  5003.2  282.84  5009.7  285.78  5024.6  287.67  5044.4  289.08
  5139.7   288.7  5213.2  290.28  5318.7  290.95  5418.8  291.26  5635.1   292.5
    5872  294.97  5967.6  297.58  6049.7  300.82  6094.7  301.57  6162.4  305.11
  6185.1  305.62    6209  307.59  6214.4  307.15    6262  308.93  6300.5  311.61
#Mann= 11 ,-1 , 0
  4788.4     .05       0  4977.7     .07       0  4979.7     .05       0
  4993.1     .07       0  5024.6     .05       0  5213.2    .035       0
  5318.7     .07       0  5418.8    .035       0  5635.1     .07       0
  5967.6     .05       0  6162.4     .12       0
Bank Sta=4979.7,4993.1
XS Rating Curve= 0 ,0
Exp/Cntr=0.3,0.1

Type RM Length L Ch R = 1 ,57621   ,471,471,471
BEGIN DESCRIPTION:
MCCOY CREEK 75.0
END DESCRIPTION:
XS GIS Cut Line= 3
      2515874.97     13660525.01        2515525.       13660725.
      2515325.01     13661924.97
#Sta/Elev= 30
  4602.3  301.59  4787.7     292  4867.2  289.01  4916.8  285.05  4932.7     285
    4960  281.03  4969.1  278.02  4969.6  277.52  4982.6  278.02  4987.1  278.69
  4991.7  279.38  4996.5  283.63  4997.5  284.51  5015.5  284.96  5038.3  287.58
  5095.2  287.99    5198  288.12  5342.5  290.93  5350.1  290.23  5451.5   291.2
  5459.1  292.13    5715  292.77  5763.2  294.49  5814.5   294.3  5870.1  295.36
  6015.8  298.35  6161.1  303.21  6181.4  304.56  6188.4  306.07  6221.9  307.01
#Mann= 11 ,-1 , 0
  4602.3     .05       0  4787.7      .1       0  4969.1    .035       0
  4982.6      .1       0  4987.1     .05       0  4996.5    .035       0
  5095.2     .05       0  5814.5     .07       0  5870.1     .05       0
  6015.8     .07       0  6188.4     .12       0
Bank Sta=4969.1,4982.6
XS Rating Curve= 0 ,0
Exp/Cntr=0.3,0.1

Type RM Length L Ch R = 1 ,57150   ,469,469,469
BEGIN DESCRIPTION:
MCCOY CREEK 74.0
END DESCRIPTION:
XS GIS Cut Line= 3
        2515675.       13659925.        2515125.       13660525.
      2514525.04     13660924.97
#Sta/Elev= 30
  4190.3  303.55  4199.2  303.47  4329.5  297.63  4431.1  293.34  4437.9  292.39
  4508.8  290.12  4572.3  288.87  4586.5  289.74  4608.1  288.24  4643.2  287.83
    4801  287.54  4912.1  287.06  4926.2  285.61  4933.6  283.64  4947.8  282.59
  4976.2  282.52    4983  280.17  4989.4  276.41  4989.9  275.91  5004.8  276.41
  5007.2   279.9  5011.7   281.9  5017.8   282.9  5068.8  285.79  5134.9  286.36
    5162  288.26    5276   290.2    5483  292.29  5643.8   295.3  5725.3  297.38
#Mann= 9 ,-1 , 0
  4190.3     .05       0  4199.2    .035       0  4329.5     .05       0
    4801      .1       0  4989.4     .05       0  5004.8      .1       0
    5276     .07       0    5483     .05       0  5643.8     .07       0
Bank Sta=4989.4,5004.8
XS Rating Curve= 0 ,0
Exp/Cntr=0.3,0.1

Type RM Length L Ch R = 1 ,56681   ,409,409,409
BEGIN DESCRIPTION:
MCCOY CREEK 73.0
END DESCRIPTION:
XS GIS Cut Line= 3
      2515975.02     13659524.99        2514775.       13660225.
      2514224.99       13660575.
#Sta/Elev= 30
  3610.7  324.96  3628.3  324.29  3902.2  314.28  4163.6  300.66  4339.3  291.79
  4420.7  289.83  4430.6   289.6  4436.4  290.75  4473.6  288.51  4583.2  286.96
  4769.7  285.28    4781  284.91    4861  286.41  4906.1  285.19  4954.9  280.63
  4986.3  279.76  4997.1  275.92  4999.9  275.91  5000.4  275.41  5015.3  275.91
  5028.8  281.53  5035.5   280.8  5049.9  284.79  5059.2  285.52  5101.6  284.35
  5153.2  286.13  5180.3  288.88  5208.1  289.95  5477.5  296.28  5651.9  303.71
#Mann= 11 ,-1 , 0
  3610.7     .07       0  3628.3     .05       0  4163.6     .07       0
  4339.3     .05       0  4420.7     .07       0  4583.2    .035       0
  4769.7     .05       0    4781      .1       0  4999.9     .05       0
  5015.3      .1       0  5208.1     .07       0
Bank Sta=4999.9,5015.3
XS Rating Curve= 0 ,0
Exp/Cntr=0.3,0.1

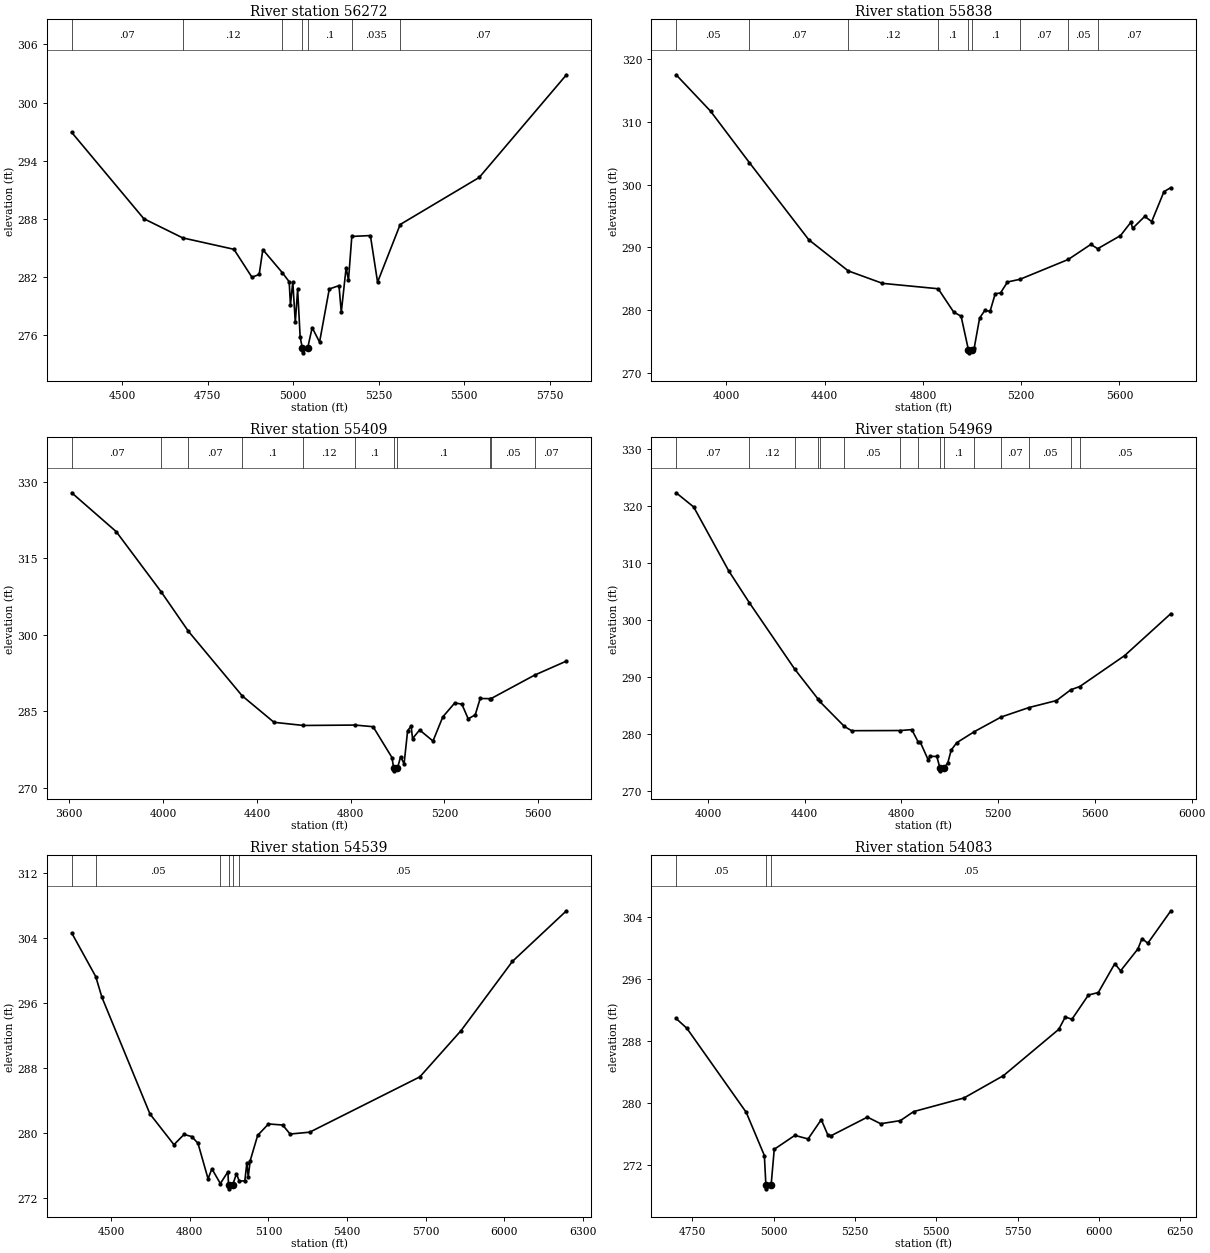
Type RM Length L Ch R = 1 ,56272   ,434,434,434
BEGIN DESCRIPTION:
MCCOY CREEK 72.0
END DESCRIPTION:
XS GIS Cut Line= 3
      2515374.98     13659675.01        2514775.       13659875.
      2514174.98     13660425.01
#Sta/Elev= 30
  4352.9  296.92  4563.7  288.01  4677.3  286.03  4827.2  284.85  4879.9  281.96
    4901  282.26  4911.6  284.82  4968.3  282.45  4988.7   281.5  4992.4  279.11
  4999.2  281.49  5006.6   277.3  5013.4  280.71  5020.8  275.78  5027.2  274.66
  5027.7  274.16  5042.7  274.66  5055.9  276.76  5077.5  275.27  5105.9  280.75
  5134.3   281.1    5141  278.35  5155.2  282.96    5162  281.65  5171.8  286.18
  5226.1  286.27  5247.1  281.46  5313.2  287.41  5544.3  292.27  5799.3  302.87
#Mann= 7 ,-1 , 0
  4352.9     .07       0  4677.3     .12       0  4968.3      .1       0
  5027.2     .05       0  5042.7      .1       0  5171.8    .035       0
  5313.2     .07       0
Bank Sta=5027.2,5042.7
XS Rating Curve= 0 ,0
Exp/Cntr=0.3,0.1

Type RM Length L Ch R = 1 ,55838   ,429,429,429
BEGIN DESCRIPTION:
MCCOY CREEK 71.0
END DESCRIPTION:
XS GIS Cut Line= 3
      2515774.97       13659525.        2514575.       13659525.
      2514025.01     13660124.99
#Sta/Elev= 30
  3795.3  317.56  3935.3  311.76  4093.9  303.52  4335.3  291.23  4495.9  286.26
  4635.3  284.27    4862  283.41  4925.3  279.68  4955.3  279.03    4985  273.68
  4985.5  273.18  5000.6  273.68  5009.1  274.03  5030.7  278.73  5051.7  279.94
  5073.3  279.81  5094.2  282.61  5115.8  282.74  5144.2  284.49  5195.2  284.92
  5391.4  288.08  5483.6  290.49  5511.3   289.8  5604.2  291.89  5646.4  294.02
  5653.5  293.05  5702.8  294.95  5731.2  294.13  5781.2  298.91  5809.2  299.55
#Mann= 9 ,-1 , 0
  3795.3     .05       0  4093.9     .07       0  4495.9     .12       0
    4862      .1       0    4985     .05       0  5000.6      .1       0
  5195.2     .07       0  5391.4     .05       0  5511.3     .07       0
Bank Sta=4985,5000.6
XS Rating Curve= 0 ,0
Exp/Cntr=0.3,0.1

Type RM Length L Ch R = 1 ,55409   ,440,440,440
BEGIN DESCRIPTION:
MCCOY CREEK 70.0
END DESCRIPTION:
XS GIS Cut Line= 3
      2515624.99       13658475.        2514425.       13659175.
      2513825.04     13659574.97
#Sta/Elev= 30
  3610.3  327.84  3800.1  320.23  3991.9  308.43  4107.7  300.72  4337.6  288.04
  4473.2  282.86  4598.9  282.24  4819.2  282.32  4895.8     282  4976.4  275.95
  4983.7  273.85  4984.2  273.35  4999.6  273.85  5013.1   276.1  5028.1  274.73
  5043.1  281.21  5058.1  282.12  5064.1  279.67  5094.2  281.36  5151.3  279.19
  5193.3  283.93  5244.4  286.66  5274.5  286.42  5301.5  283.54  5331.5  284.32
  5352.6  287.53  5396.1  287.49  5397.1  287.46  5584.9  292.11  5720.6  294.86
#Mann= 11 ,-1 , 0
  3610.3     .07       0  3991.9     .12       0  4107.7     .07       0
  4337.6      .1       0  4598.9     .12       0  4819.2      .1       0
  4983.7     .05       0  4999.6      .1       0  5396.1     .07       0
  5397.1     .05       0  5584.9     .07       0
Bank Sta=4983.7,4999.6
XS Rating Curve= 0 ,0
Exp/Cntr=0.3,0.1

Type RM Length L Ch R = 1 ,54969   ,430,430,430
BEGIN DESCRIPTION:
MCCOY CREEK 69.0
END DESCRIPTION:
XS GIS Cut Line= 3
      2515475.04     13658474.99        2514375.       13658775.
      2513474.96       13658675.
#Sta/Elev= 30
  3868.2  322.36  3940.8  319.87  4085.9  308.65  4170.5  303.11  4358.6  291.43
  4456.1  286.13  4461.4  285.78  4564.2  281.37  4593.8  280.63  4795.3  280.66
  4842.6  280.82  4869.6  278.62  4877.1  278.68  4911.7  275.41  4916.9  276.14
  4946.2  276.11    4959  274.09  4959.5  273.59    4975  274.09  4991.1  274.92
  5005.8  277.24  5028.5  278.52    5102  280.48  5212.4  283.03  5326.3  284.68
  5441.1  285.92  5500.3  287.81  5537.5  288.38  5722.8   293.8    5914  301.17
#Mann= 15 ,-1 , 0
  3868.2     .07       0  4170.5     .12       0  4358.6     .07       0
  4456.1     .12       0  4461.4     .07       0  4564.2     .05       0
  4795.3     .12       0  4869.6      .1       0    4959     .05       0
    4975      .1       0    5102     .05       0  5212.4     .07       0
  5326.3     .05       0  5500.3     .07       0  5537.5     .05       0
Bank Sta=4959,4975
XS Rating Curve= 0 ,0
Exp/Cntr=0.3,0.1

Type RM Length L Ch R = 1 ,54539   ,456,456,456
BEGIN DESCRIPTION:
MCCOY CREEK 68.0
END DESCRIPTION:
XS GIS Cut Line= 3
      2515074.97     13658125.01        2514475.       13658375.
        2513275.       13658675.
#Sta/Elev= 30
  4349.5  304.62  4441.1  299.26  4464.8   296.7  4647.9  282.36  4739.5  278.58
  4777.9  279.84  4807.2  279.58    4831  278.76  4869.5  274.39  4884.1  275.61
  4916.4   273.8  4945.3  275.25  4947.5  273.65    4948  273.15  4963.6  273.65
  4977.8  275.01  4988.2  274.12  5009.8  274.12  5017.5  276.36  5022.7  274.63
  5030.4  276.63  5058.7  279.73    5100  281.13  5154.1     281  5182.4  279.89
  5257.2  280.12  5677.2  286.92  5834.4  292.61  6030.2  301.12  6236.4  307.35
#Mann= 6 ,-1 , 0
  4349.5     .07       0  4441.1     .05       0  4916.4      .1       0
  4947.5     .05       0  4963.6      .1       0  4988.2     .05       0
Bank Sta=4947.5,4963.6
XS Rating Curve= 0 ,0
Exp/Cntr=0.3,0.1

Type RM Length L Ch R = 1 ,54083   ,431,431,431
BEGIN DESCRIPTION:
MCCOY CREEK 67.0
END DESCRIPTION:
XS GIS Cut Line= 3
      2514825.04     13657924.99        2514525.       13657975.
      2513325.03     13657775.01
#Sta/Elev= 30
  4700.1  290.89  4733.1  289.63  4915.6  278.81  4971.3  273.26    4976  269.47
  4976.5  268.97  4992.1  269.47  5001.7  274.06  5065.1  275.85  5105.7  275.39
  5146.2  277.87  5166.5   275.9  5176.6  275.81  5288.1   278.2  5328.7  277.35
  5389.5  277.75  5430.1  278.91  5584.7  280.66  5706.3  283.54  5876.1  289.49
  5896.4  291.09  5916.7  290.79  5967.4  293.91  5997.8  294.23  6048.5  297.95
  6066.2  297.02  6119.5  299.84  6132.1  301.18  6149.9  300.57  6220.8  304.75
#Mann= 3 ,-1 , 0
  4700.1     .05       0    4976     .05       0  4992.1     .05       0
Bank Sta=4976,4992.1
XS Rating Curve= 0 ,0
Exp/Cntr=0.3,0.1

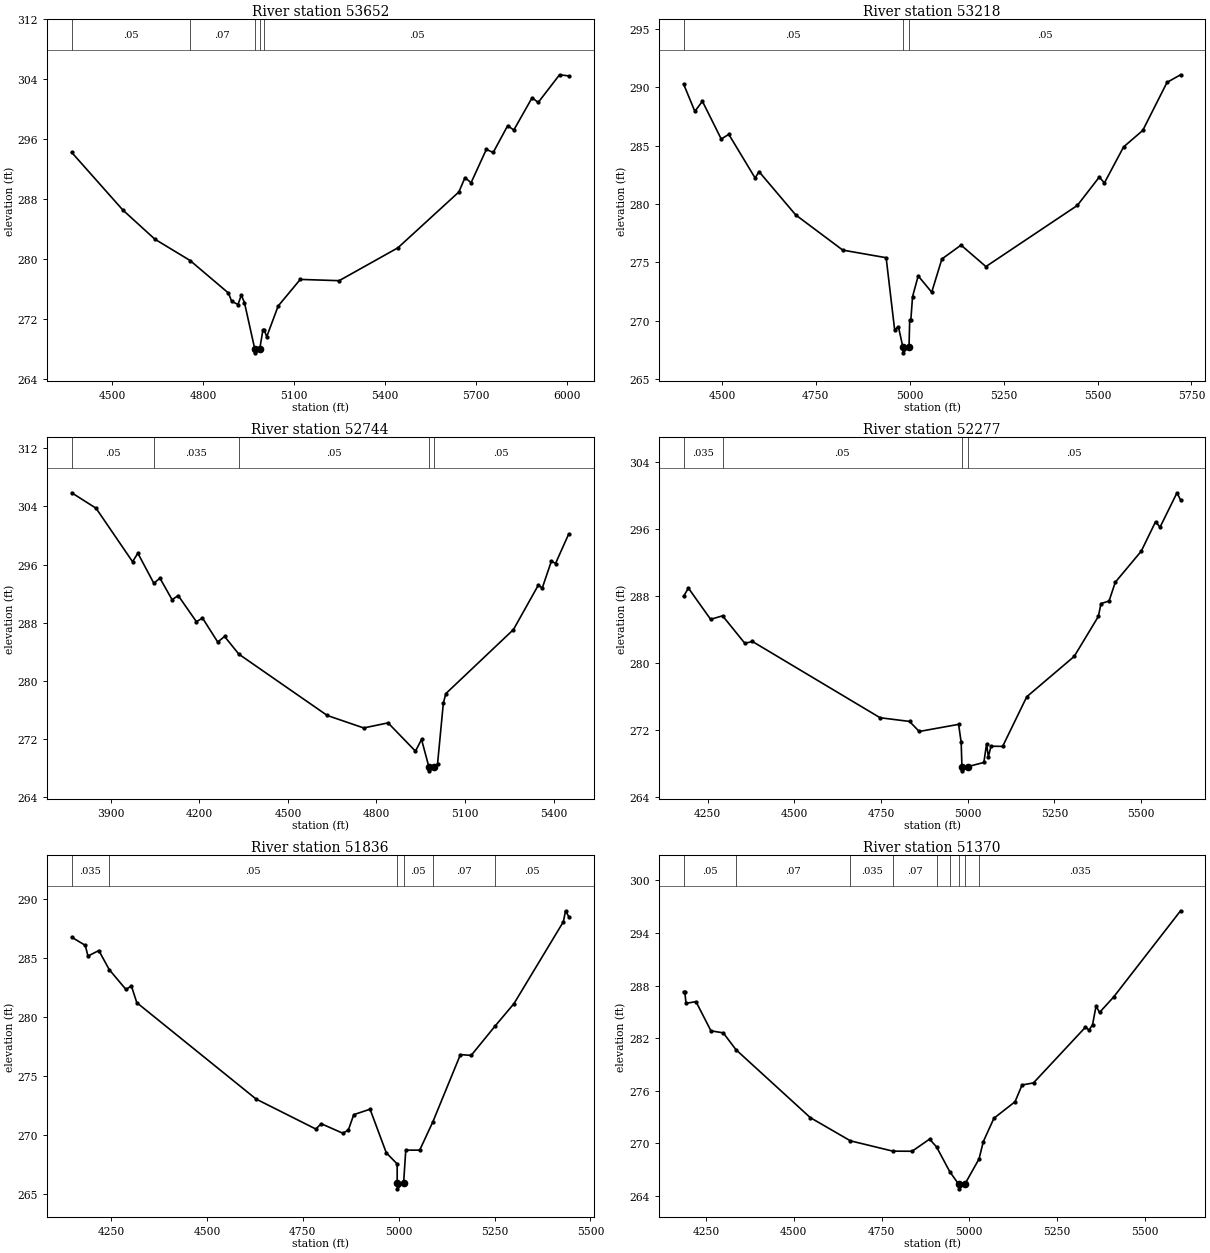
Type RM Length L Ch R = 1 ,53652   ,434,434,434
BEGIN DESCRIPTION:
MCCOY CREEK 66.0
END DESCRIPTION:
XS GIS Cut Line= 3
      2514925.01       13657825.        2514325.       13657625.
      2513324.96       13657725.
#Sta/Elev= 30
  4367.2  294.27  4535.9  286.58  4641.3   282.7  4757.2  279.86  4883.7  275.52
  4894.3  274.42  4915.3  273.99  4925.9  275.25  4936.4  274.24  4970.4  268.05
  4970.9  267.55  4986.7  268.05    4997  270.56  5001.8  270.56  5009.7  269.69
  5047.4  273.79  5120.3  277.34  5248.4  277.17  5441.9  281.55  5642.9     289
    5663  290.91  5683.1  290.23  5733.3  294.67  5755.9  294.26  5803.7  297.84
  5823.8  297.25  5884.1  301.56  5904.2  300.93  5974.5  304.62  6004.7  304.47
#Mann= 5 ,-1 , 0
  4367.2     .05       0  4757.2     .07       0  4970.4     .05       0
  4986.7     .07       0  5001.8     .05       0
Bank Sta=4970.4,4986.7
XS Rating Curve= 0 ,0
Exp/Cntr=0.3,0.1

Type RM Length L Ch R = 1 ,53218   ,474,474,474
BEGIN DESCRIPTION:
MCCOY CREEK 65.0
END DESCRIPTION:
XS GIS Cut Line= 3
      2514824.96       13657175.        2514225.       13657225.
      2513625.04     13657624.97
#Sta/Elev= 30
    4398  290.29  4428.1  287.94  4448.1  288.81  4498.3  285.57  4518.4  285.97
  4588.6  282.22  4598.7  282.78  4696.5  279.06  4821.9  276.04  4937.3  275.39
  4959.9  269.21  4969.9  269.48  4981.8  267.73  4982.3  267.23  4998.2  267.73
    5000  270.03    5003  270.03  5007.6  272.05  5022.6  273.83  5058.6  272.43
  5085.7  275.28  5136.7  276.47  5202.9  274.63  5446.2  279.87  5504.8  282.31
  5518.3   281.8  5569.4  284.89  5620.5  286.31  5685.1  290.43  5721.1  291.08
#Mann= 3 ,-1 , 0
    4398     .05       0  4981.8     .05       0  4998.2     .05       0
Bank Sta=4981.8,4998.2
XS Rating Curve= 0 ,0
Exp/Cntr=0.3,0.1

Type RM Length L Ch R = 1 ,52744   ,467,467,467
BEGIN DESCRIPTION:
MCCOY CREEK 64.0
END DESCRIPTION:
XS GIS Cut Line= 3
        2515225.       13657125.        2514025.       13656825.
      2513625.04     13656625.02
#Sta/Elev= 30
  3767.2  305.89  3849.7  303.76  3973.4  296.39  3991.4  297.56  4045.6  293.41
  4066.1  294.13  4107.4  291.15    4128  291.73  4189.8  288.12  4210.4  288.63
    4262  285.32  4285.2  286.09  4333.6  283.65  4633.1   275.2  4756.7  273.48
  4839.2  274.18    4932  270.28  4952.6   271.9  4977.8  268.07  4978.3  267.57
  4994.3  268.07  5006.9  268.55  5026.5   276.9  5034.9  278.21  5264.1  287.04
  5347.9  293.13  5361.9  292.79  5392.6  296.47  5406.6  296.14  5451.3  300.21
#Mann= 5 ,-1 , 0
  3767.2     .05       0  4045.6    .035       0  4333.6     .05       0
  4977.8     .05       0  4994.3     .05       0
Bank Sta=4977.8,4994.3
XS Rating Curve= 0 ,0
Exp/Cntr=0.3,0.1

Type RM Length L Ch R = 1 ,52277   ,441,441,441
BEGIN DESCRIPTION:
MCCOY CREEK 63.0
END DESCRIPTION:
XS GIS Cut Line= 3
      2514825.03     13656975.03        2514225.       13656425.
      2513625.05     13656574.99
#Sta/Elev= 30
    4181  287.94  4194.9  288.93    4259   285.2  4293.5  285.62  4357.7  282.33
  4379.3  282.56  4747.4  273.45  4832.2  273.01  4860.2  271.81  4973.7  272.66
  4981.1  270.51  4983.3  267.61  4983.8  267.11  4999.8  267.61  5046.5  268.11
  5054.3  270.33  5059.4  268.78  5067.1  270.05  5100.6  270.03  5170.2  275.96
  5306.8  280.77  5376.4  285.54  5384.1  287.08  5407.3  287.39  5425.3  289.63
  5500.1  293.34  5541.3  296.85  5554.2   296.2  5603.1  300.31  5613.4  299.45
#Mann= 4 ,-1 , 0
    4181    .035       0  4293.5     .05       0  4983.3     .05       0
  4999.8     .05       0
Bank Sta=4983.3,4999.8
XS Rating Curve= 0 ,0
Exp/Cntr=0.3,0.1

Type RM Length L Ch R = 1 ,51836   ,466,466,466
BEGIN DESCRIPTION:
MCCOY CREEK 62.0
END DESCRIPTION:
XS GIS Cut Line= 3
        2514925.       13656625.        2514325.       13656025.
      2513925.03     13655825.02
#Sta/Elev= 30
  4147.6  286.78    4183  286.09    4190  285.18  4218.3  285.65  4245.3  284.04
    4289  282.35  4303.2  282.65  4317.3  281.23  4628.4  273.06    4784  270.52
  4798.1  270.97  4854.7  270.16  4868.8  270.44    4883  271.74  4925.4   272.2
  4967.8   268.5  4996.1  267.56  4996.2  265.95  4996.7  265.45  5012.9  265.95
  5018.5  268.73  5054.8  268.73    5089  271.12    5161  276.83    5189  276.76
  5250.9  279.23  5300.8  281.16  5429.4  288.09    5435  289.02  5443.3  288.53
#Mann= 6 ,-1 , 0
  4147.6    .035       0  4245.3     .05       0  4996.2     .05       0
  5012.9     .05       0    5089     .07       0  5250.9     .05       0
Bank Sta=4996.2,5012.9
XS Rating Curve= 0 ,0
Exp/Cntr=0.3,0.1

Type RM Length L Ch R = 1 ,51370   ,472,472,472
BEGIN DESCRIPTION:
MCCOY CREEK 61.0
END DESCRIPTION:
XS GIS Cut Line= 3
      2515024.98     13656174.98        2514425.       13655625.
      2513824.99       13655575.
#Sta/Elev= 30
  4185.8  287.31  4189.2  287.31  4192.9  285.98  4221.2  286.17  4263.8  282.84
  4298.9  282.61  4335.3  280.68  4546.8  272.94  4661.1  270.29  4782.2  269.11
  4836.9   269.1  4886.6  270.48  4906.5   269.6  4944.5  266.75  4970.1  265.31
  4970.6  264.81  4986.8  265.31  5027.7  268.23  5039.8   270.2    5070  272.86
  5130.2  274.75  5150.2  276.66  5182.8   276.9  5330.9  283.26  5340.9  282.93
  5350.9  283.52    5361  285.66    5371  284.94  5411.1   286.7  5601.8  296.54
#Mann= 9 ,-1 , 0
  4185.8     .05       0  4335.3     .07       0  4661.1    .035       0
  4782.2     .07       0  4906.5    .035       0  4944.5     .07       0
  4970.1     .05       0  4986.8     .07       0  5027.7    .035       0
Bank Sta=4970.1,4986.8
XS Rating Curve= 0 ,0
Exp/Cntr=0.3,0.1

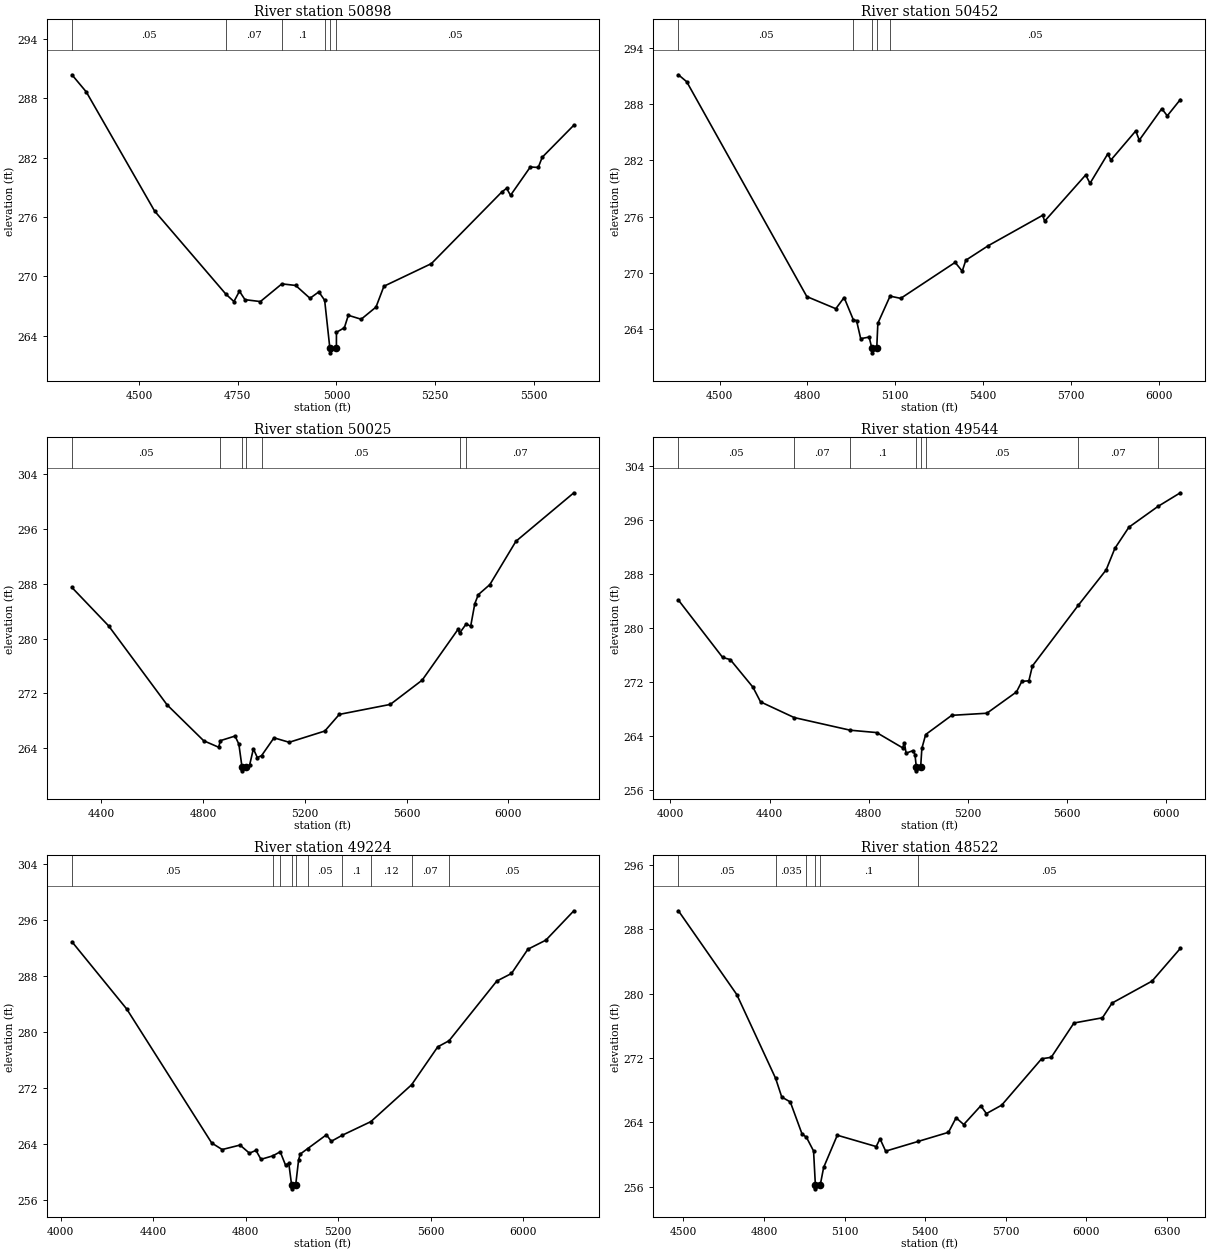
Type RM Length L Ch R = 1 ,50898   ,446,446,446
BEGIN DESCRIPTION:
MCCOY CREEK 60.0
END DESCRIPTION:
XS GIS Cut Line= 3
      2515274.97     13655574.98        2514675.       13655275.
      2514074.96       13655325.
#Sta/Elev= 30
  4329.2   290.4  4365.5  288.67  4538.8  276.61  4719.6   268.2    4740  267.45
    4754   268.5    4768  267.64  4807.1  267.45  4861.6  269.24  4896.6  269.08
  4932.9  267.78  4955.3  268.43  4970.1  267.58  4983.2  262.76  4983.7  262.26
  4999.9  262.76    5000  264.34  5020.1   264.8  5030.1  266.06  5062.7  265.66
  5100.3  266.89  5120.4     269  5240.8  271.29  5418.9  278.52  5431.5  278.91
  5441.5   278.2  5491.7  281.07  5511.8  281.02  5521.8  282.05  5602.1   285.3
#Mann= 6 ,-1 , 0
  4329.2     .05       0  4719.6     .07       0  4861.6      .1       0
  4970.1     .05       0  4983.2     .05       0  4999.9     .05       0
Bank Sta=4983.2,4999.9
XS Rating Curve= 0 ,0
Exp/Cntr=0.3,0.1

Type RM Length L Ch R = 1 ,50452   ,427,427,427
BEGIN DESCRIPTION:
MCCOY CREEK 59.0
END DESCRIPTION:
XS GIS Cut Line= 3
      2515425.02     13655425.02        2514975.       13654975.
      2513974.97     13654574.99
#Sta/Elev= 30
  4359.4   291.1  4387.7  290.36  4797.8  267.48  4896.8  266.19  4925.1  267.38
  4956.8  264.99  4967.5  264.93  4981.7     263  5010.6  263.17  5019.7  261.99
  5020.2  261.49  5036.5  261.99  5040.3  264.64    5082  267.53  5118.3  267.29
  5304.1  271.12  5328.4  270.19  5340.5  271.35  5417.2   272.9    5603  276.14
  5609.7  275.51  5749.8  280.43  5764.6  279.54  5825.1  282.67  5835.9  282.02
  5920.7  285.12  5932.8  284.14  6009.6  287.49  6028.4  286.73  6072.9  288.46
#Mann= 5 ,-1 , 0
  4359.4     .05       0  4956.8     .07       0  5019.7     .05       0
  5036.5     .07       0    5082     .05       0
Bank Sta=5019.7,5036.5
XS Rating Curve= 0 ,0
Exp/Cntr=0.3,0.1

Type RM Length L Ch R = 1 ,50025   ,481,481,481
BEGIN DESCRIPTION:
MCCOY CREEK 58.0
END DESCRIPTION:
XS GIS Cut Line= 3
      2515525.01     13655225.01        2515125.       13654625.
      2514525.01     13653525.02
#Sta/Elev= 30
    4284  287.47  4428.2  281.87  4658.1  270.34  4802.3  265.09  4860.9  264.15
  4868.1  265.11  4925.5  265.78  4940.5   264.6  4953.1   261.2  4953.6   260.7
  4970.1   261.2  4982.6  261.51  4997.6  263.91  5013.2  262.63    5030  262.93
  5078.7  265.52  5138.5  264.87  5278.5  266.51  5335.5  268.94  5536.2   270.4
  5661.5  273.94  5802.5  281.36  5808.5   280.8  5834.7  282.15  5852.3  281.82
  5868.5   285.1  5882.2  286.42  5927.8   287.9  6030.3  294.22  6258.1   301.3
#Mann= 7 ,-1 , 0
    4284     .05       0  4868.1      .1       0  4953.1     .05       0
  4970.1      .1       0    5030     .05       0  5808.5    .035       0
  5834.7     .07       0
Bank Sta=4953.1,4970.1
XS Rating Curve= 0 ,0
Exp/Cntr=0.3,0.1

Type RM Length L Ch R = 1 ,49544   ,320,320,320
BEGIN DESCRIPTION:
B19364
END DESCRIPTION:
XS GIS Cut Line= 3
      2515512.87     13655120.25      2515347.56     13654277.14
      2514570.64     13653406.56
#Sta/Elev= 30
    4032  284.15  4210.6  275.66  4241.2  275.35  4332.9  271.26  4363.6  269.09
  4499.4  266.77  4725.5   264.9  4832.2  264.55  4936.7   262.3  4944.3  263.03
    4951   261.5  4979.4  261.89  4986.9   261.3  4992.5  259.39    4993  258.89
  5009.7  259.39  5014.7  262.21  5030.1  264.26  5135.3   267.1    5277  267.41
  5396.6  270.56  5418.3  272.12  5446.7  272.21  5460.9   274.4  5646.6   283.4
  5758.6  288.61  5793.7  291.79  5850.5  294.93  5967.7     298    6058  300.02
#Mann= 8 ,-1 , 0
    4032     .05       0  4499.4     .07       0  4725.5      .1       0
  4992.5     .05       0  5009.7      .1       0  5030.1     .05       0
  5646.6     .07       0  5967.7     .05       0
Bank Sta=4992.5,5009.7
XS Rating Curve= 0 ,0
Exp/Cntr=0.3,0.1

Type RM Length L Ch R = 1 ,49224   ,702,702,702
BEGIN DESCRIPTION:
MCCOY CREEK 57.0
END DESCRIPTION:
XS GIS Cut Line= 3
      2516306.36     13654431.44      2515656.13     13654117.35
      2514592.68     13653136.55
#Sta/Elev= 30
  4049.3  292.95    4286  283.33  4653.2  264.17  4698.4  263.23  4775.6  263.87
  4816.2  262.71  4844.5  263.11  4866.1  261.83  4917.4  262.33  4949.3  262.91
  4972.1  261.01  4986.3  261.25  4998.7  258.11  4999.2  257.61  5015.9  258.11
  5028.8  261.77  5035.6  262.58  5067.3  263.35    5149  265.34    5170  264.41
  5217.1  265.27  5340.7  267.22  5516.9  272.49    5630  277.92  5678.8  278.79
  5885.1  287.33  5948.6  288.41  6019.5  291.88  6097.2  293.18  6218.1  297.38
#Mann= 10 ,-1 , 0
  4049.3     .05       0  4917.4      .1       0  4949.3    .035       0
  4998.7    .035       0  5015.9    .035       0  5067.3     .05       0
  5217.1      .1       0  5340.7     .12       0  5516.9     .07       0
  5678.8     .05       0
Bank Sta=4998.7,5015.9
XS Rating Curve= 0 ,0
Exp/Cntr=0.3,0.1

Type RM Length L Ch R = 1 ,48522   ,291,291,291
BEGIN DESCRIPTION:
B19362
END DESCRIPTION:
XS GIS Cut Line= 3
      2516256.73     13654249.56      2515926.13      13653665.5
      2515039.53      13652861.5
#Sta/Elev= 30
  4481.6  290.32  4698.8   279.9  4843.3  269.48  4866.2  267.15    4898  266.54
  4941.3  262.59  4958.3  262.13  4984.6  260.44  4991.3  256.23  4991.8  255.73
  5009.6  256.23  5022.1  258.39  5072.9   262.4  5217.7  260.99  5231.9  261.96
  5252.9  260.42    5373  261.62  5486.7  262.76  5515.1  264.57  5543.5  263.73
    5607  266.06  5627.9  265.09  5684.7  266.14  5833.4  271.91  5869.2  272.09
  5953.7  276.36  6059.8  277.01  6095.6  278.84  6244.3  281.57  6349.6  285.64
#Mann= 6 ,-1 , 0
  4481.6     .05       0  4843.3    .035       0  4958.3      .1       0
  4991.3     .05       0  5009.6      .1       0    5373     .05       0
Bank Sta=4991.3,5009.6
XS Rating Curve= 0 ,0
Exp/Cntr=0.3,0.1

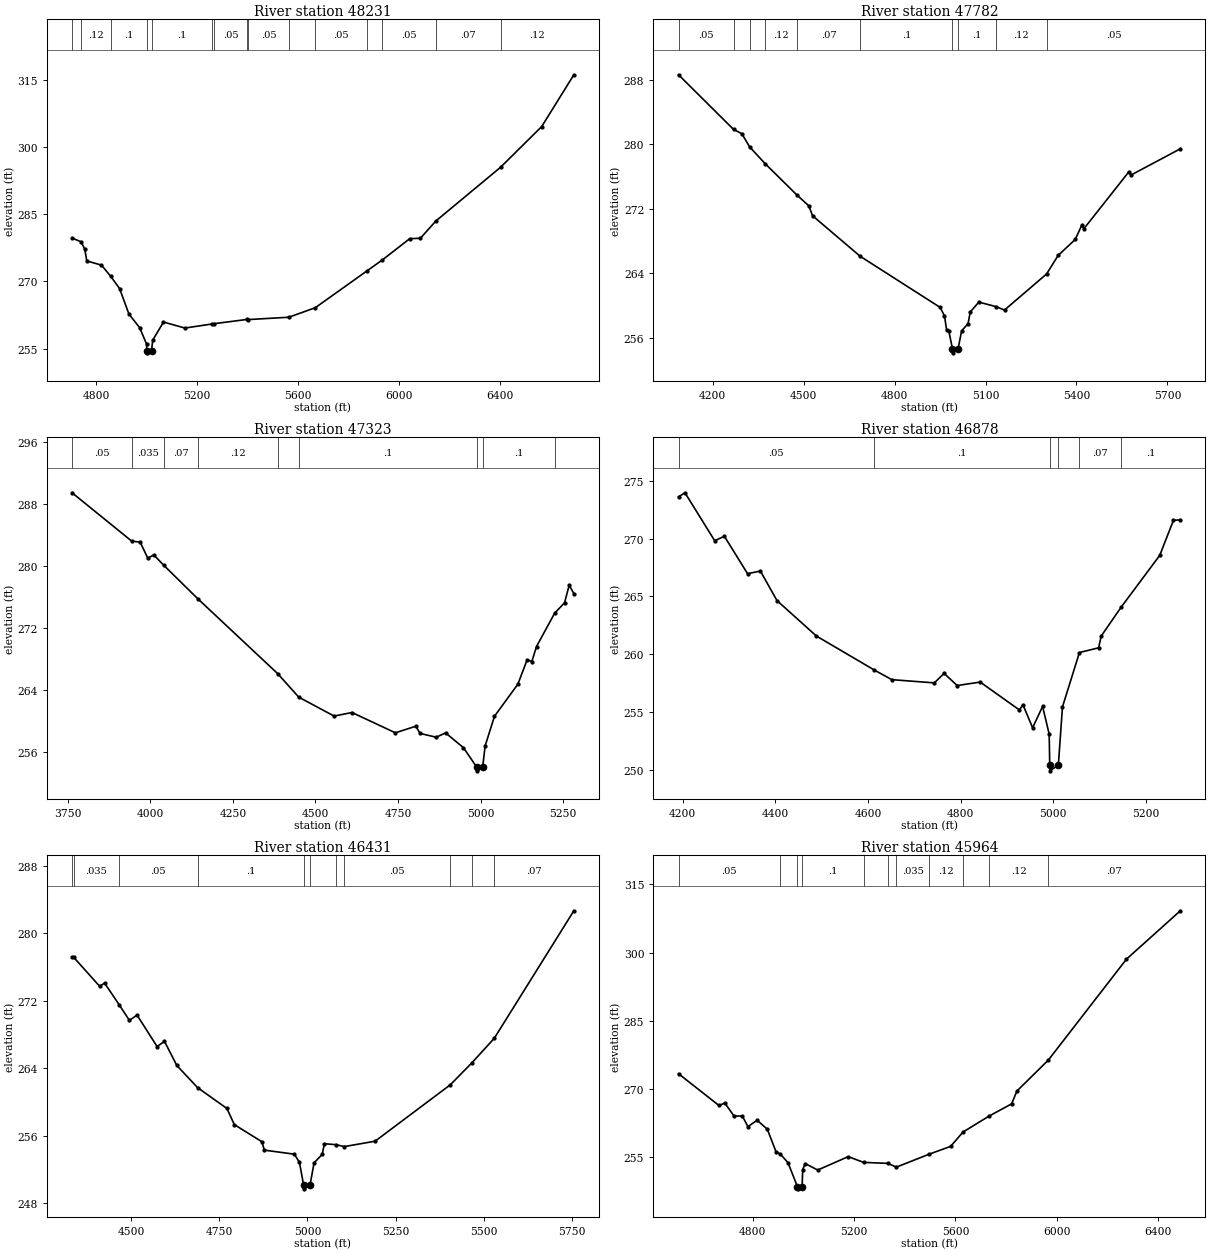
Type RM Length L Ch R = 1 ,48231   ,449,449,449
BEGIN DESCRIPTION:
MCCOY CREEK 56.0
END DESCRIPTION:
XS GIS Cut Line= 3
        2516375.     13653874.99        2516225.       13653625.
        2515025.       13652425.
#Sta/Elev= 30
  4704.1  279.66  4740.1   278.8  4754.6  277.14  4762.4  274.55  4820.7  273.61
  4856.9  271.14  4892.6  268.37  4929.6  262.68  4972.3  259.64  4999.2  256.01
  5000.6  254.55  5001.1  254.05  5018.9  254.55  5023.9  256.89  5066.4  260.92
  5151.2  259.58  5260.6   260.5  5266.8  260.55  5398.8  261.51  5402.1  261.47
  5563.2  261.99  5668.1  264.12  5871.9  272.29  5933.5  274.76  6042.2  279.51
  6084.6  279.61  6145.5  283.44  6402.2  295.44  6565.4  304.53  6692.7  316.07
#Mann= 15 ,-1 , 0
  4704.1    .035       0  4740.1     .12       0  4856.9      .1       0
  5000.6     .05       0  5018.9      .1       0  5260.6     .12       0
  5266.8     .05       0  5398.8     .12       0  5402.1     .05       0
  5563.2     .12       0  5668.1     .05       0  5871.9     .07       0
  5933.5     .05       0  6145.5     .07       0  6402.2     .12       0
Bank Sta=5000.6,5018.9
XS Rating Curve= 0 ,0
Exp/Cntr=0.3,0.1

Type RM Length L Ch R = 1 ,47782   ,459,459,459
BEGIN DESCRIPTION:
B19363
END DESCRIPTION:
XS GIS Cut Line= 3
      2516686.55     13654023.66      2516460.63     13653334.89
      2515789.18     13652690.95
#Sta/Elev= 30
  4087.3  288.61  4268.9  281.83    4296  281.31  4322.2  279.65  4372.7   277.6
  4477.3  273.72  4517.4  272.34  4529.3  271.13  4686.6   266.1  4950.4  259.76
  4964.6   258.7  4971.8  256.91  4978.7  256.86  4990.9  254.63  4991.4  254.13
  5009.3  254.63  5021.2  256.86  5042.3  257.75  5049.5  259.19  5077.8  260.42
  5133.7  259.87  5162.7  259.44  5301.3  263.91  5339.5  266.21  5396.1   268.2
  5417.1  269.94  5424.4  269.52  5572.8  276.58    5580  276.18  5742.5  279.43
#Mann= 10 ,-1 , 0
  4087.3     .05       0  4268.9    .035       0  4322.2     .05       0
  4372.7     .12       0  4477.3     .07       0  4686.6      .1       0
  4990.9     .05       0  5009.3      .1       0  5133.7     .12       0
  5301.3     .05       0
Bank Sta=4990.9,5009.3
XS Rating Curve= 0 ,0
Exp/Cntr=0.3,0.1

Type RM Length L Ch R = 1 ,47323   ,445,445,445
BEGIN DESCRIPTION:
MCCOY CREEK 55.0
END DESCRIPTION:
XS GIS Cut Line= 3
      2516775.01     13654025.03        2516475.       13652825.
        2516275.       13652625.
#Sta/Elev= 30
  3762.8  289.43  3943.4  283.19    3969  283.06  3992.2  280.98  4010.2  281.41
  4040.6  280.07  4142.8  275.78  4385.3  266.09  4449.6  263.04  4556.5   260.6
  4610.6  261.06  4742.1  258.44  4803.9  259.29  4816.8  258.36  4865.8  257.87
  4894.1  258.43  4948.2  256.52    4988  254.03  4988.5  253.53  5006.4  254.03
  5013.9  256.75  5042.2  260.58  5112.9  264.71  5141.2  267.87  5155.3  267.64
  5169.5  269.58  5224.3  273.88  5254.3  275.22  5268.5   277.5  5282.6  276.41
#Mann= 9 ,-1 , 0
  3762.8     .05       0  3943.4    .035       0  4040.6     .07       0
  4142.8     .12       0  4385.3     .07       0  4449.6      .1       0
    4988     .05       0  5006.4      .1       0  5224.3     .12       0
Bank Sta=4988,5006.4
XS Rating Curve= 0 ,0
Exp/Cntr=0.3,0.1

Type RM Length L Ch R = 1 ,46878   ,447,447,447
BEGIN DESCRIPTION:
MCCOY CREEK 54.0
END DESCRIPTION:
XS GIS Cut Line= 3
      2517425.03     13653125.03        2516825.       13652575.
      2516575.04     13652475.01
#Sta/Elev= 30
  4190.9  273.63  4204.8  273.98  4268.9  269.83  4289.9  270.21  4339.9  266.97
  4367.6   267.2  4403.4  264.64  4488.5  261.57  4612.4  258.65  4651.2  257.79
  4743.1  257.51  4764.1  258.33  4792.5  257.28  4842.1  257.58  4926.9  255.16
  4934.3  255.63  4955.2  253.62  4976.8  255.47    4991  253.07  4992.2  250.39
  4992.7  249.89  5010.8  250.39  5019.7  255.43  5056.3  260.14  5097.8  260.55
  5103.2  261.56  5146.7  264.09  5229.7  268.56  5259.3   271.6  5274.1  271.63
#Mann= 6 ,-1 , 0
  4190.9     .05       0  4612.4      .1       0  4992.2     .05       0
  5010.8      .1       0  5056.3     .07       0  5146.7      .1       0
Bank Sta=4992.2,5010.8
XS Rating Curve= 0 ,0
Exp/Cntr=0.3,0.1

Type RM Length L Ch R = 1 ,46431   ,467,467,467
BEGIN DESCRIPTION:
MCCOY CREEK 53.0
END DESCRIPTION:
XS GIS Cut Line= 3
        2517725.       13652875.        2517225.       13652425.
      2516624.99     13651974.99
#Sta/Elev= 30
  4332.5   277.2  4336.7  277.19  4410.6  273.74  4424.8  274.11  4465.8  271.56
  4495.1  269.69  4516.7  270.32  4573.5  266.59  4594.5   267.2  4629.6  264.34
  4688.2  261.72  4771.6  259.24  4792.5  257.33  4870.6   255.3  4877.7   254.3
    4963  253.82  4977.2  252.84  4988.8  250.21  4989.3  249.71  5007.4  250.21
  5018.7   252.8  5041.6  253.79  5047.9  255.06  5080.6  254.95  5104.2  254.72
  5191.6  255.36  5404.9  262.05  5465.6  264.63  5529.6  267.57  5755.2  282.69
#Mann= 11 ,-1 , 0
  4332.5     .05       0  4336.7    .035       0  4465.8     .05       0
  4688.2      .1       0  4988.8     .05       0  5007.4      .1       0
  5080.6     .07       0  5104.2     .05       0  5404.9     .07       0
  5465.6     .05       0  5529.6     .07       0
Bank Sta=4988.8,5007.4
XS Rating Curve= 0 ,0
Exp/Cntr=0.3,0.1

Type RM Length L Ch R = 1 ,45964   ,848,848,848
BEGIN DESCRIPTION:
MCCOY CREEK 52.0
END DESCRIPTION:
XS GIS Cut Line= 3
      2517825.02     13652675.04        2517625.       13652225.
        2516525.       13651225.
#Sta/Elev= 30
  4507.9  273.39  4667.3  266.41  4690.6  266.94  4726.8  264.08  4759.6   264.1
  4781.5  261.75  4817.8  263.16  4858.1  261.19    4893  256.15  4908.1   255.8
  4939.5  253.85  4976.7  248.58  4977.2  248.08  4995.3  248.58  4997.7  252.32
  5007.5  253.64  5056.8  252.21  5177.1  255.16  5237.7   253.9  5332.6  253.68
  5367.3  252.86    5497  255.71  5581.2  257.42  5629.9  260.57  5733.1  264.09
  5821.7  266.77  5842.7   269.6  5966.6   276.4  6274.5  298.58    6487  309.22
#Mann= 11 ,-1 , 0
  4507.9     .05       0  4908.1      .1       0  4976.7     .05       0
  4995.3      .1       0  5237.7     .07       0  5332.6     .12       0
  5367.3    .035       0    5497     .12       0  5629.9     .07       0
  5733.1     .12       0  5966.6     .07       0
Bank Sta=4976.7,4995.3
XS Rating Curve= 0 ,0
Exp/Cntr=0.3,0.1