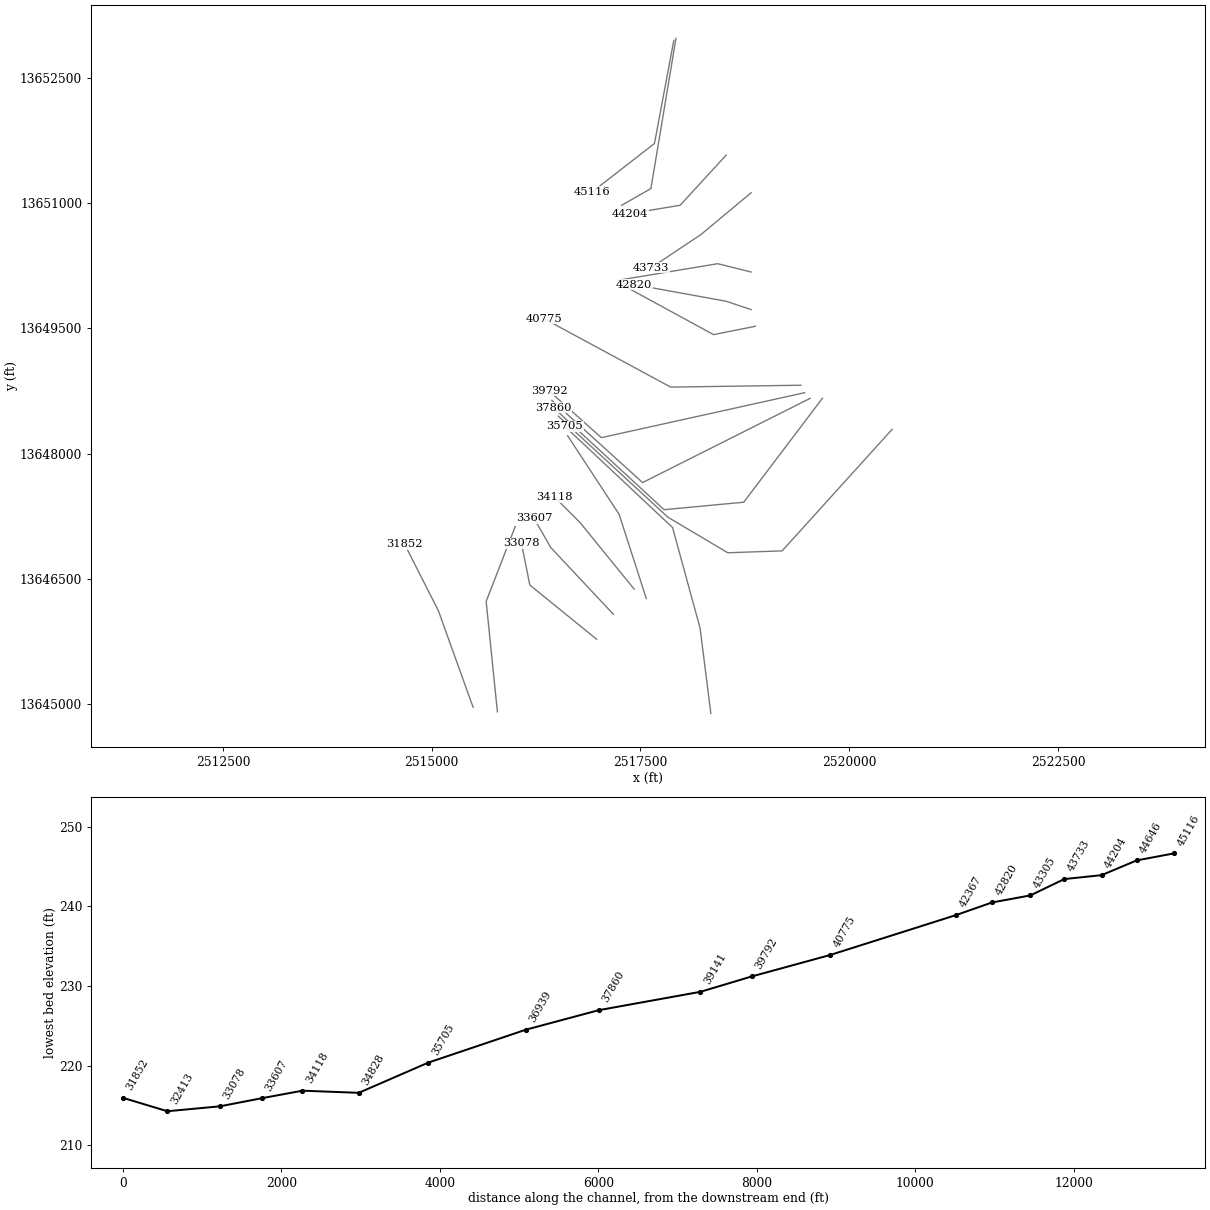
HEC-RAS study MCCOY CREEK.prj: MCCOY CREEK Base Level Engineering

--- MCCOY CREEK.g01 (geometry) --- (continued)

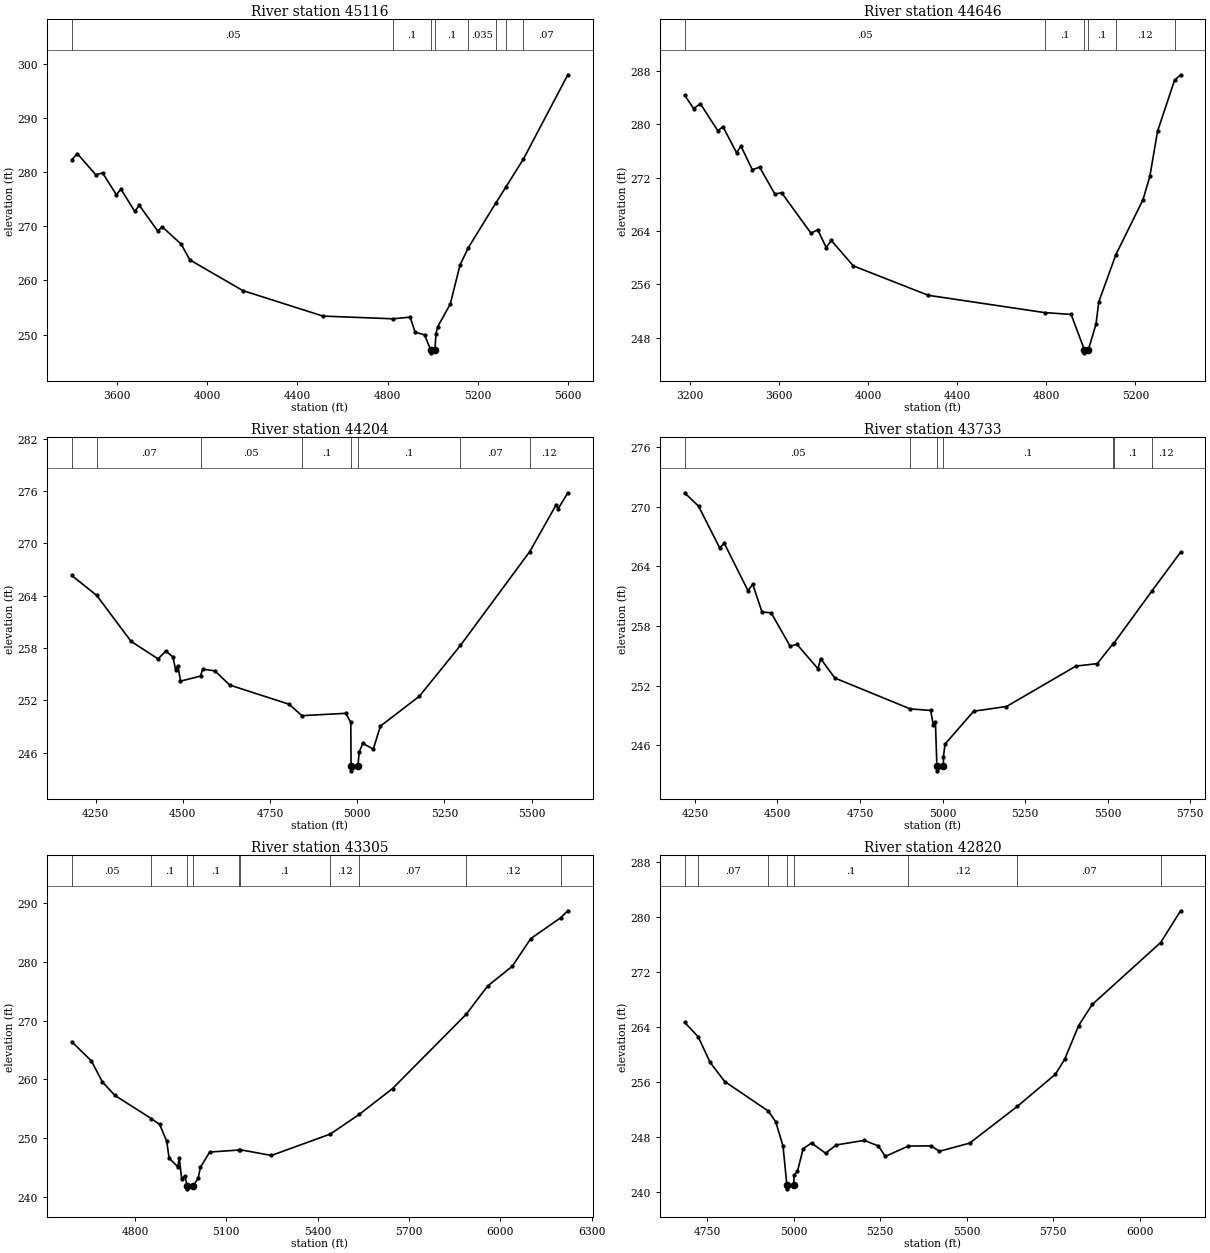
Type RM Length L Ch R = 1 ,45116   ,470,470,470
BEGIN DESCRIPTION:
B19361
END DESCRIPTION:
XS GIS Cut Line= 3
      2517898.82     13652949.21      2517667.38     13651714.87
      2516923.53     13651136.32
#Sta/Elev= 30
  3400.5  282.26  3425.1  283.39  3507.1  279.48    3537  279.84  3598.1   275.8
  3618.4  276.84  3679.5  272.73  3699.8  273.85  3781.2  269.12  3801.6  269.87
  3885.3  266.69  3923.7  263.78  4158.3  258.12  4513.8  253.41    4824  252.91
  4900.1  253.22    4922  250.44  4963.6  249.95  4991.4  247.13  4991.9  246.63
    5010  247.13  5014.1  250.04  5021.5  251.41  5077.6  255.61  5121.1  262.85
  5158.3  266.06  5280.3  274.33  5323.5  277.17  5402.3  282.42  5598.7  297.94
#Mann= 8 ,-1 , 0
  3400.5     .05       0    4824      .1       0  4991.4     .05       0
    5010      .1       0  5158.3    .035       0  5280.3     .07       0
  5323.5    .035       0  5402.3     .07       0
Bank Sta=4991.4,5010
XS Rating Curve= 0 ,0
Exp/Cntr=0.3,0.1

Type RM Length L Ch R = 1 ,44646   ,442,442,442
BEGIN DESCRIPTION:
MCCOY CREEK 51.0
END DESCRIPTION:
XS GIS Cut Line= 3
        2517925.     13652974.99        2517625.       13651175.
      2517275.02     13650975.01
#Sta/Elev= 30
  3175.1  284.39  3215.6  282.36  3246.1  283.08  3324.6  279.02  3347.4  279.65
  3408.3  275.74  3428.5  276.72  3479.2   273.2  3512.2  273.57  3580.6  269.55
    3611  269.74  3742.8  263.68  3773.2  264.19  3811.2  261.53  3834.1  262.59
  3932.9  258.78    4270  254.37  4792.1  251.78  4911.2  251.51  4970.3  246.25
  4970.8  245.75    4989  246.25    5023  250.05  5035.2  253.36  5112.4  260.48
  5233.9  268.69  5264.8   272.2  5299.4  278.96  5375.8  286.61    5403  287.42
#Mann= 6 ,-1 , 0
  3175.1     .05       0  4792.1      .1       0  4970.3     .05       0
    4989      .1       0  5112.4     .12       0  5375.8     .07       0
Bank Sta=4970.3,4989
XS Rating Curve= 0 ,0
Exp/Cntr=0.3,0.1

Type RM Length L Ch R = 1 ,44204   ,471,471,471
BEGIN DESCRIPTION:
MCCOY CREEK 50.0
END DESCRIPTION:
XS GIS Cut Line= 3
      2518524.98     13651574.97        2517975.       13650975.
      2517374.98       13650875.
#Sta/Elev= 30
  4181.8  266.31  4253.4  264.02  4351.6  258.76  4429.3  256.74  4450.9  257.63
  4471.9  256.98  4479.3  255.51  4486.1  255.98  4493.5  254.19  4550.9  254.77
    4557  255.56  4592.1  255.37  4634.7  253.74  4804.9  251.54  4841.6  250.23
  4967.6   250.5  4981.8  249.45  4982.5   244.4    4983   243.9  5002.1   244.4
  5005.8  246.06    5016  247.04  5046.4  246.41  5066.7  249.03  5178.2  252.45
    5296  258.28    5495  269.06    5571  274.45  5576.1  273.95    5604   275.8
#Mann= 8 ,-1 , 0
  4181.8     .05       0  4253.4     .07       0  4550.9     .05       0
  4841.6      .1       0  4982.5     .05       0  5002.1      .1       0
    5296     .07       0    5495     .12       0
Bank Sta=4982.5,5002.1
XS Rating Curve= 0 ,0
Exp/Cntr=0.3,0.1

Type RM Length L Ch R = 1 ,43733   ,428,428,428
BEGIN DESCRIPTION:
MCCOY CREEK 49.0
END DESCRIPTION:
XS GIS Cut Line= 3
      2518825.03     13651125.03        2518225.       13650625.
      2517624.98     13650224.99
#Sta/Elev= 30
  4218.7  271.42    4261  270.07  4324.8  265.88  4339.1  266.32  4410.7  261.56
  4425.1  262.21    4453  259.42    4481  259.32  4538.3  255.97  4559.1  256.15
  4622.9  253.69  4630.7  254.71  4673.7  252.76  4901.9  249.65    4964  249.49
  4971.8  248.04  4978.3  248.37  4982.8  243.91  4983.3  243.41  5002.4  243.91
  5002.8  244.84  5007.3   246.1  5094.4  249.42  5193.6  249.89  5403.9  253.96
  5468.5  254.21  5515.8  256.19  5518.6  256.26  5634.7  261.56  5720.9  265.44
#Mann= 7 ,-1 , 0
  4218.7     .05       0  4901.9      .1       0  4982.8     .05       0
  5002.4      .1       0  5515.8     .07       0  5518.6      .1       0
  5634.7     .12       0
Bank Sta=4982.8,5002.4
XS Rating Curve= 0 ,0
Exp/Cntr=0.3,0.1

Type RM Length L Ch R = 1 ,43305   ,485,485,485
BEGIN DESCRIPTION:
MCCOY CREEK 48.0
END DESCRIPTION:
XS GIS Cut Line= 3
      2518825.01       13650175.        2518425.       13650275.
      2517224.97       13650075.
#Sta/Elev= 30
  4592.8  266.39  4657.2  263.12  4693.3  259.55  4734.5  257.25  4854.1  253.31
  4881.4  252.31  4904.6  249.47  4912.3   246.6  4940.7  245.12  4945.8   246.6
  4953.6   243.1  4963.9  243.54  4972.1  241.86  4972.6  241.36  4991.7  241.86
  5007.7  243.17  5015.3  245.02  5045.7  247.62  5141.2  247.96  5144.1  248.03
  5248.4  247.04  5442.2  250.69  5536.7  254.02  5646.3  258.43  5888.2  271.07
  5958.1  275.85  6039.2  279.22    6100  283.94  6197.7  287.46  6221.7  288.67
#Mann= 10 ,-1 , 0
  4592.8     .05       0  4854.1      .1       0  4972.1     .05       0
  4991.7      .1       0  5141.2     .07       0  5144.1      .1       0
  5442.2     .12       0  5536.7     .07       0  5888.2     .12       0
  6197.7     .07       0
Bank Sta=4972.1,4991.7
XS Rating Curve= 0 ,0
Exp/Cntr=0.3,0.1

Type RM Length L Ch R = 1 ,42820   ,453,453,453
BEGIN DESCRIPTION:
MCCOY CREEK 47.0
END DESCRIPTION:
XS GIS Cut Line= 3
      2518825.02     13649724.99        2518525.       13649825.
      2517424.99       13650025.
#Sta/Elev= 30
  4684.2  264.69  4723.4   262.6    4758  258.86  4800.2  256.08    4926  251.79
  4947.7  250.22  4968.8   246.7  4980.1  240.97  4980.6  240.47  4999.8  240.97
  5000.5  242.43  5010.6  243.02  5027.1  246.31  5051.3  247.14  5091.9  245.65
  5122.4  246.85  5203.7  247.52  5244.4  246.71  5264.7  245.19  5331.1  246.69
  5396.8  246.72    5421  245.93  5508.6  247.12    5646  252.45  5756.4  257.13
  5783.1  259.29  5823.7  264.22  5863.1  267.29  6060.8  276.29  6118.5  280.91
#Mann= 8 ,-1 , 0
  4684.2     .05       0  4723.4     .07       0    4926      .1       0
  4980.1     .05       0  4999.8      .1       0  5331.1     .12       0
    5646     .07       0  6060.8     .12       0
Bank Sta=4980.1,4999.8
XS Rating Curve= 0 ,0
Exp/Cntr=0.3,0.1

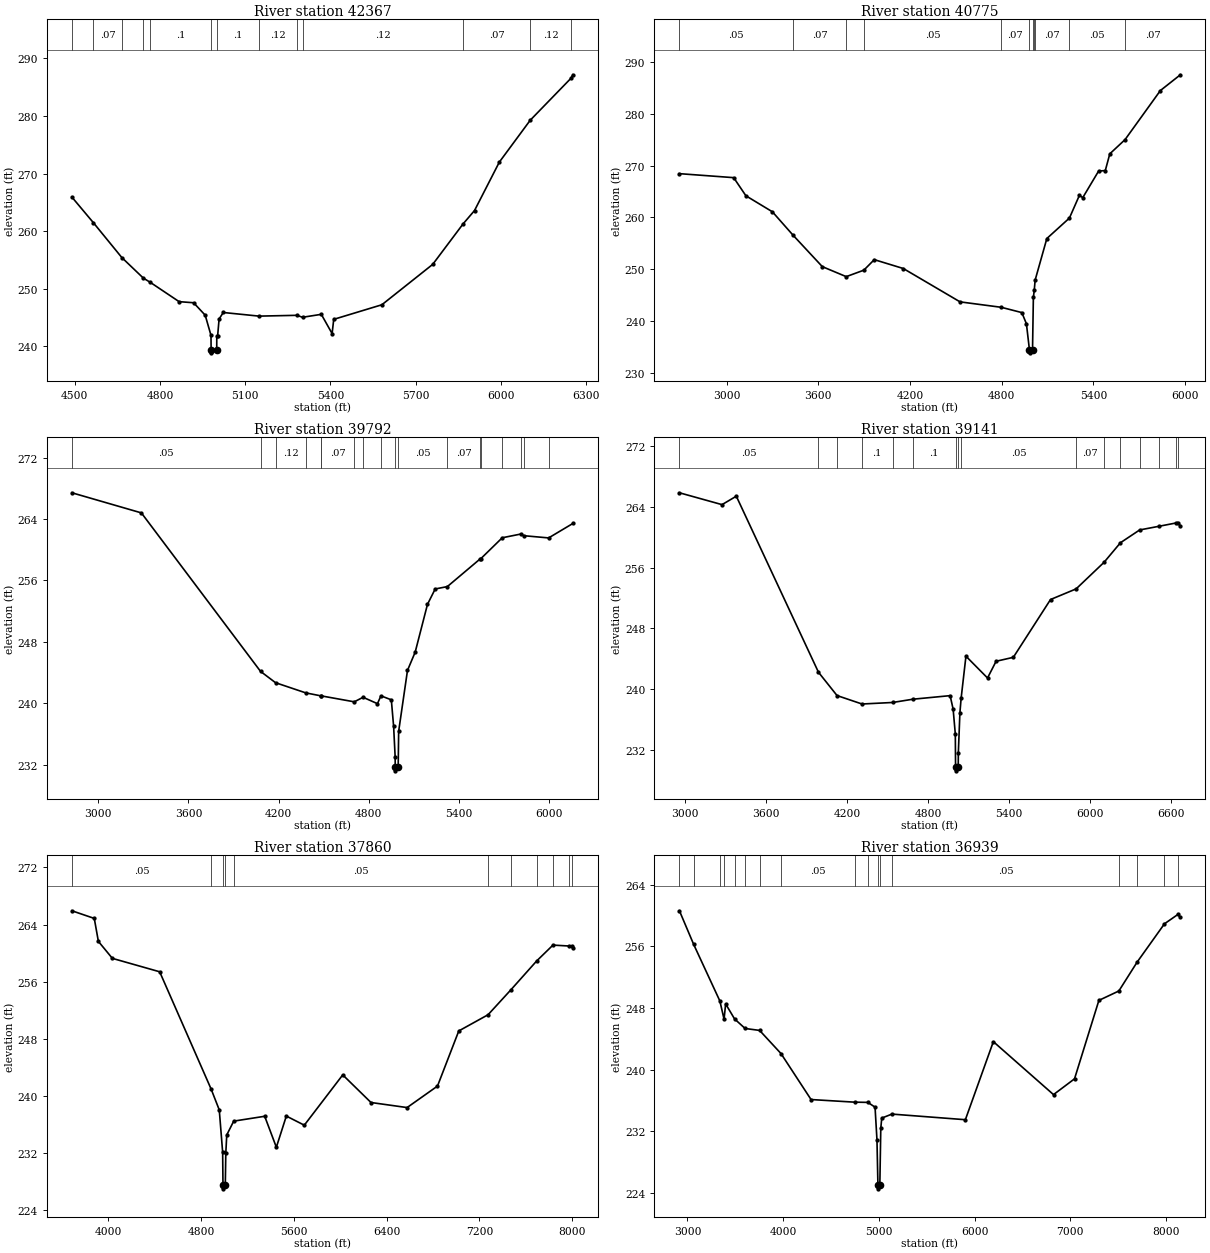
Type RM Length L Ch R = 1 ,42367   ,1592,1592,1592
BEGIN DESCRIPTION:
MCCOY CREEK 46.0
END DESCRIPTION:
XS GIS Cut Line= 3
      2518875.01       13649525.        2518375.       13649425.
      2517275.01       13650025.
#Sta/Elev= 30
    4490  265.91  4565.9  261.45  4665.7  255.42  4741.3  251.86  4765.5  251.13
  4867.3  247.77  4918.3  247.58  4959.1  245.42  4979.5  241.92  4979.9  239.39
  4980.4  238.89  4999.6  239.39  4999.9   241.8  5002.8   241.8    5008  244.76
  5022.7  245.89  5148.5  245.26    5282   245.4  5301.6  245.06  5367.7  245.57
  5405.7  242.23  5411.4   244.7  5580.8  247.23  5759.8  254.24  5866.5  261.25
  5906.9  263.58  5994.2  271.98    6103  279.25  6245.8   286.5  6252.9  287.13
#Mann= 13 ,-1 , 0
    4490     .05       0  4565.9     .07       0  4665.7      .1       0
  4741.3     .07       0  4765.5      .1       0  4979.9     .05       0
  4999.6      .1       0  5148.5     .12       0    5282     .07       0
  5301.6     .12       0  5866.5     .07       0    6103     .12       0
  6245.8     .07       0
Bank Sta=4979.9,4999.6
XS Rating Curve= 0 ,0
Exp/Cntr=0.3,0.1

Type RM Length L Ch R = 1 ,40775   ,983,983,983
BEGIN DESCRIPTION:
B19360
END DESCRIPTION:
XS GIS Cut Line= 3
      2519420.06     13648818.73      2517861.42      13648796.3
       2516348.8     13649614.24
#Sta/Elev= 30
    2691  268.46  3046.1  267.69  3126.1  264.19  3299.4   261.1  3435.3  256.56
  3626.2  250.51  3782.7  248.58  3897.9  249.83  3966.2  251.86  4156.2  250.15
  4527.6  243.71  4797.6  242.66  4931.9  241.64  4961.9  239.48    4982  234.37
  4982.5  233.87  5001.8  234.37  5007.4  244.57  5013.1  245.91    5019  247.92
  5095.6  255.94  5243.3  259.89  5308.7  264.28  5330.6  263.83  5434.3  268.96
  5478.1  269.06  5507.6  272.29  5607.3  275.03  5838.7  284.51  5969.4  287.55
#Mann= 11 ,-1 , 0
    2691     .05       0  3435.3     .07       0  3782.7      .1       0
  3897.9     .05       0  4797.6     .07       0    4982     .05       0
  5001.8     .07       0  5013.1      .1       0    5019     .07       0
  5243.3     .05       0  5607.3     .07       0
Bank Sta=4982,5001.8
XS Rating Curve= 0 ,0
Exp/Cntr=0.3,0.1

Type RM Length L Ch R = 1 ,39792   ,651,651,651
BEGIN DESCRIPTION:
B19359
END DESCRIPTION:
XS GIS Cut Line= 3
      2519464.98     13648729.03      2517031.63     13648190.78
       2516404.5     13648750.72
#Sta/Elev= 30
    2825  267.42  3287.2   264.8  4079.8  244.16  4179.9  242.68  4380.2  241.36
  4480.4  240.97  4482.3  240.97  4703.6  240.19  4762.3  240.78  4857.9  239.95
    4881  240.97  4950.2  240.45  4965.5  236.99  4975.7  233.01  4976.1   231.7
  4976.6   231.2  4995.9   231.7    4999  236.35  5057.7  244.28  5108.9  246.66
  5190.8  252.89    5242  254.89  5322.9   255.2  5540.3  258.79  5544.8  258.82
  5688.2  261.56  5810.4  262.04  5831.5  261.83  5996.8  261.54  6157.9  263.42
#Mann= 18 ,-1 , 0
    2825     .05       0  4079.8     .07       0  4179.9     .12       0
  4380.2     .07       0  4480.4     .12       0  4482.3     .07       0
  4703.6      .1       0  4762.3     .07       0    4881     .05       0
  4976.1     .05       0  4995.9     .05       0  5322.9     .07       0
  5540.3     .12       0  5544.8    .035       0  5688.2     .12       0
  5810.4     .07       0  5831.5     .12       0  5996.8     .05       0
Bank Sta=4976.1,4995.9
XS Rating Curve= 0 ,0
Exp/Cntr=0.3,0.1

Type RM Length L Ch R = 1 ,39141   ,1281,1281,1281
BEGIN DESCRIPTION:
B19358
END DESCRIPTION:
XS GIS Cut Line= 3
      2519532.18     13648661.72      2517525.02     13647652.54
      2516438.65     13648638.11
#Sta/Elev= 30
    2956  265.83  3271.7  264.27  3377.7  265.38  3986.6  242.23  4124.4  239.16
  4309.6  238.05  4536.2  238.25  4686.7  238.68  4962.7  239.15    4985  237.37
  5001.1   234.1    5003  229.76  5003.5  229.26  5022.8  229.76  5023.5  231.61
  5035.2  236.91  5044.4  238.83  5079.9  244.34  5239.9  241.47  5303.4  243.67
  5431.2  244.19  5706.9  251.79  5896.6  253.19  6103.4  256.68  6225.3  259.26
  6367.5  260.94  6509.7  261.42  6634.9  261.85  6651.9  261.92  6669.4  261.45
#Mann= 16 ,-1 , 0
    2956     .05       0  3986.6     .12       0  4124.4     .05       0
  4309.6      .1       0  4536.2     .05       0  4686.7      .1       0
    5003     .05       0  5022.8      .1       0  5044.4     .05       0
  5896.6     .07       0  6103.4     .12       0  6225.3    .035       0
  6367.5     .07       0  6509.7     .12       0  6634.9     .07       0
  6651.9     .05       0
Bank Sta=5003,5022.8
XS Rating Curve= 0 ,0
Exp/Cntr=0.3,0.1

Type RM Length L Ch R = 1 ,37860   ,921,921,921
BEGIN DESCRIPTION:
B19357
END DESCRIPTION:
XS GIS Cut Line= 4
        2519678.     13648661.75      2518736.07     13647417.05
      2517782.93     13647327.35      2516459.89     13648549.48
#Sta/Elev= 30
  3686.6  265.93  3879.5  264.86  3914.9  261.64  4035.6  259.26  4443.4  257.38
  4887.1  240.94  4957.3  238.02  4986.5  232.07  4989.3  227.46  4989.8  226.96
  5009.2  227.46  5013.6  231.94  5021.8  234.51  5081.8  236.45    5349  237.13
  5449.5  232.79  5535.5  237.16  5690.5  235.88    6022  242.93  6265.5  239.06
  6576.8  238.35  6838.8  241.36  7022.5  249.09    7275  251.36  7472.8  254.87
  7693.6  258.89  7834.5  261.12  7975.4  260.99  7997.4  260.99    8006  260.75
#Mann= 11 ,-1 , 0
  3686.6     .05       0  4887.1      .1       0  4989.3     .05       0
  5009.2      .1       0  5081.8     .05       0    7275     .07       0
  7472.8     .12       0  7693.6    .035       0  7834.5     .07       0
  7975.4     .12       0  7997.4     .07       0
Bank Sta=4989.3,5009.2
XS Rating Curve= 0 ,0
Exp/Cntr=0.3,0.1

Type RM Length L Ch R = 1 ,36939   ,1234,1234,1234
BEGIN DESCRIPTION:
B19356
END DESCRIPTION:
XS GIS Cut Line= 5
      2520512.61      13648289.8      2519195.82     13646833.96
      2518545.44     13646811.53      2517827.78     13647237.64
      2516515.79     13648448.71
#Sta/Elev= 30
  2916.2  260.63  3065.5  256.25  3338.8  248.91  3382.5  246.55  3399.2  248.53
  3492.3  246.58  3602.6  245.34  3753.9  245.09  3976.9  242.09  4291.4  236.11
  4745.4  235.77  4884.8  235.74  4960.1  235.12  4980.1  230.88  4990.1  225.01
  4990.6  224.51  5010.1  225.01  5020.1  232.38  5030.1   233.7  5136.2  234.22
  5903.8  233.49  6196.1  243.63  6824.7  236.75  7044.2   238.8  7298.8  248.99
  7507.3  250.21  7698.7  253.97    7984  258.94    8125  260.16  8150.1  259.76
#Mann= 17 ,-1 , 0
  2916.2     .05       0  3065.5     .12       0  3338.8     .07       0
  3382.5      .1       0  3492.3     .07       0  3602.6     .05       0
  3753.9     .07       0  3976.9     .05       0  4745.4     .07       0
  4884.8      .1       0  4990.1     .05       0  5010.1      .1       0
  5136.2     .05       0  7507.3     .07       0  7698.7     .12       0
    7984    .035       0    8125     .07       0
Bank Sta=4990.1,5010.1
XS Rating Curve= 0 ,0
Exp/Cntr=0.3,0.1

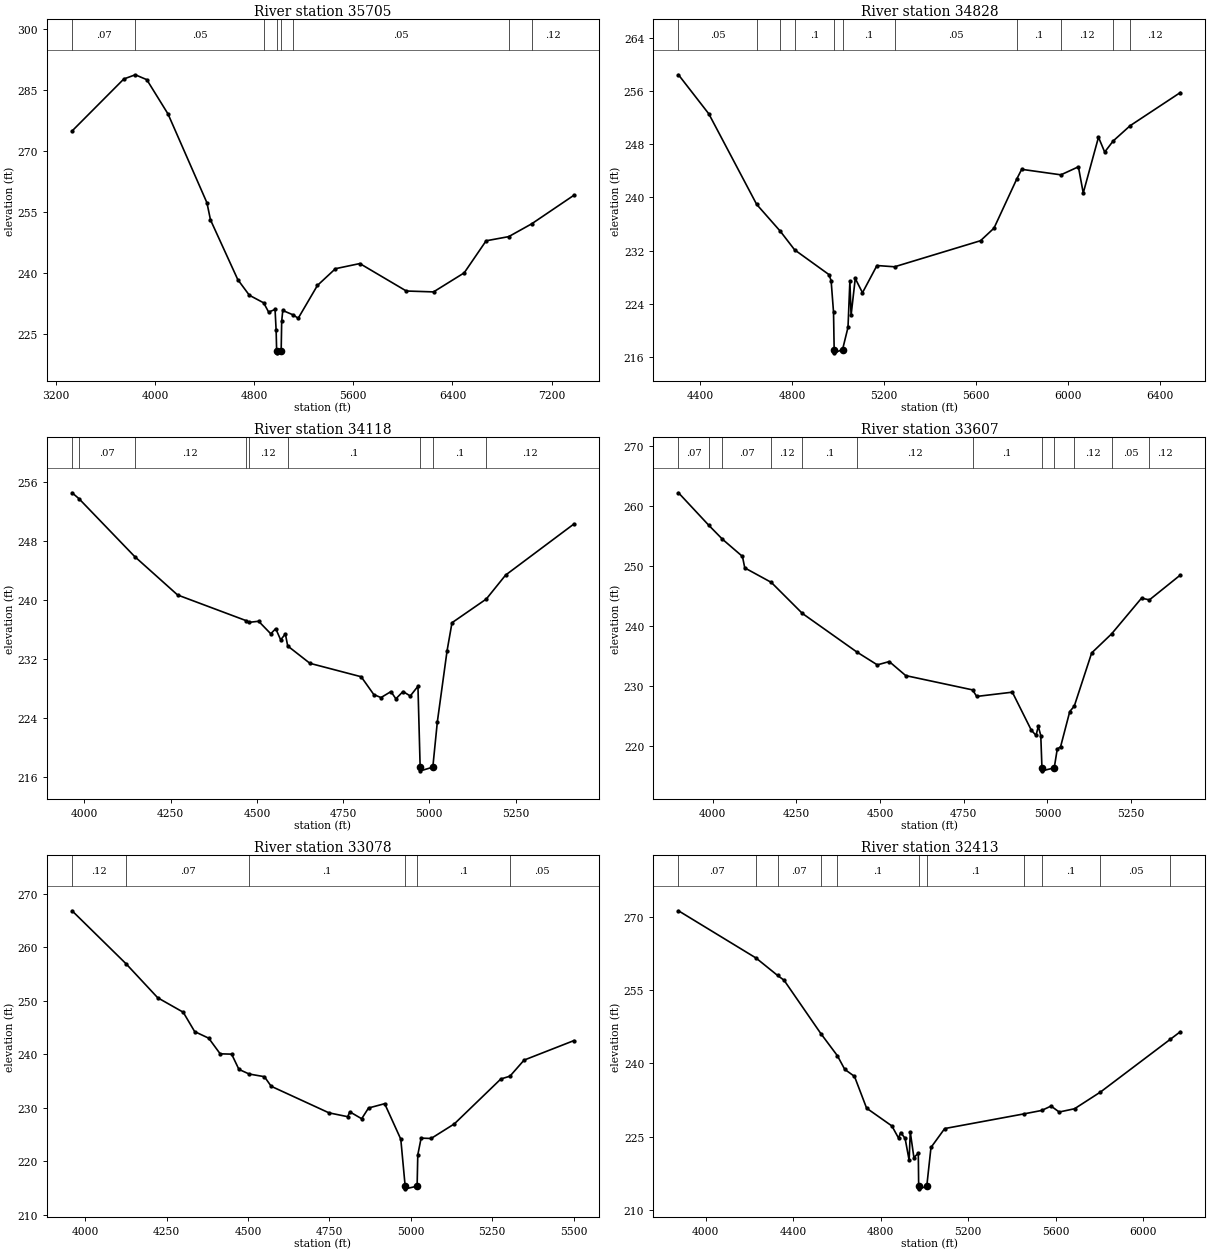
Type RM Length L Ch R = 1 ,35705   ,877,877,877
BEGIN DESCRIPTION:
B19355
END DESCRIPTION:
XS GIS Cut Line= 4
      2518342.49     13644887.06      2518213.42      13645909.3
      2517883.85     13647114.29      2516594.28     13648325.37
#Sta/Elev= 30
  3331.3  274.84  3748.9  287.61  3841.4  288.64    3934  287.44  4105.3  279.02
  4419.4  257.21  4447.9  253.02  4668.2  238.35  4761.5  234.51  4877.2  232.64
    4917  230.38  4968.9  231.02  4977.6  225.86  4981.7  220.87  4982.6  220.37
  5018.2  220.87  5022.4  228.09  5031.1  230.77  5116.3  229.67  5155.5  228.85
    5311  236.93  5456.1  241.03  5652.9  242.29    6028  235.55  6247.3  235.33
  6494.9  240.01  6671.7  247.88  6853.8   248.9  7038.9  252.04    7380  259.06
#Mann= 8 ,-1 , 0
  3331.3     .07       0  3841.4     .05       0  4877.2      .1       0
  4981.7     .05       0  5018.2      .1       0  5116.3     .05       0
  6853.8     .07       0  7038.9     .12       0
Bank Sta=4981.7,5018.2
XS Rating Curve= 0 ,0
Exp/Cntr=0.3,0.1

Type RM Length L Ch R = 1 ,34828   ,710,710,710
BEGIN DESCRIPTION:
B19354
END DESCRIPTION:
XS GIS Cut Line= 3
      2517569.88     13646262.05      2517244.69     13647271.28
      2516627.95     13648213.21
#Sta/Elev= 30
  4304.1  258.49  4436.3   252.6  4644.8  238.95  4747.4  234.92  4810.2   232.1
  4959.8  228.37  4969.1  227.45  4979.6  222.69  4982.3  217.08  4983.2  216.58
  5018.9  217.08  5042.6  220.42  5050.8  227.38    5056  222.22  5074.2  227.79
  5105.7  225.64  5168.7  229.74  5245.4  229.55  5619.9  233.48  5678.5  235.37
  5777.5  242.76  5799.2  244.24  5970.1  243.41  6046.3  244.62  6067.4  240.67
  6133.8  249.08  6160.8  246.84  6197.7  248.51  6271.9  250.82  6490.3  255.81
#Mann= 11 ,-1 , 0
  4304.1     .05       0  4644.8     .07       0  4747.4     .12       0
  4810.2      .1       0  4982.3     .05       0  5018.9      .1       0
  5245.4     .05       0  5777.5      .1       0  5970.1     .12       0
  6197.7     .07       0  6271.9     .12       0
Bank Sta=4982.3,5018.9
XS Rating Curve= 0 ,0
Exp/Cntr=0.3,0.1

Type RM Length L Ch R = 1 ,34118   ,511,511,511
BEGIN DESCRIPTION:
MCCOY CREEK 42.0
END DESCRIPTION:
XS GIS Cut Line= 3
      2517424.98     13646375.02        2516775.       13647175.
      2516475.01     13647474.99
#Sta/Elev= 30
  3964.2  254.53    3984  253.74  4145.7  245.89  4270.2  240.68    4469   237.2
  4477.1  236.97  4505.1  237.12  4540.3  235.42  4554.6  236.12    4569   234.6
  4582.6   235.4  4589.4  233.77  4653.8  231.42  4802.4   229.6  4839.1  227.18
  4859.9  226.78  4888.7  227.59    4903  226.61  4923.8   227.6  4944.7  226.99
    4967  228.31  4973.4  217.35  4974.3  216.85  5010.1  217.35  5023.2  223.48
  5051.5  233.14  5065.7  236.92  5165.1  240.13  5221.2  243.38  5419.2   250.3
#Mann= 9 ,-1 , 0
  3964.2     .05       0    3984     .07       0  4145.7     .12       0
    4469      .1       0  4477.1     .12       0  4589.4      .1       0
  4973.4     .05       0  5010.1      .1       0  5165.1     .12       0
Bank Sta=4973.4,5010.1
XS Rating Curve= 0 ,0
Exp/Cntr=0.3,0.1

Type RM Length L Ch R = 1 ,33607   ,529,529,529
BEGIN DESCRIPTION:
MCCOY CREEK 41.0
END DESCRIPTION:
XS GIS Cut Line= 3
        2517175.       13646075.        2516425.       13646875.
        2516225.       13647225.
#Sta/Elev= 30
  3897.4  262.25  3988.4  256.81  4028.8  254.51  4088.6  251.64  4095.5  249.73
  4174.7  247.32  4267.7  242.14  4431.1  235.69  4491.6  233.57  4527.3  234.12
  4576.6  231.78  4776.2   229.4  4788.6  228.31  4895.1  229.02  4951.7   222.7
  4965.9  221.81  4972.7  223.33  4980.1  221.79  4983.6  216.41  4984.5  215.91
  5020.3  216.41  5029.3  219.53  5039.3  219.93  5066.7  225.79  5080.2   226.7
  5132.2  235.56  5191.8  238.74  5281.2  244.69  5304.7   244.4  5397.1  248.54
#Mann= 12 ,-1 , 0
  3897.4     .07       0  3988.4     .12       0  4028.8     .07       0
  4174.7     .12       0  4267.7      .1       0  4431.1     .12       0
  4776.2      .1       0  4983.6     .05       0  5020.3      .1       0
  5080.2     .12       0  5191.8     .05       0  5304.7     .12       0
Bank Sta=4983.6,5020.3
XS Rating Curve= 0 ,0
Exp/Cntr=0.3,0.1

Type RM Length L Ch R = 1 ,33078   ,665,665,665
BEGIN DESCRIPTION:
MCCOY CREEK 40.0
END DESCRIPTION:
XS GIS Cut Line= 3
      2516975.01     13645774.99        2516175.       13646425.
        2516075.     13646925.01
#Sta/Elev= 30
  3959.9  266.81  4125.4  256.93  4222.8  250.57  4301.1  247.87  4336.3  244.25
  4379.4  243.02  4414.6   240.1  4449.8  240.04  4472.1   237.2  4503.5  236.33
  4550.4  235.83  4571.2  234.04  4748.6  229.08  4806.1  228.36  4812.5  229.27
    4849  227.98    4870  229.98  4919.6  230.79  4969.1  224.16  4982.5  215.39
  4983.4  214.89  5019.2  215.39  5021.3  221.25  5031.5  224.36  5062.1  224.29
  5133.5  227.02  5276.2   235.4  5304.3  235.93  5347.6  238.93  5500.6  242.57
#Mann= 6 ,-1 , 0
  3959.9     .12       0  4125.4     .07       0  4503.5      .1       0
  4982.5     .05       0  5019.2      .1       0  5304.3     .05       0
Bank Sta=4982.5,5019.2
XS Rating Curve= 0 ,0
Exp/Cntr=0.3,0.1

Type RM Length L Ch R = 1 ,32413   ,561,561,561
BEGIN DESCRIPTION:
B19353
END DESCRIPTION:
XS GIS Cut Line= 3
      2515786.94      13644905.3      2515652.38     13646228.43
      2515999.99     13647125.48
#Sta/Elev= 30
  3876.3  271.28  4230.3   261.6    4329  258.02  4358.5  257.04  4526.5   246.1
  4601.8  241.58  4635.8  238.76  4680.1  237.33  4735.5  230.81    4851  227.16
  4881.2  224.69  4891.2  225.81  4911.3  224.62  4929.8  220.12  4934.9  225.94
  4951.5  220.69  4971.6  221.57  4973.3  214.77  4974.2  214.27  5010.2  214.77
  5029.5  222.75  5092.2  226.63  5454.5  229.64  5534.9  230.34  5577.9  231.24
  5615.1  230.02  5685.2  230.69  5803.7  234.12  6122.5  244.93  6168.3  246.48
#Mann= 11 ,-1 , 0
  3876.3     .07       0  4230.3     .12       0    4329     .07       0
  4526.5     .12       0  4601.8      .1       0  4973.3     .05       0
  5010.2      .1       0  5454.5    .035       0  5534.9      .1       0
  5803.7     .05       0  6122.5     .07       0
Bank Sta=4973.3,5010.2
XS Rating Curve= 0 ,0
Exp/Cntr=0.3,0.1

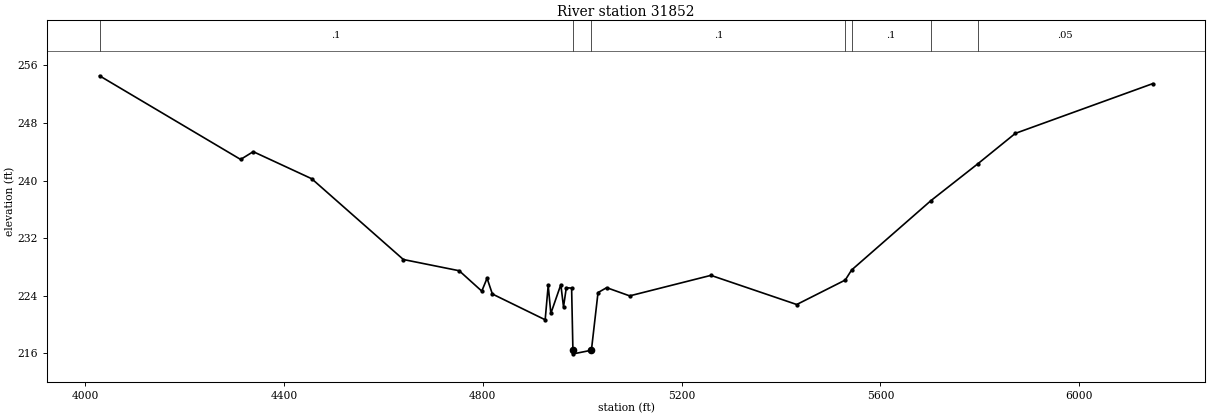
Type RM Length L Ch R = 1 ,31852   ,1109,1109,1109
BEGIN DESCRIPTION:
MCCOY CREEK 39.0
END DESCRIPTION:
XS GIS Cut Line= 3
      2515495.38     13644961.36       2515080.5      13646116.3
      2514677.43     13646911.25
#Sta/Elev= 30
  4029.2  254.57    4313  242.95  4338.4  244.03    4456  240.27  4640.4  229.05
  4752.7  227.49  4798.1  224.66  4808.7  226.45  4819.4  224.26  4925.6  220.68
  4931.7  225.46    4937  221.56  4957.1  225.56  4962.5  222.47  4968.1  225.13
  4978.8  225.08  4981.4  216.45  4982.4  215.95  5018.6  216.45  5031.9  224.46
  5049.3  225.14  5095.6     224    5259  226.85  5431.6   222.8  5529.2   226.2
  5541.9  227.59  5701.7  237.24  5795.2  242.31  5871.3  246.57  6147.7  253.48
#Mann= 7 ,-1 , 0
  4029.2      .1       0  4981.4     .05       0  5018.6      .1       0
  5529.2    .035       0  5541.9      .1       0  5701.7     .12       0
  5795.2     .05       0
Bank Sta=4981.4,5018.6
XS Rating Curve= 0 ,0
Exp/Cntr=0.3,0.1