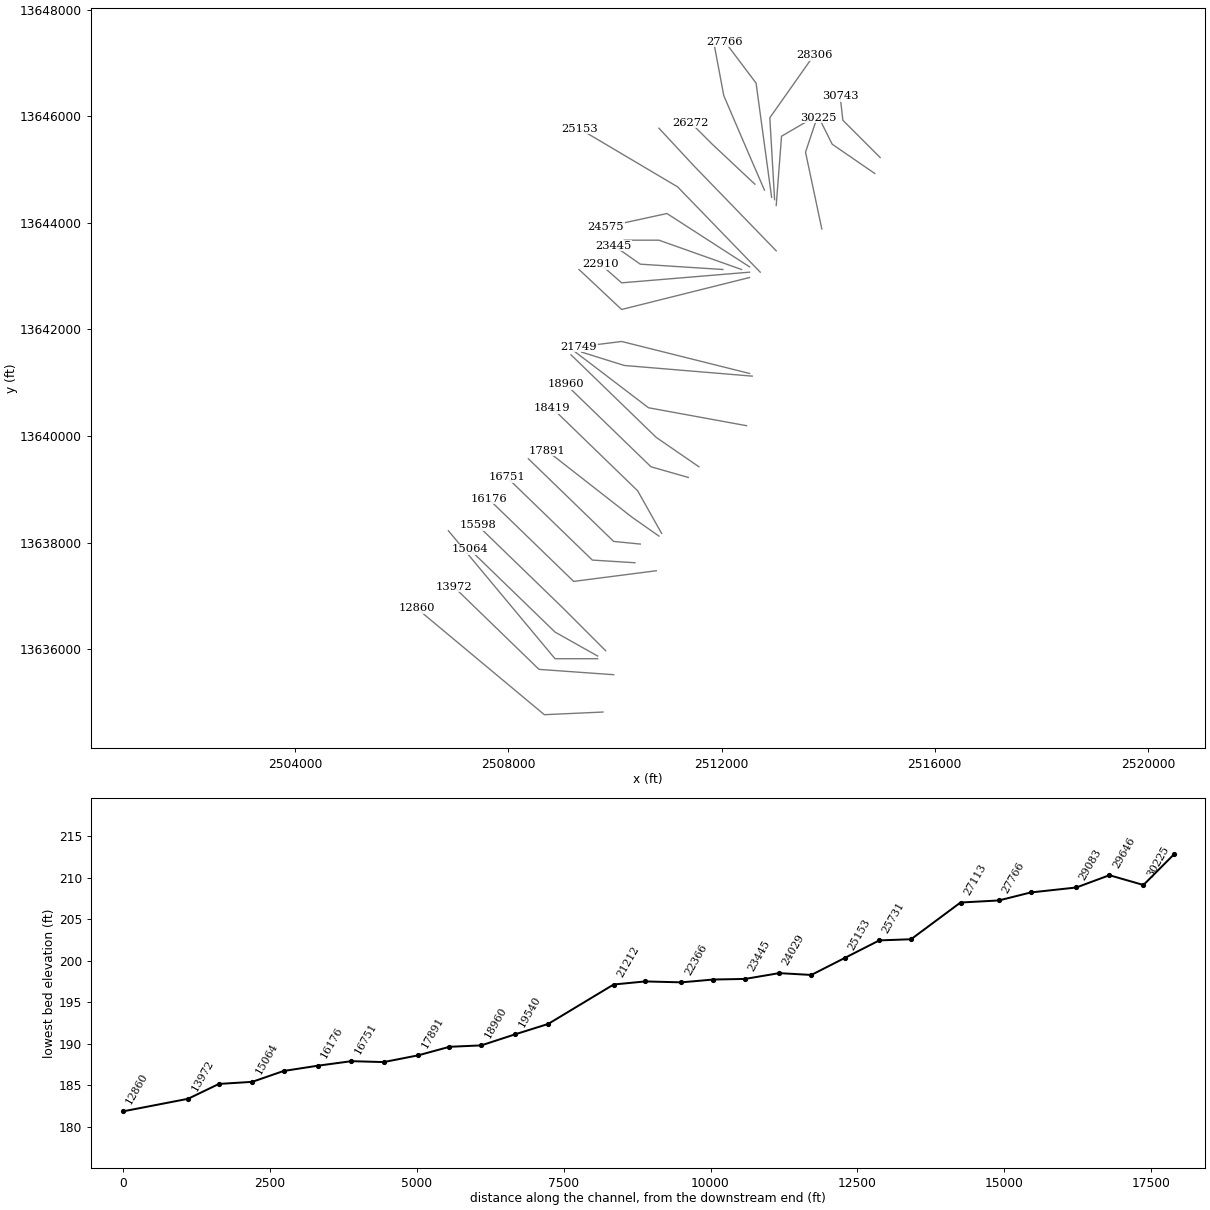
HEC-RAS study MCCOY CREEK.prj: MCCOY CREEK Base Level Engineering

--- MCCOY CREEK.g01 (geometry) --- (continued)

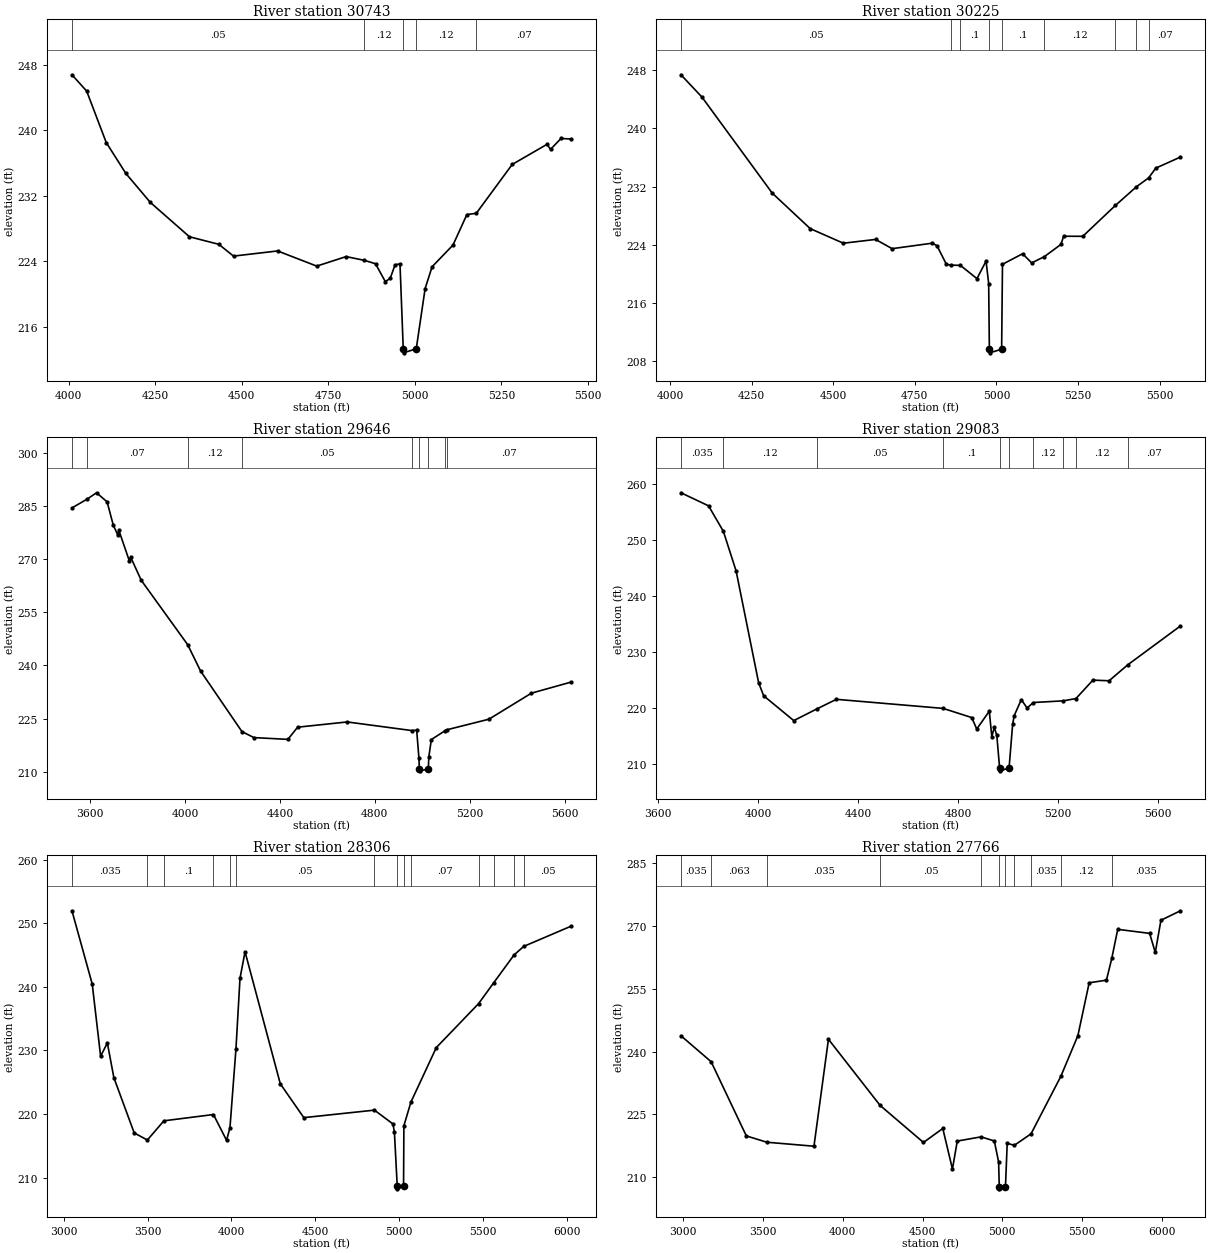
Type RM Length L Ch R = 1 ,30743   ,518,518,518
BEGIN DESCRIPTION:
MCCOY CREEK 38.0
END DESCRIPTION:
XS GIS Cut Line= 3
      2514975.03     13645224.97        2514275.       13645925.
        2514225.     13646375.04
#Sta/Elev= 30
  4009.7  246.75  4052.2  244.76  4108.7  238.48  4165.3  234.71    4236  231.17
  4349.2  226.97    4434  226.05  4476.4  224.61  4603.7  225.24  4716.8  223.39
  4801.7  224.55  4853.8   224.1  4886.6  223.68  4914.8   221.5    4929  221.89
  4943.1  223.55  4957.3  223.66  4966.7   213.3  4967.7   212.8  5004.3   213.3
  5029.9  220.65    5050  223.31  5110.4  225.96  5150.6  229.69  5177.6  229.83
  5281.4   235.8    5382  238.26  5392.1  237.64  5422.3  238.97  5452.5  238.91
#Mann= 5 ,-1 , 0
  4009.7     .05       0  4853.8     .12       0  4966.7     .05       0
  5004.3     .12       0  5177.6     .07       0
Bank Sta=4966.7,5004.3
XS Rating Curve= 0 ,0
Exp/Cntr=0.3,0.1

Type RM Length L Ch R = 1 ,30225   ,579,579,579
BEGIN DESCRIPTION:
MCCOY CREEK 37.0
END DESCRIPTION:
XS GIS Cut Line= 3
      2514875.03     13644924.98        2514075.       13645475.
      2513824.99     13645975.02
#Sta/Elev= 30
  4033.9  247.37  4098.2   244.3  4313.3   231.1  4429.7  226.21  4531.2   224.2
  4629.9  224.72  4680.7  223.45  4803.1   224.2    4818  223.87    4847  221.28
    4861  221.19  4889.8  221.15  4940.5  219.33  4968.4  221.74  4976.4  218.65
  4978.5  209.62  4979.5  209.12  5016.1  209.62  5018.7   221.3  5080.2  222.75
  5108.2  221.49  5147.2  222.36  5197.6  224.03    5206  225.16  5264.7  225.15
  5364.4  229.39  5429.1  231.97  5466.2  233.18  5488.3  234.53  5563.8  236.05
#Mann= 9 ,-1 , 0
  4033.9     .05       0    4861     .12       0  4889.8      .1       0
  4978.5     .05       0  5016.1      .1       0  5147.2     .12       0
  5364.4     .07       0  5429.1     .12       0  5466.2     .07       0
Bank Sta=4978.5,5016.1
XS Rating Curve= 0 ,0
Exp/Cntr=0.3,0.1

Type RM Length L Ch R = 1 ,29646   ,563,563,563
BEGIN DESCRIPTION:
MCCOY CREEK 36.0
END DESCRIPTION:
XS GIS Cut Line= 3
      2513880.67      13643884.8        2513575.       13645325.
      2513774.99     13645924.97
#Sta/Elev= 30
  3523.6   284.4  3586.8  286.86  3627.2  288.67  3671.7  286.11  3697.6  279.59
  3716.2  276.85  3721.3  278.08  3765.9  269.38    3771  270.53  3815.5  264.01
  4011.3  245.85  4065.6  238.43  4239.9  221.36  4290.5  219.67  4433.6  219.17
  4474.5   222.6  4683.4  224.08  4955.8  221.65  4976.2  221.75  4985.7  213.92
  4987.6   210.8  4988.6   210.3  5025.2   210.8  5027.5  214.25    5038  219.12
  5097.1  221.66    5105   221.9  5280.5  224.85  5459.7  232.19  5628.3  235.34
#Mann= 9 ,-1 , 0
  3523.6     .05       0  3586.8     .07       0  4011.3     .12       0
  4239.9     .05       0  4955.8     .07       0  4987.6     .05       0
  5025.2     .07       0  5097.1      .1       0    5105     .07       0
Bank Sta=4987.6,5025.2
XS Rating Curve= 0 ,0
Exp/Cntr=0.3,0.1

Type RM Length L Ch R = 1 ,29083   ,777,777,777
BEGIN DESCRIPTION:
MCCOY CREEK 35.0
END DESCRIPTION:
XS GIS Cut Line= 3
        2513025.     13644325.04        2513125.       13645625.
      2513724.98     13645974.99
#Sta/Elev= 30
    3692  258.47  3802.3  256.14  3861.6  251.59  3912.6  244.51  4002.9  224.51
  4022.9  222.22  4143.3  217.79    4235  219.86  4313.8  221.59  4740.8  219.97
  4855.4  218.33  4875.4  216.28  4925.6  219.47  4935.6  214.94  4945.7  216.58
  4955.7  215.14  4966.9  209.32  4967.9  208.82  5004.7  209.32    5019   217.1
  5025.2  218.67  5053.7  221.53  5076.8  220.04  5101.9  221.02  5222.2  221.32
  5272.4  221.73  5340.2  225.02  5404.7   224.9  5480.2  227.77  5690.4  234.69
#Mann= 10 ,-1 , 0
    3692    .035       0  3861.6     .12       0    4235     .05       0
  4740.8      .1       0  4966.9     .05       0  5004.7      .1       0
  5101.9     .12       0  5222.2     .07       0  5272.4     .12       0
  5480.2     .07       0
Bank Sta=4966.9,5004.7
XS Rating Curve= 0 ,0
Exp/Cntr=0.3,0.1

Type RM Length L Ch R = 1 ,28306   ,540,540,540
BEGIN DESCRIPTION:
B19352
END DESCRIPTION:
XS GIS Cut Line= 3
      2512994.81     13644434.27       2512905.1     13645970.53
      2513734.89     13647147.93
#Sta/Elev= 30
  3048.8  251.96  3169.7  240.44  3219.8  229.08  3259.9  231.17  3298.9   225.7
  3420.2  217.01  3498.7   215.9  3597.3  218.92  3892.8  219.91  3971.1  215.85
  3991.3  217.84  4027.1  230.24  4051.2  241.34  4081.3  245.51  4291.6  224.74
  4431.9  219.42  4853.1   220.6  4963.5  218.43  4972.2  217.14  4988.9  208.72
  4989.9  208.22  5026.8  208.72  5028.8  218.14  5070.6  221.86  5222.1  230.44
  5474.5  237.36  5564.7  240.64  5686.1  245.02    5744  246.36  6028.1  249.56
#Mann= 14 ,-1 , 0
  3048.8    .035       0  3498.7     .12       0  3597.3      .1       0
  3892.8     .05       0  3991.3      .1       0  4027.1     .05       0
  4853.1      .1       0  4988.9     .05       0  5026.8      .1       0
  5070.6     .07       0  5474.5     .05       0  5564.7    .035       0
  5686.1     .12       0    5744     .05       0
Bank Sta=4988.9,5026.8
XS Rating Curve= 0 ,0
Exp/Cntr=0.3,0.1

Type RM Length L Ch R = 1 ,27766   ,653,653,653
BEGIN DESCRIPTION:
B19351
END DESCRIPTION:
XS GIS Cut Line= 3
      2512938.75     13644479.13      2512647.19      13646620.9
      2512064.08     13647394.65
#Sta/Elev= 30
  2985.7  243.78  3174.6   237.6  3395.3  219.89  3524.1  218.38  3819.2  217.43
    3910  242.95  4233.9  227.16  4505.5  218.33  4626.6  221.66  4687.1  211.98
  4717.4  218.66  4866.2  219.66  4949.5  218.69  4976.5  213.69  4980.5  207.76
  4981.5  207.26  5019.5  207.76  5030.3  218.13  5074.9  217.64  5179.8  220.39
  5366.8  234.13  5473.3  243.81  5544.1  256.43  5652.3  257.05  5685.6  262.23
  5723.1  269.18    5923  268.22  5958.4  263.66  5993.8  271.35  6116.1  273.61
#Mann= 11 ,-1 , 0
  2985.7    .035       0  3174.6    .063       0  3524.1    .035       0
  4233.9     .05       0  4866.2      .1       0  4980.5     .05       0
  5019.5      .1       0  5074.9     .12       0  5179.8    .035       0
  5366.8     .12       0  5685.6    .035       0
Bank Sta=4980.5,5019.5
XS Rating Curve= 0 ,0
Exp/Cntr=0.3,0.1

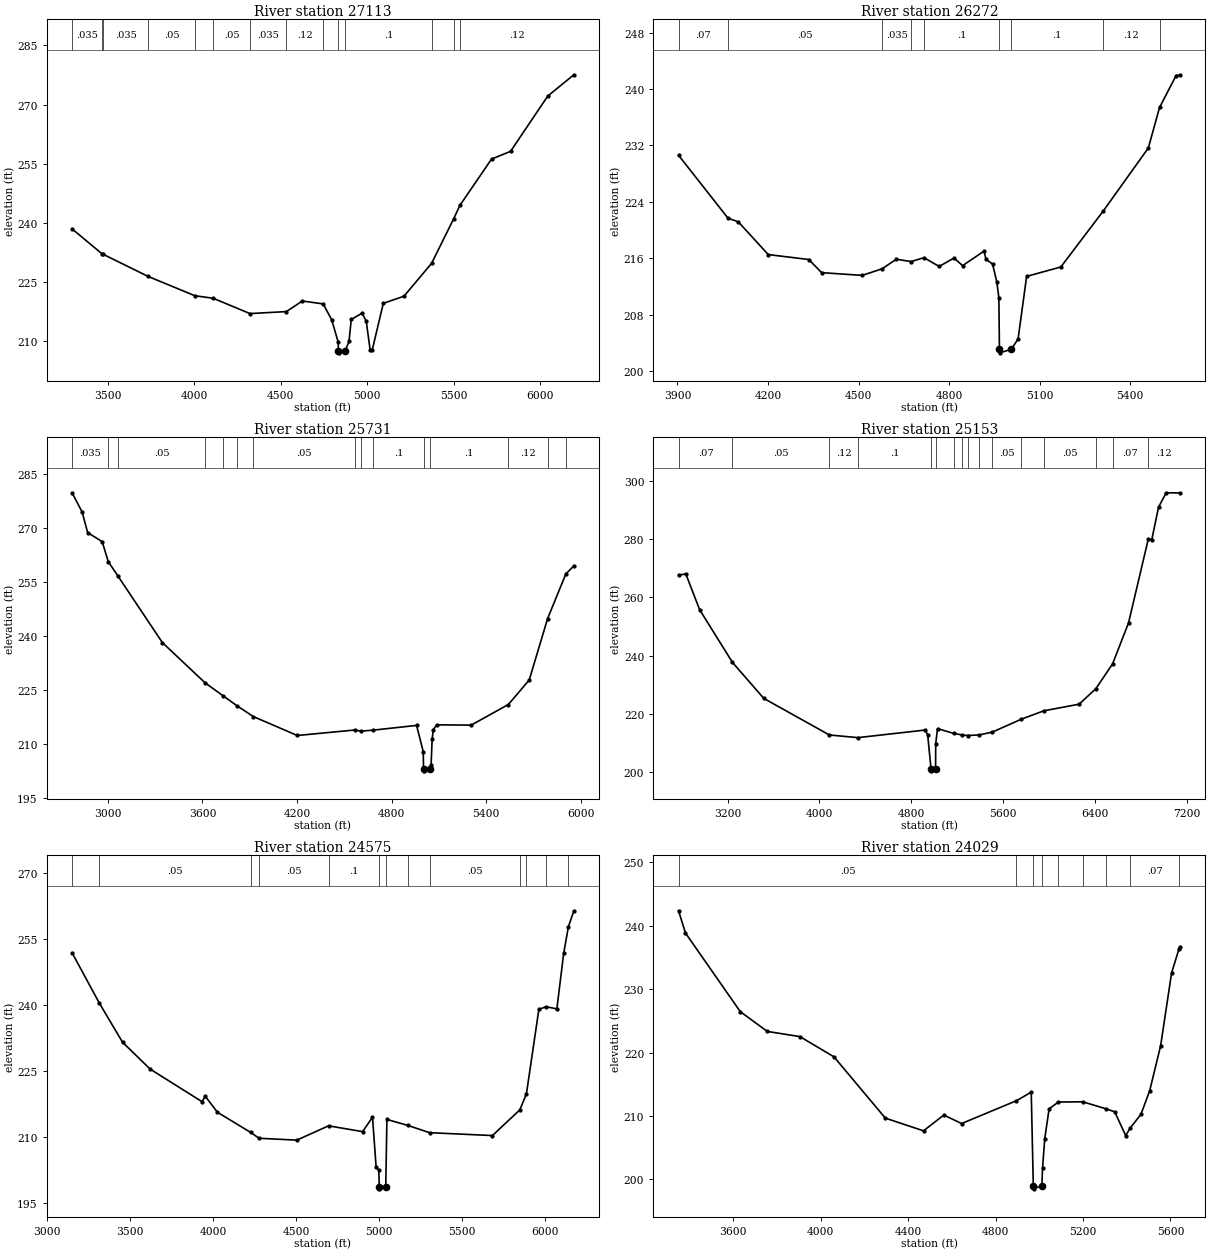
Type RM Length L Ch R = 1 ,27113   ,841,841,841
BEGIN DESCRIPTION:
B19350
END DESCRIPTION:
XS GIS Cut Line= 4
      2512804.17     13644613.74      2512411.71     13645521.99
      2512041.67     13646385.42      2511862.25     13647338.58
#Sta/Elev= 30
  3295.1  238.45  3469.7  232.07  3474.4  232.01    3735  226.38  4004.4   221.5
  4110.4  220.85  4322.4  216.97  4533.1  217.47  4625.1  220.16    4746  219.42
  4795.1  215.36  4831.8  209.83    4834  207.51    4835  207.01    4873  207.51
  4894.9  209.92  4907.9  215.48    4971  217.09  4994.6     215  5016.7  207.83
  5029.1  207.73  5092.9  219.56  5212.6  221.38  5372.1  229.72  5499.1  240.98
    5536  244.45  5718.2  256.15  5828.2  258.12  6043.2  272.15  6193.8  277.54
#Mann= 14 ,-1 , 0
  3295.1    .035       0  3469.7     .07       0  3474.4    .035       0
    3735     .05       0  4004.4    .035       0  4110.4     .05       0
  4322.4    .035       0  4533.1     .12       0    4746      .1       0
    4834     .05       0    4873      .1       0  5372.1     .12       0
  5499.1      .1       0    5536     .12       0
Bank Sta=4834,4873
XS Rating Curve= 0 ,0
Exp/Cntr=0.3,0.1

Type RM Length L Ch R = 1 ,26272   ,541,541,541
BEGIN DESCRIPTION:
MCCOY CREEK 31.0
END DESCRIPTION:
XS GIS Cut Line= 3
      2512624.98     13644725.02        2511825.       13645475.
      2511425.03     13645874.97
#Sta/Elev= 30
  3903.7   230.6  4067.6  221.68  4101.7  221.16  4200.9  216.52  4335.2  215.82
  4377.7  213.96    4512  213.57  4578.2  214.51  4625.4  215.86  4674.1  215.53
  4716.7  216.08    4767  214.84  4816.3  216.03  4844.7  214.95  4915.5  217.01
  4922.3  215.85  4943.8  215.19    4958  212.65  4964.8  210.41  4966.7  203.09
  4967.7  202.59  5005.9  203.09  5028.5  204.56  5056.8  213.43    5170  214.76
  5310.3  222.68  5459.9  231.63  5497.1  237.38  5551.8  241.89  5565.9  242.01
#Mann= 9 ,-1 , 0
  3903.7     .07       0  4067.6     .05       0  4578.2    .035       0
  4674.1     .12       0  4716.7      .1       0  4966.7     .05       0
  5005.9      .1       0  5310.3     .12       0  5497.1     .07       0
Bank Sta=4966.7,5005.9
XS Rating Curve= 0 ,0
Exp/Cntr=0.3,0.1

Type RM Length L Ch R = 1 ,25731   ,578,578,578
BEGIN DESCRIPTION:
MCCOY CREEK 30.0
END DESCRIPTION:
XS GIS Cut Line= 3
      2513024.99     13643475.01        2511475.       13645075.
        2510825.     13645774.99
#Sta/Elev= 30
  2772.8   279.7  2836.5  274.37  2871.7  268.63  2963.8  266.13  3002.3  260.58
  3063.5  256.58  3345.5  238.09  3615.8  226.93  3730.6   223.3  3819.4  220.51
    3923  217.52  4201.4  212.27  4567.4   213.8  4604.5  213.47  4683.7  213.76
  4958.1  215.07  5000.5  207.75  5002.1  202.95  5003.1  202.45  5041.3  202.95
  5050.1  204.08  5056.9  211.33  5064.2  213.87  5085.2  215.23  5304.6  215.15
  5540.2  220.88  5672.5  227.68  5789.2  244.75  5904.8  257.15  5955.7  259.39
#Mann= 15 ,-1 , 0
  2772.8    .035       0  3002.3     .07       0  3063.5     .05       0
  3615.8     .07       0  3730.6     .05       0  3819.4     .07       0
    3923     .05       0  4567.4    .035       0  4604.5     .05       0
  4683.7      .1       0  5002.1     .05       0  5041.3      .1       0
  5540.2     .12       0  5789.2     .07       0  5904.8     .12       0
Bank Sta=5002.1,5041.3
XS Rating Curve= 0 ,0
Exp/Cntr=0.3,0.1

Type RM Length L Ch R = 1 ,25153   ,578,578,578
BEGIN DESCRIPTION:
MCCOY CREEK 29.0
END DESCRIPTION:
XS GIS Cut Line= 3
      2512725.03     13643074.97        2511175.       13644675.
      2509328.98     13645768.12
#Sta/Elev= 30
  2772.3  267.69    2836  268.06  2956.1  255.79    3242  237.67  3514.9  225.29
  4086.8   212.7  4335.4  211.79  4922.2   214.4  4943.5  212.73  4973.3  200.87
  4974.3  200.37  5012.5  200.87  5013.6  209.68  5029.3  214.89  5171.3  213.23
  5246.4  212.68  5295.7  212.52    5394  212.73  5506.9  213.69  5756.4  218.07
  5956.2  221.02  6263.4  223.28  6409.3  228.62  6555.1  237.15  6694.3  251.28
  6866.1  280.03  6897.1  279.91  6955.5  291.04  7022.2  295.98  7145.4  295.93
#Mann= 16 ,-1 , 0
  2772.3     .07       0    3242     .05       0  4086.8     .12       0
  4335.4      .1       0  4973.3     .05       0  5012.5      .1       0
  5171.3     .12       0  5246.4     .07       0  5295.7     .05       0
    5394     .07       0  5506.9     .05       0  5756.4    .035       0
  5956.2     .05       0  6409.3     .12       0  6555.1     .07       0
  6866.1     .12       0
Bank Sta=4973.3,5012.5
XS Rating Curve= 0 ,0
Exp/Cntr=0.3,0.1

Type RM Length L Ch R = 1 ,24575   ,546,546,546
BEGIN DESCRIPTION:
MCCOY CREEK 28.0
END DESCRIPTION:
XS GIS Cut Line= 3
      2512524.97     13643175.02        2510975.       13644175.
      2509825.02       13643925.
#Sta/Elev= 30
  3150.1  251.89    3315  240.41    3454  231.58  3620.3  225.48  3931.8   218.1
  3952.9  219.26  4025.5  215.68    4225  211.11    4276  209.77  4503.3  209.35
  4694.4   212.6  4899.5  211.28    4959  214.55  4981.1  203.18  4997.2  202.56
  4999.6  198.79  5000.6  198.29  5038.8  198.79  5045.8  214.05  5172.9  212.68
  5303.2  211.04  5681.3  210.39  5846.3  216.23  5885.9  219.87  5960.7  239.02
  6003.2  239.65  6069.2  239.16  6110.1  251.73  6138.6  257.81  6171.5  261.43
#Mann= 13 ,-1 , 0
  3150.1     .07       0    3315     .05       0    4225     .07       0
    4276     .05       0  4694.4      .1       0  4999.6     .05       0
  5038.8      .1       0  5172.9     .07       0  5303.2     .05       0
  5846.3     .07       0  5885.9     .12       0  6003.2     .07       0
  6138.6     .12       0
Bank Sta=4999.6,5038.8
XS Rating Curve= 0 ,0
Exp/Cntr=0.3,0.1

Type RM Length L Ch R = 1 ,24029   ,584,584,584
BEGIN DESCRIPTION:
MCCOY CREEK 27.0
END DESCRIPTION:
XS GIS Cut Line= 3
      2512375.01       13643125.        2510825.       13643675.
        2510175.       13643675.
#Sta/Elev= 30
  3350.3  242.37  3382.1  238.86  3632.9  226.45  3756.4  223.34  3905.5  222.52
  4061.2  219.33  4296.1  209.66  4470.7  207.66  4563.3  210.15  4644.8  208.81
  4895.6  212.41  4963.2  213.76  4972.7  199.01  4973.7  198.51  5011.9  199.01
    5015  201.84    5025  206.43    5045  211.13  5087.1   212.2    5199  212.24
  5304.4  211.14    5345  210.66    5395  206.92  5415.6  208.09    5465  210.27
    5505     214    5555  221.09    5605  232.56  5638.4  236.31    5645  236.73
#Mann= 9 ,-1 , 0
  3350.3     .05       0  4895.6      .1       0  4972.7     .05       0
  5011.9      .1       0  5087.1     .07       0    5199     .05       0
  5304.4      .1       0  5415.6     .07       0  5638.4     .12       0
Bank Sta=4972.7,5011.9
XS Rating Curve= 0 ,0
Exp/Cntr=0.3,0.1

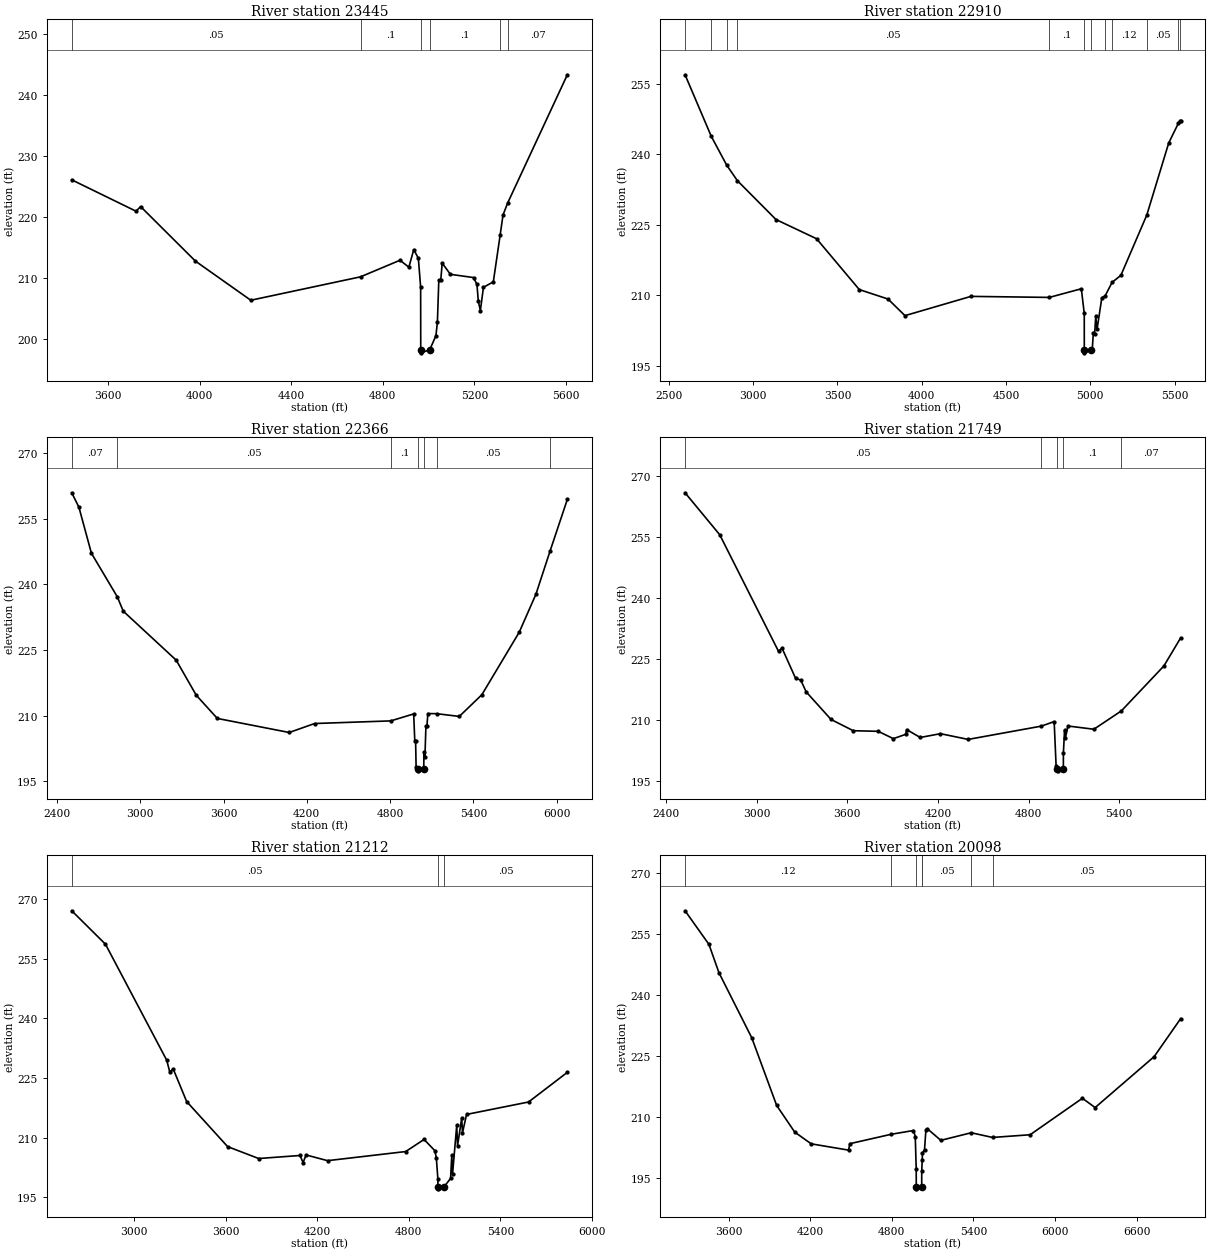
Type RM Length L Ch R = 1 ,23445   ,535,535,535
BEGIN DESCRIPTION:
MCCOY CREEK 26.0
END DESCRIPTION:
XS GIS Cut Line= 3
      2512025.02       13643125.        2510475.       13643225.
      2509974.97     13643575.02
#Sta/Elev= 30
  3441.9   226.1  3722.5  220.97  3742.5  221.73  3981.8  212.81  4223.5  206.41
  4702.7  210.24  4874.9  212.95  4913.7  211.82    4935  214.69  4955.1  213.27
  4965.1  208.56  4965.5  198.31  4966.5  197.81  5004.7  198.31  5031.8  200.61
  5038.3  202.84  5044.4   209.7  5053.1  209.76  5059.2  212.48    5095  210.65
  5196.1  210.12  5210.9  208.99    5217  206.22  5225.8  204.72  5239.3  208.52
  5282.4  209.42  5312.3  217.09  5324.7  220.34  5345.4  222.35  5605.5  243.28
#Mann= 6 ,-1 , 0
  3441.9     .05       0  4702.7      .1       0  4965.5     .05       0
  5004.7      .1       0  5312.3     .12       0  5345.4     .07       0
Bank Sta=4965.5,5004.7
XS Rating Curve= 0 ,0
Exp/Cntr=0.3,0.1

Type RM Length L Ch R = 1 ,22910   ,544,544,544
BEGIN DESCRIPTION:
MCCOY CREEK 25.0
END DESCRIPTION:
XS GIS Cut Line= 3
      2512525.04       13643075.        2510125.       13642875.
      2509724.97     13643225.02
#Sta/Elev= 30
  2596.2  256.94  2751.6  243.84    2843  237.71  2906.4   234.4  3135.6  226.12
  3376.4  222.03  3629.8  211.21  3800.4  209.19  3900.7  205.66  4292.1  209.76
  4756.7  209.54  4946.9  211.38  4964.4  206.13  4964.6  198.24  4965.6  197.74
  5004.3  198.24  5011.7  198.33  5018.3  202.06  5025.9  201.78  5032.6  205.55
  5040.1  202.71  5068.6  209.47  5087.8  209.84  5129.4  212.74  5181.6  214.24
  5335.1  227.05  5465.4  242.42  5522.5   246.6  5531.5  247.03  5536.1  247.17
#Mann= 12 ,-1 , 0
  2596.2     .07       0  2751.6     .05       0    2843     .07       0
  2906.4     .05       0  4756.7      .1       0  4964.6     .05       0
  5004.3      .1       0  5087.8     .05       0  5129.4     .12       0
  5335.1     .05       0  5522.5     .07       0  5531.5     .12       0
Bank Sta=4964.6,5004.3
XS Rating Curve= 0 ,0
Exp/Cntr=0.3,0.1

Type RM Length L Ch R = 1 ,22366   ,617,617,617
BEGIN DESCRIPTION:
MCCOY CREEK 24.0
END DESCRIPTION:
XS GIS Cut Line= 3
      2512525.02       13642975.        2510125.       13642375.
      2509324.98     13643125.02
#Sta/Elev= 30
  2506.7  260.92  2558.3  257.62  2648.4   247.1  2834.9  237.15  2877.8  233.87
  3259.2  222.68  3403.5  214.68  3555.5  209.37  4073.5  206.16  4256.5  208.21
  4804.8  208.81  4970.3   210.4    4978   204.3    4984   204.3  4987.7  198.24
    5003   197.9    5004   197.4  5042.7   197.9  5044.3  201.73  5051.2  200.57
  5058.5  207.69  5065.3  207.57  5072.6  210.48  5134.8  210.46  5298.8  209.83
  5461.5  214.79  5730.6  229.06  5850.8  237.73  5952.4  247.57  6077.2   259.4
#Mann= 7 ,-1 , 0
  2506.7     .07       0  2834.9     .05       0  4804.8      .1       0
    5003     .05       0  5042.7      .1       0  5134.8     .05       0
  5952.4     .07       0
Bank Sta=5003,5042.7
XS Rating Curve= 0 ,0
Exp/Cntr=0.3,0.1

Type RM Length L Ch R = 1 ,21749   ,537,537,537
BEGIN DESCRIPTION:
MCCOY CREEK 23.0
END DESCRIPTION:
XS GIS Cut Line= 3
      2512525.04     13641174.99        2510125.       13641775.
      2509325.03       13641675.
#Sta/Elev= 30
  2526.5  265.91  2755.9  255.59    3145  226.91  3168.2   227.7  3258.4  220.23
  3291.9  219.86    3328  216.94  3492.9  210.14  3639.8  207.38  3804.7  207.23
  3905.2  205.43  3987.7   206.5  3992.8  207.66    4083  205.72    4217  206.65
    4400  205.24  4884.9  208.51  4969.5  209.63  4982.4  198.69  4990.6  198.01
  4991.6  197.51  5030.3  198.01  5030.6  201.91  5038.2  207.44  5043.2   205.5
  5060.9  208.54  5232.2  207.74  5414.2  212.25  5695.8  223.31  5806.6  230.21
#Mann= 5 ,-1 , 0
  2526.5     .05       0  4884.9      .1       0  4990.6     .05       0
  5030.3      .1       0  5414.2     .07       0
Bank Sta=4990.6,5030.3
XS Rating Curve= 0 ,0
Exp/Cntr=0.3,0.1

Type RM Length L Ch R = 1 ,21212   ,1114,1114,1114
BEGIN DESCRIPTION:
MCCOY CREEK 22.0
END DESCRIPTION:
XS GIS Cut Line= 3
      2512575.04       13641125.        2510175.       13641325.
      2509375.01       13641575.
#Sta/Elev= 30
  2591.6  267.01  2812.4  258.61  3213.8  229.45  3233.9  226.47  3256.4  227.25
  3344.2  219.08  3612.7  207.75  3815.9  204.76  4086.8  205.52  4106.9  203.75
  4126.9  205.65  4267.4  204.22  4779.2  206.51  4899.6  209.55  4969.9  206.74
  4979.9  204.95  4989.9   199.7  4990.5  197.64  4991.5  197.14  5030.3  197.64
  5073.3  199.76  5081.2  205.56  5086.4  200.98  5113.6  213.09  5118.9  207.97
  5146.1  214.91  5151.3  211.24  5178.1  215.84    5584  218.96  5838.1  226.41
#Mann= 3 ,-1 , 0
  2591.6     .05       0  4990.5     .05       0  5030.3     .05       0
Bank Sta=4990.5,5030.3
XS Rating Curve= 0 ,0
Exp/Cntr=0.3,0.1

Type RM Length L Ch R = 1 ,20098   ,558,558,558
BEGIN DESCRIPTION:
B19349
END DESCRIPTION:
XS GIS Cut Line= 3
      2512467.78     13640195.63      2510628.78     13640532.03
      2509215.86     13641608.54
#Sta/Elev= 30
  3278.9  260.61  3454.5  252.37  3528.1  245.42  3769.7  229.44  3952.7  212.85
  4085.6  206.31  4206.8  203.43  4481.3  201.89  4491.5  203.47  4795.9  205.78
  4959.1   206.7  4972.4  205.23  4979.4  197.34  4979.9  192.89  4980.9  192.39
  5019.7  192.89  5020.1  196.79  5023.3  199.36  5025.6  201.21  5040.4  201.97
  5050.6  206.78  5060.8  207.15  5160.5  204.29  5384.1  206.15  5540.8     205
  5817.4  205.66    6202  214.61  6295.5  212.33    6730  224.83  6924.7  234.14
#Mann= 7 ,-1 , 0
  3278.9     .12       0  4795.9      .1       0  4979.9     .05       0
  5019.7      .1       0  5023.3     .05       0  5384.1    .035       0
  5540.8     .05       0
Bank Sta=4979.9,5019.7
XS Rating Curve= 0 ,0
Exp/Cntr=0.3,0.1

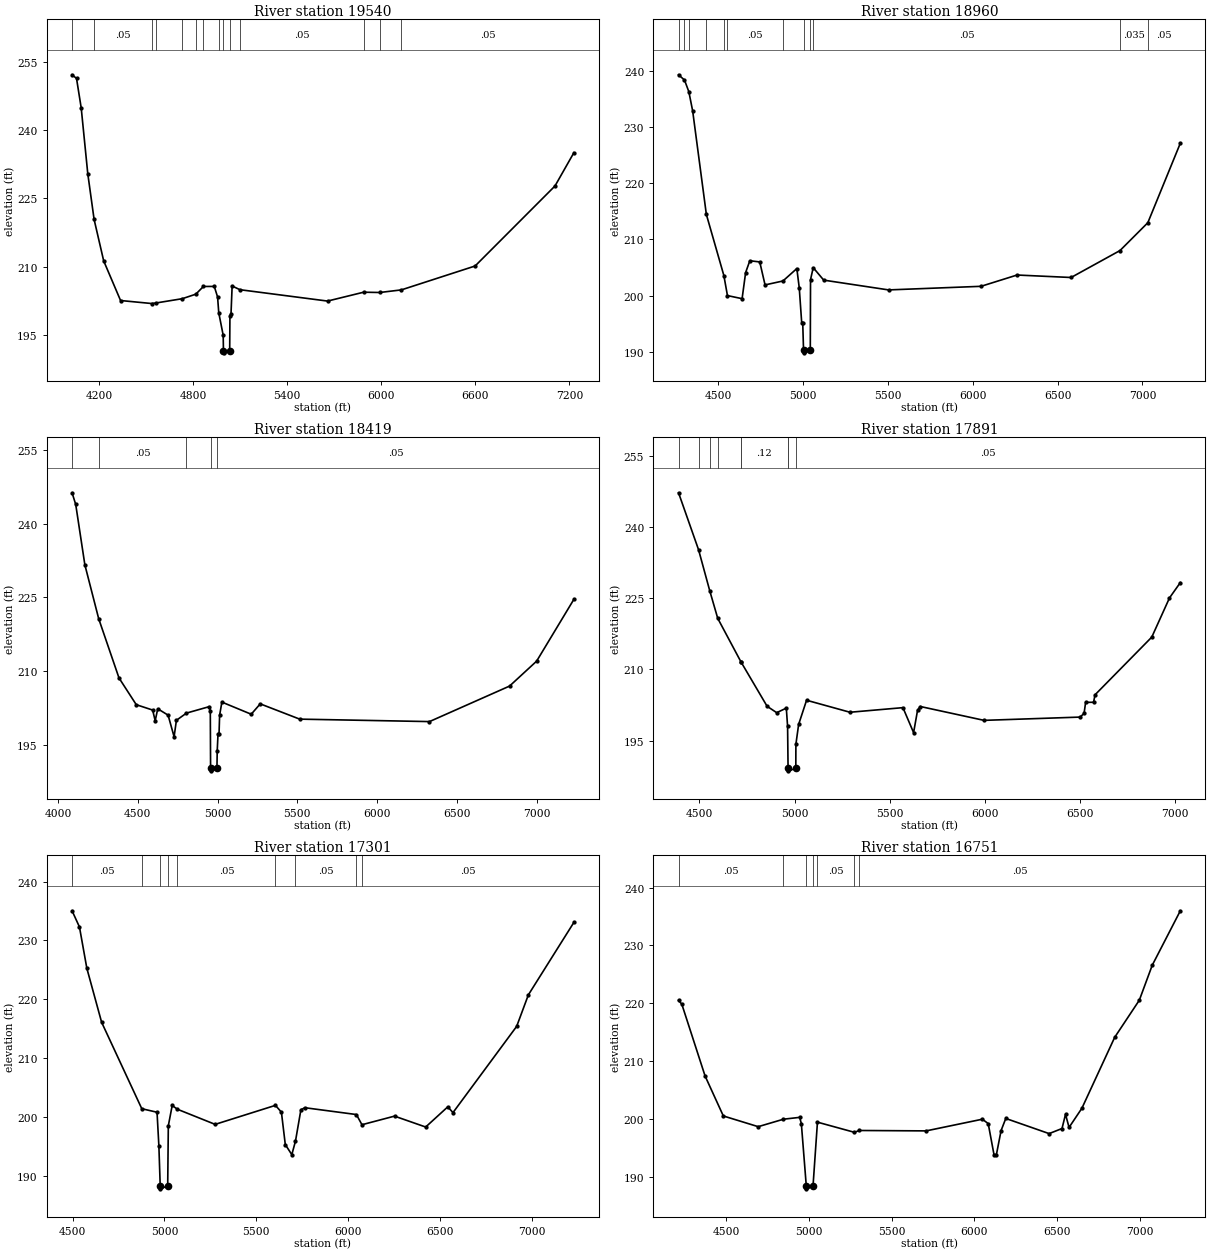
Type RM Length L Ch R = 1 ,19540   ,580,580,580
BEGIN DESCRIPTION:
MCCOY CREEK 21.0
END DESCRIPTION:
XS GIS Cut Line= 3
      2511574.97     13639425.02        2510775.       13639975.
      2509174.97     13641525.03
#Sta/Elev= 30
  4029.3  252.11  4057.7  251.31  4087.5  244.86  4129.4  230.43  4169.8  220.39
  4230.9   211.3  4338.4  202.62  4537.3  201.96  4564.3  202.08  4731.7  203.02
  4818.1  204.01  4866.5   205.7  4935.8  205.71  4956.8   203.4  4964.3  199.94
  4992.6     195  4994.2  191.65  4995.2  191.15    5034  191.65  5035.5  199.23
  5042.4  199.69  5049.6   205.8  5099.5  204.99  5657.7   202.5  5887.4  204.44
  5990.6  204.38  6128.2  204.95  6598.4  210.19  7107.5  227.73  7227.8  235.02
#Mann= 14 ,-1 , 0
  4029.3     .12       0  4169.8     .05       0  4537.3      .1       0
  4564.3     .05       0  4731.7     .12       0  4818.1     .05       0
  4866.5     .12       0  4964.3      .1       0  4994.2     .05       0
    5034      .1       0  5099.5     .05       0  5887.4     .07       0
  5990.6    .035       0  6128.2     .05       0
Bank Sta=4994.2,5034
XS Rating Curve= 0 ,0
Exp/Cntr=0.3,0.1

Type RM Length L Ch R = 1 ,18960   ,541,541,541
BEGIN DESCRIPTION:
MCCOY CREEK 20.0
END DESCRIPTION:
XS GIS Cut Line= 3
      2511374.99       13639225.        2510675.       13639425.
      2509074.97     13640975.02
#Sta/Elev= 30
  4267.5   239.3  4302.6  238.36  4328.2  236.29  4350.7  232.87  4431.4  214.44
  4534.5  203.57  4555.6     200  4641.9  199.45  4662.7   204.1  4687.4   206.2
  4745.9  205.99  4777.1   201.9  4882.5   202.6  4964.3  204.81  4978.6  201.37
  4992.9   195.2    4999   195.2  5003.8  190.31  5004.8  189.81  5043.6  190.31
    5045  202.85  5060.8  204.97  5122.7  202.75  5504.7  201.01  6049.3  201.65
  6261.5  203.66  6579.7  203.22  6867.6  208.01  7031.8  212.97  7223.2  227.12
#Mann= 12 ,-1 , 0
  4267.5     .05       0  4302.6     .12       0  4328.2     .05       0
  4431.4      .1       0  4534.5     .07       0  4555.6     .05       0
  4882.5      .1       0  5003.8     .05       0  5043.6      .1       0
  5060.8     .05       0  6867.6    .035       0  7031.8     .05       0
Bank Sta=5003.8,5043.6
XS Rating Curve= 0 ,0
Exp/Cntr=0.3,0.1

Type RM Length L Ch R = 1 ,18419   ,528,528,528
BEGIN DESCRIPTION:
MCCOY CREEK 19.0
END DESCRIPTION:
XS GIS Cut Line= 3
      2510874.98     13638175.03        2510425.       13638975.
      2508825.01     13640524.99
#Sta/Elev= 30
  4087.7  246.27  4110.6  243.89    4168  231.58  4254.7  220.61  4381.8  208.56
  4490.2  203.11  4592.8  202.02  4608.8  199.84  4624.7  202.28  4689.7  200.98
  4727.3  196.58  4741.7  199.93  4804.9   201.4  4948.2  202.72  4954.2  201.91
    4956  190.14    4957  189.64  4995.8  190.14  4997.6  193.72  5002.7   197.2
    5009   197.2  5012.6  200.96  5026.8  203.64  5210.7  201.17  5267.3  203.28
  5514.7  200.17  6328.1  199.67    6830   206.9  6999.8  211.98  7233.2  224.56
#Mann= 5 ,-1 , 0
  4087.7     .12       0  4254.7     .05       0  4804.9      .1       0
    4956     .05       0  4995.8     .05       0
Bank Sta=4956,4995.8
XS Rating Curve= 0 ,0
Exp/Cntr=0.3,0.1

Type RM Length L Ch R = 1 ,17891   ,590,590,590
BEGIN DESCRIPTION:
MCCOY CREEK 18.0
END DESCRIPTION:
XS GIS Cut Line= 3
      2510825.03     13638124.98        2510325.       13638475.
      2508724.97     13639725.03
#Sta/Elev= 30
  4389.7  247.23  4495.2  235.21    4554  226.57    4596  220.76  4718.6  211.56
  4719.1  211.53  4855.8  202.23  4906.3  200.88  4956.9  201.84  4963.6  198.02
  4966.2  189.12  4967.2  188.62  5006.9  189.12  5007.3  194.21  5021.8  198.41
  5063.5   203.5  5291.9  200.97  5570.7  201.94  5626.8  196.67  5647.6  201.39
  5662.1  202.18  5997.6  199.26  6503.2  199.95    6524  200.74  6532.1  203.06
  6573.7  203.07  6581.9  204.66  6880.3  216.81  6973.5  225.07  7030.5   228.3
#Mann= 9 ,-1 , 0
  4389.7     .12       0  4495.2     .07       0    4554     .05       0
    4596     .07       0  4718.6     .05       0  4719.1     .12       0
  4963.6     .05       0  4966.2     .05       0  5006.9     .05       0
Bank Sta=4966.2,5006.9
XS Rating Curve= 0 ,0
Exp/Cntr=0.3,0.1

Type RM Length L Ch R = 1 ,17301   ,550,550,550
BEGIN DESCRIPTION:
MCCOY CREEK 17.0
END DESCRIPTION:
XS GIS Cut Line= 3
      2510474.98       13637975.        2509975.       13638025.
      2508375.03     13639574.97
#Sta/Elev= 30
  4497.5  235.03  4537.7  232.28  4577.9  225.26  4658.3  216.09  4876.8  201.41
  4959.8  200.81  4969.8  195.09  4977.1   188.3  4978.1   187.8  5017.8   188.3
  5021.2  198.51  5042.3  201.96  5070.5  201.32  5275.9  198.75    5604  201.98
  5636.5  200.82  5657.6  195.32  5693.1  193.61  5713.1  195.92  5742.5  201.23
  5763.8  201.58  6044.5  200.42  6074.7  198.69  6251.8  200.15  6421.4   198.3
  6541.7  201.73    6570  200.75  6916.5   215.4  6980.1  220.75  7227.6  233.05
#Mann= 9 ,-1 , 0
  4497.5     .05       0  4876.8      .1       0  4977.1     .05       0
  5017.8      .1       0  5070.5     .05       0    5604      .1       0
  5713.1     .05       0  6044.5      .1       0  6074.7     .05       0
Bank Sta=4977.1,5017.8
XS Rating Curve= 0 ,0
Exp/Cntr=0.3,0.1

Type RM Length L Ch R = 1 ,16751   ,575,575,575
BEGIN DESCRIPTION:
MCCOY CREEK 16.0
END DESCRIPTION:
XS GIS Cut Line= 3
        2510375.       13637625.        2509575.       13637675.
      2507975.02     13639224.98
#Sta/Elev= 30
  4213.4  220.52  4233.4  219.82  4373.7  207.42  4483.9  200.51  4694.3  198.66
    4847  199.95  4944.8  200.27  4954.8  199.18  4984.6  188.41  4985.6  187.91
  5025.3  188.41    5052  199.44  5275.6  197.68  5304.1     198  5708.1  197.93
  6047.4  199.95  6082.9  199.19  6118.1  193.77  6132.3  193.82  6160.6  197.99
  6188.9  200.08  6450.5  197.46  6528.4  198.34  6549.5   200.8  6570.9  198.53
  6648.5  201.85  6846.6  214.12  6995.1  220.53    7073  226.57  7242.6  235.99
#Mann= 7 ,-1 , 0
  4213.4     .05       0    4847      .1       0  4984.6     .05       0
  5025.3      .1       0    5052     .05       0  5275.6     .07       0
  5304.1     .05       0
Bank Sta=4984.6,5025.3
XS Rating Curve= 0 ,0
Exp/Cntr=0.3,0.1

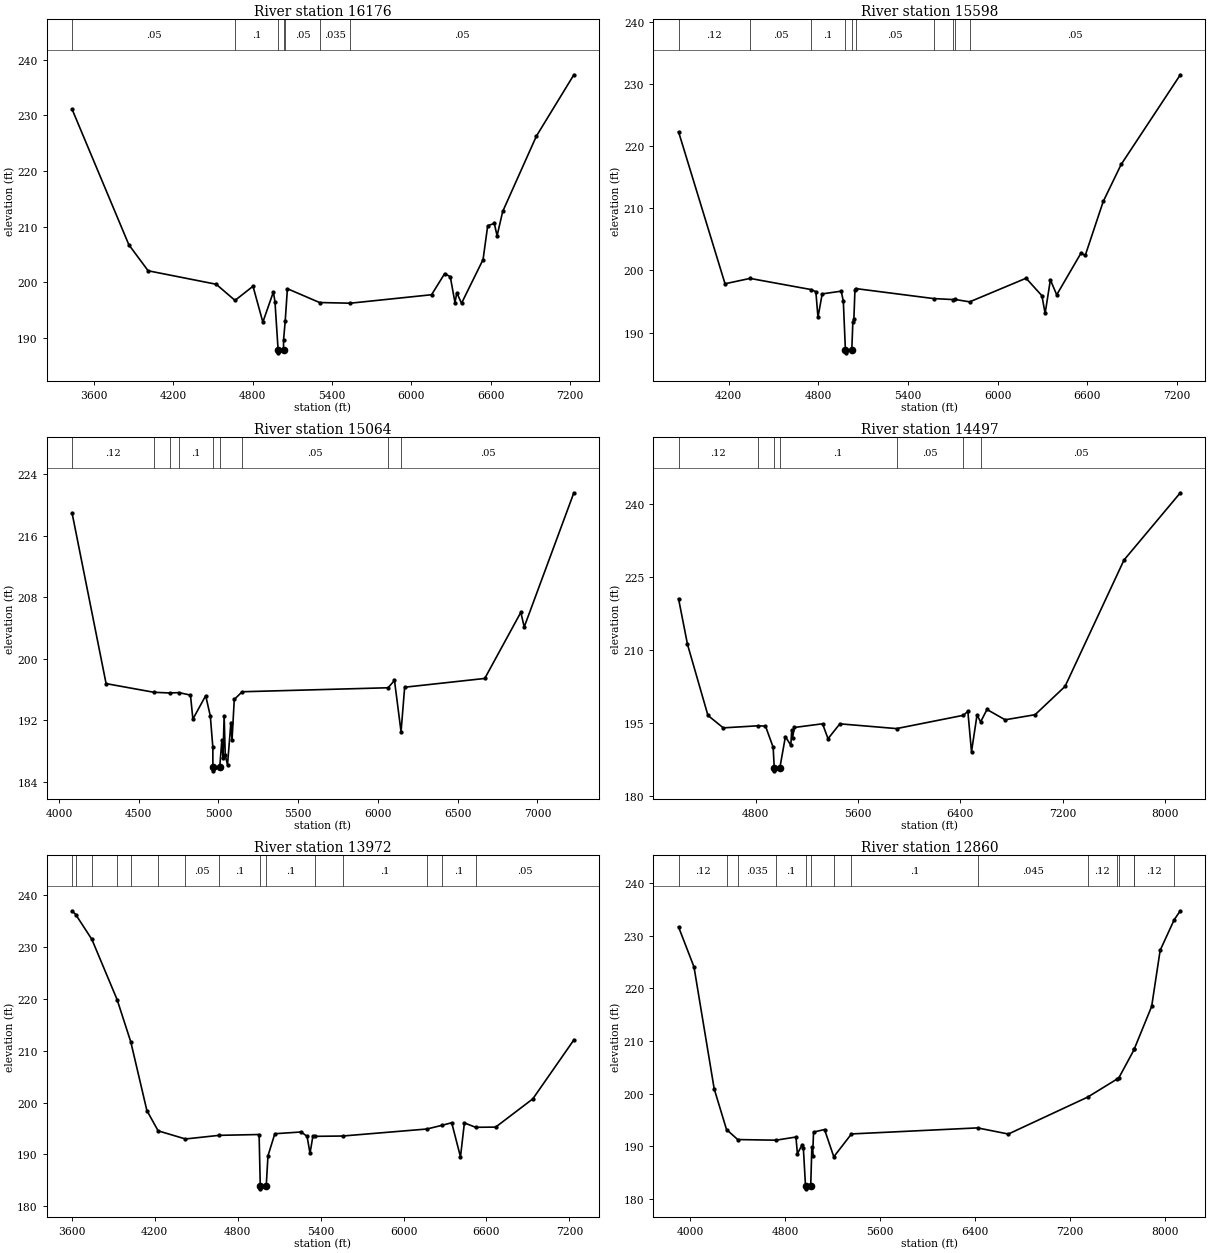
Type RM Length L Ch R = 1 ,16176   ,578,578,578
BEGIN DESCRIPTION:
MCCOY CREEK 15.0
END DESCRIPTION:
XS GIS Cut Line= 3
      2510774.98       13637475.        2509225.       13637275.
        2507625.       13638825.
#Sta/Elev= 30
  3436.6  231.09  3865.7  206.75  4011.3  202.09  4525.5  199.67  4667.5  196.77
  4803.4  199.31  4877.8  192.87  4957.2  198.28  4969.2  196.57  4993.1  187.86
  4994.1  187.36  5033.8  187.86  5034.2  189.69  5046.8  193.09  5063.1  198.87
  5306.3  196.39  5538.1  196.27  6152.2  197.79  6251.3  201.58  6293.7  201.02
    6329  196.38  6343.1  198.14  6378.4  196.25  6541.2   204.1  6576.4  210.19
  6626.1  210.58  6647.2  208.38  6689.6  212.74  6944.3  226.27  7227.1  237.27
#Mann= 7 ,-1 , 0
  3436.6     .05       0  4667.5      .1       0  4993.1     .05       0
  5033.8      .1       0  5046.8     .05       0  5306.3    .035       0
  5538.1     .05       0
Bank Sta=4993.1,5033.8
XS Rating Curve= 0 ,0
Exp/Cntr=0.3,0.1

Type RM Length L Ch R = 1 ,15598   ,534,534,534
BEGIN DESCRIPTION:
MCCOY CREEK 14.0
END DESCRIPTION:
XS GIS Cut Line= 3
      2509825.02     13635974.98        2509025.       13636775.
      2507424.97     13638325.03
#Sta/Elev= 30
    3864  222.29  4175.2  197.84  4342.8   198.7  4750.6  196.91  4783.3  196.57
  4797.4  192.45  4825.7  196.21    4953  196.65  4967.1  195.04    4981  187.23
    4982  186.73  5023.9  187.23  5030.8  191.61  5037.7  192.14  5044.9  196.81
  5048.7  197.07  5570.9  195.46    5700   195.3  5711.6  195.33  5812.9  194.93
  6190.6  198.73  6296.6  195.91    6318  193.07  6353.2  198.46  6395.7  196.06
  6558.2  202.77  6586.5  202.39  6706.9  211.07    6827  217.03  7223.1  231.45
#Mann= 10 ,-1 , 0
    3864     .12       0  4342.8     .05       0  4750.6      .1       0
    4981     .05       0  5023.9      .1       0  5048.7     .05       0
  5570.9    .035       0    5700     .05       0  5711.6    .035       0
  5812.9     .05       0
Bank Sta=4981,5023.9
XS Rating Curve= 0 ,0
Exp/Cntr=0.3,0.1

Type RM Length L Ch R = 1 ,15064   ,567,567,567
BEGIN DESCRIPTION:
MCCOY CREEK 13.0
END DESCRIPTION:
XS GIS Cut Line= 3
      2509675.03     13635874.98        2508875.       13636325.
      2507274.99     13637875.01
#Sta/Elev= 30
  4082.4  218.97  4295.7  196.77  4595.7  195.64  4696.2  195.55  4753.2   195.6
  4824.7  195.27  4839.7  192.15    4920   195.2    4949  192.56  4964.9  188.48
  4965.2  185.92  4966.2  185.42  5008.1  185.92  5021.5  189.43  5028.5  187.07
  5035.7  192.61  5042.6  187.47  5056.8   186.2  5078.1   191.7  5085.1   189.4
  5099.2  194.71  5148.7  195.71  6063.3  196.23  6103.5  197.18  6144.7   190.5
  6167.3   196.3  6669.4  197.44  6895.5  206.04  6916.8  204.14    7228   221.6
#Mann= 9 ,-1 , 0
  4082.4     .12       0  4595.7     .07       0  4696.2     .05       0
  4753.2      .1       0  4965.2     .05       0  5008.1      .1       0
  5148.7     .05       0  6063.3     .12       0  6144.7     .05       0
Bank Sta=4965.2,5008.1
XS Rating Curve= 0 ,0
Exp/Cntr=0.3,0.1

Type RM Length L Ch R = 1 ,14497   ,525,525,525
BEGIN DESCRIPTION:
MCCOY CREEK 12.0
END DESCRIPTION:
XS GIS Cut Line= 3
      2509675.02       13635825.        2508875.       13635825.
      2506875.01     13638224.98
#Sta/Elev= 30
  4196.4  220.59  4266.4  211.19  4426.4  196.57  4546.4  194.01  4819.9  194.44
  4876.4  194.37  4936.4  190.01    4945  185.67    4946  185.17  4987.9  185.67
  5032.2  192.21  5074.5  190.42  5081.7  193.62  5088.2  191.99  5102.5  194.09
  5322.5  194.85  5365.5  191.78  5457.9  194.84  5901.4  193.86  6424.6   196.6
  6458.9  197.42  6487.5  189.09  6530.5  196.63  6558.9  195.25  6608.6  197.79
  6750.5  195.67  6984.8  196.72  7219.1  202.54  7679.9  228.53  8120.5  242.37
#Mann= 7 ,-1 , 0
  4196.4     .12       0  4819.9      .1       0    4945     .05       0
  4987.9      .1       0  5901.4     .05       0  6424.6     .12       0
  6558.9     .05       0
Bank Sta=4945,4987.9
XS Rating Curve= 0 ,0
Exp/Cntr=0.3,0.1

Type RM Length L Ch R = 1 ,13972   ,1112,1112,1112
BEGIN DESCRIPTION:
MCCOY CREEK 11.0
END DESCRIPTION:
XS GIS Cut Line= 3
      2509975.04       13635525.        2508575.       13635625.
      2506974.98     13637175.02
#Sta/Elev= 30
  3601.3  236.97  3627.9  236.24  3744.8  231.45  3927.5  219.83  4026.3  211.69
  4142.7  198.47    4224  194.56  4421.7  192.99    4665  193.69  4954.8  193.85
  4963.4  183.88  4964.4  183.38  5006.3  183.88  5018.9  189.74  5068.6     194
  5259.5  194.34  5301.9   193.5  5323.2  190.23  5344.3  193.57  5362.4   193.5
  5559.1  193.56  6168.9  194.91  6279.1  195.63  6348.6  196.12  6412.1  189.54
  6440.4  196.09  6521.3  195.24  6666.8  195.28  6935.6  200.72  7232.6  212.08
#Mann= 15 ,-1 , 0
  3601.3     .05       0  3627.9     .07       0  3744.8    .035       0
  3927.5     .12       0  4026.3     .05       0    4224     .12       0
  4421.7     .05       0    4665      .1       0  4963.4     .05       0
  5006.3      .1       0  5362.4     .12       0  5559.1      .1       0
  6168.9     .05       0  6279.1      .1       0  6521.3     .05       0
Bank Sta=4963.4,5006.3
XS Rating Curve= 0 ,0
Exp/Cntr=0.3,0.1

Type RM Length L Ch R = 1 ,12860   ,755,755,755
BEGIN DESCRIPTION:
MCCOY CREEK 10.0
END DESCRIPTION:
XS GIS Cut Line= 3
      2509775.01       13634825.        2508675.       13634775.
      2506275.03     13636774.97
#Sta/Elev= 30
  3903.5  231.71  4033.6   224.1  4203.8  200.88  4307.5  193.15  4401.8  191.24
  4724.1  191.12    4892  191.72  4904.5  188.54  4944.6  190.26  4954.6   189.6
  4972.8  182.36  4973.8  181.86  5016.4  182.36  5026.1  189.84  5032.6  188.11
  5040.4  192.66  5132.9  193.15  5210.8  187.96  5359.7  192.31  6421.2  193.46
  6680.6  192.29  7348.7  199.32  7592.1   202.7  7611.1  202.99    7741  208.42
  7742.2  208.55  7887.3  216.58  7958.9  227.26  8077.7   233.1  8128.7  234.78
#Mann= 15 ,-1 , 0
  3903.5     .12       0  4307.5     .05       0  4401.8    .035       0
  4724.1      .1       0  4972.8     .05       0  5016.4      .1       0
  5210.8    .035       0  5359.7      .1       0  6421.2    .045       0
  7348.7     .12       0  7592.1     .07       0  7611.1     .12       0
    7741     .07       0  7742.2     .12       0  8077.7     .05       0
Bank Sta=4972.8,5016.4
XS Rating Curve= 0 ,0
Exp/Cntr=0.3,0.1