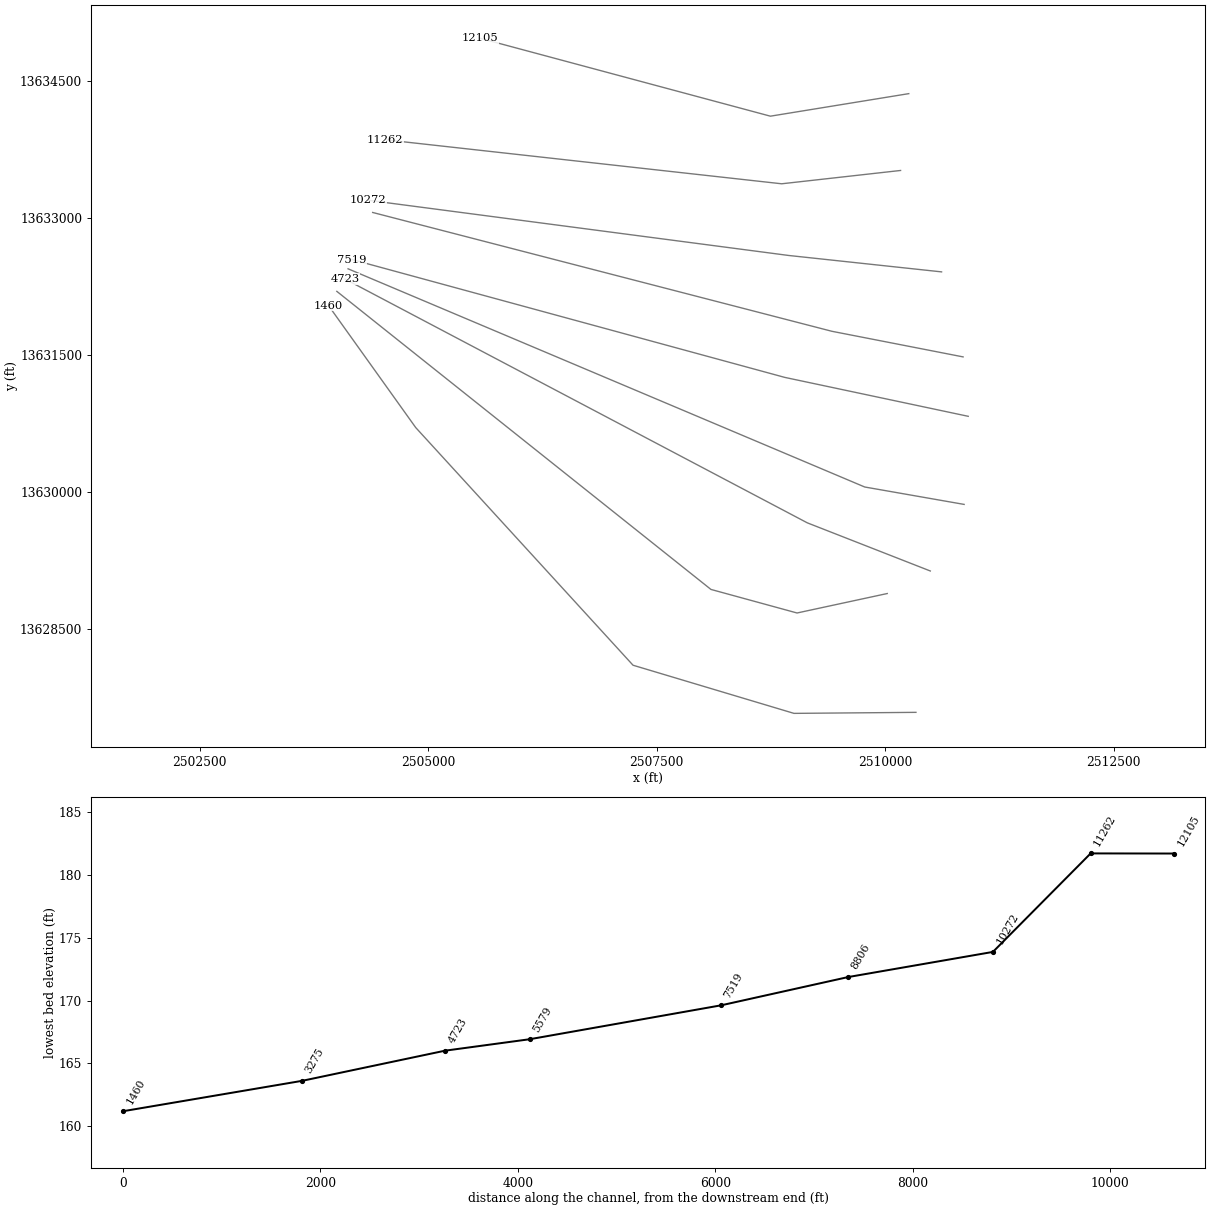
HEC-RAS study MCCOY CREEK.prj: MCCOY CREEK Base Level Engineering

--- MCCOY CREEK.g01 (geometry) --- (continued)

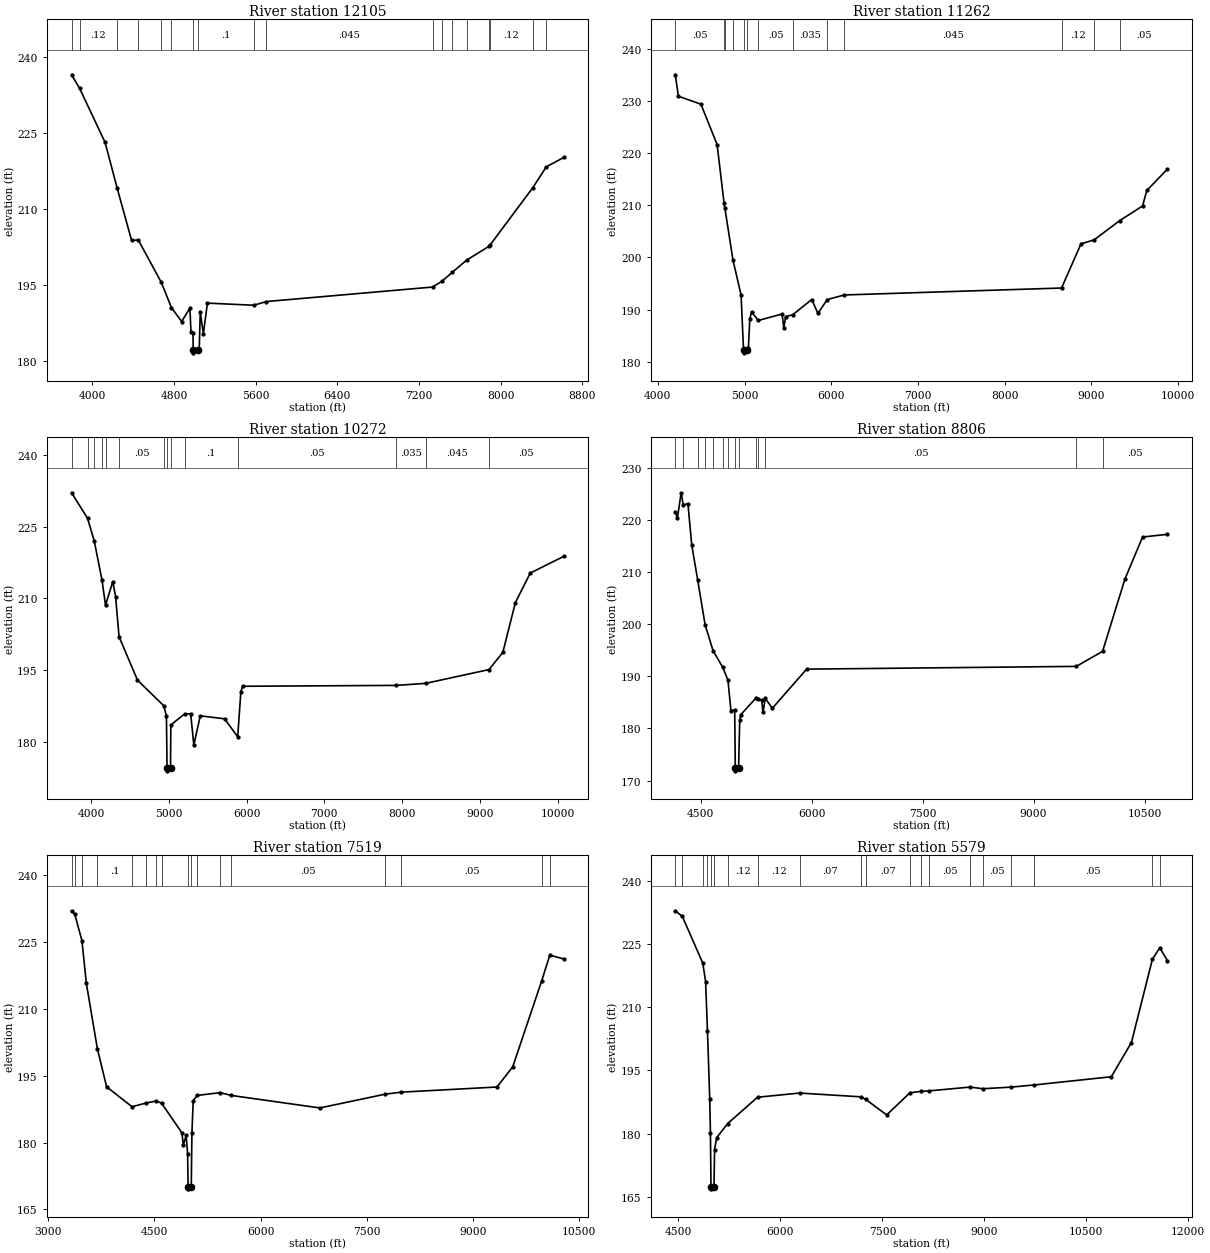
Type RM Length L Ch R = 1 ,12105   ,843,843,843
BEGIN DESCRIPTION:
B19348
END DESCRIPTION:
XS GIS Cut Line= 3
      2510258.73     13634364.66      2508744.93     13634117.97
      2505571.92     13634970.08
#Sta/Elev= 30
  3797.5  236.56  3876.3  233.87  4125.5  223.22  4244.2  214.16  4384.9   203.9
  4451.3  203.96  4675.7  195.61    4775  190.64  4875.3  187.88  4956.3  190.52
  4966.4   185.9  4986.7  185.56  4988.1   182.2  4989.1   181.7  5031.8   182.2
  5047.5  182.41  5057.6  189.69    5088   185.5  5127.8  191.51  5582.4  191.09
  5705.5  191.82  7332.3  194.68  7424.8  195.83  7527.5  197.62  7667.8  200.01
  7885.4  202.72  7895.6  202.97  8313.6  214.27    8446  218.39  8616.7  220.24
#Mann= 18 ,-1 , 0
  3797.5     .07       0  3876.3     .12       0  4244.2      .1       0
  4451.3     .12       0  4675.7     .05       0    4775      .1       0
  4988.1     .05       0  5031.8      .1       0  5582.4     .12       0
  5705.5    .045       0  7332.3    .035       0  7424.8     .12       0
  7527.5     .07       0  7667.8     .12       0  7885.4     .07       0
  7895.6     .12       0  8313.6     .07       0    8446     .12       0
Bank Sta=4988.1,5031.8
XS Rating Curve= 0 ,0
Exp/Cntr=0.3,0.1

Type RM Length L Ch R = 1 ,11262   ,990,990,990
BEGIN DESCRIPTION:
B19347
END DESCRIPTION:
XS GIS Cut Line= 3
      2510168.99     13633523.65      2508868.28     13633377.88
      2504529.63     13633859.96
#Sta/Elev= 30
  4201.8  234.99  4237.8  230.88  4497.6  229.35  4683.7  221.63  4764.1  210.46
  4773.7  209.44  4866.7   199.5  4960.5  192.79    4989  182.21    4990  181.71
  5032.7  182.21  5044.4  182.56  5061.1  188.24  5081.3  189.55  5158.9  187.91
  5433.5  189.15  5453.6  186.43  5473.7  188.66  5553.9  188.99  5775.6  191.93
    5846  189.27  5953.8  191.91  6149.7   192.8  8655.4  194.13  8879.9   202.6
  9029.7  203.34  9327.6  207.06  9588.9  209.84  9639.2  212.83    9876  216.91
#Mann= 13 ,-1 , 0
  4201.8     .05       0  4764.1    .035       0  4773.7     .05       0
  4866.7    .035       0    4989     .05       0  5032.7    .035       0
  5158.9     .05       0  5553.9    .035       0  5953.8      .1       0
  6149.7    .045       0  8655.4     .12       0  9029.7    .035       0
  9327.6     .05       0
Bank Sta=4989,5032.7
XS Rating Curve= 0 ,0
Exp/Cntr=0.3,0.1

Type RM Length L Ch R = 1 ,10272   ,1466,1466,1466
BEGIN DESCRIPTION:
B19346
END DESCRIPTION:
XS GIS Cut Line= 3
      2510617.58     13632413.53      2508946.77     13632592.95
      2504338.99     13633198.35
#Sta/Elev= 30
  3750.5  232.06  3955.5  226.73  4042.1  221.97  4141.4   213.8  4186.9  208.54
  4280.3  213.47  4316.3  210.34  4360.7  201.95  4597.9  192.84  4935.4   187.5
  4970.1  185.36  4978.1  174.37  4979.1  173.87  5022.4  174.37    5027  183.48
  5204.4  185.79  5281.8  185.81  5322.1  179.29  5405.4  185.38  5717.8  184.76
  5886.5  180.99  5926.9  190.38  5948.9  191.57  7921.9  191.75  8302.3  192.17
  9117.1  195.06  9295.6  198.65    9457  209.08  9648.6  215.26 10078.3  218.75
#Mann= 14 ,-1 , 0
  3750.5    .035       0  3955.5     .05       0  4042.1     .07       0
  4141.4     .05       0  4186.9     .07       0  4360.7     .05       0
  4935.4     .12       0  4978.1     .05       0  5022.4     .12       0
  5204.4      .1       0  5886.5     .05       0  7921.9    .035       0
  8302.3    .045       0  9117.1     .05       0
Bank Sta=4978.1,5022.4
XS Rating Curve= 0 ,0
Exp/Cntr=0.3,0.1

Type RM Length L Ch R = 1 ,8806    ,1287,1287,1287
BEGIN DESCRIPTION:
B19345
END DESCRIPTION:
XS GIS Cut Line= 3
      2510853.06     13631482.82      2509417.74     13631763.16
      2504394.15     13633063.91
#Sta/Elev= 30
  4156.5  221.58  4185.1  220.37    4236  225.24  4263.8  222.94  4327.7  223.13
  4378.7  215.23  4458.5  208.57    4559  199.95    4667  194.93  4798.2  191.74
  4868.6  189.27  4908.5  183.41  4959.4  183.58  4967.8  172.37  4968.8  171.87
  5012.2  172.37  5027.2  181.57    5041  182.63  5247.1  185.85  5271.9  185.71
  5326.2   185.4  5341.6  183.08  5372.7  185.77  5468.9  183.89  5931.7  191.39
  9577.5  191.92  9931.9  194.81 10234.1  208.68 10472.5  216.75 10808.2  217.26
#Mann= 14 ,-1 , 0
  4156.5    .035       0  4263.8     .12       0  4458.5    .045       0
    4559     .12       0    4667      .1       0  4798.2    .045       0
  4868.6      .1       0  4967.8     .05       0  5012.2      .1       0
  5247.1     .12       0  5271.9    .035       0  5372.7     .05       0
  9577.5    .035       0  9931.9     .05       0
Bank Sta=4967.8,5012.2
XS Rating Curve= 0 ,0
Exp/Cntr=0.3,0.1

Type RM Length L Ch R = 1 ,7519    ,1940,1940,1940
BEGIN DESCRIPTION:
B19344
END DESCRIPTION:
XS GIS Cut Line= 3
      2510909.14     13630832.44      2508901.92     13631258.55
      2504169.93     13632548.08
#Sta/Elev= 30
  3328.6  231.94    3374  231.16  3475.1  225.24  3537.3  215.67  3692.6  201.07
  3823.5  192.49  4183.2  188.02  4385.8  188.87  4521.8  189.29  4599.8  188.84
  4886.7  182.21  4909.1  179.48    4948  181.62  4968.5   177.5    4976  170.12
    4977  169.62  5020.4  170.12  5029.8  182.16  5047.8  189.39  5104.4  190.56
  5430.2  191.18  5587.3  190.55  6838.8  187.75  7761.6  190.84  7989.9  191.29
  9341.6  192.44  9564.6  196.97  9972.7  216.17 10088.4  221.99 10285.1  221.15
#Mann= 17 ,-1 , 0
  3328.6    .035       0    3374    .045       0  3475.1     .12       0
  3692.6      .1       0  4183.2     .12       0  4385.8      .1       0
  4521.8     .12       0  4599.8      .1       0    4976     .05       0
  5020.4      .1       0  5104.4     .07       0  5430.2    .035       0
  5587.3     .05       0  7761.6    .035       0  7989.9     .05       0
  9972.7    .035       0 10088.4     .05       0
Bank Sta=4976,5020.4
XS Rating Curve= 0 ,0
Exp/Cntr=0.3,0.1

Type RM Length L Ch R = 1 ,5579    ,856,856,856
BEGIN DESCRIPTION:
B19343
END DESCRIPTION:
XS GIS Cut Line= 3
      2510864.26     13629868.09      2509776.57     13630058.72
      2504125.02     13632447.17
#Sta/Elev= 30
    4453  232.88  4556.9  231.54  4857.6  220.46    4899  216.09  4926.4  204.47
  4959.9  188.25    4970  180.22  4978.2  167.42  4979.2  166.92  5022.7  167.42
  5030.9  176.23  5061.4  179.06  5223.1  182.39  5662.9  188.65  6280.8  189.64
  7181.3  188.75  7256.1  188.12  7563.1  184.45  7904.8  189.71  8066.1  190.03
  8181.9  190.15  8789.9  191.06  8977.3  190.67  9387.4  191.04  9726.5  191.55
 10867.7  193.51 11163.4  201.63 11472.2  221.38 11580.3  224.11 11692.8  221.06
#Mann= 20 ,-1 , 0
    4453     .07       0  4556.9    .045       0  4857.6     .12       0
  4926.4      .1       0  4978.2     .05       0  5022.7      .1       0
  5223.1     .12       0  5662.9     .12       0  6280.8     .07       0
  7181.3     .12       0  7256.1     .07       0  7904.8     .05       0
  8066.1    .035       0  8181.9     .05       0  8789.9    .035       0
  8977.3     .05       0  9387.4    .035       0  9726.5     .05       0
 11472.2    .035       0 11580.3     .05       0
Bank Sta=4978.2,5022.7
XS Rating Curve= 0 ,0
Exp/Cntr=0.3,0.1

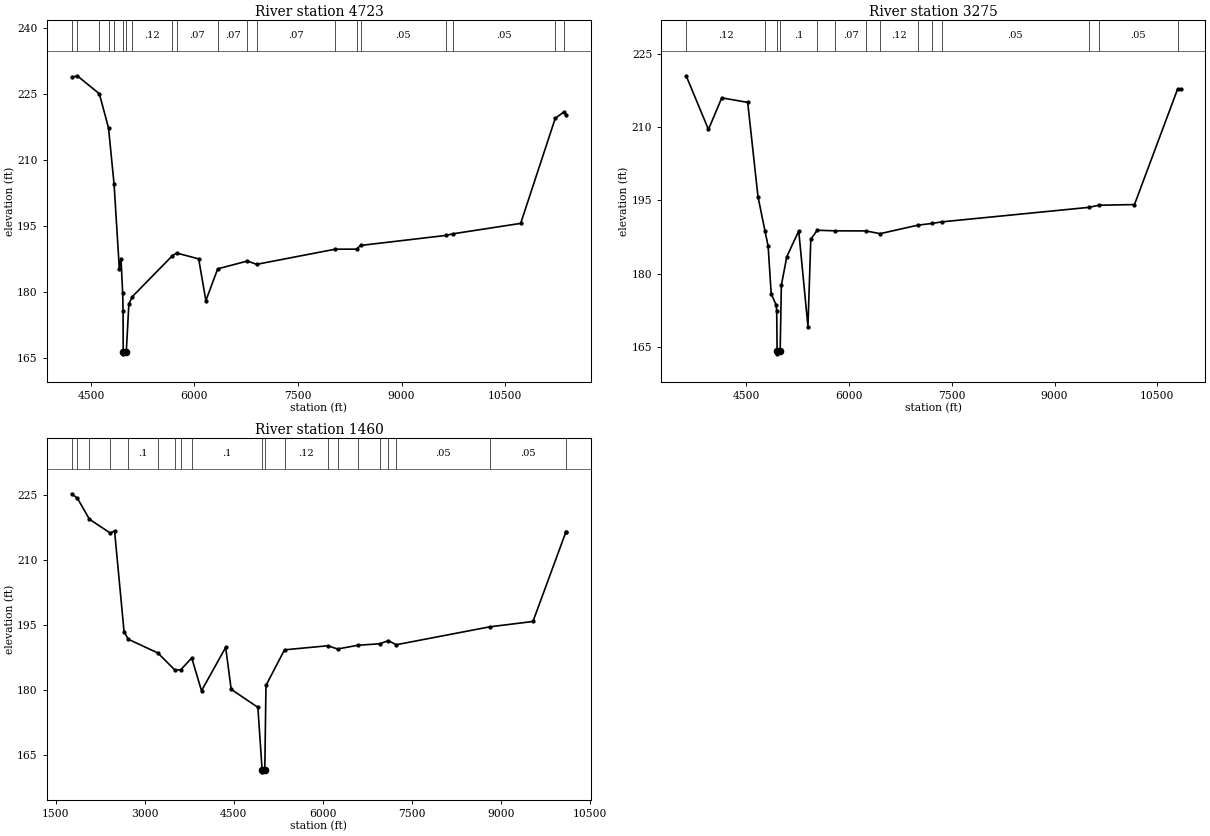
Type RM Length L Ch R = 1 ,4723    ,1448,1448,1448
BEGIN DESCRIPTION:
B19342
END DESCRIPTION:
XS GIS Cut Line= 3
       2510494.2     13629139.23      2509148.62     13629666.25
      2504091.41     13632335.02
#Sta/Elev= 30
  4221.9  228.81  4301.6  229.17  4622.1  225.09    4755  217.34  4835.8  204.52
  4911.6  185.38  4936.1  187.54  4960.5  179.73  4965.9  175.79  4968.1  166.51
  4969.1  166.01  5012.6  166.51    5050  177.36  5100.7  179.01  5681.4  188.32
  5743.2   188.9    6061  187.58  6165.4   178.1  6336.5  185.31  6765.4  187.09
  6900.8  186.34  8038.6  189.78  8347.7  189.79  8405.2  190.63  9644.5  192.91
  9750.2  193.29 10725.3  195.64 11225.5  219.48 11352.9  220.99 11385.2  220.27
#Mann= 20 ,-1 , 0
  4221.9     .12       0  4301.6     .12       0  4622.1     .07       0
    4755     .07       0  4835.8      .1       0  4968.1     .05       0
  5012.6      .1       0  5100.7     .12       0  5681.4      .1       0
  5743.2     .07       0  6336.5     .07       0  6765.4     .12       0
  6900.8     .07       0  8038.6     .05       0  8347.7    .035       0
  8405.2     .05       0  9644.5    .035       0  9750.2     .05       0
 11225.5    .035       0 11352.9     .05       0
Bank Sta=4968.1,5012.6
XS Rating Curve= 0 ,0
Exp/Cntr=0.3,0.1

Type RM Length L Ch R = 1 ,3275    ,1815,1815,1815
BEGIN DESCRIPTION:
B19341
END DESCRIPTION:
XS GIS Cut Line= 4
      2510023.21     13628892.52      2509036.48     13628679.47
      2508094.56     13628937.38        2504002.     13632200.22
#Sta/Elev= 30
  3621.5  220.46    3947  209.48  4141.4  215.95  4519.9  215.02  4669.8  195.77
  4773.1  188.67  4818.1  185.65    4863  175.89  4937.1  173.52  4943.5  172.32
  4949.3  164.11  4950.3  163.61  4993.9  164.11  5011.3  177.63  5090.6  183.46
    5265  188.73  5399.7  169.19  5441.2  187.05  5535.4  188.88  5796.8  188.76
  6244.3  188.74  6453.7  188.18  7008.5  189.93  7206.5  190.26  7359.1   190.6
  9495.8  193.55  9648.4  193.99 10166.9  194.13 10795.1  217.69 10841.6  217.69
#Mann= 14 ,-1 , 0
  3621.5     .12       0  4773.1      .1       0  4949.3     .05       0
  4993.9      .1       0  5535.4     .12       0  5796.8     .07       0
  6244.3    .035       0  6453.7     .12       0  7008.5     .07       0
  7206.5    .035       0  7359.1     .05       0  9495.8    .035       0
  9648.4     .05       0 10795.1    .035       0
Bank Sta=4949.3,4993.9
XS Rating Curve= 0 ,0
Exp/Cntr=0.3,0.1

Type RM Length L Ch R = 1 ,1460    ,0,0,0
BEGIN DESCRIPTION:
B19340
END DESCRIPTION:
XS GIS Cut Line= 5
      2510337.21     13627591.77      2509002.84     13627580.56
      2507242.34     13628107.59       2504865.1      13630709.1
      2503911.98     13632043.46
#Sta/Elev= 30
  1767.6  225.34  1864.3   224.3  2065.4  219.48  2418.5  216.27  2489.8  216.79
  2649.8  193.56  2721.3  191.78  3220.2  188.61  3510.4  184.63  3605.4  184.74
  3791.1  187.46  3955.7  179.89  4362.8   189.9  4455.8  180.23  4905.6  176.07
  4977.1  161.69  4978.1  161.19  5022.5  161.69  5042.4  181.13  5354.7  189.34
  6085.6  190.28  6248.9  189.53    6592  190.39  6960.4  190.74  7106.7  191.46
  7236.5  190.51  8813.2  194.64  9542.8  195.88 10100.3  216.62 10103.6  216.53
#Mann= 20 ,-1 , 0
  1767.6     .07       0  1864.3     .12       0  2065.4     .07       0
  2418.5     .12       0  2721.3      .1       0  3220.2     .12       0
  3510.4      .1       0  3605.4     .12       0  3791.1      .1       0
  4977.1     .05       0  5022.5      .1       0  5354.7     .12       0
  6085.6     .07       0  6248.9     .12       0    6592     .12       0
  6960.4     .07       0  7106.7    .035       0  7236.5     .05       0
  8813.2     .05       0 10100.3    .035       0
Bank Sta=4977.1,5022.5
XS Rating Curve= 0 ,0
Exp/Cntr=0.3,0.1

Chan Stop Cuts=-1
Use User Specified Reach Order=0
Composite Channel Slope=5