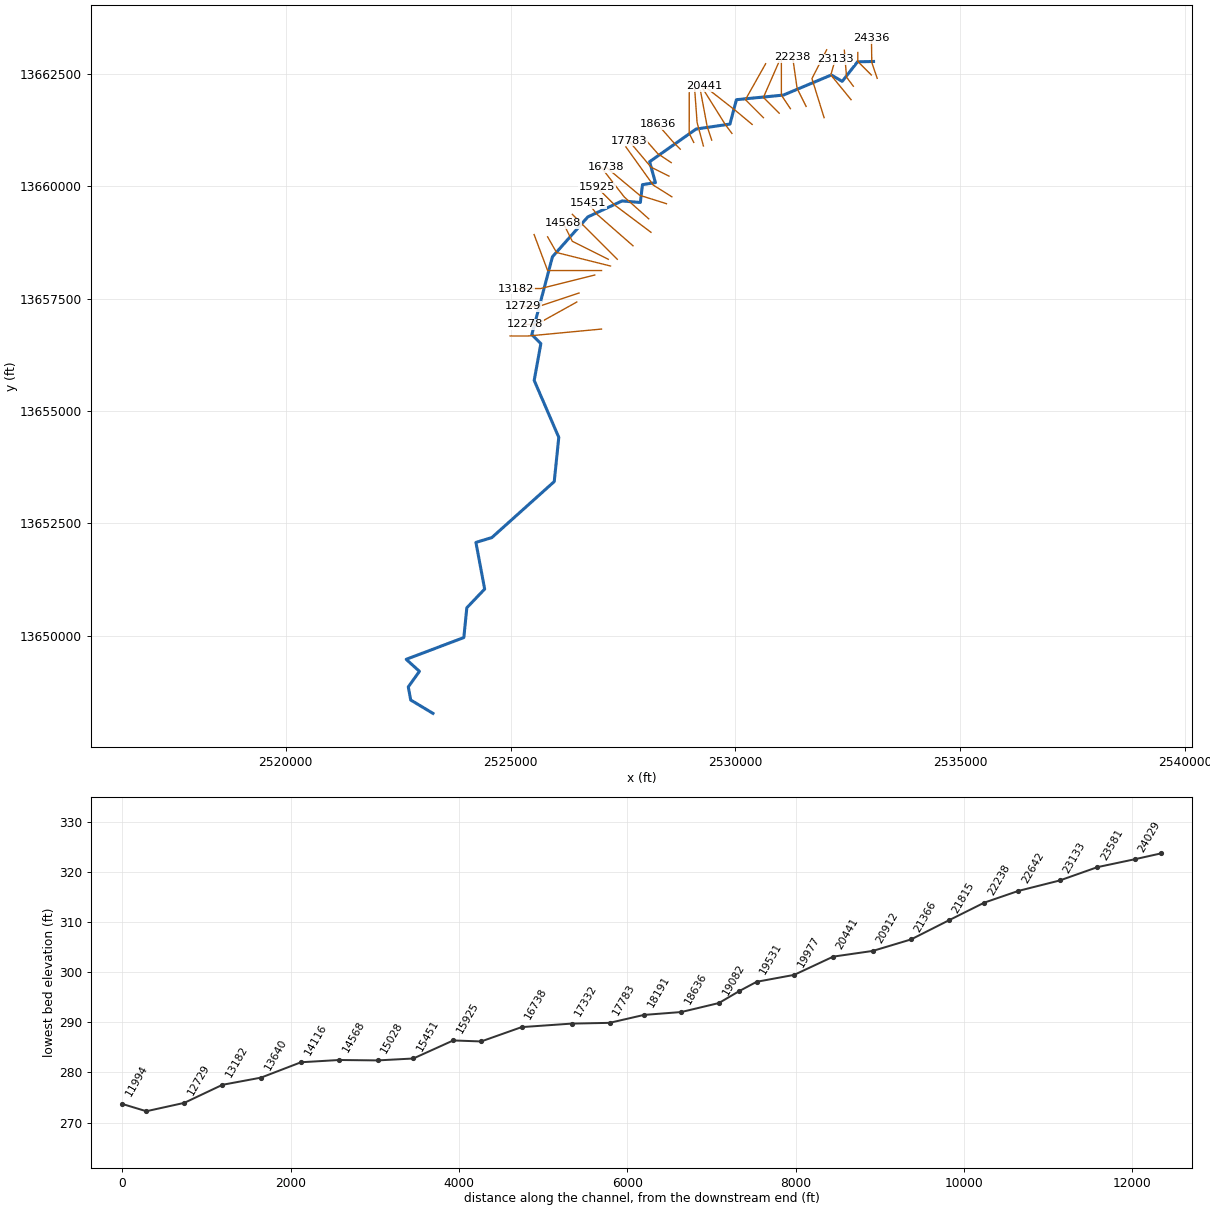
--- NORTH FORK QUEENS CREEK.prj (project) ---

Proj Title=NORTH FORK QUEENS CREEK Base Level Engineering
Current Plan=p01
Default Exp/Contr=0.3,0.1
English Units
Geom File=g01
Flow File=f01
Plan File=p01
Y Axis Title=Elevation
X Axis Title(PF)=Main Channel Distance
X Axis Title(XS)=Station
BEGIN DESCRIPTION:
NORTH FORK QUEENS CREEK
END DESCRIPTION:
DSS Export Rating Curves= 0
DSS Export Rating Curve Sorted= 0
DSS Export Volume Flow Curves= 0
DXF OffsetX= 0
DXF OffsetY= 0
DXF ScaleX= 1
DXF ScaleY= 10

--- NORTH FORK QUEENS CREEK.p01 (plan) ---

Plan Title=Multiple Run
Short Identifier=Multiple
Geom File=g01
Flow File=f01
Subcritical Flow
K Sum by GR= 0
Std Step Tol= 0.01
Critical Tol= 0.01
Num of Std Step Trials= 20
Max Error Tol= 0.3
Flow Tol Ratio= 0.001
Split Flow NTrial= 30
Split Flow Tol= 0.02
Split Flow Ratio= 0.02
Log Output Level= 0
Friction Slope Method= 1
Unsteady Friction Slope Method= 2
Unsteady Bridges Friction Slope Method= 1
Parabolic Critical Depth
Global Vel Dist=  1 , 1 , 1
Global Log Level= 0
CheckData=True
Encroach Param= -1, 0, 0, 0
BEGIN DESCRIPTION:
Multiple Run
END DESCRIPTION:

--- NORTH FORK QUEENS CREEK.f01 (steady flow) ---

Flow Title=Multiple
Number of Profiles=7
Profile Names=10-year,25-year,50-year,1pct_min,100-year,1pct_plu,500-year
River Rch & RM= NORTH FORK QUEEN,Reach-1,24336
     667    1062    1414     912    1820    3631    2980
River Rch & RM= NORTH FORK QUEEN,Reach-1,22642
     876    1417    1906    1241    2477    4942    4136
River Rch & RM= NORTH FORK QUEEN,Reach-1,20441
    1317    2178    2977    1967    3924    7830    6749
River Rch & RM= NORTH FORK QUEEN,Reach-1,19531
    1500    2507    3449    2291    4572    9122    7960
River Rch & RM= NORTH FORK QUEEN,Reach-1,16257
    1738    2922    4036    2692    5371   10716    9420
River Rch & RM= NORTH FORK QUEEN,Reach-1,13182
    2020    3415    4734    3167    6318   12607   11151
River Rch & RM= NORTH FORK QUEEN,Reach-1,10008
    2188    3714    5163    3462    6907   13782   12251
River Rch & RM= NORTH FORK QUEEN,Reach-1,9123
    3052    5253    7370    4984    9943   19840   17934
River Rch & RM= NORTH FORK QUEEN,Reach-1,2300
    3062    5266    7384    4990    9956   19864   17933
Boundary for River Rch & Prof#=NORTH FORK QUEEN,Reach-1,1
Up Type=0
Dn Type=3
Dn Slope=0.005
Boundary for River Rch & Prof#=NORTH FORK QUEEN,Reach-1,2
Up Type=0
Dn Type=3
Dn Slope=0.005
Boundary for River Rch & Prof#=NORTH FORK QUEEN,Reach-1,3
Up Type=0
Dn Type=3
Dn Slope=0.005
Boundary for River Rch & Prof#=NORTH FORK QUEEN,Reach-1,4
Up Type=0
Dn Type=3
Dn Slope=0.005
Boundary for River Rch & Prof#=NORTH FORK QUEEN,Reach-1,5
Up Type=0
Dn Type=3
Dn Slope=0.005
Boundary for River Rch & Prof#=NORTH FORK QUEEN,Reach-1,6
Up Type=0
Dn Type=3
Dn Slope=0.005
Boundary for River Rch & Prof#=NORTH FORK QUEEN,Reach-1,7
Up Type=0
Dn Type=3
Dn Slope=0.005

--- NORTH FORK QUEENS CREEK.g01 (geometry) ---

Geom Title=Existing Conditions
Program Version=4.10

River Reach=NORTH FORK QUEEN,Reach-1
Reach XY= 30
        2533075.       13662775.      2532718.81     13662767.17
      2532378.42     13662332.76      2532135.64     13662474.45
      2531069.09     13662027.22        2530025.       13661925.
      2529881.52     13661382.67      2529126.58     13661271.17
      2528094.23     13660545.38      2528223.04     13660080.87
      2527935.34     13660035.24      2527888.33     13659638.32
      2527480.93     13659672.75      2526718.94     13659316.86
      2525933.16     13658431.05      2525474.47     13656699.88
      2525675.32     13656500.12      2525526.96     13655680.89
      2526073.78      13654414.5      2525972.93     13653430.86
      2524585.12     13652185.34      2524230.73     13652077.55
      2524425.05     13651040.34      2524028.13     13650623.37
      2523961.77     13649961.33      2522680.05     13649477.26
       2522974.5     13649209.79      2522726.47     13648863.51
      2522780.52     13648572.56        2523275.       13648275.

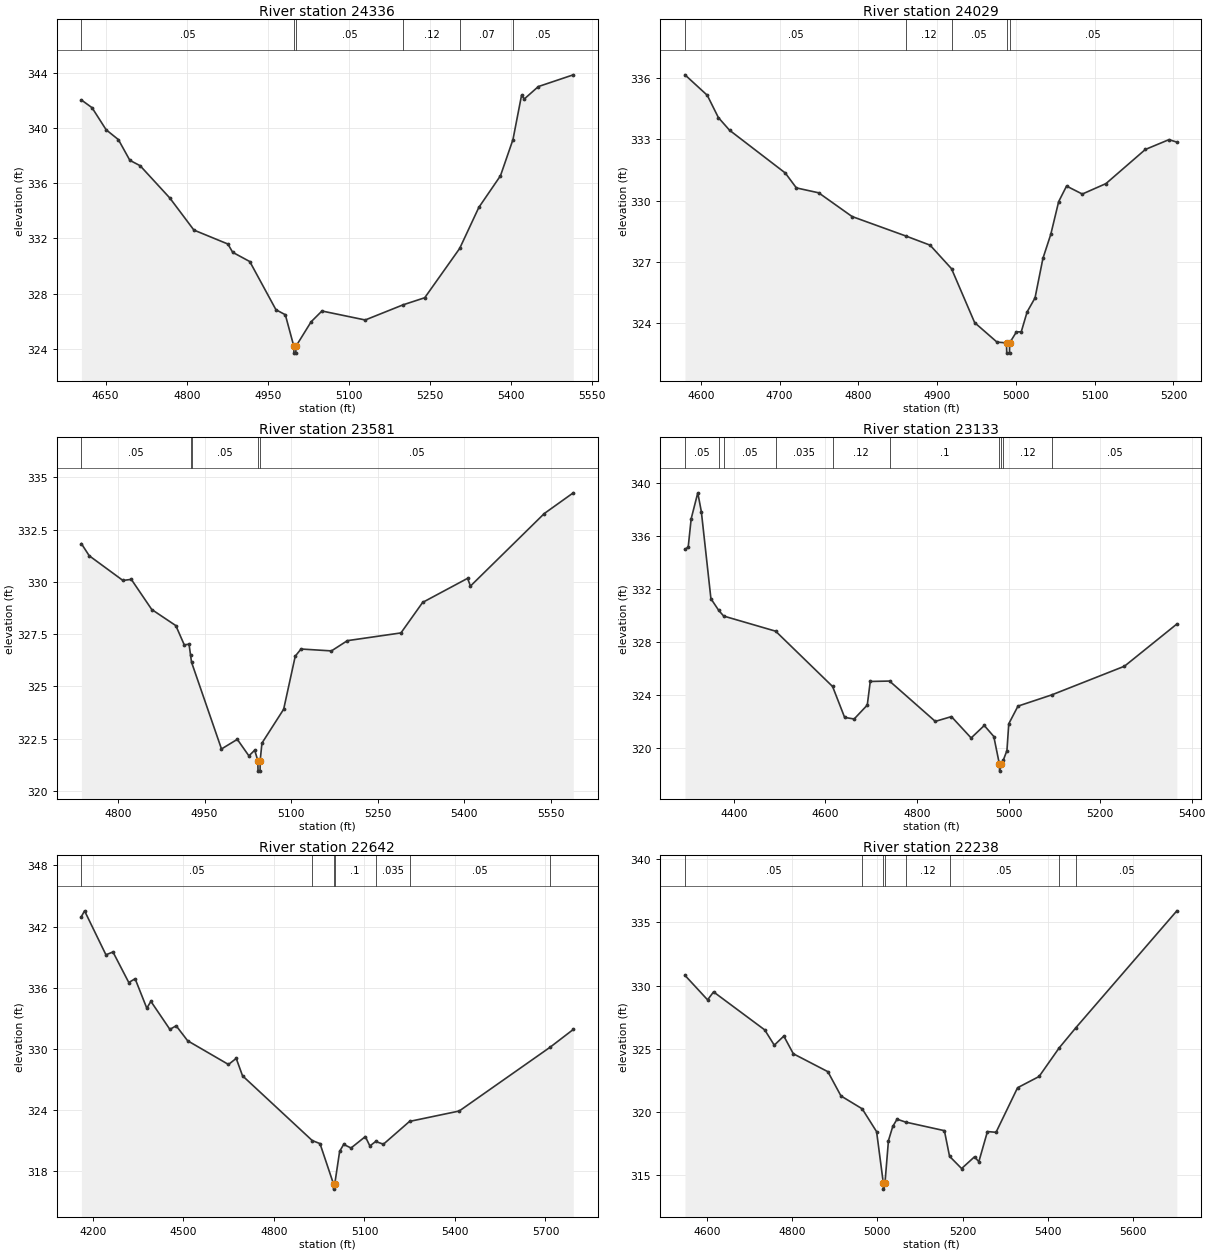
Type RM Length L Ch R = 1 ,24336   ,307,307,307
BEGIN DESCRIPTION:
B19803
END DESCRIPTION:
XS GIS Cut Line= 3
      2533155.92     13662400.19      2533035.54     13662754.64
      2533028.85     13663289.57
#Sta/Elev= 30
  4605.3  342.02    4625  341.46  4651.1  339.86  4673.7  339.15  4694.9  337.65
  4713.9  337.26  4768.8  334.92  4813.3   332.6  4876.1  331.59    4885  330.99
  4916.6  330.32    4965  326.83  4982.3  326.47    4998  324.19  4998.2  323.69
  5001.7  323.69    5002  324.19    5030  325.96    5050  326.74    5130  326.09
  5200.2  327.19    5240   327.7  5304.6  331.27    5340  334.24    5380  336.53
  5403.1  339.15    5419  342.36    5424  342.09    5450  342.99  5514.6  343.84
#Mann= 6 ,-1 , 0
  4605.3     .05       0    4998     .05       0    5002     .05       0
  5200.2     .12       0  5304.6     .07       0  5403.1     .05       0
Bank Sta=4998,5002
XS Rating Curve= 0 ,0
Exp/Cntr=0.3,0.1

Type RM Length L Ch R = 1 ,24029   ,448,448,448
BEGIN DESCRIPTION:
NORTH FORK QUEENS CREEK 52.0
END DESCRIPTION:
XS GIS Cut Line= 3
      2533025.01     13662474.99        2532725.       13662775.
        2532725.     13662975.03
#Sta/Elev= 30
    4580  336.15  4608.3  335.15  4622.4  334.06  4636.6  333.44  4707.3  331.35
  4721.4  330.62  4749.7  330.38  4792.1  329.22  4860.2  328.27  4891.1  327.82
  4918.3  326.67  4947.7  324.03    4976  323.08  4988.1  323.04  4988.4  322.54
  4991.9  322.54  4992.1  323.04  5000.7  323.58  5006.8  323.58  5014.3  324.56
  5024.3  325.24  5034.3  327.17  5044.3  328.35  5054.3  329.95  5064.3  330.71
  5084.3  330.32  5114.3  330.83  5164.3   332.5  5194.3  332.98  5204.3  332.86
#Mann= 5 ,-1 , 0
    4580     .05       0  4860.2     .12       0  4918.3     .05       0
  4988.1     .05       0  4992.1     .05       0
Bank Sta=4988.1,4992.1
XS Rating Curve= 0 ,0
Exp/Cntr=0.3,0.1

Type RM Length L Ch R = 1 ,23581   ,448,448,448
BEGIN DESCRIPTION:
NORTH FORK QUEENS CREEK 51.0
END DESCRIPTION:
XS GIS Cut Line= 3
      2532625.02     13662224.97        2532475.       13662425.
        2532425.     13663024.98
#Sta/Elev= 30
  4736.6  331.83  4750.2  331.25  4808.5  330.07  4823.1  330.12  4858.5  328.68
  4900.2  327.91  4914.8  326.99  4923.1  327.02  4925.7   326.5  4927.4  326.16
  4979.3  322.01  5006.7  322.47  5026.8  321.68  5036.8  321.95  5042.3  321.45
  5042.6  320.95  5046.1  320.95  5046.3  321.45  5049.4  322.29    5087  323.91
  5107.1  326.45  5117.1  326.79  5169.8   326.7  5197.4  327.19  5290.2  327.56
  5327.8  329.02  5405.6  330.17  5410.6   329.8  5538.5  333.27  5588.7  334.26
#Mann= 5 ,-1 , 0
  4736.6     .05       0  4925.7     .12       0  4927.4     .05       0
  5042.3     .05       0  5046.3     .05       0
Bank Sta=5042.3,5046.3
XS Rating Curve= 0 ,0
Exp/Cntr=0.3,0.1

Type RM Length L Ch R = 1 ,23133   ,491,491,491
BEGIN DESCRIPTION:
NORTH FORK QUEENS CREEK 50.0
END DESCRIPTION:
XS GIS Cut Line= 3
      2532574.97     13661925.03        2532125.       13662475.
        2532225.       13662825.
#Sta/Elev= 30
  4293.1     335  4300.2  335.19  4306.7  337.32  4321.1  339.27  4328.9  337.85
  4349.8  331.29  4366.8  330.41  4377.7  329.98  4491.2  328.84  4615.6  324.67
  4641.9  322.34  4662.7  322.22  4691.4  323.27  4697.9  325.05    4740  325.08
    4840  322.04  4875.2   322.4  4918.3  320.79    4947  321.73  4967.8   320.9
  4980.2  318.79  4980.4  318.29  4984.2  318.79  4988.8  319.14  4996.5  319.84
  5000.5  321.86  5020.6  323.19  5094.6  324.04  5253.3   326.2  5367.7  329.38
#Mann= 10 ,-1 , 0
  4293.1     .05       0  4366.8      .1       0  4377.7     .05       0
  4491.2    .035       0  4615.6     .12       0    4740      .1       0
  4980.2     .05       0  4984.2      .1       0  4988.8     .12       0
  5094.6     .05       0
Bank Sta=4980.2,4984.2
XS Rating Curve= 0 ,0
Exp/Cntr=0.3,0.1

Type RM Length L Ch R = 1 ,22642   ,404,404,404
BEGIN DESCRIPTION:
NORTH FORK QUEENS CREEK 49.0
END DESCRIPTION:
XS GIS Cut Line= 3
      2531975.01     13661524.98      2531704.83     13662393.54
      2532032.51     13663035.53
#Sta/Elev= 30
  4161.7  342.97  4172.2  343.54  4243.1  339.22  4266.4   339.5  4318.8   336.5
  4339.8  336.87  4378.5  333.98  4392.1  334.65    4455   331.9  4475.9  332.25
  4513.9  330.78  4649.3  328.45  4674.9  329.05  4695.8  327.34  4926.9  320.98
  4952.6  320.68  4997.5  316.71  4997.8  316.21  5001.5  316.71  5017.7  319.92
    5031   320.6  5055.5  320.25  5102.9  321.37  5117.9  320.45  5137.2  320.89
  5162.8  320.62  5249.4  322.86    5414  323.88    5716  330.16  5792.1  331.89
#Mann= 7 ,-1 , 0
  4161.7     .05       0  4926.9      .1       0  4997.5     .05       0
  5001.5      .1       0  5137.2    .035       0  5249.4     .05       0
    5716      .1       0
Bank Sta=4997.5,5001.5
XS Rating Curve= 0 ,0
Exp/Cntr=0.3,0.1

Type RM Length L Ch R = 1 ,22238   ,423,423,423
BEGIN DESCRIPTION:
NORTH FORK QUEENS CREEK 48.0
END DESCRIPTION:
XS GIS Cut Line= 3
      2531574.99     13661775.02        2531375.       13662175.
        2531275.     13662875.01
#Sta/Elev= 30
  4548.5  330.81  4601.6  328.87  4615.6   329.5  4735.7  326.49  4758.1  325.28
  4780.5     326  4802.8   324.6  4883.9  323.18  4914.6  321.26  4964.4  320.24
  4998.2  318.43  5013.9  314.38  5014.1  313.88  5017.9  314.38    5026  317.72
  5036.1  318.84  5046.2  319.42  5066.2  319.19  5157.3  318.51  5169.4  316.48
  5197.7  315.51    5228  316.44  5238.1  316.05  5258.3  318.44  5278.5  318.38
    5329  321.91  5379.5   322.8  5426.3  325.05    5466  326.67  5702.8  335.92
#Mann= 8 ,-1 , 0
  4548.5     .05       0  4964.4      .1       0  5013.9     .05       0
  5017.9      .1       0  5066.2     .12       0  5169.4     .05       0
  5426.3     .07       0    5466     .05       0
Bank Sta=5013.9,5017.9
XS Rating Curve= 0 ,0
Exp/Cntr=0.3,0.1

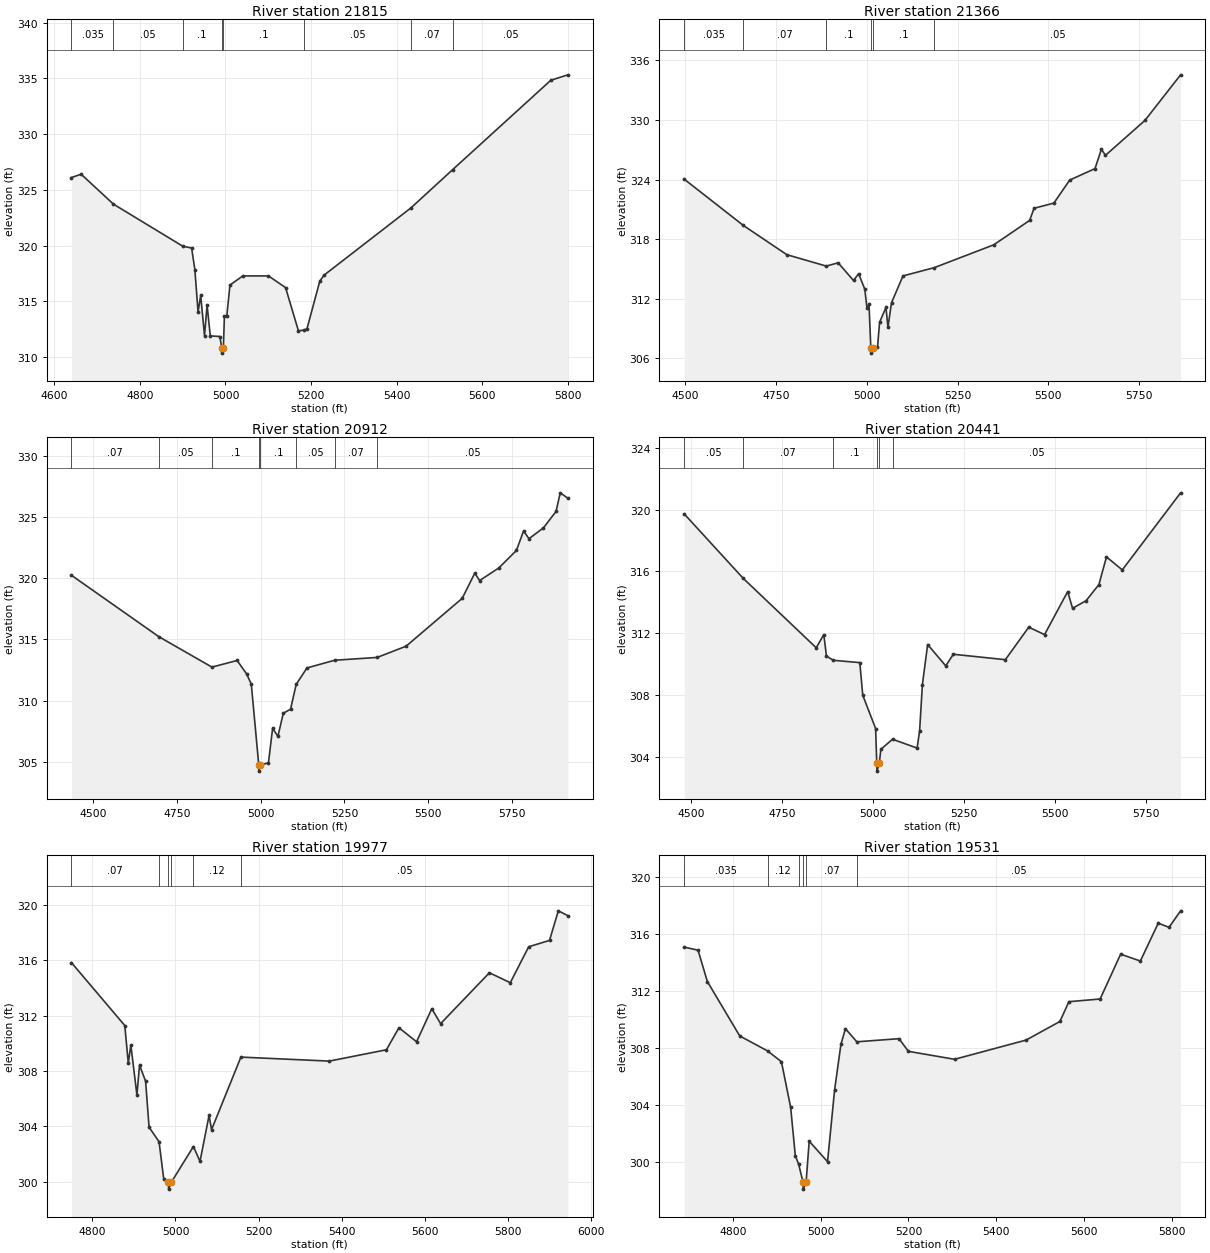
Type RM Length L Ch R = 1 ,21815   ,449,449,449
BEGIN DESCRIPTION:
NORTH FORK QUEENS CREEK 47.0
END DESCRIPTION:
XS GIS Cut Line= 3
      2531224.99     13661725.01        2531025.       13662025.
        2531025.     13662824.96
#Sta/Elev= 30
    4640   326.1  4662.5   326.4  4738.2  323.71    4900  319.94  4920.9  319.77
  4928.4  317.84  4935.9  314.03    4942  315.52    4951  311.91    4957  314.64
  4964.5  311.89    4987  311.83    4991  310.84  4991.2  310.34  4995.1  310.84
  4997.5  313.64    5003  313.64  5010.5  316.45  5040.5  317.27  5100.5  317.27
  5140.5  316.22  5170.5  312.35  5183.1   312.4  5190.5  312.52  5220.5   316.8
  5230.5  317.34  5433.4  323.37  5531.4  326.82  5760.5  334.83  5800.5  335.32
#Mann= 8 ,-1 , 0
    4640    .035       0  4738.2     .05       0    4900      .1       0
    4991     .05       0  4995.1      .1       0  5183.1     .05       0
  5433.4     .07       0  5531.4     .05       0
Bank Sta=4991,4995.1
XS Rating Curve= 0 ,0
Exp/Cntr=0.3,0.1

Type RM Length L Ch R = 1 ,21366   ,454,454,454
BEGIN DESCRIPTION:
NORTH FORK QUEENS CREEK 46.0
END DESCRIPTION:
XS GIS Cut Line= 3
        2530975.       13661625.        2530625.       13661975.
      2530975.01     13662775.01
#Sta/Elev= 30
  4496.5  324.04  4659.6  319.38  4779.3  316.44  4888.2  315.29  4920.8  315.62
  4963.2  313.84  4977.3  314.52  4994.2  312.97  5000.4  311.03  5005.9  311.46
  5010.9  307.03  5011.3  306.53  5015.7  307.03  5029.3  307.11  5035.1  309.64
  5052.7  311.13  5058.1  309.13  5067.9   311.6  5099.5   314.3  5186.2  315.14
  5349.7  317.43  5448.7  319.89  5460.8  321.11  5515.4  321.63  5559.1  323.95
  5628.8   325.1  5646.4  327.05  5657.7  326.44  5766.4  329.95  5864.7  334.54
#Mann= 6 ,-1 , 0
  4496.5    .035       0  4659.6     .07       0  4888.2      .1       0
  5010.9     .05       0  5015.7      .1       0  5186.2     .05       0
Bank Sta=5010.9,5015.7
XS Rating Curve= 0 ,0
Exp/Cntr=0.3,0.1

Type RM Length L Ch R = 1 ,20912   ,471,471,471
BEGIN DESCRIPTION:
NORTH FORK QUEENS CREEK 45.0
END DESCRIPTION:
XS GIS Cut Line= 3
      2530625.03     13661524.97        2530225.       13661925.
      2530674.99     13662724.99
#Sta/Elev= 30
  4434.4  320.24  4695.2  315.23  4854.1  312.74  4929.4  313.28  4957.7  312.19
  4971.8  311.35  4994.1  304.74  4994.5  304.24    4999  304.74  5023.1  304.92
  5035.5  307.74  5051.4  307.08  5067.4  308.97  5089.1   309.3    5106  311.33
  5138.1  312.67  5220.8   313.3  5348.1  313.53  5434.5  314.45  5602.2  318.36
  5639.8  320.42  5654.1  319.81  5711.5  320.84  5764.1  322.27  5785.7  323.87
  5801.7  323.23    5845  324.12  5882.6  325.46  5895.1  326.98    5918  326.54
#Mann= 8 ,-1 , 0
  4434.4     .07       0  4695.2     .05       0  4854.1      .1       0
  4994.1     .05       0    4999      .1       0    5106     .05       0
  5220.8     .07       0  5348.1     .05       0
Bank Sta=4994.1,4999
XS Rating Curve= 0 ,0
Exp/Cntr=0.3,0.1

Type RM Length L Ch R = 1 ,20441   ,464,464,464
BEGIN DESCRIPTION:
NORTH FORK QUEENS CREEK 44.0
END DESCRIPTION:
XS GIS Cut Line= 3
      2530374.99     13661375.01       2530019.7     13661671.34
      2529310.89     13662226.35
#Sta/Elev= 30
  4481.3  319.72  4643.1  315.56  4843.8  311.07  4864.6  311.92  4871.9  310.53
  4891.1  310.26  4963.5  310.11  4971.6     308  5006.9  305.85    5010   303.6
  5010.5   303.1  5016.9   303.6  5021.3  304.51  5053.3  305.16  5120.8  304.59
  5127.7  305.71  5135.3  308.69  5149.7  311.28  5199.4   309.9  5220.3  310.65
  5363.1   310.3  5427.3   312.4  5470.7  311.92  5534.2   314.7  5547.6  313.62
  5584.6  314.11  5619.9  315.15  5640.7  316.94  5684.1   316.1  5844.2  321.08
#Mann= 6 ,-1 , 0
  4481.3     .05       0  4643.1     .07       0  4891.1      .1       0
    5010     .05       0  5016.9      .1       0  5053.3     .05       0
Bank Sta=5010,5016.9
XS Rating Curve= 0 ,0
Exp/Cntr=0.3,0.1

Type RM Length L Ch R = 1 ,19977   ,446,446,446
BEGIN DESCRIPTION:
NORTH FORK QUEENS CREEK 43.0
END DESCRIPTION:
XS GIS Cut Line= 3
      2529925.02     13661174.98        2529775.       13661375.
      2529275.01     13662174.98
#Sta/Elev= 30
    4750  315.84  4878.2  311.29  4886.5  308.58  4892.7  309.88  4907.3  306.27
  4913.6  308.43  4928.2  307.26  4936.5  303.94  4960.5  302.89  4971.9  300.17
    4983  299.96  4983.5  299.46    4990  299.96  5043.1  302.54    5059  301.47
  5080.8   304.8  5086.7  303.76  5157.3  309.01  5369.7  308.72  5507.1  309.54
  5537.2  311.13  5579.6  310.12  5616.2  312.51  5637.4  311.43  5754.7  315.11
  5804.9  314.39  5849.1  316.99  5899.2  317.45  5920.4  319.59  5943.4  319.24
#Mann= 6 ,-1 , 0
    4750     .07       0  4960.5      .1       0    4983     .05       0
    4990      .1       0  5043.1     .12       0  5157.3     .05       0
Bank Sta=4983,4990
XS Rating Curve= 0 ,0
Exp/Cntr=0.3,0.1

Type RM Length L Ch R = 1 ,19531   ,205,205,205
BEGIN DESCRIPTION:
NORTH FORK QUEENS CREEK 42.0
END DESCRIPTION:
XS GIS Cut Line= 3
        2529475.       13661025.        2529375.       13661325.
      2529224.99     13662125.03
#Sta/Elev= 30
  4689.5   315.1  4721.1  314.88  4742.2  312.68    4816  308.85  4879.3   307.8
  4910.9  307.04  4931.9  303.83  4942.5  300.43  4950.2  299.82    4960  298.58
  4960.5  298.08  4967.1  298.58  4974.1  301.45  5015.9  300.01    5032  305.07
  5046.4  308.27  5056.6  309.36  5082.6  308.44  5178.7  308.66  5199.9  307.77
    5305  307.21  5467.8  308.56    5545  309.87  5565.3  311.26  5636.5  311.45
  5683.2   314.6  5728.1  314.12  5768.8  316.78  5793.4  316.49  5819.7  317.65
#Mann= 6 ,-1 , 0
  4689.5    .035       0  4879.3     .12       0  4950.2     .07       0
    4960     .05       0  4967.1     .07       0  5082.6     .05       0
Bank Sta=4960,4967.1
XS Rating Curve= 0 ,0
Exp/Cntr=0.3,0.1

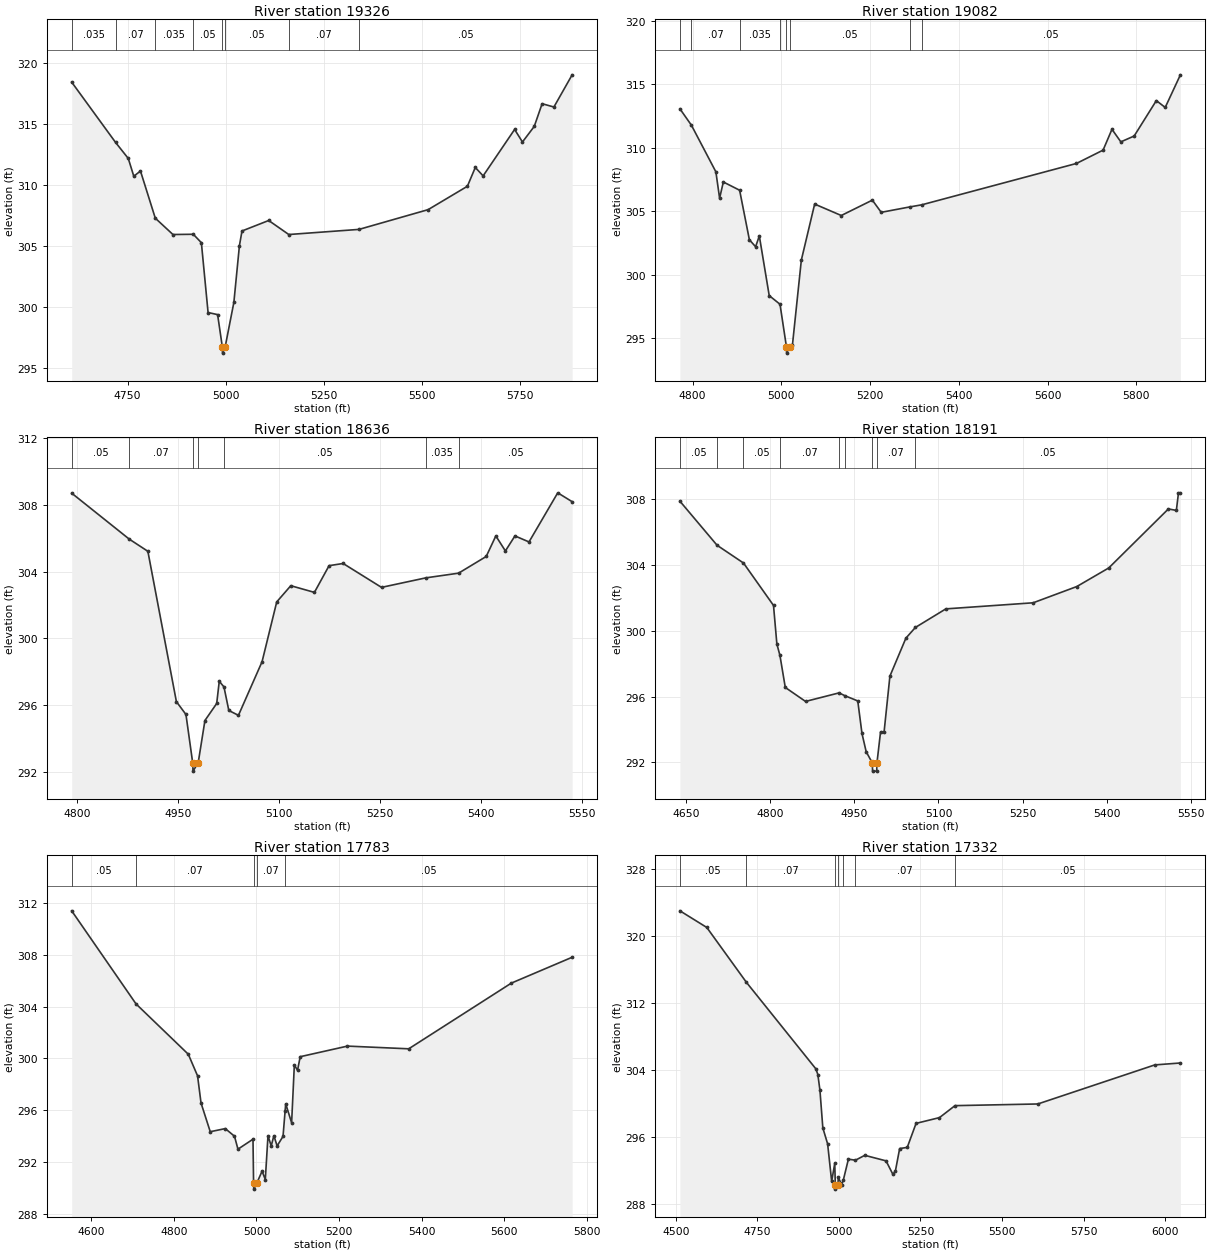
Type RM Length L Ch R = 1 ,19326   ,244,244,244
BEGIN DESCRIPTION:
B19802
END DESCRIPTION:
XS GIS Cut Line= 3
      2529290.81     13660895.67      2529150.39     13661417.24
        2529097.     13662151.36
#Sta/Elev= 30
  4607.3  318.47  4719.3  313.52  4751.6  312.21  4765.7  310.75  4782.7  311.18
  4820.5  307.31  4865.5  305.97  4917.4  305.99    4938   305.3  4955.1  299.57
  4979.4   299.4  4991.5  296.74    4992  296.24  4998.6  296.74  5020.9  300.41
    5035  305.05  5041.6  306.26  5109.7  307.12  5160.9  305.97  5339.9  306.39
  5516.2  308.01  5616.4  309.93  5636.5  311.47  5656.5  310.78  5736.8  314.59
  5756.8  313.56  5786.9  314.84  5806.9   316.7    5837  316.43  5883.5  319.07
#Mann= 8 ,-1 , 0
  4607.3    .035       0  4719.3     .07       0  4820.5    .035       0
  4917.4     .05       0  4991.5     .05       0  4998.6     .05       0
  5160.9     .07       0  5339.9     .05       0
Bank Sta=4991.5,4998.6
XS Rating Curve= 0 ,0
Exp/Cntr=0.3,0.1

Type RM Length L Ch R = 1 ,19082   ,446,446,446
BEGIN DESCRIPTION:
NORTH FORK QUEENS CREEK 41.0
END DESCRIPTION:
XS GIS Cut Line= 3
      2529074.99     13660975.01        2528975.       13661175.
      2528976.52     13662079.21
#Sta/Elev= 30
  4771.4  313.08  4797.3  311.79  4852.4  308.12  4860.8  306.04  4869.2  307.32
  4905.9  306.67  4927.9  302.77  4941.9  302.22  4950.3  303.07  4972.6  298.37
  4996.9  297.69  5011.4  294.34  5011.9  293.84  5018.5  294.34    5025   294.5
    5045  301.17    5075  305.58    5135  304.68    5205  305.89    5225  304.93
  5290.1  305.36  5316.2  305.52    5665  308.78    5725  309.83    5745  311.47
    5765  310.48    5795  310.94    5845  313.73    5865  313.19  5899.2  315.76
#Mann= 8 ,-1 , 0
  4771.4    .035       0  4797.3     .07       0  4905.9    .035       0
  4996.9     .05       0  5011.4     .05       0  5018.5     .05       0
  5290.1     .07       0  5316.2     .05       0
Bank Sta=5011.4,5018.5
XS Rating Curve= 0 ,0
Exp/Cntr=0.3,0.1

Type RM Length L Ch R = 1 ,18636   ,445,445,445
BEGIN DESCRIPTION:
NORTH FORK QUEENS CREEK 40.0
END DESCRIPTION:
XS GIS Cut Line= 3
      2528775.03     13660824.97        2528625.       13660975.
      2528274.99     13661375.01
#Sta/Elev= 30
  4792.2  308.69  4877.7  305.94  4905.4  305.21  4947.8  296.21    4962  295.44
    4972  292.55  4972.5  292.05  4980.2  292.55  4990.2  295.08  5007.7   296.1
  5011.5  297.43  5018.5  297.09  5025.7  295.68    5040  295.39  5075.1   298.6
  5096.9  302.18  5117.8  303.15  5152.9  302.75  5174.7  304.35  5195.6  304.48
  5252.6  303.05  5318.5  303.62  5367.1   303.9  5408.2   304.9  5422.5  306.13
  5436.7  305.23  5450.9  306.13  5471.8  305.77  5514.5  308.71  5535.9  308.18
#Mann= 7 ,-1 , 0
  4792.2     .05       0  4877.7     .07       0    4972     .05       0
  4980.2     .07       0  5018.5     .05       0  5318.5    .035       0
  5367.1     .05       0
Bank Sta=4972,4980.2
XS Rating Curve= 0 ,0
Exp/Cntr=0.3,0.1

Type RM Length L Ch R = 1 ,18191   ,408,408,408
BEGIN DESCRIPTION:
NORTH FORK QUEENS CREEK 39.0
END DESCRIPTION:
XS GIS Cut Line= 3
        2528575.       13660525.        2528275.       13660725.
      2527924.98     13661125.02
#Sta/Elev= 30
  4639.2  307.89  4705.4  305.21  4752.5  304.13    4806  301.55    4812   299.2
  4817.4  298.52    4827  296.56  4863.1  295.71  4922.9  296.23  4933.1  296.06
  4956.2  295.74  4963.7  293.76  4971.2  292.65  4982.1  291.97  4982.6  291.47
  4989.9  291.47  4990.4  291.97  4996.8  293.85  5003.1  293.85  5013.5  297.25
    5042  299.56  5058.9  300.21  5113.2  301.34  5268.8  301.71  5346.7   302.7
  5403.6  303.83  5509.9  307.42  5524.1  307.33  5527.9   308.4  5531.3   308.4
#Mann= 9 ,-1 , 0
  4639.2     .05       0  4705.4     .07       0  4752.5     .05       0
  4817.4     .07       0  4922.9      .1       0  4933.1     .07       0
  4982.1     .05       0  4990.4     .07       0  5058.9     .05       0
Bank Sta=4982.1,4990.4
XS Rating Curve= 0 ,0
Exp/Cntr=0.3,0.1

Type RM Length L Ch R = 1 ,17783   ,451,451,451
BEGIN DESCRIPTION:
NORTH FORK QUEENS CREEK 38.0
END DESCRIPTION:
XS GIS Cut Line= 3
      2528525.02     13660224.99        2528125.       13660425.
      2527632.42     13661009.35
#Sta/Elev= 30
  4552.7  311.41  4708.5  304.21    4835  300.32  4857.4  298.65  4865.8  296.55
  4888.1  294.33  4924.5  294.57  4946.8  293.98  4955.2  292.98  4991.6  293.75
    4993  290.39  4993.5  289.89  5001.3  290.39  5013.6  291.28  5021.4  290.63
  5027.9  294.02  5035.7  293.23  5042.2  294.02    5050  293.23  5064.3  293.97
  5069.4  295.95  5070.8  296.49  5085.1  295.02  5091.7  299.49  5099.4  299.08
  5105.9  300.13  5220.3  300.95  5368.6  300.74    5617  305.82  5764.2  307.82
#Mann= 5 ,-1 , 0
  4552.7     .05       0  4708.5     .07       0    4993     .05       0
  5001.3     .07       0  5069.4     .05       0
Bank Sta=4993,5001.3
XS Rating Curve= 0 ,0
Exp/Cntr=0.3,0.1

Type RM Length L Ch R = 1 ,17332   ,594,594,594
BEGIN DESCRIPTION:
NORTH FORK QUEENS CREEK 37.0
END DESCRIPTION:
XS GIS Cut Line= 3
      2528588.68     13659765.55        2528175.       13660025.
      2527565.56      13660875.6
#Sta/Elev= 30
  4512.3  323.01  4594.7  321.02  4715.8  314.48  4929.3  304.11  4935.2  303.44
  4941.6  301.57  4950.5  297.06  4965.2  295.15  4977.6  290.67  4987.1  292.82
  4988.8  290.24  4989.3  289.74  4997.2  290.24  4997.7  291.18    5008  290.28
  5013.7  290.88  5028.9  293.32  5050.6   293.2  5079.2  293.78  5144.3  293.12
  5165.2  291.52  5172.8  291.86  5186.1  294.59  5209.4  294.73  5236.4   297.6
  5308.2  298.29  5355.8  299.72  5609.8  299.92  5968.5  304.59    6047  304.82
#Mann= 7 ,-1 , 0
  4512.3     .05       0  4715.8     .07       0  4988.8     .05       0
  4997.2     .07       0  5013.7      .1       0  5050.6     .07       0
  5355.8     .05       0
Bank Sta=4988.8,4997.2
XS Rating Curve= 0 ,0
Exp/Cntr=0.3,0.1

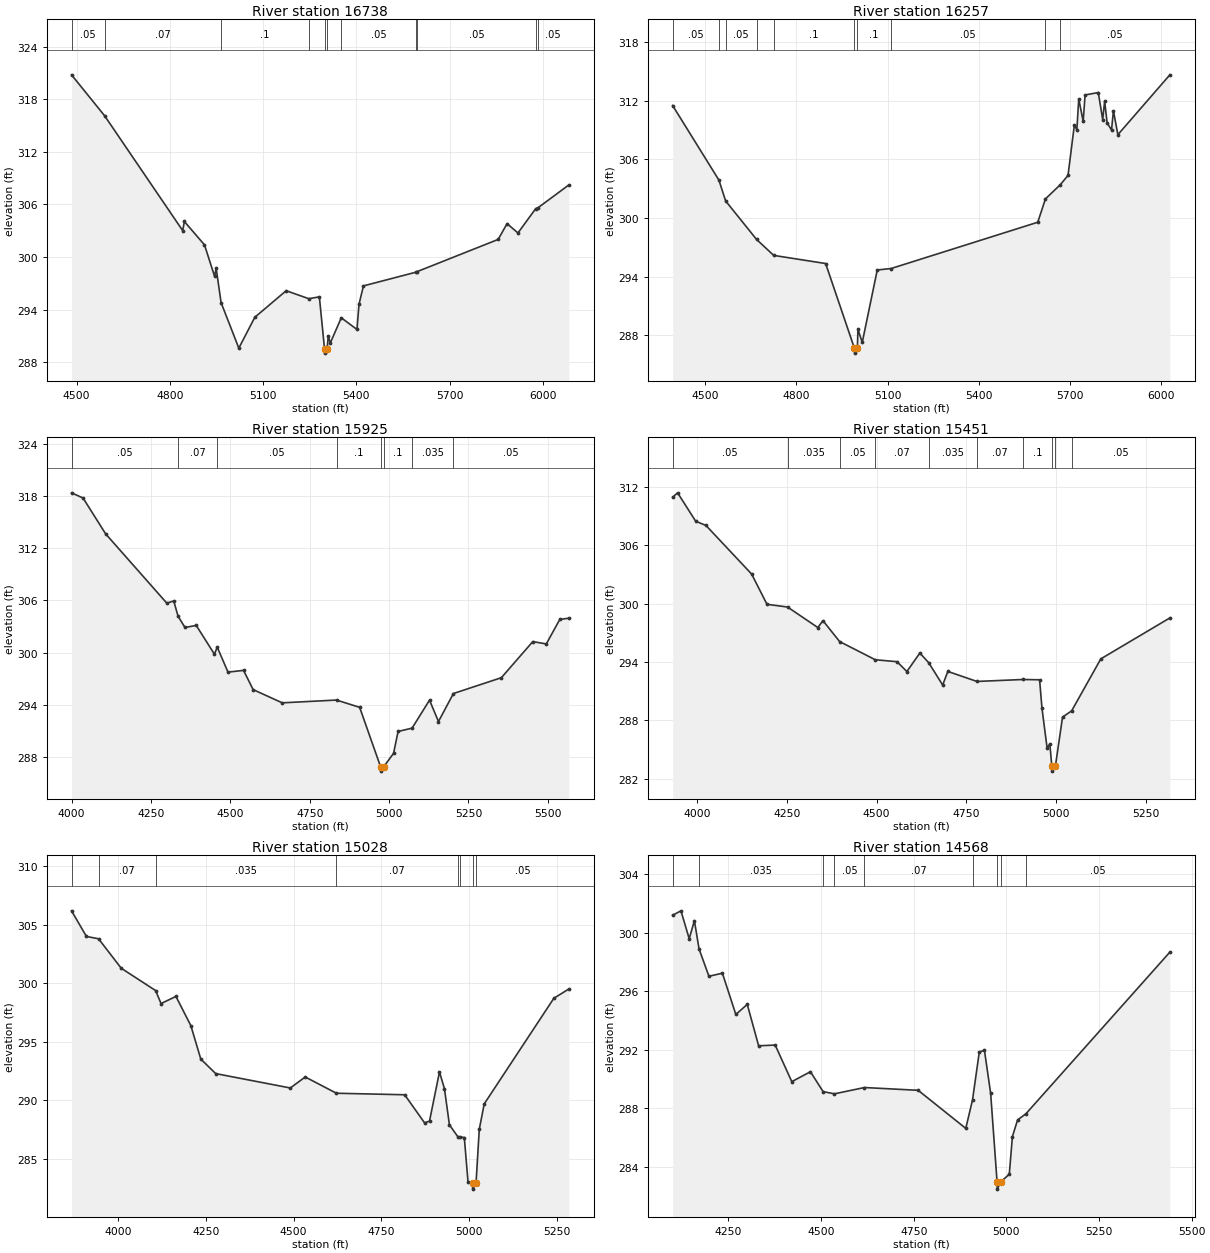
Type RM Length L Ch R = 1 ,16738   ,481,481,481
BEGIN DESCRIPTION:
NORTH FORK QUEENS CREEK 36.0
END DESCRIPTION:
XS GIS Cut Line= 3
      2528468.29     13659611.75      2527873.17     13659798.98
      2527125.01     13660424.99
#Sta/Elev= 30
  4483.7  320.79  4590.3  316.11  4841.4  303.01  4846.6  304.06  4911.4  301.39
  4943.8  297.81    4949  298.72  4964.8   294.8  5021.8  289.61  5073.3  293.13
  5174.2  296.16  5246.9  295.25  5280.9  295.46  5297.5  289.54    5298  289.04
  5305.9  289.54  5309.5  290.99    5316  290.19  5351.4  293.07  5401.9  291.74
  5408.4  294.61  5422.7  296.71  5591.1  298.27  5594.7  298.33    5856  302.01
  5884.7  303.81  5919.8  302.75  5976.9  305.53  5983.3   305.6  6083.1  308.22
#Mann= 11 ,-1 , 0
  4483.7     .05       0  4590.3     .07       0  4964.8      .1       0
  5246.9     .07       0  5297.5     .05       0  5305.9     .07       0
  5351.4     .05       0  5591.1     .07       0  5594.7     .05       0
  5976.9    .035       0  5983.3     .05       0
Bank Sta=5297.5,5305.9
XS Rating Curve= 0 ,0
Exp/Cntr=0.3,0.1

Type RM Length L Ch R = 1 ,16257   ,332,332,332
BEGIN DESCRIPTION:
NORTH FORK QUEENS CREEK 35.0
END DESCRIPTION:
XS GIS Cut Line= 3
      2528074.98     13659275.02      2527532.13     13659758.86
        2526975.       13660475.
#Sta/Elev= 30
  4393.5  311.49  4545.7  303.86  4567.6  301.74  4669.4   297.8  4725.8  296.17
  4896.4  295.34    4991  286.68  4991.5  286.18  5000.7  286.68  5002.6  288.61
  5016.8  287.28  5066.1  294.68  5111.7  294.83  5593.7  299.56    5619  301.95
  5667.6  303.39  5693.2  304.35    5714   309.5  5722.2     309  5728.5  312.18
    5743  309.86  5749.3  312.57  5792.7  312.82  5807.2  310.05  5813.6  311.95
  5821.7  309.71  5836.2  308.99  5842.5  310.96    5857  308.51    6028  314.63
#Mann= 10 ,-1 , 0
  4393.5     .05       0  4545.7     .07       0  4567.6     .05       0
  4669.4     .07       0  4725.8      .1       0    4991     .05       0
  5000.7      .1       0  5111.7     .05       0    5619    .035       0
  5667.6     .05       0
Bank Sta=4991,5000.7
XS Rating Curve= 0 ,0
Exp/Cntr=0.3,0.1

Type RM Length L Ch R = 1 ,15925   ,474,474,474
BEGIN DESCRIPTION:
NORTH FORK QUEENS CREEK 34.0
END DESCRIPTION:
XS GIS Cut Line= 3
      2528124.99     13658975.01        2527325.       13659575.
      2526924.98     13659975.02
#Sta/Elev= 30
    4000  318.37  4036.4  317.77  4107.3  313.66    4300  305.69  4321.9  305.94
  4335.4  304.19  4357.3  302.89  4392.7  303.13    4450  299.82  4458.8  300.63
  4492.7  297.76  4541.7  297.96  4571.9  295.75  4663.5  294.23  4834.4  294.55
  4907.3  293.71  4973.2  286.88  4973.7  286.38    4983  286.88  5014.1  288.43
  5028.3  290.94  5072.3  291.32  5127.3  294.54  5155.5  292.08  5202.5   295.3
  5353.5  297.12  5452.5  301.27    5495     301  5537.4  303.81  5565.7  303.96
#Mann= 8 ,-1 , 0
    4000     .05       0  4335.4     .07       0  4458.8     .05       0
  4834.4      .1       0  4973.2     .05       0    4983      .1       0
  5072.3    .035       0  5202.5     .05       0
Bank Sta=4973.2,4983
XS Rating Curve= 0 ,0
Exp/Cntr=0.3,0.1

Type RM Length L Ch R = 1 ,15451   ,423,423,423
BEGIN DESCRIPTION:
NORTH FORK QUEENS CREEK 33.0
END DESCRIPTION:
XS GIS Cut Line= 3
      2527725.01     13658674.99        2526925.       13659375.
      2526724.99     13659625.01
#Sta/Elev= 30
  3932.8  310.94  3946.6  311.39  3996.9  308.47  4025.4  308.04  4152.5  303.04
  4195.2  299.93  4252.4  299.65  4336.7  297.54  4350.9  298.25  4397.3   296.1
  4496.5  294.23  4556.9  294.03  4584.4  293.02  4620.5  294.92    4645  293.93
    4684  291.63  4698.3  293.03  4779.1     292  4907.4   292.2  4953.6  292.17
  4960.2  289.25  4974.5  285.15  4982.1  285.58  4987.6  283.28  4988.1  282.78
  4997.5  283.28  5017.4  288.33  5042.8  288.98  5123.9  294.32    5316  298.53
#Mann= 10 ,-1 , 0
  3932.8     .05       0  4252.4    .035       0  4397.3     .05       0
  4496.5     .07       0    4645    .035       0  4779.1     .07       0
  4907.4      .1       0  4987.6     .05       0  4997.5      .1       0
  5042.8     .05       0
Bank Sta=4987.6,4997.5
XS Rating Curve= 0 ,0
Exp/Cntr=0.3,0.1

Type RM Length L Ch R = 1 ,15028   ,460,460,460
BEGIN DESCRIPTION:
NORTH FORK QUEENS CREEK 32.0
END DESCRIPTION:
XS GIS Cut Line= 3
        2527375.       13658375.        2526575.       13659175.
      2526375.01     13659374.99
#Sta/Elev= 30
  3868.4   306.2  3910.8  304.01  3945.3  303.81  4009.8  301.29  4107.6  299.38
    4123  298.27  4165.4  298.88  4207.8  296.38  4236.1  293.52  4278.5  292.28
  4490.7  291.05  4533.1  291.99  4621.9   290.6  4815.9  290.47  4872.5  288.07
  4886.6  288.22  4914.9  292.42  4929.1  290.99  4943.2   287.9  4966.7   286.9
  4972.7  286.87  4985.6  286.81  4996.2  282.99  5008.9   282.9  5009.4   282.4
  5018.9   282.9  5028.1  287.51  5042.2  289.69  5240.2  298.72  5282.6  299.51
#Mann= 8 ,-1 , 0
  3868.4     .05       0  3945.3     .07       0  4107.6    .035       0
  4621.9     .07       0  4966.7      .1       0  4972.7     .05       0
  5008.9     .05       0  5018.9     .05       0
Bank Sta=5008.9,5018.9
XS Rating Curve= 0 ,0
Exp/Cntr=0.3,0.1

Type RM Length L Ch R = 1 ,14568   ,452,452,452
BEGIN DESCRIPTION:
NORTH FORK QUEENS CREEK 31.0
END DESCRIPTION:
XS GIS Cut Line= 3
      2527175.02     13658374.99        2526375.       13658775.
      2526174.98     13659175.03
#Sta/Elev= 30
  4099.5  301.19  4121.9  301.49  4144.2  299.58  4158.2  300.82  4170.7  298.89
  4197.4  297.02  4233.7  297.23    4270  294.41  4300.8   295.1  4331.5  292.27
  4376.2  292.32    4421  289.82  4471.3   290.5  4505.5  289.14  4536.1  288.99
  4617.1  289.42    4762  289.23  4890.5  286.63  4908.7  288.58  4926.9  291.84
  4940.8  291.97  4957.6  289.02  4974.9  282.98  4975.4  282.48  4985.1  282.98
  5007.9   283.5  5016.3  286.07  5030.3  287.21  5052.5  287.62  5441.2  298.67
#Mann= 9 ,-1 , 0
  4099.5     .07       0  4170.7    .035       0  4505.5     .07       0
  4536.1     .05       0  4617.1     .07       0  4908.7      .1       0
  4974.9     .05       0  4985.1      .1       0  5052.5     .05       0
Bank Sta=4974.9,4985.1
XS Rating Curve= 0 ,0
Exp/Cntr=0.3,0.1

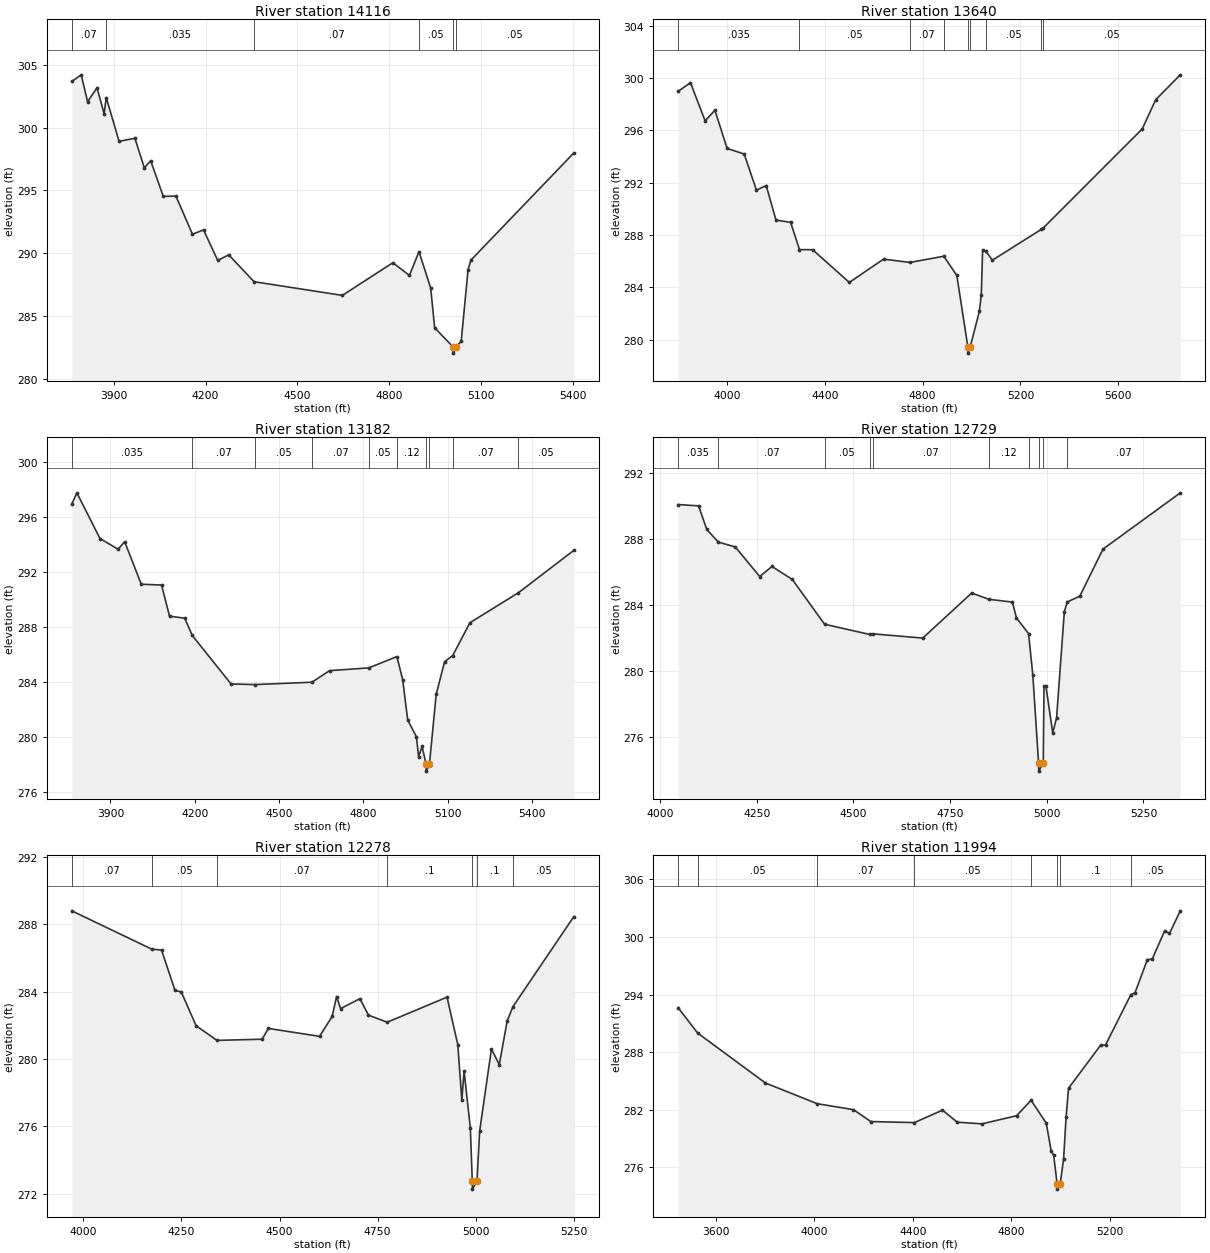
Type RM Length L Ch R = 1 ,14116   ,476,476,476
BEGIN DESCRIPTION:
NORTH FORK QUEENS CREEK 30.0
END DESCRIPTION:
XS GIS Cut Line= 3
      2527225.02     13658224.99        2526025.       13658525.
      2525824.98     13658875.03
#Sta/Elev= 30
    3763  303.67  3793.9   304.2  3814.6  302.06  3845.5  303.16  3868.7   301.1
  3875.7  302.38  3917.6   298.9  3969.2  299.15  4000.1  296.79  4020.7  297.36
  4061.9  294.52  4103.2  294.54  4157.3   291.5  4193.4  291.85  4239.8  289.42
  4275.8  289.86  4358.4  287.72  4646.9  286.63  4811.8  289.23    4866  288.22
  4897.2  290.11  4935.5  287.21  4948.4  284.05  5008.5  282.53    5009  282.03
  5018.7  282.53  5035.2  282.99  5057.5  288.67  5066.9  289.44  5403.1  297.98
#Mann= 6 ,-1 , 0
    3763     .07       0  3875.7    .035       0  4358.4     .07       0
  4897.2     .05       0  5008.5     .05       0  5018.7     .05       0
Bank Sta=5008.5,5018.7
XS Rating Curve= 0 ,0
Exp/Cntr=0.3,0.1

Type RM Length L Ch R = 1 ,13640   ,458,458,458
BEGIN DESCRIPTION:
NORTH FORK QUEENS CREEK 29.0
END DESCRIPTION:
XS GIS Cut Line= 3
      2527024.96       13658125.        2525825.       13658125.
      2525524.99     13658925.04
#Sta/Elev= 30
    3800  298.99    3850  299.65    3910  296.73    3950  297.54    4000  294.62
    4070  294.19    4120  291.43    4160  291.78    4200  289.14    4260  288.96
  4296.1  286.88    4350  286.87    4500  284.37    4640  286.15  4748.3   285.9
  4886.6  286.37    4940   284.9  4984.8  279.46  4985.3  278.96  4995.1  279.46
    5032  282.15    5040  283.39  5045.4  286.82  5059.5  286.74  5085.4  286.07
  5285.1  288.42  5292.7  288.52  5698.6  296.11  5753.8  298.35  5854.4  300.25
#Mann= 9 ,-1 , 0
    3800    .035       0  4296.1     .05       0  4748.3     .07       0
  4886.6      .1       0  4984.8     .05       0  4995.1      .1       0
  5059.5     .05       0  5285.1    .035       0  5292.7     .05       0
Bank Sta=4984.8,4995.1
XS Rating Curve= 0 ,0
Exp/Cntr=0.3,0.1

Type RM Length L Ch R = 1 ,13182   ,453,453,453
BEGIN DESCRIPTION:
NORTH FORK QUEENS CREEK 28.0
END DESCRIPTION:
XS GIS Cut Line= 3
      2526875.03     13658025.01        2525675.       13657725.
      2525124.97       13657725.
#Sta/Elev= 30
  3762.6  296.93  3780.7  297.75  3863.1  294.43  3927.6  293.65  3950.8   294.2
    4010  291.11  4082.2  291.05  4110.5  288.79  4164.6  288.64  4191.4  287.39
  4329.6  283.86  4415.7  283.82  4617.7  283.99    4680  284.83  4819.2  285.03
  4919.9  285.85  4940.3  284.18  4958.3  281.24  4989.3  280.03    4997  278.59
  5009.6  279.33  5023.6  278.03  5024.1  277.53  5035.6  278.03  5059.6   283.1
  5089.6  285.48  5118.5  285.93  5179.6  288.31  5352.2  290.49  5549.6  293.57
#Mann= 10 ,-1 , 0
  3762.6    .035       0  4191.4     .07       0  4415.7     .05       0
  4617.7     .07       0  4819.2     .05       0  4919.9     .12       0
  5023.6     .05       0  5035.6     .12       0  5118.5     .07       0
  5352.2     .05       0
Bank Sta=5023.6,5035.6
XS Rating Curve= 0 ,0
Exp/Cntr=0.3,0.1

Type RM Length L Ch R = 1 ,12729   ,451,451,451
BEGIN DESCRIPTION:
NORTH FORK QUEENS CREEK 27.0
END DESCRIPTION:
XS GIS Cut Line= 3
      2526525.01       13657625.        2525625.       13657325.
      2525274.99       13657325.
#Sta/Elev= 30
  4046.7  290.08  4099.4     290  4120.5  288.57  4150.2  287.81  4194.3  287.51
  4257.5  285.72  4289.2  286.33  4341.9  285.54  4425.2  282.83  4541.9  282.21
  4549.3  282.25  4679.2  281.99  4805.7  284.72  4850.2  284.34  4911.1  284.17
  4921.6  283.21  4952.9  282.26  4963.8  279.78  4978.8  274.43  4979.3  273.93
  4990.9  274.43  4992.8  279.06  4997.9  279.06  5015.4  276.24  5025.4  277.17
  5045.4   283.6  5053.1  284.18  5085.4  284.53  5145.4  287.38  5345.4  290.79
#Mann= 10 ,-1 , 0
  4046.7    .035       0  4150.2     .07       0  4425.2     .05       0
  4541.9     .12       0  4549.3     .07       0  4850.2     .12       0
  4952.9      .1       0  4978.8     .05       0  4990.9      .1       0
  5053.1     .07       0
Bank Sta=4978.8,4990.9
XS Rating Curve= 0 ,0
Exp/Cntr=0.3,0.1

Type RM Length L Ch R = 1 ,12278   ,284,284,284
BEGIN DESCRIPTION:
NORTH FORK QUEENS CREEK 26.0
END DESCRIPTION:
XS GIS Cut Line= 3
        2526475.       13657425.        2525575.       13656925.
      2525324.97       13656925.
#Sta/Elev= 30
  3970.4   288.8  4174.5  286.52  4199.2  286.47  4233.5  284.07  4249.5  283.98
  4287.3  281.97  4340.4   281.1  4455.4  281.17  4471.5  281.81  4601.9  281.34
  4633.9  282.52  4645.3   283.7  4655.6  282.99  4704.8  283.58  4726.6   282.6
  4774.3  282.18  4926.8  283.67  4954.2  280.85  4964.5  277.55  4970.2  279.29
  4986.2  275.89  4991.1  272.76  4991.6  272.26  5003.2  272.76    5010  275.72
    5040  280.59    5060  279.66    5080  282.25  5094.9  283.11    5250  288.46
#Mann= 7 ,-1 , 0
  3970.4     .07       0  4174.5     .05       0  4340.4     .07       0
  4774.3      .1       0  4991.1     .05       0  5003.2      .1       0
  5094.9     .05       0
Bank Sta=4991.1,5003.2
XS Rating Curve= 0 ,0
Exp/Cntr=0.3,0.1

Type RM Length L Ch R = 1 ,11994   ,636,636,636
BEGIN DESCRIPTION:
NORTH FORK QUEENS CREEK 25.0
END DESCRIPTION:
XS GIS Cut Line= 3
      2527023.96     13656823.26      2525398.97     13656669.46
      2524991.02     13656669.46
#Sta/Elev= 30
    3447  292.61  3525.9  289.98  3801.3  284.77    4012  282.61  4159.1  281.99
  4229.5  280.75  4406.8  280.64  4520.7  281.94    4581  280.68  4681.5  280.51
  4822.1  281.36  4880.8  282.97  4942.6  280.58  4962.5  277.67  4972.7  277.22
  4986.8   274.2  4987.3   273.7  4998.9   274.2  5012.9  276.84    5023  281.18
    5033  284.22  5163.2  288.71  5183.2  288.73  5286.1  293.98  5303.2  294.19
  5353.2  297.63  5373.2  297.71  5423.2  300.62  5443.2  300.37  5487.2  302.73
#Mann= 8 ,-1 , 0
    3447    .035       0  3525.9     .05       0    4012     .07       0
  4406.8     .05       0  4880.8      .1       0  4986.8    .035       0
  4998.9      .1       0  5286.1     .05       0
Bank Sta=4986.8,4998.9
XS Rating Curve= 0 ,0
Exp/Cntr=0.3,0.1