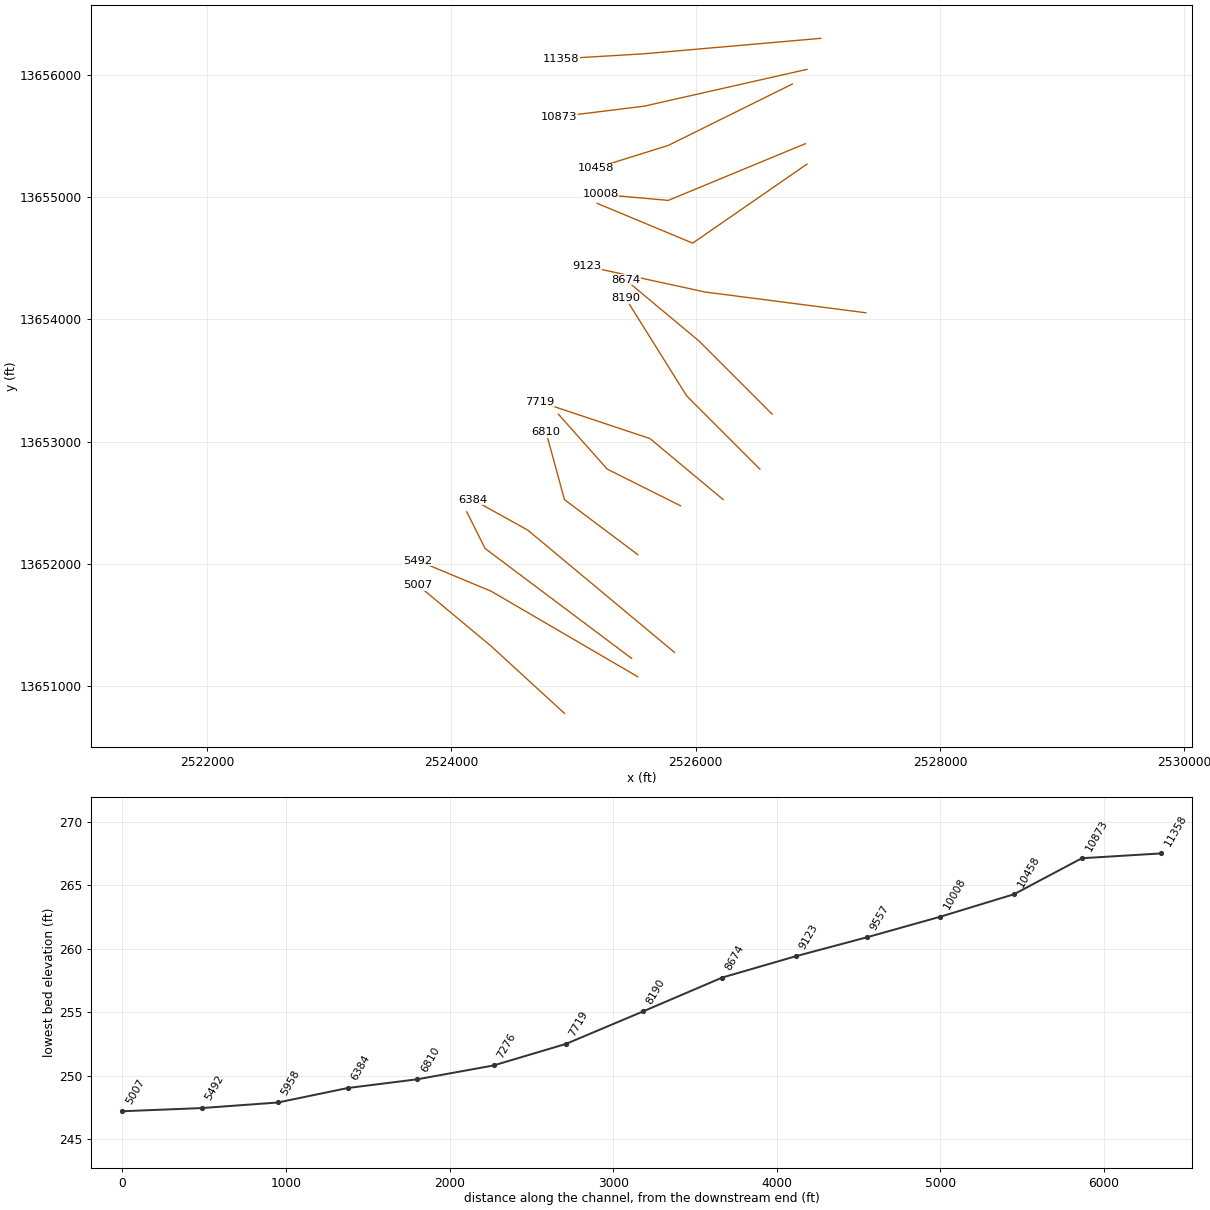
HEC-RAS study NORTH FORK QUEENS CREEK.prj: NORTH FORK QUEENS CREEK Base Level Engineering

--- NORTH FORK QUEENS CREEK.g01 (geometry) --- (continued)

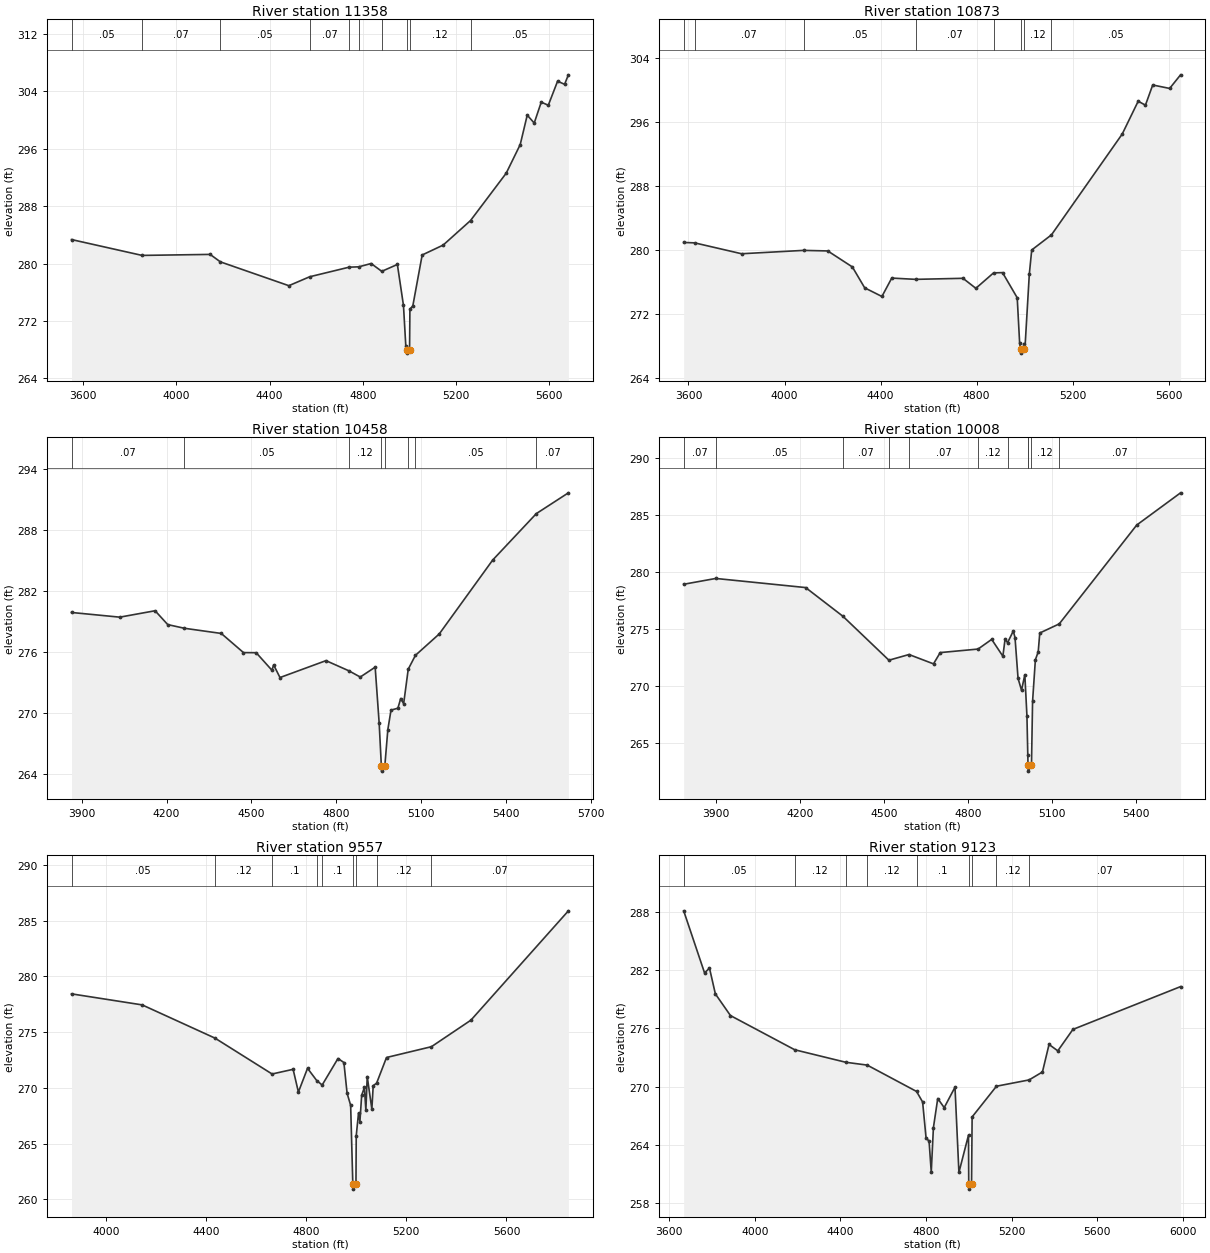
Type RM Length L Ch R = 1 ,11358   ,485,485,485
BEGIN DESCRIPTION:
NORTH FORK QUEENS CREEK 24.0
END DESCRIPTION:
XS GIS Cut Line= 3
      2527023.95     13656301.68        2525575.       13656175.
      2524898.68     13656134.57
#Sta/Elev= 30
    3550  283.36  3852.9  281.15  4144.8  281.29  4188.8  280.25  4482.5  276.93
  4571.6  278.17  4741.1  279.51  4782.8  279.56  4835.5  280.02  4881.3  278.93
  4948.2  279.89  4974.4  274.17  4984.4   268.5  4988.3  268.03  4988.8  267.53
  5000.5  268.03    5002  273.65  5014.5  274.12  5054.6  281.21  5144.7  282.59
  5262.1  286.01  5415.2  292.61  5475.3   296.6  5505.4   300.7  5535.4   299.6
  5565.5  302.51  5595.8  302.08  5635.6  305.43  5665.7     305    5682  306.32
#Mann= 10 ,-1 , 0
    3550     .05       0  3852.9     .07       0  4188.8     .05       0
  4571.6     .07       0  4741.1     .05       0  4782.8     .07       0
  4881.3     .12       0  4988.3     .05       0  5000.5     .12       0
  5262.1     .05       0
Bank Sta=4988.3,5000.5
XS Rating Curve= 0 ,0
Exp/Cntr=0.3,0.1

Type RM Length L Ch R = 1 ,10873   ,415,415,415
BEGIN DESCRIPTION:
NORTH FORK QUEENS CREEK 23.0
END DESCRIPTION:
XS GIS Cut Line= 3
       2526910.2     13656047.56      2525579.52     13655746.65
      2524879.84     13655660.02
#Sta/Elev= 30
  3580.1  280.98  3625.8  280.93  3821.2  279.57  4079.1  279.99  4180.1  279.92
  4282.6  277.92  4333.9  275.31  4405.6  274.23  4446.6  276.53  4545.5  276.37
  4743.3   276.5  4796.8  275.25  4870.7  277.18    4908  277.21  4969.1  274.07
  4979.2   268.4  4983.1  267.65  4983.6  267.15  4995.3  267.65  4996.4  268.35
  5001.4  267.79  5019.5  277.03  5029.5  280.04  5111.7  281.93  5406.4  294.53
  5472.9  298.63  5503.1  298.14  5533.4  300.66  5603.9  300.23  5649.4  301.93
#Mann= 8 ,-1 , 0
  3580.1     .05       0  3625.8     .07       0  4079.1     .05       0
  4545.5     .07       0  4870.7     .12       0  4983.1     .05       0
  4995.3     .12       0  5111.7     .05       0
Bank Sta=4983.1,4995.3
XS Rating Curve= 0 ,0
Exp/Cntr=0.3,0.1

Type RM Length L Ch R = 1 ,10458   ,450,450,450
BEGIN DESCRIPTION:
NORTH FORK QUEENS CREEK 22.0
END DESCRIPTION:
XS GIS Cut Line= 3
      2526789.88      13655927.2        2525775.       13655425.
      2525179.18     13655238.71
#Sta/Elev= 30
  3863.8  279.89  4034.4  279.43  4159.3  280.06    4204   278.7  4262.7  278.34
  4393.3  277.83  4471.8  275.95  4516.7  275.94  4572.2  274.22  4578.4  274.74
  4600.8   273.5  4763.4  275.16  4844.5  274.16  4884.6  273.55  4937.3  274.52
  4951.5     269  4959.2  264.81  4959.7  264.31  4971.4  264.81  4982.1  268.39
  4993.3   270.3  5017.6  270.49  5027.6  271.44    5038  270.93  5054.2  274.32
  5079.6  275.68  5163.8  277.78  5352.8  285.04  5507.1   289.6  5620.4  291.64
#Mann= 8 ,-1 , 0
  3863.8     .07       0  4262.7     .05       0  4844.5     .12       0
  4959.2     .05       0  4971.4     .12       0  5054.2      .1       0
  5079.6     .05       0  5507.1     .07       0
Bank Sta=4959.2,4971.4
XS Rating Curve= 0 ,0
Exp/Cntr=0.3,0.1

Type RM Length L Ch R = 1 ,10008   ,451,451,451
BEGIN DESCRIPTION:
NORTH FORK QUEENS CREEK 21.0
END DESCRIPTION:
XS GIS Cut Line= 3
      2526896.88     13655439.05        2525775.       13654975.
      2525219.25     13655024.38
#Sta/Elev= 30
  3785.9  278.95  3900.3  279.46  4220.8  278.66  4353.7  276.14  4517.8  272.28
  4589.4  272.78  4676.8  271.96  4700.7  272.95  4835.7  273.26  4884.3  274.11
  4924.2  272.63  4932.1  274.15    4941  273.82  4961.4  274.85  4967.5  274.27
  4978.3  270.69  4990.7  269.64  5002.5  271.01    5010  267.39  5013.1  263.93
  5013.9  263.04  5014.4  262.54  5026.2  263.04  5030.1  268.67  5040.1  272.32
  5050.2  273.01  5055.8  274.67  5125.2  275.47  5401.5  284.15  5557.9  286.98
#Mann= 11 ,-1 , 0
  3785.9     .07       0  3900.3     .05       0  4353.7     .07       0
  4517.8     .12       0  4589.4     .07       0  4835.7     .12       0
    4941      .1       0  5013.1     .12       0  5013.9     .05       0
  5026.2     .12       0  5125.2     .07       0
Bank Sta=5013.9,5026.2
XS Rating Curve= 0 ,0
Exp/Cntr=0.3,0.1

Type RM Length L Ch R = 1 ,9557    ,434,434,434
BEGIN DESCRIPTION:
NORTH FORK QUEENS CREEK 20.0
END DESCRIPTION:
XS GIS Cut Line= 3
      2526910.22     13655271.86        2525975.       13654625.
      2525192.73     13654950.46
#Sta/Elev= 30
  3862.9  278.43  4145.1  277.44  4435.8  274.46  4663.9  271.24  4747.9  271.66
    4769  269.62  4805.5  271.75  4842.3  270.65  4863.9  270.25  4927.1  272.63
  4950.7  272.27  4963.5  269.51  4977.7  268.43  4986.3  261.41  4986.8  260.91
  4998.9  261.41    5000   265.7  5009.2  267.75  5014.7  266.97  5021.7  269.33
  5032.5  270.03  5038.5     268  5043.9  271.01  5062.4  268.09  5067.8  270.19
  5081.4  270.42  5120.9  272.72  5300.4  273.69    5458  276.07  5847.3  285.88
#Mann= 9 ,-1 , 0
  3862.9     .05       0  4435.8     .12       0  4663.9      .1       0
  4842.3     .07       0  4863.9      .1       0  4986.3     .05       0
  4998.9      .1       0  5081.4     .12       0  5300.4     .07       0
Bank Sta=4986.3,4998.9
XS Rating Curve= 0 ,0
Exp/Cntr=0.3,0.1

Type RM Length L Ch R = 1 ,9123    ,449,449,449
BEGIN DESCRIPTION:
NORTH FORK QUEENS CREEK 19.0
END DESCRIPTION:
XS GIS Cut Line= 3
      2527391.67     13654054.84        2526075.       13654225.
       2525104.7     13654436.01
#Sta/Elev= 30
  3668.2  288.14  3765.7  281.73  3788.7  282.23  3816.1  279.57  3886.7  277.33
    4187   273.8  4425.6  272.51  4525.2  272.22  4755.8   269.5  4784.1  268.41
    4800  264.74  4814.3  264.35  4824.4  261.18  4834.5  265.77  4854.7  268.77
  4884.9  267.83  4935.3  269.94  4953.6  261.14  4998.4     265  4999.5  259.92
    5000  259.42  5012.6  259.92  5015.3  266.87    5129  270.04  5281.4  270.69
  5343.7  271.51  5374.5  274.35  5415.4  273.69  5485.9   275.9  5988.8  280.32
#Mann= 9 ,-1 , 0
  3668.2     .05       0    4187     .12       0  4425.6     .05       0
  4525.2     .12       0  4755.8      .1       0  4999.5     .05       0
  5012.6      .1       0    5129     .12       0  5281.4     .07       0
Bank Sta=4999.5,5012.6
XS Rating Curve= 0 ,0
Exp/Cntr=0.3,0.1

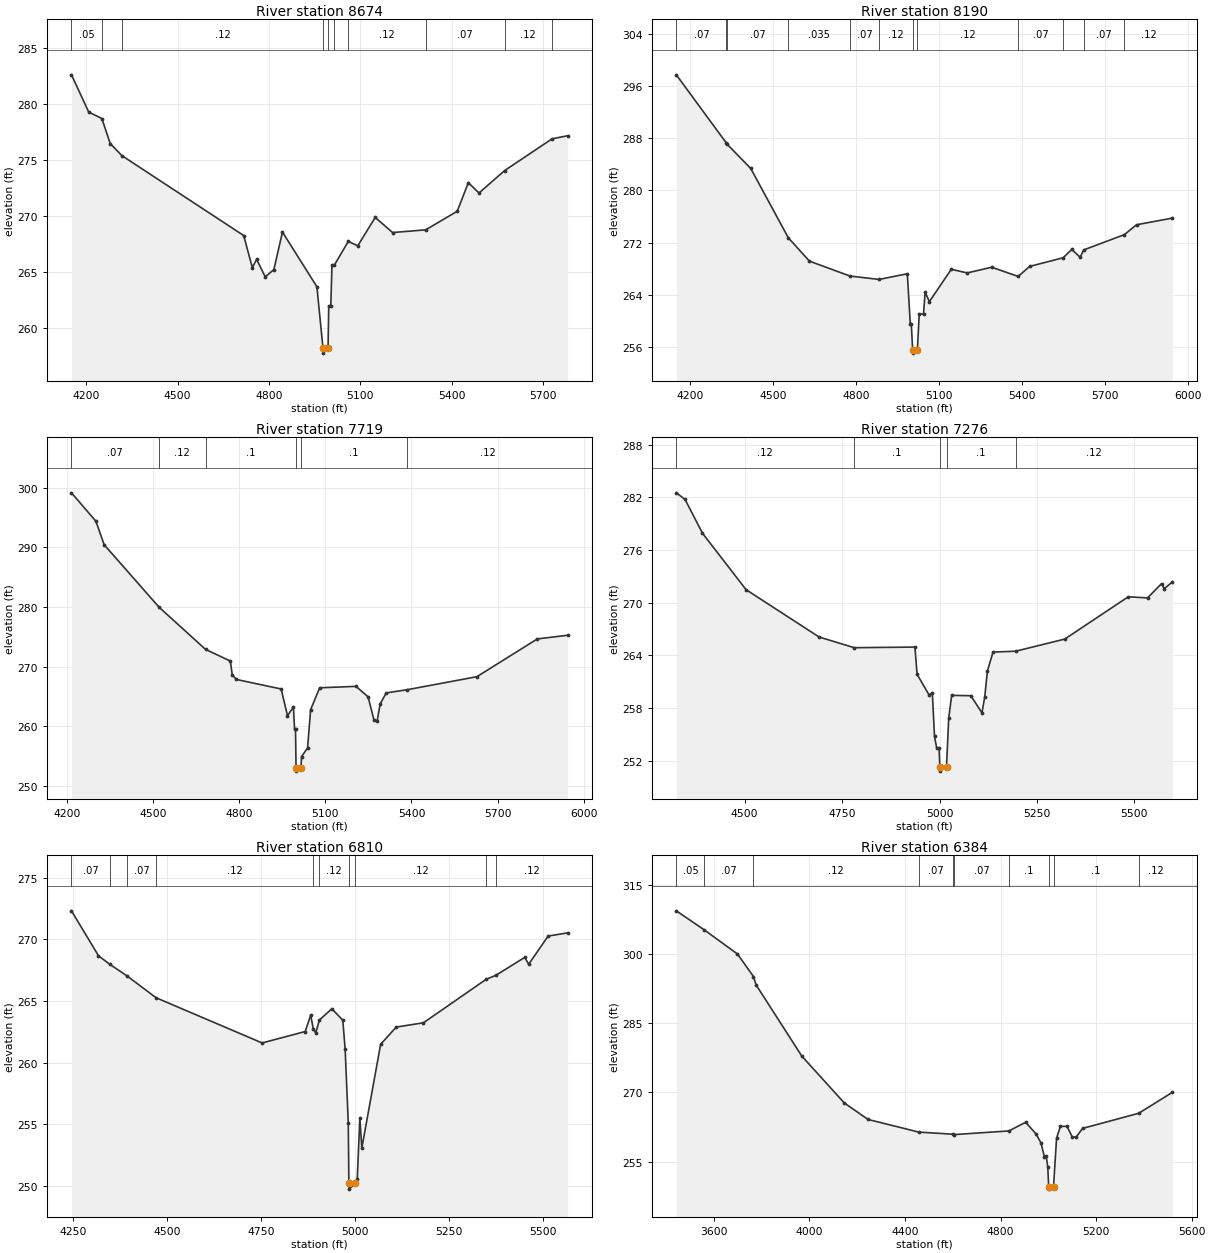
Type RM Length L Ch R = 1 ,8674    ,484,484,484
BEGIN DESCRIPTION:
NORTH FORK QUEENS CREEK 18.0
END DESCRIPTION:
XS GIS Cut Line= 3
        2526625.       13653225.        2526025.       13653825.
      2525424.96     13654325.03
#Sta/Elev= 30
  4151.5  282.64  4208.1  279.31  4251.3  278.73  4278.8  276.49  4317.1  275.41
  4717.2  268.26  4745.5  265.39  4759.6  266.13  4787.9  264.57  4816.2  265.21
  4844.5  268.57  4957.6  263.68  4977.4  258.24  4977.9  257.74  4994.3  258.24
  4996.5  261.98  5003.3  261.98  5007.2  265.63  5014.6   265.6  5060.8  267.74
  5091.8  267.34  5149.1  269.88  5206.3  268.53  5314.8  268.77  5418.5  270.43
    5455  272.99  5490.1  272.07  5574.5  274.08  5729.8  276.91  5781.1  277.19
#Mann= 10 ,-1 , 0
  4151.5     .05       0  4251.3     .07       0  4317.1     .12       0
  4977.4     .05       0  4994.3     .12       0  5014.6      .1       0
  5060.8     .12       0  5314.8     .07       0  5574.5     .12       0
  5729.8     .07       0
Bank Sta=4977.4,4994.3
XS Rating Curve= 0 ,0
Exp/Cntr=0.3,0.1

Type RM Length L Ch R = 1 ,8190    ,471,471,471
BEGIN DESCRIPTION:
NORTH FORK QUEENS CREEK 17.0
END DESCRIPTION:
XS GIS Cut Line= 3
      2526525.02     13652774.98        2525925.       13653375.
      2525424.97     13654175.04
#Sta/Elev= 30
  4151.7  297.71  4332.2  287.27  4333.2  287.16  4420.4  283.37  4556.2  272.74
  4632.6  269.16    4779  266.88  4883.9  266.36  4986.1  267.23  4996.7  259.59
  5000.3  259.59  5005.3  255.57  5005.8  255.07  5022.4  255.57  5029.1  261.09
  5044.5  261.04  5050.4  264.41  5065.7  262.96  5144.7  267.91  5202.5  267.36
  5290.9  268.23  5386.3  266.82  5427.7  268.35  5549.3  269.69  5579.9  270.96
  5610.5  269.76  5622.9  270.88  5770.2  273.23  5813.9  274.74  5943.7  275.76
#Mann= 12 ,-1 , 0
  4151.7     .07       0  4332.2     .12       0  4333.2     .07       0
  4556.2    .035       0    4779     .07       0  4883.9     .12       0
  5005.3     .05       0  5022.4     .12       0  5386.3     .07       0
  5549.3     .12       0  5622.9     .07       0  5770.2     .12       0
Bank Sta=5005.3,5022.4
XS Rating Curve= 0 ,0
Exp/Cntr=0.3,0.1

Type RM Length L Ch R = 1 ,7719    ,443,443,443
BEGIN DESCRIPTION:
NORTH FORK QUEENS CREEK 16.0
END DESCRIPTION:
XS GIS Cut Line= 3
      2526225.03     13652524.97        2525625.       13653025.
      2524724.96     13653325.01
#Sta/Elev= 30
  4214.6  299.13  4299.9  294.36  4328.5  290.44    4520  279.97  4682.2   272.9
  4768.5  270.95    4775  268.68  4789.3  267.87  4945.6  266.27  4967.7  261.79
  4988.5  263.25  4992.4   259.5  4995.7   259.5  4997.6  253.01  4998.1  252.51
  5014.8  253.01  5016.8  254.96  5037.8  256.38  5048.4  262.81    5080  266.47
  5206.5  266.71  5248.7  264.96  5269.7     261  5280.3  260.92  5290.8  263.75
  5311.9  265.61  5385.3  266.15  5628.1  268.33  5838.9  274.66  5944.4  275.27
#Mann= 6 ,-1 , 0
  4214.6     .07       0    4520     .12       0  4682.2      .1       0
  4997.6     .05       0  5014.8      .1       0  5385.3     .12       0
Bank Sta=4997.6,5014.8
XS Rating Curve= 0 ,0
Exp/Cntr=0.3,0.1

Type RM Length L Ch R = 1 ,7276    ,466,466,466
BEGIN DESCRIPTION:
NORTH FORK QUEENS CREEK 15.0
END DESCRIPTION:
XS GIS Cut Line= 3
        2525875.       13652475.        2525275.       13652775.
        2524875.       13653225.
#Sta/Elev= 30
  4324.7  282.51  4347.1  281.76  4391.8  277.91  4503.6  271.48  4690.9  266.09
  4781.1  264.87  4936.8  264.94  4942.4  261.84  4973.2  259.48  4981.5  259.75
  4987.1  254.76  4992.7  253.46  4998.9  253.46  5000.7  251.31  5001.2  250.81
  5017.9  251.31  5023.5  256.82  5031.1  259.44  5080.4   259.4  5108.8  257.44
  5115.9  259.26    5123  262.25  5137.3  264.37  5195.4  264.47  5321.2  265.85
  5484.3  270.67  5533.6  270.54  5569.6  272.17  5576.3  271.59  5597.6  272.37
#Mann= 5 ,-1 , 0
  4324.7     .12       0  4781.1      .1       0  5000.7     .05       0
  5017.9      .1       0  5195.4     .12       0
Bank Sta=5000.7,5017.9
XS Rating Curve= 0 ,0
Exp/Cntr=0.3,0.1

Type RM Length L Ch R = 1 ,6810    ,426,426,426
BEGIN DESCRIPTION:
NORTH FORK QUEENS CREEK 14.0
END DESCRIPTION:
XS GIS Cut Line= 3
      2525525.03     13652074.98        2524925.       13652525.
      2524775.01     13653074.98
#Sta/Elev= 30
    4246  272.32  4317.9  268.67  4347.3  267.99  4392.6  267.06  4471.2  265.26
  4753.3  261.59  4867.9  262.52  4882.5  263.85  4889.2  262.76    4896   262.4
  4905.6  263.45  4938.7  264.37  4967.9  263.44  4974.2  261.07  4982.5  255.11
  4984.1  250.22  4984.6  249.72  5001.7  250.22  5006.4  250.54  5013.3  255.51
  5018.5  253.05  5068.6  261.48  5110.1  262.88  5182.6  263.23  5349.4  266.76
  5374.5  267.07  5452.1  268.54  5462.5  267.98  5514.3  270.27  5566.1  270.53
#Mann= 10 ,-1 , 0
    4246     .07       0  4347.3     .12       0  4392.6     .07       0
  4471.2     .12       0  4889.2      .1       0  4905.6     .12       0
  4984.1     .05       0  5001.7     .12       0  5349.4     .07       0
  5374.5     .12       0
Bank Sta=4984.1,5001.7
XS Rating Curve= 0 ,0
Exp/Cntr=0.3,0.1

Type RM Length L Ch R = 1 ,6384    ,426,426,426
BEGIN DESCRIPTION:
NORTH FORK QUEENS CREEK 13.0
END DESCRIPTION:
XS GIS Cut Line= 3
      2525825.02     13651274.98        2524625.       13652275.
      2524174.97     13652525.02
#Sta/Elev= 30
  3442.8  309.39  3560.5  305.23  3698.6  300.03  3765.7  295.14  3776.7  293.33
  3968.1  277.88  4145.8  267.73  4245.3  264.14  4457.9   261.4  4600.7  260.94
  4606.9  260.86  4834.7  261.65  4905.3  263.53  4948.3  261.01  4969.1  259.08
  4983.4  256.08  4991.2  256.23  4997.7  253.83  5001.6  249.57    5004  249.53
  5004.5  249.03  5021.7  249.53  5034.6   260.1  5050.6  262.65  5078.1  262.65
  5099.8   260.4  5115.8  260.28  5143.3   262.2  5378.5  265.48  5519.7  270.04
#Mann= 10 ,-1 , 0
  3442.8     .05       0  3560.5     .07       0  3765.7     .12       0
  4457.9     .07       0  4600.7     .12       0  4606.9     .07       0
  4834.7      .1       0    5004     .05       0  5021.7      .1       0
  5378.5     .12       0
Bank Sta=5004,5021.7
XS Rating Curve= 0 ,0
Exp/Cntr=0.3,0.1

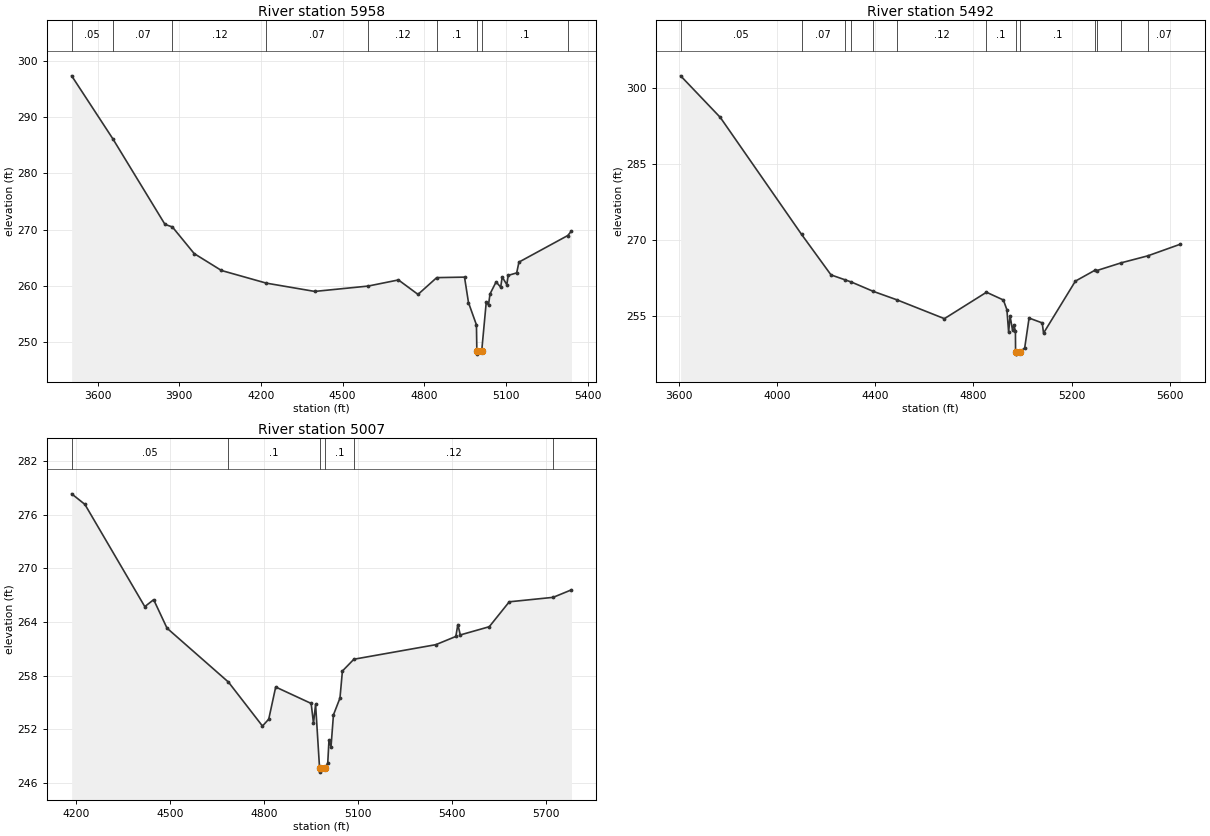
Type RM Length L Ch R = 1 ,5958    ,466,466,466
BEGIN DESCRIPTION:
NORTH FORK QUEENS CREEK 12.0
END DESCRIPTION:
XS GIS Cut Line= 3
      2525475.02     13651224.99        2524275.       13652125.
      2524125.01     13652424.97
#Sta/Elev= 30
    3505  297.33    3656  286.16  3847.7  270.94    3875  270.48    3955  265.75
    4055  262.75    4220   260.5  4397.7  259.03  4593.7  259.98    4705  261.07
  4776.9   258.5  4845.6  261.48  4947.7  261.57  4962.3  257.04  4991.5  253.08
    4993  248.39  4993.5  247.89  5010.7  248.39  5027.4  257.07  5035.8  256.65
  5041.4  258.59  5063.7  260.72  5080.5  259.78  5086.1   261.6  5102.9  260.24
  5108.4  261.88  5139.2  262.32  5147.6  264.24  5326.9  268.96  5340.4  269.76
#Mann= 9 ,-1 , 0
    3505     .05       0    3656     .07       0    3875     .12       0
    4220     .07       0  4593.7     .12       0  4845.6      .1       0
    4993     .05       0  5010.7      .1       0  5326.9     .12       0
Bank Sta=4993,5010.7
XS Rating Curve= 0 ,0
Exp/Cntr=0.3,0.1

Type RM Length L Ch R = 1 ,5492    ,485,485,485
BEGIN DESCRIPTION:
NORTH FORK QUEENS CREEK 11.0
END DESCRIPTION:
XS GIS Cut Line= 3
      2525524.96     13651075.02        2524325.       13651775.
        2523725.       13652025.
#Sta/Elev= 30
  3605.2  302.45  3767.2  294.22  4098.4  271.13  4218.7  263.11  4275.1  262.15
  4301.8   261.7  4390.9  259.86  4488.3  258.17  4681.4  254.46  4853.1  259.68
    4922  258.15  4936.5  256.21  4943.5  251.78  4949.3     255  4959.3  252.21
    4965  253.26  4971.2  251.94  4971.8  247.95  4972.3  247.45  4989.8  247.95
    5009  248.67  5026.9  254.58  5080.5  253.62  5085.9   251.6  5215.9  261.88
  5295.3  264.02  5302.9  263.96  5403.2   265.5    5511  266.87  5644.4  269.18
#Mann= 13 ,-1 , 0
  3605.2     .05       0  4098.4     .07       0  4275.1     .05       0
  4301.8     .12       0  4390.9     .07       0  4488.3     .12       0
  4853.1      .1       0  4971.8     .05       0  4989.8      .1       0
  5295.3     .12       0  5302.9      .1       0  5403.2     .12       0
    5511     .07       0
Bank Sta=4971.8,4989.8
XS Rating Curve= 0 ,0
Exp/Cntr=0.3,0.1

Type RM Length L Ch R = 1 ,5007    ,471,471,471
BEGIN DESCRIPTION:
NORTH FORK QUEENS CREEK 10.0
END DESCRIPTION:
XS GIS Cut Line= 3
      2524924.97     13650775.03        2524325.       13651325.
      2523725.02     13651824.98
#Sta/Elev= 30
  4185.9  278.36  4228.1  277.18  4419.3  265.73  4447.6  266.51  4490.2  263.32
  4686.3  257.28  4794.8  252.36  4814.8  253.13    4837  256.73  4950.2  254.89
  4957.6  252.67  4964.3  254.78  4976.9   247.7  4977.4   247.2  4994.9   247.7
  5003.1  248.21    5007  250.75  5013.5  250.02  5021.3  253.61  5042.1  255.49
  5049.9  258.52  5086.5  259.84    5348  261.47  5411.8  262.39  5418.3  263.72
  5426.1  262.56  5518.5  263.48  5582.3  266.27  5722.3  266.77  5780.8  267.61
#Mann= 6 ,-1 , 0
  4185.9     .05       0  4686.3      .1       0  4976.9     .05       0
  4994.9      .1       0  5086.5     .12       0  5722.3     .07       0
Bank Sta=4976.9,4994.9
XS Rating Curve= 0 ,0
Exp/Cntr=0.3,0.1