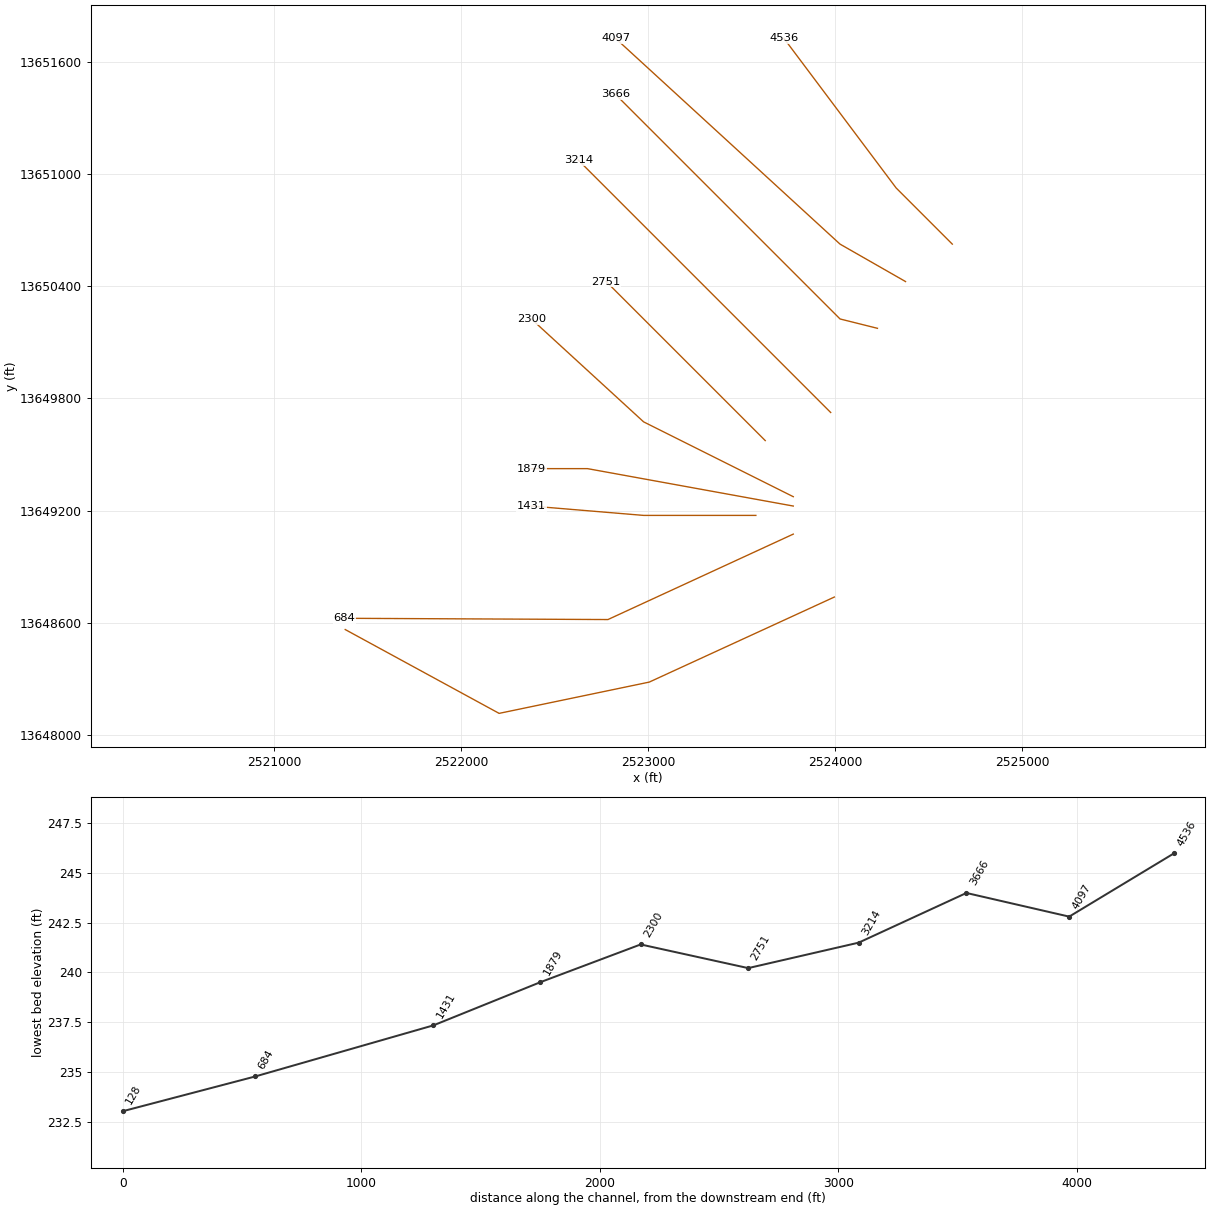
HEC-RAS study NORTH FORK QUEENS CREEK.prj: NORTH FORK QUEENS CREEK Base Level Engineering

--- NORTH FORK QUEENS CREEK.g01 (geometry) --- (continued)

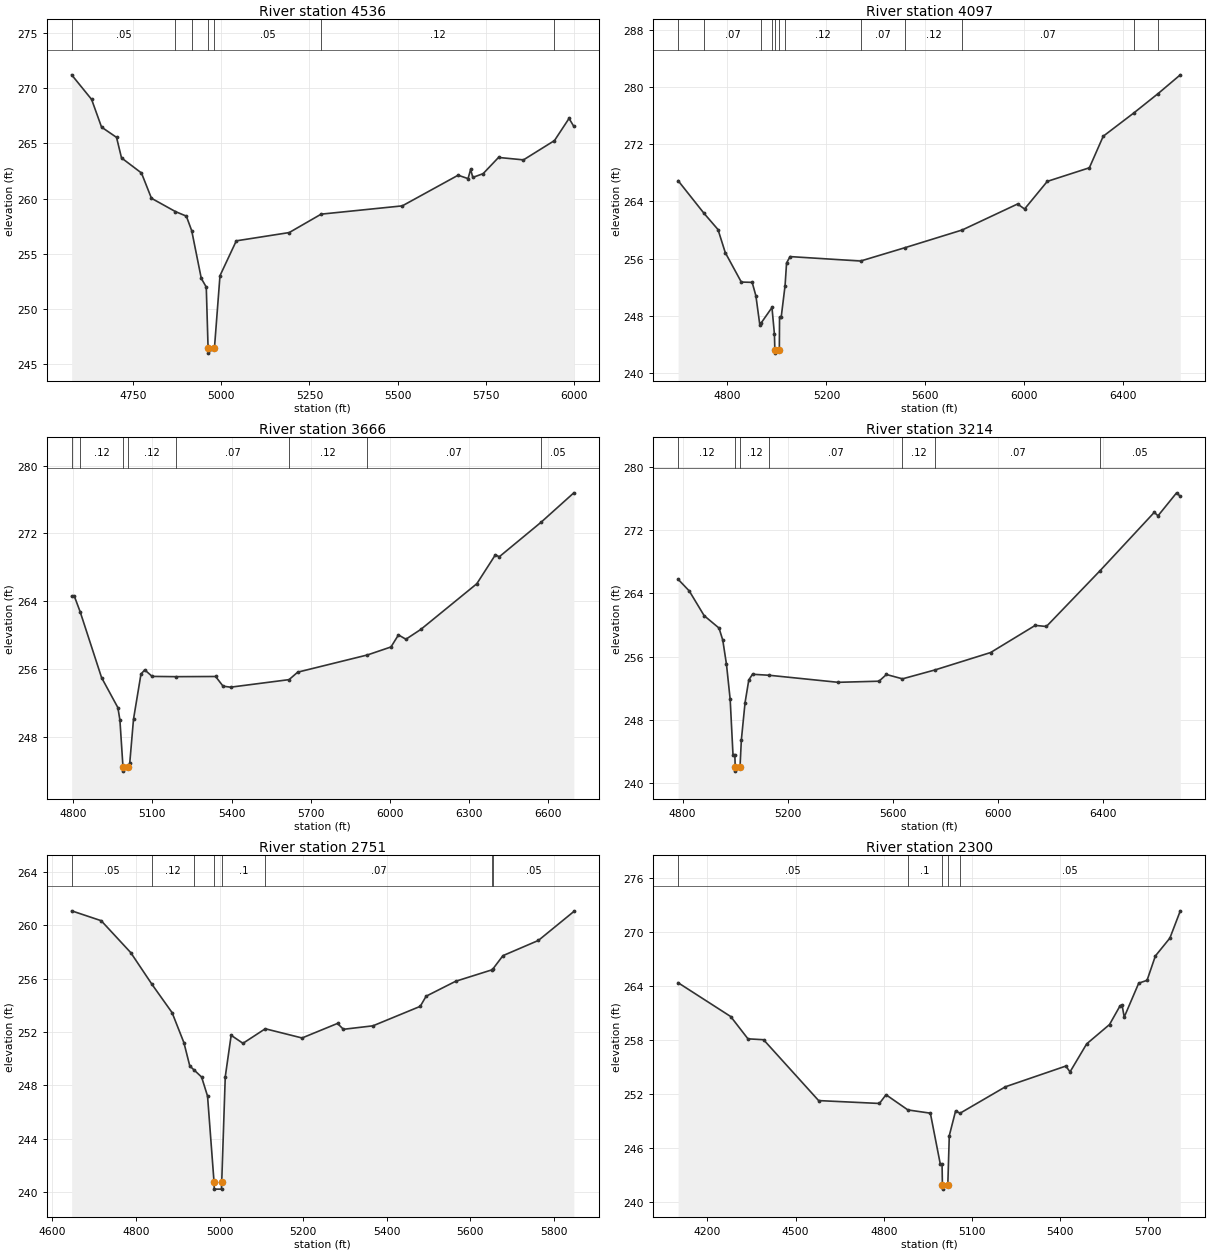
Type RM Length L Ch R = 1 ,4536    ,439,439,439
BEGIN DESCRIPTION:
NORTH FORK QUEENS CREEK 9.0
END DESCRIPTION:
XS GIS Cut Line= 3
      2524624.99     13650625.01        2524325.       13650925.
      2523724.97     13651725.04
#Sta/Elev= 30
  4575.6  271.22  4632.2  268.99  4660.4  266.48  4702.9  265.55    4717  263.69
  4773.6  262.32  4801.9  260.03  4870.1  258.82  4900.9  258.41  4916.2  257.08
  4943.3  252.76  4957.4  251.98  4962.5  246.49    4963  245.99  4980.7  246.49
  4996.3  253.01  5042.6  256.17  5192.6  256.92  5283.3  258.59  5513.4  259.34
  5671.7  262.12  5699.9  261.81  5707.1  262.64  5713.4  261.92  5742.6  262.26
  5786.3  263.73  5857.1  263.51    5945  265.26  5986.3  267.27  5999.9  266.54
#Mann= 7 ,-1 , 0
  4575.6     .05       0  4870.1     .12       0  4916.2     .05       0
  4962.5     .05       0  4980.7     .05       0  5283.3     .12       0
    5945     .07       0
Bank Sta=4962.5,4980.7
XS Rating Curve= 0 ,0
Exp/Cntr=0.3,0.1

Type RM Length L Ch R = 1 ,4097    ,431,431,431
BEGIN DESCRIPTION:
NORTH FORK QUEENS CREEK 8.0
END DESCRIPTION:
XS GIS Cut Line= 3
      2524375.03     13650424.98        2524025.       13650625.
      2522825.02     13651724.98
#Sta/Elev= 30
  4600.4  266.91  4705.5  262.33  4761.7  260.08  4791.2  256.85    4856  252.74
  4899.9   252.7    4915  250.81  4930.8  246.76  4935.8     247    4980  249.19
  4989.9  245.46  4991.6  243.31  4992.1  242.81  5009.8  243.31  5010.6   247.8
  5017.4  247.86    5033  252.26    5039  255.41  5053.2   256.3  5338.5  255.68
  5516.5  257.53  5749.4  260.02  5973.2  263.65  6001.6  262.95  6093.4  266.81
  6263.6  268.71  6319.7  273.12  6443.3  276.37  6541.6  279.08  6631.4   281.7
#Mann= 12 ,-1 , 0
  4600.4     .05       0  4705.5     .07       0  4935.8     .12       0
    4980     .07       0  4991.6     .05       0  5009.8     .07       0
    5033     .12       0  5338.5     .07       0  5516.5     .12       0
  5749.4     .07       0  6443.3     .05       0  6541.6     .07       0
Bank Sta=4991.6,5009.8
XS Rating Curve= 0 ,0
Exp/Cntr=0.3,0.1

Type RM Length L Ch R = 1 ,3666    ,452,452,452
BEGIN DESCRIPTION:
NORTH FORK QUEENS CREEK 7.0
END DESCRIPTION:
XS GIS Cut Line= 3
      2524224.99       13650175.        2524025.       13650225.
        2522825.       13651425.
#Sta/Elev= 30
  4794.2  264.59  4804.5   264.6  4826.5  262.77  4907.6  255.02  4969.4  251.48
  4977.1  250.02  4988.7   244.5  4989.2     244  5006.9   244.5  5014.5  244.98
  5028.6  250.12  5056.9  255.43  5071.1  255.93  5099.3  255.16  5188.5  255.13
  5339.8  255.15    5368  254.01  5396.3  253.89  5618.1  254.78  5650.9  255.66
  5915.4  257.69  6004.4  258.63  6032.7  260.05    6061  259.54  6117.6   260.7
  6329.7  266.08  6400.4   269.5  6414.6  269.25  6573.1  273.32  6697.4  276.79
#Mann= 8 ,-1 , 0
  4794.2     .07       0  4826.5     .12       0  4988.7     .05       0
  5006.9     .12       0  5188.5     .07       0  5618.1     .12       0
  5915.4     .07       0  6573.1     .05       0
Bank Sta=4988.7,5006.9
XS Rating Curve= 0 ,0
Exp/Cntr=0.3,0.1

Type RM Length L Ch R = 1 ,3214    ,463,463,463
BEGIN DESCRIPTION:
NORTH FORK QUEENS CREEK 6.0
END DESCRIPTION:
XS GIS Cut Line= 3
      2523974.97     13649725.03        2523825.       13649875.
      2522625.03     13651074.97
#Sta/Elev= 30
  4782.9   265.8  4825.3  264.32  4881.9  261.19  4938.4  259.62  4952.6   258.1
  4966.7  255.04  4980.8  250.59  4991.5  243.59  4998.5  243.59    5000     242
  5000.5   241.5  5018.2     242  5023.3  245.45  5037.4  250.18  5051.6  253.05
  5065.7  253.77  5129.9  253.64    5391  252.75  5546.5  252.89  5574.8  253.74
  5635.9  253.19  5759.7  254.32  5970.8  256.52  6140.5  259.96  6182.9  259.82
  6387.3   266.9  6593.1  274.28  6607.2  273.84  6677.9  276.75    6692   276.3
#Mann= 7 ,-1 , 0
  4782.9     .12       0    5000     .05       0  5018.2     .12       0
  5129.9     .07       0  5635.9     .12       0  5759.7     .07       0
  6387.3     .05       0
Bank Sta=5000,5018.2
XS Rating Curve= 0 ,0
Exp/Cntr=0.3,0.1

Type RM Length L Ch R = 1 ,2751    ,451,451,451
BEGIN DESCRIPTION:
NORTH FORK QUEENS CREEK 5.0
END DESCRIPTION:
XS GIS Cut Line= 3
      2523624.99     13649575.01        2523375.       13649825.
      2522774.98     13650425.02
#Sta/Elev= 30
  4645.9  261.08  4716.6  260.34  4787.3  257.95  4838.4  255.56  4886.3  253.45
  4914.6   251.2  4928.7  249.45    4939  249.15    4957  248.62  4971.2  247.19
  4986.8  240.72  4987.3  240.22  5004.6  240.22  5005.1  240.72  5013.6  248.64
  5027.7  251.75    5056  251.15  5109.4  252.24  5197.4  251.55  5282.3  252.64
  5296.4   252.2  5367.1  252.46  5480.3  253.92  5494.4  254.68  5565.1   255.8
  5651.3  256.65  5654.9  256.75  5678.3  257.72  5763.1  258.86    5848  261.03
#Mann= 8 ,-1 , 0
  4645.9     .05       0  4838.4     .12       0    4939      .1       0
  4986.8     .05       0  5005.1      .1       0  5109.4     .07       0
  5651.3     .12       0  5654.9     .05       0
Bank Sta=4986.8,5005.1
XS Rating Curve= 0 ,0
Exp/Cntr=0.3,0.1

Type RM Length L Ch R = 1 ,2300    ,421,421,421
BEGIN DESCRIPTION:
NORTH FORK QUEENS CREEK 4.0
END DESCRIPTION:
XS GIS Cut Line= 3
      2523775.04     13649274.98        2522975.       13649675.
      2522375.01     13650224.99
#Sta/Elev= 30
  4100.4  264.37  4279.3  260.61    4338  258.13  4391.1  258.03  4578.4  251.26
  4785.2  250.94  4807.6  251.91  4882.1  250.22  4958.5  249.86  4992.1  244.23
  4998.3  244.23  4999.5  241.91    5000  241.41  5017.9  241.91  5022.9  247.36
  5044.5  250.12  5059.3  249.85  5214.1   252.8  5419.4   255.1  5433.6  254.45
  5490.3  257.57    5568  259.72  5603.8   261.8  5610.6   261.9    5618  260.55
  5667.3  264.32  5695.7  264.64    5724  267.35  5773.4  269.34  5808.8  272.37
#Mann= 5 ,-1 , 0
  4100.4     .05       0  4882.1      .1       0  4999.5     .05       0
  5017.9      .1       0  5059.3     .05       0
Bank Sta=4999.5,5017.9
XS Rating Curve= 0 ,0
Exp/Cntr=0.3,0.1

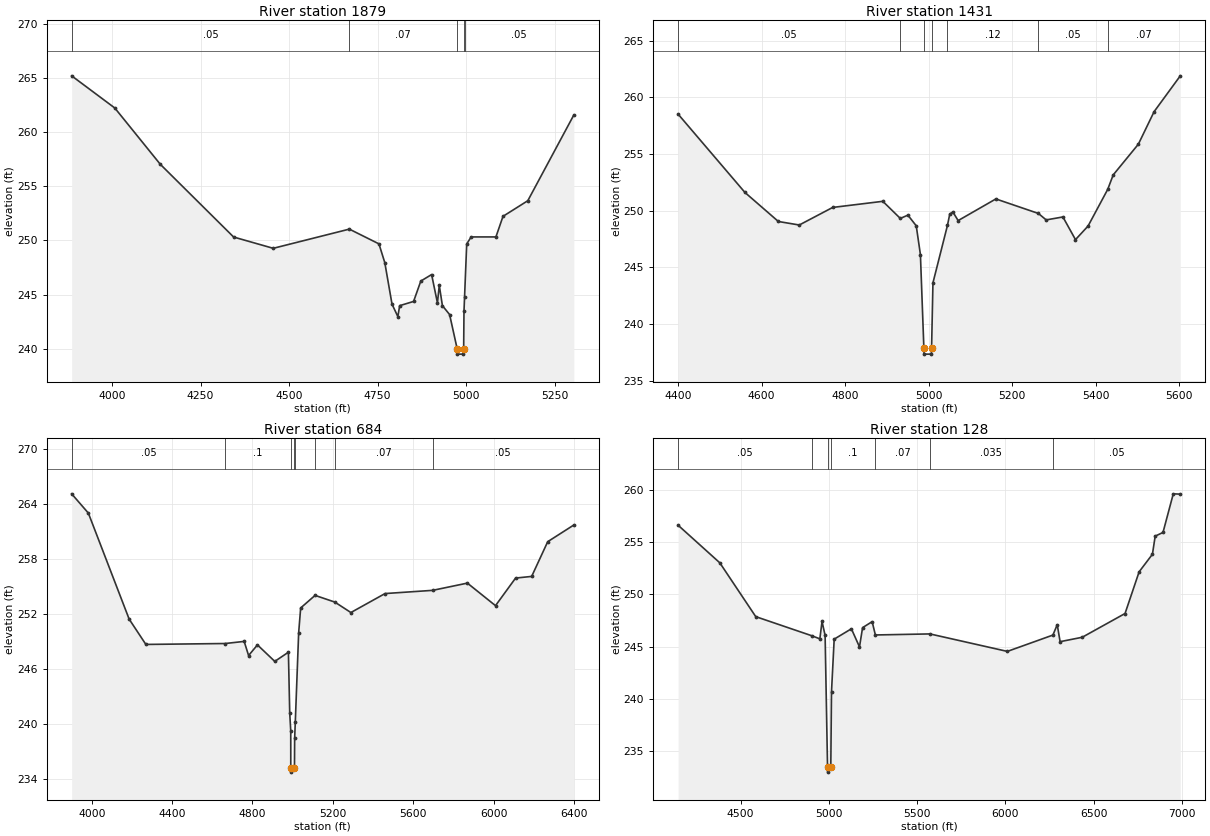
Type RM Length L Ch R = 1 ,1879    ,448,448,448
BEGIN DESCRIPTION:
NORTH FORK QUEENS CREEK 3.0
END DESCRIPTION:
XS GIS Cut Line= 3
      2523774.98       13649225.        2522675.       13649425.
      2522375.01       13649425.
#Sta/Elev= 30
  3886.1  265.18    4008  262.21  4136.4  257.02  4343.5  250.31  4455.3  249.27
  4670.2  251.04  4753.8  249.68  4770.3  247.95  4790.7  244.12  4807.2  242.97
  4812.3  243.98  4851.6  244.37    4872  246.25  4902.5  246.85    4919  244.23
  4924.1  245.86    4933  243.98  4953.3  243.16  4974.6  240.01  4975.1  239.51
  4992.5  239.51    4993  240.01  4993.9  243.45  4995.6  244.82  5001.6  249.67
  5014.1  250.32  5084.1  250.32  5104.1  252.22  5174.1  253.66  5304.1  261.57
#Mann= 5 ,-1 , 0
  3886.1     .05       0  4670.2     .07       0  4974.6     .05       0
    4993     .07       0  4995.6     .05       0
Bank Sta=4974.6,4993
XS Rating Curve= 0 ,0
Exp/Cntr=0.3,0.1

Type RM Length L Ch R = 1 ,1431    ,747,747,747
BEGIN DESCRIPTION:
NORTH FORK QUEENS CREEK 2.0
END DESCRIPTION:
XS GIS Cut Line= 3
      2523575.01       13649175.        2522975.       13649175.
      2522374.99       13649225.
#Sta/Elev= 30
  4400.4  258.51  4560.4   251.6  4640.4  249.04  4690.4  248.73  4770.4  250.28
  4890.4  250.82  4932.3  249.31  4950.4   249.6  4970.4  248.66  4980.4  246.12
  4988.7  237.84  4989.2  237.34  5006.6  237.34  5007.1  237.84  5010.4  243.63
  5045.1  248.69  5050.6  249.69  5058.1  249.88  5070.7  249.12    5161  251.03
  5262.8  249.75  5281.4  249.18  5321.5  249.44  5351.6  247.44  5381.7  248.64
  5428.7  251.87  5441.9  253.15  5502.1  255.86  5539.8  258.73  5602.5  261.89
#Mann= 7 ,-1 , 0
  4400.4     .05       0  4932.3      .1       0  4988.7     .05       0
  5007.1      .1       0  5045.1     .12       0  5262.8     .05       0
  5428.7     .07       0
Bank Sta=4988.7,5007.1
XS Rating Curve= 0 ,0
Exp/Cntr=0.3,0.1

Type RM Length L Ch R = 1 ,684     ,556,556,556
BEGIN DESCRIPTION:
NORTH FORK QUEENS CREEK 1.0
END DESCRIPTION:
XS GIS Cut Line= 3
      2523774.96     13649074.98      2522784.35     13648618.29
      2521374.98       13648625.
#Sta/Elev= 30
  3899.7  265.13  3982.8  263.03    4186  251.46  4269.2   248.7  4663.8   248.8
  4758.6  249.03  4780.6  247.49  4824.7  248.65    4911  246.85  4978.8  247.85
  4985.4  241.21  4990.5  239.26  4990.6  235.27  4991.1  234.77  5009.1  235.27
  5009.9  238.44  5013.2  240.25  5029.9  249.97  5039.9  252.68  5111.6  254.05
    5210  253.32  5289.9  252.18  5459.9  254.25  5696.8   254.6  5869.9  255.39
  6009.9  252.93  6109.9  255.94  6189.9  256.12  6269.9  259.91  6399.9  261.73
#Mann= 8 ,-1 , 0
  3899.7     .05       0  4663.8      .1       0  4990.6     .05       0
  5009.1      .1       0  5013.2     .12       0  5111.6    .035       0
    5210     .07       0  5696.8     .05       0
Bank Sta=4990.6,5009.1
XS Rating Curve= 0 ,0
Exp/Cntr=0.3,0.1

Type RM Length L Ch R = 1 ,128     ,0,0,0
BEGIN DESCRIPTION:
B19801
END DESCRIPTION:
XS GIS Cut Line= 4
      2523994.73     13648738.67      2523005.02     13648283.94
      2522202.58     13648116.77      2521380.04     13648564.82
#Sta/Elev= 30
  4145.8   256.6  4382.1  253.01  4585.7  247.87  4902.4  246.05  4948.9  245.75
  4961.2  247.41  4978.7  246.08  4992.4  233.52  4992.9  233.02  5010.9  233.52
  5014.9  240.69  5030.1  245.72  5127.6  246.71  5173.5  244.98    5191  246.82
  5245.2  247.39  5263.5  246.12  5572.5  246.22  6011.3  244.55  6269.4  246.11
    6294   247.1  6310.2  245.48  6435.5   245.9  6678.2  248.17  6757.9  252.15
  6833.4  253.83    6849  255.56  6893.2  255.91  6951.5   259.6  6991.3  259.57
#Mann= 7 ,-1 , 0
  4145.8     .05       0  4902.4      .1       0  4992.4     .05       0
  5010.9      .1       0  5263.5     .07       0  5572.5    .035       0
  6269.4     .05       0
Bank Sta=4992.4,5010.9
XS Rating Curve= 0 ,0
Exp/Cntr=0.3,0.1

Chan Stop Cuts=-1
Use User Specified Reach Order=0
Composite Channel Slope=5