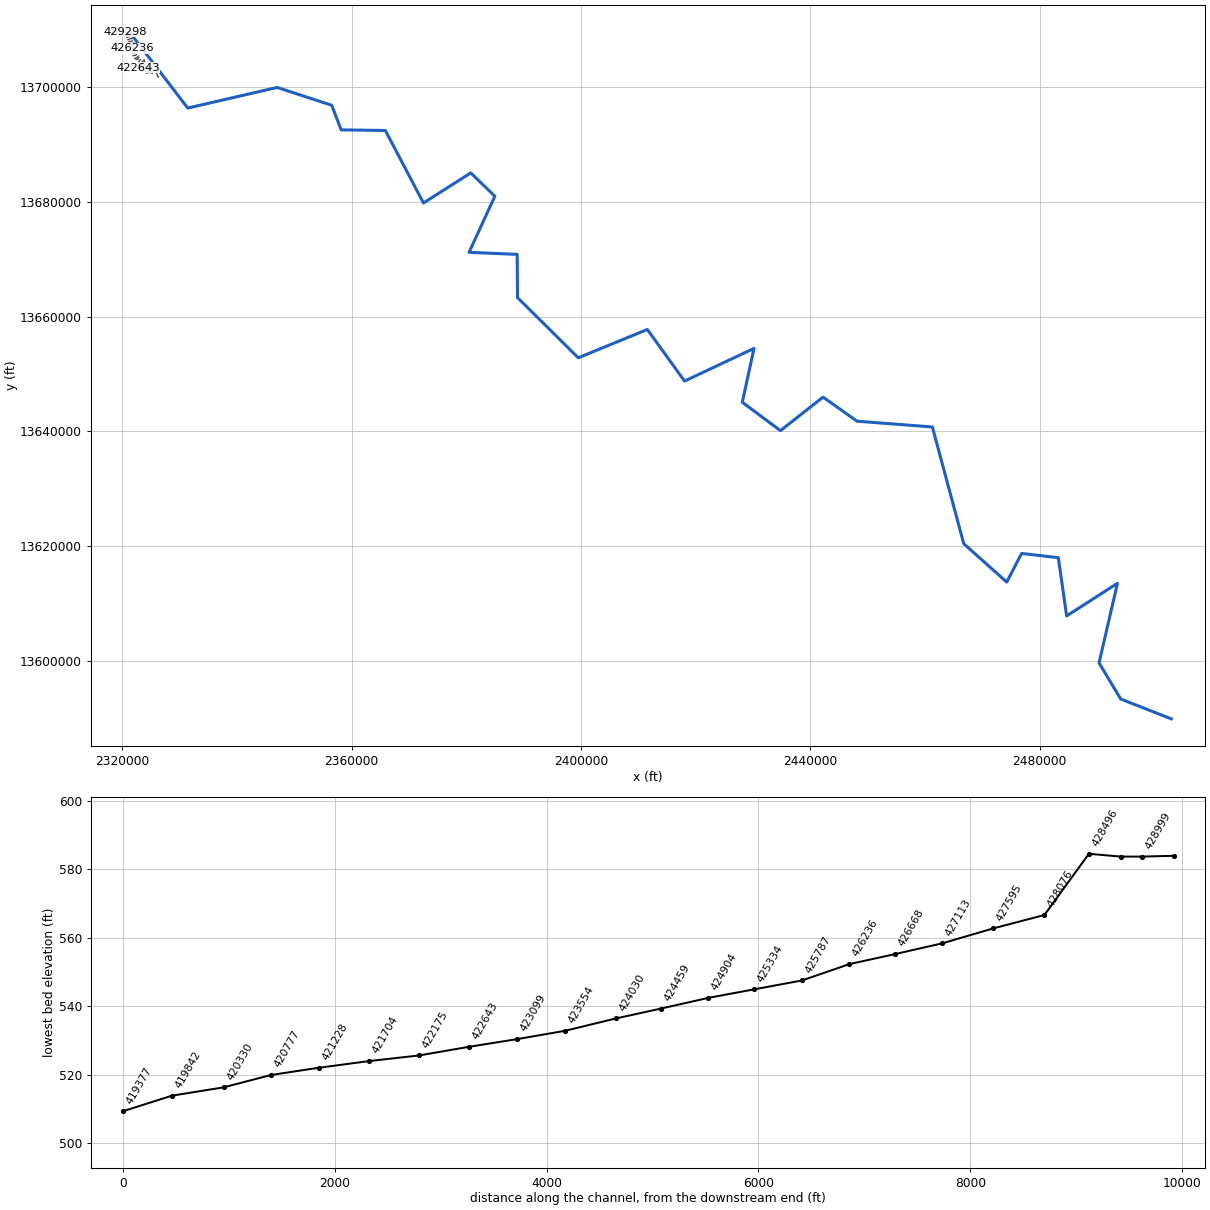
--- SANDIES CREEK.prj (project) ---

Proj Title=SANDIES CREEK Base Level Engineering
Current Plan=p01
Default Exp/Contr=0.3,0.1
English Units
Geom File=g01
Flow File=f01
Plan File=p01
Y Axis Title=Elevation
X Axis Title(PF)=Main Channel Distance
X Axis Title(XS)=Station
BEGIN DESCRIPTION:
SANDIES CREEK
END DESCRIPTION:
DSS Export Rating Curves= 0
DSS Export Rating Curve Sorted= 0
DSS Export Volume Flow Curves= 0
DXF OffsetX= 0
DXF OffsetY= 0
DXF ScaleX= 1
DXF ScaleY= 10

--- SANDIES CREEK.p01 (plan) ---

Plan Title=Multiple Run
Program Version=4.10
Short Identifier=Multiple
Geom File=g01
Flow File=f01
Subcritical Flow
K Sum by GR= 0
Std Step Tol= 0.01
Critical Tol= 0.01
Num of Std Step Trials= 20
Max Error Tol= 0.3
Flow Tol Ratio= 0.001
Split Flow NTrial= 30
Split Flow Tol= 0.02
Split Flow Ratio= 0.02
Log Output Level= 0
Friction Slope Method= 1
Unsteady Friction Slope Method= 2
Unsteady Bridges Friction Slope Method= 1
Parabolic Critical Depth
Global Vel Dist= 1 , 1 , 1
Global Log Level= 0
CheckData=True
Encroach Param=-1 ,0,0, 0
BEGIN DESCRIPTION:
Multiple Run
END DESCRIPTION:
Computation Interval=1HOUR
Output Interval=1HOUR
Run HTab= 0
Run UNet= 0
Run PostProcess= 0
Run WQNet= 0
UNET Theta= 1
UNET Theta Warmup= 1
UNET ZTol= 0.02
UNET ZSATol= 0.05
UNET MxIter= 20
UNET MaxInSteps= 0
UNET DtIC= 0
UNET DtMin= 0
UNET MaxCRTS= 20
UNET WFStab= 2
UNET SFStab= 1
UNET WFX= 1
UNET SFX= 1
UNET DSS MLevel= 4
UNET DZMax Abort= 100
UNET Convert EG Bridges= 0
UNET Use Existing IB Tables=-1
UNET Froude Reduction=False
UNET Froude Limit= 1
UNET Froude Power= 10
UNET Time Slicing=0,0, 5
UNET Junction Losses=0
Instantaneous Interval=1HOUR
Write IC File= 0
Write IC File at Sim End=0
Echo Input=False
Echo Parameters=False
Echo Output=False
Write Detailed= 0
WQ AD Non Conservative
WQ ULTIMATE=-1
WQ Max Comp Step=1HOUR
WQ Output Interval=15MIN
WQ Output Selected Increments= 0
WQ Output face flow=0
WQ Output face velocity=0
WQ Output face area=0
WQ Output face dispersion=0
WQ Output cell volume=0
WQ Output cell surface area=0
WQ Output cell continuity=0
WQ Output cumulative cell continuity=0
WQ Output face conc=0
WQ Output face dconc_dx=0
WQ Output face courant=0
WQ Output face peclet=0
WQ Output face adv mass=0
WQ Output face disp mass=0
WQ Output cell mass=0
WQ Output cell source sink temp=0
WQ Output cell source sink nsm=0
WQ Output MaxMinRange=-1
WQ Daily Max Min Mean=-1
WQ Daily Range=0
WQ Daily Time=0
WQ Create Restart=0
WQ Fixed Restart=0
WQ System Summary=0
WQ Use Fixed Temperature=0
Sorting and Armoring Iterations= 10
XS Update Threshold= 0.02
Hydraulics Update Threshold= 0.02
Energy Slope Method= 1
Volume Change Method= 0
XS Weighting Method= 0
Number of US Weighted Cross Sections= 1
Number of DS Weighted Cross Sections= 1
Upstream XS Weight=0.25
Main XS Weight=0.5
Downstream XS Weight=0.25
Number of DS XS's Weighted with US Boundary= 1
Upstream Boundary Weight= 1
Weight of XSs Associated with US Boundary= 0
Number of US XS's Weighted with DS Boundary= 1
Downstream Boundary Weight= 0.5
Weight of XSs Associated with DS Boundary= 0.5
Sediment Output Level= 4
Mass or Volume Output= 0
Output Increment Type= 1
Profile and TS Output Increment= 10
XS Output Flag= 0
XS Output Increment= 10
Disregard all LS=0
Disregard all Conn=0
Disregard all Breaches=0
Disregard all Pumps=0

--- SANDIES CREEK.f01 (steady flow) ---

Flow Title=Multiple
Number of Profiles=7
Profile Names=10-year,25-year,50-year,1pct_min,100-year,1pct_plu,500-year
River Rch & RM= SANDIES CREEK,Reach-1,429298
    1043    1769    2459    1655    3301    6587    5902
River Rch & RM= SANDIES CREEK,Reach-1,424459
    1305    2238    3133    2122    4233    8447    7670
River Rch & RM= SANDIES CREEK,Reach-1,422643
    2144    3726    5260    3584    7150   14266   13113
River Rch & RM= SANDIES CREEK,Reach-1,419377
    2266    3944    5573    3799    7580   15125   13922
River Rch & RM= SANDIES CREEK,Reach-1,418051
    3422    6109    8784    6091   12153   24249   23093
River Rch & RM= SANDIES CREEK,Reach-1,415824
    3271    5789    8274    5701   11375   22696   21338
River Rch & RM= SANDIES CREEK,Reach-1,412246
    3777    6714    9623    6646   13260   26458   24992
River Rch & RM= SANDIES CREEK,Reach-1,409544
    4242    7550   10829    7481   14927   29783   28148
River Rch & RM= SANDIES CREEK,Reach-1,404582
    5203    9307   13397    9282   18519   36951   35122
River Rch & RM= SANDIES CREEK,Reach-1,401856
    5396    9632   13845    9576   19106   38122   36109
River Rch & RM= SANDIES CREEK,Reach-1,395245
    5411    9650   13861    9580   19114   38137   36066
River Rch & RM= SANDIES CREEK,Reach-1,392861
    6324   11326   16315   11304   22555   45003   42773
River Rch & RM= SANDIES CREEK,Reach-1,388959
    6693   12002   17306   12001   23945   47777   45484
River Rch & RM= SANDIES CREEK,Reach-1,386765
    7269   13053   18840   13075   26088   52052   49624
River Rch & RM= SANDIES CREEK,Reach-1,382815
    7156   12820   18473   12798   25536   50950   48405
River Rch & RM= SANDIES CREEK,Reach-1,379389
    7414   13277   19127   13246   26429   52732   50057
River Rch & RM= SANDIES CREEK,Reach-1,372148
    8629   15448   22255   15410   30746   61347   58178
River Rch & RM= SANDIES CREEK,Reach-1,367778
    8481   15105   21685   14958   29846   59551   56051
River Rch & RM= SANDIES CREEK,Reach-1,355152
    9061   16109   23097   15909   31743   63335   59427
River Rch & RM= SANDIES CREEK,Reach-1,341127
    8932   15802   22579   15496   30919   61691   57464
River Rch & RM= SANDIES CREEK,Reach-1,327095
   12447   22166   31829   21942   43780   87354   82057
River Rch & RM= SANDIES CREEK,Reach-1,325634
   12456   22160   31799   21905   43706   87205   81796
River Rch & RM= SANDIES CREEK,Reach-1,322036
   13014   23160   33243   22904   45700   91183   85554
River Rch & RM= SANDIES CREEK,Reach-1,318962
   12609   22323   31926   21914   43724   87241   81236
River Rch & RM= SANDIES CREEK,Reach-1,306304
   12527   22120   31578   21634   43166   86127   79893
River Rch & RM= SANDIES CREEK,Reach-1,299224
   12386   21835   31135   21306   42510   84819   78492
River Rch & RM= SANDIES CREEK,Reach-1,295345
   12373   21792   31055   21236   42372   84544   78132
River Rch & RM= SANDIES CREEK,Reach-1,290464
   12139   21308   30294   20666   41234   82272   75662
River Rch & RM= SANDIES CREEK,Reach-1,279261
   16235   28615   40816   27927   55721  111179  102806
River Rch & RM= SANDIES CREEK,Reach-1,272205
   16138   28423   40520   27709   55286  110311  101888
River Rch & RM= SANDIES CREEK,Reach-1,258762
   16458   28932   41193   28132   56130  111994  103159
River Rch & RM= SANDIES CREEK,Reach-1,254740
   16371   28735   40870   27881   55629  110995  102015
River Rch & RM= SANDIES CREEK,Reach-1,246761
   16426   28823   40986   27953   55774  111283  102229
River Rch & RM= SANDIES CREEK,Reach-1,243495
   16245   28439   40376   27491   54852  109445  100206
River Rch & RM= SANDIES CREEK,Reach-1,232877
   16192   28325   40194   27353   54576  108894   99597
River Rch & RM= SANDIES CREEK,Reach-1,230496
   16729   29186   41348   28093   56054  111842  101917
River Rch & RM= SANDIES CREEK,Reach-1,226352
   16202   28119   39693   26867   53606  106959   96730
River Rch & RM= SANDIES CREEK,Reach-1,195266
   16110   27929   39396   26645   53164  106077   95784
River Rch & RM= SANDIES CREEK,Reach-1,192284
   23030   40054   56661   38427   76671  152980  138786
River Rch & RM= SANDIES CREEK,Reach-1,180064
   22926   39831   56304   38156   76131  151902  137599
River Rch & RM= SANDIES CREEK,Reach-1,175847
   21867   37755   53141   35852   71535  142730  128141
River Rch & RM= SANDIES CREEK,Reach-1,151107
   21497   37011   51992   35006   69845  139360  124604
River Rch & RM= SANDIES CREEK,Reach-1,138892
   27999   48193   67736   45631   91046  181660  162456
River Rch & RM= SANDIES CREEK,Reach-1,122412
   26545   45666   64145   43183   86161  171913  153595
River Rch & RM= SANDIES CREEK,Reach-1,114551
   26524   45597   64018   43075   85946  171485  153054
River Rch & RM= SANDIES CREEK,Reach-1,108262
   26373   45289   63539   42720   85237  170071  151559
River Rch & RM= SANDIES CREEK,Reach-1,102588
   26703   45857   64338   43259   86313  172218  153481
River Rch & RM= SANDIES CREEK,Reach-1,100165
   26730   45895   64384   43285   86365  172321  153537
River Rch & RM= SANDIES CREEK,Reach-1,97613
   26595   45612   63939   42952   85700  170994  152112
River Rch & RM= SANDIES CREEK,Reach-1,88849
   26583   45576   63873   42897   85591  170777  151844
River Rch & RM= SANDIES CREEK,Reach-1,78894
   26602   45607   63915   42925   85656  170886  151935
River Rch & RM= SANDIES CREEK,Reach-1,75100
   26756   45870   64283   43171   86138  171868  152802
River Rch & RM= SANDIES CREEK,Reach-1,73244
   26694   45747   64094   43033   85862  171318  152234
River Rch & RM= SANDIES CREEK,Reach-1,67798
   26348   45070   63065   42286   84371  168343  149191
River Rch & RM= SANDIES CREEK,Reach-1,56553
   28564   48828   68308   45790   91362  182292  161441
River Rch & RM= SANDIES CREEK,Reach-1,45289
   28552   48795   68248   45741   91266  182100  161209
River Rch & RM= SANDIES CREEK,Reach-1,42593
   28466   48625   67990   45553   90891  181351  160442
River Rch & RM= SANDIES CREEK,Reach-1,37651
   28179   48069   67148   44945   89677  178930  157987
River Rch & RM= SANDIES CREEK,Reach-1,23541
   27977   47678   66557   44518   88825  177230  156267
River Rch & RM= SANDIES CREEK,Reach-1,16506
   28622   48776   68092   45547   90878  181326  159884
River Rch & RM= SANDIES CREEK,Reach-1,8506
   28548   48618   67841   45358   90501  180573  159069
Boundary for River Rch & Prof#=SANDIES CREEK,Reach-1,1
Up Type=0
Dn Type=3
Dn Slope=0.0003
Boundary for River Rch & Prof#=SANDIES CREEK,Reach-1,2
Up Type=0
Dn Type=3
Dn Slope=0.0003
Boundary for River Rch & Prof#=SANDIES CREEK,Reach-1,3
Up Type=0
Dn Type=3
Dn Slope=0.0003
Boundary for River Rch & Prof#=SANDIES CREEK,Reach-1,4
Up Type=0
Dn Type=3
Dn Slope=0.0003
Boundary for River Rch & Prof#=SANDIES CREEK,Reach-1,5
Up Type=0
Dn Type=3
Dn Slope=0.0003
Boundary for River Rch & Prof#=SANDIES CREEK,Reach-1,6
Up Type=0
Dn Type=3
Dn Slope=0.0003
Boundary for River Rch & Prof#=SANDIES CREEK,Reach-1,7
Up Type=0
Dn Type=3
Dn Slope=0.0003

--- SANDIES CREEK.g01 (geometry) ---

Geom Title=Existing Conditions
Program Version=4.10

River Reach=SANDIES CREEK   ,Reach-1
Reach XY= 30
       2321248.4     13709656.73      2331426.34     13696378.27
      2347019.14     13699972.93      2356531.06     13696866.86
      2358176.46     13692578.54      2365884.82     13692464.53
      2372526.56     13679828.76        2380775.       13685075.
      2384975.44     13681004.82      2380480.83      13671222.7
      2388869.38     13670869.38      2388930.84     13663322.71
      2399522.41     13652830.14       2411564.5      13657773.8
      2418050.09     13648774.79       2430164.3      13654474.3
      2428127.35     13645080.98       2434776.5     13640128.46
      2442199.92      13645975.2      2448130.48     13641777.08
      2461266.99     13640772.16      2466738.49     13620411.44
      2474235.47     13613725.93      2476826.28     13618721.48
        2483225.       13617975.      2484680.85     13607827.06
      2493538.24     13613511.39      2490328.38      13599626.4
      2494114.89     13593335.38        2502925.       13589875.

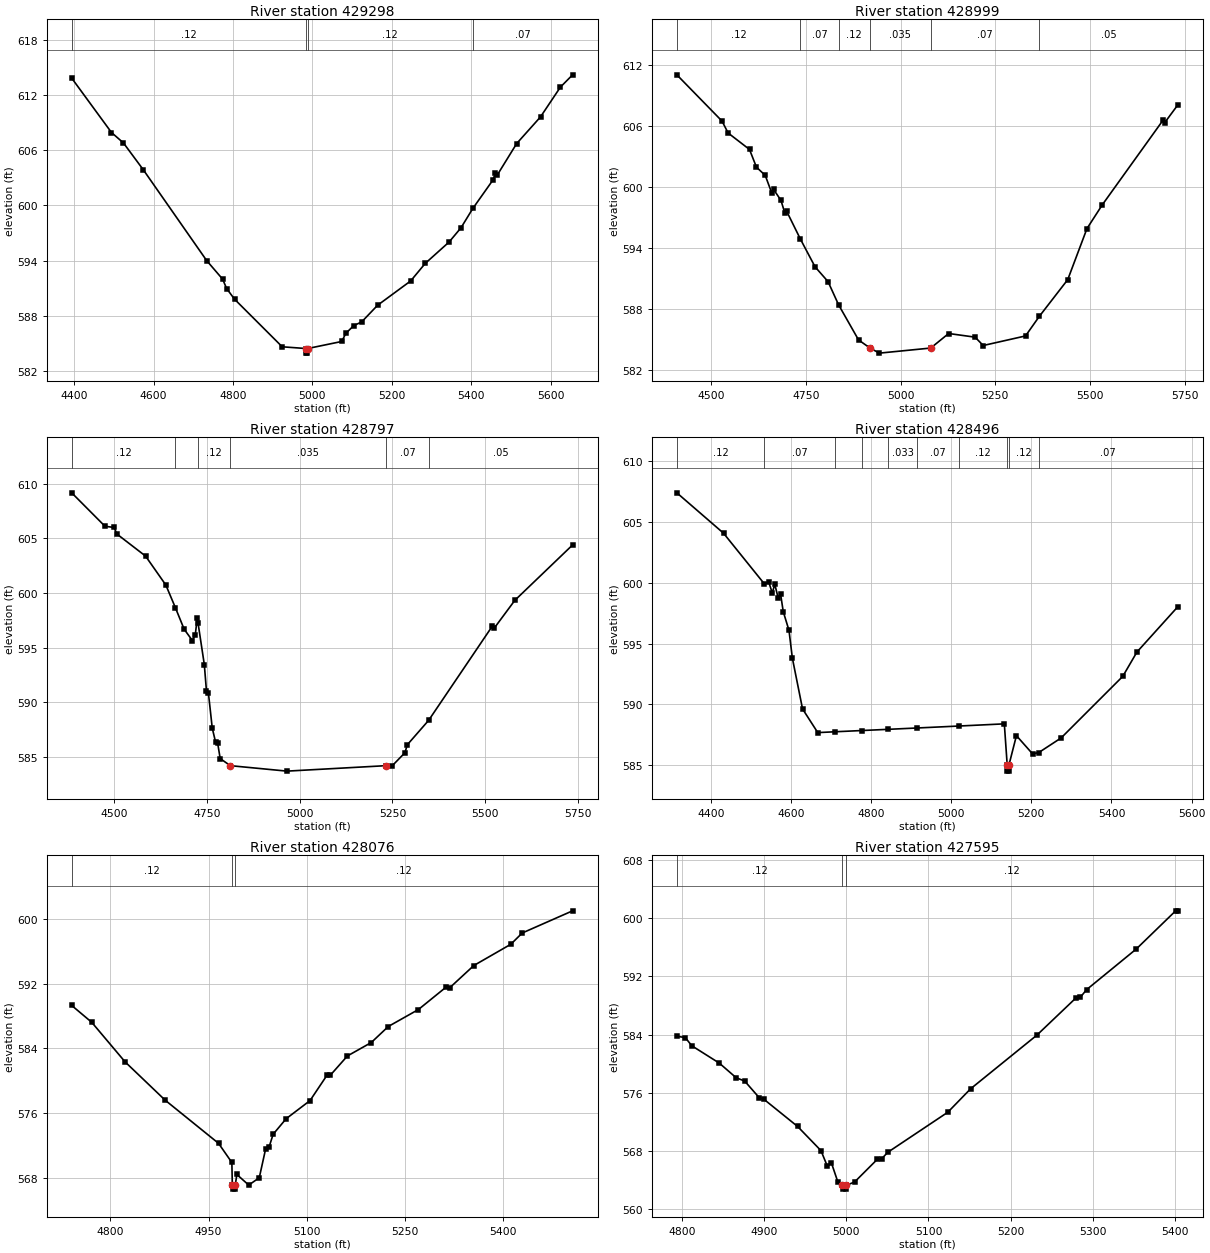
Type RM Length L Ch R = 1 ,429298  ,299,299,299
BEGIN DESCRIPTION:
C20484b
END DESCRIPTION:
XS GIS Cut Line= 3
      2321845.15      13709637.2      2321241.89     13709628.52
      2320584.32      13709658.9
#Sta/Elev= 30
  4393.8  613.86    4494  607.94    4524  606.81    4574  603.89    4734  593.98
    4774  591.97    4784  590.95    4804  589.79    4924  584.61    4984  584.42
  4984.2  583.92  4987.7  583.92    4988  584.42  5074.1  585.19  5084.1  586.07
  5104.1  586.91  5124.2  587.32  5164.2  589.13  5247.6  591.78  5284.3  593.69
  5344.4  596.02  5374.4  597.57  5404.1  599.67  5454.5  602.75  5461.1  603.55
  5466.1  603.34  5514.6  606.74  5574.6  609.64  5624.7  612.88  5655.4  614.22
#Mann= 4 ,-1 , 0
  4393.8     .12       0    4984     .05       0    4988     .12       0
  5404.1     .07       0
Bank Sta=4984,4988
XS Rating Curve= 0 ,0
Exp/Cntr=0.3,0.1

Type RM Length L Ch R = 1 ,428999  ,202,202,202
BEGIN DESCRIPTION:
C20484a
END DESCRIPTION:
XS GIS Cut Line= 3
      2321830.04      13709485.3      2321265.76     13709333.38
      2320538.77     13709214.02
#Sta/Elev= 30
    4410  611.06  4529.1  606.51  4545.2  605.34  4601.6  603.72  4619.9  601.98
  4643.1  601.17  4659.9  599.48  4665.1  599.79  4684.5  598.72  4694.6  597.49
  4699.8  597.63  4735.5  594.93  4774.5  592.18  4808.8  590.72  4836.6  588.44
  4889.2  584.99  4919.4  584.19  4944.2  583.69  5079.6  584.19  5126.9  585.62
  5196.6  585.26  5218.1  584.44  5329.6  585.38  5366.1  587.31    5441  590.92
  5491.7  595.94  5532.2  598.28  5691.8  606.57  5696.8  606.36  5731.1  608.09
#Mann= 6 ,-1 , 0
    4410     .12       0  4735.5     .07       0  4836.6     .12       0
  4919.4    .035       0  5079.6     .07       0  5366.1     .05       0
Bank Sta=4919.4,5079.6
XS Rating Curve= 0 ,0
Exp/Cntr=0.3,0.1

Type RM Length L Ch R = 1 ,428797  ,301,301,301
BEGIN DESCRIPTION:
C20484
END DESCRIPTION:
XS GIS Cut Line= 3
      2321838.77     13709350.15      2321152.41     13709087.04
      2320545.86     13708984.04
#Sta/Elev= 30
  4385.5  609.16  4475.2   606.1  4499.8  605.99  4507.3  605.39  4584.6  603.37
  4639.3  600.72  4665.1  598.64  4688.6  596.68  4710.8  595.64  4718.7  596.18
    4724  597.74    4726  597.26    4743  593.44  4748.7  591.06  4754.1  590.82
  4764.4  587.62  4773.4  586.34  4778.7   586.3  4785.8  584.84  4813.1  584.19
  4965.6  583.69  5233.1  584.19  5249.8  584.19  5283.7  585.37  5290.4  586.11
  5347.8  588.34  5519.8  596.98  5524.9  596.79  5580.1  599.32  5735.8  604.39
#Mann= 6 ,-1 , 0
  4385.5     .12       0  4665.1     .07       0    4726     .12       0
  4813.1    .035       0  5233.1     .07       0  5347.8     .05       0
Bank Sta=4813.1,5233.1
XS Rating Curve= 0 ,0
Exp/Cntr=0.3,0.1

Type RM Length L Ch R = 1 ,428496  ,420,420,420
BEGIN DESCRIPTION:
SANDIES CREEK 1.0
END DESCRIPTION:
XS GIS Cut Line= 6
      2321838.66     13709283.45       2321582.6     13709094.66
      2321413.33     13708934.07      2321351.79     13708848.06
      2321098.66      13708808.2      2320788.29     13708680.15
#Sta/Elev= 30
  4315.5   607.4  4431.9  604.08    4534   599.9  4545.1  600.03  4553.6  599.16
  4559.8  599.88  4568.2  598.76  4574.4  599.05    4581  597.62  4595.3  596.08
  4603.7   593.8  4629.1  589.62  4667.1  587.67  4711.2  587.74  4776.8  587.84
  4843.2  587.94  4915.1  588.05    5019  588.21  5132.6  588.39  5139.8     585
  5140.1   584.5  5143.8   584.5  5144.1     585  5162.8  587.42  5203.1  585.92
  5218.6  586.03  5274.3  587.23  5428.2   592.3  5463.5   594.3  5565.3  598.02
#Mann= 10 ,-1 , 0
  4315.5     .12       0    4534     .07       0  4711.2      .1       0
  4776.8     .07       0  4843.2    .033       0  4915.1     .07       0
    5019     .12       0  5139.8     .05       0  5144.1     .12       0
  5218.6     .07       0
Bank Sta=5139.8,5144.1
XS Rating Curve= 0 ,0
Exp/Cntr=0.3,0.1

Type RM Length L Ch R = 1 ,428076  ,481,481,481
BEGIN DESCRIPTION:
SANDIES CREEK 2.0
END DESCRIPTION:
XS GIS Cut Line= 3
      2321725.05     13708525.01        2321475.       13708475.
      2320992.21     13708308.78
#Sta/Elev= 30
  4740.8  589.31  4771.4  587.23  4822.4  582.34  4883.6  577.61  4965.2  572.28
  4985.6  569.91  4986.3  567.12  4986.7  566.62  4990.5  566.62  4990.8  567.12
  4993.2  568.43  5011.4  567.12  5027.5  568.03  5037.3  571.62  5042.6  571.85
  5048.7   573.4  5068.6  575.32  5105.1  577.56    5131  580.69  5136.3  580.71
  5162.2  583.07  5198.7  584.73  5224.7  586.71  5270.8  588.81  5313.1  591.58
  5318.4  591.48  5355.4  594.24    5412  596.87  5429.4  598.26  5506.4     601
#Mann= 3 ,-1 , 0
  4740.8     .12       0  4986.3     .05       0  4990.8     .12       0
Bank Sta=4986.3,4990.8
XS Rating Curve= 0 ,0
Exp/Cntr=0.3,0.1

Type RM Length L Ch R = 1 ,427595  ,482,482,482
BEGIN DESCRIPTION:
SANDIES CREEK 3.0
END DESCRIPTION:
XS GIS Cut Line= 3
      2321775.02     13708075.01        2321575.       13708025.
      2321174.99       13707975.
#Sta/Elev= 30
  4793.9  583.76  4804.2  583.58    4812  582.46  4845.5  580.07  4866.1  578.05
  4876.4   577.6  4894.4  575.27  4899.6  575.11  4940.8  571.35  4969.2  568.03
  4976.9   565.9    4982  566.31  4989.8   563.7  4995.2  563.23  4995.5  562.73
  4999.4  562.73  4999.7  563.23  5010.2  563.72  5037.9  566.85  5042.9  566.89
  5050.5   567.8  5123.5  573.31  5151.2  576.53  5231.9  583.92  5279.7  589.07
  5284.8  589.14  5292.3  590.17  5352.8  595.77  5400.7  601.02  5403.2  601.02
#Mann= 3 ,-1 , 0
  4793.9     .12       0  4995.2     .05       0  4999.7     .12       0
Bank Sta=4995.2,4999.7
XS Rating Curve= 0 ,0
Exp/Cntr=0.3,0.1

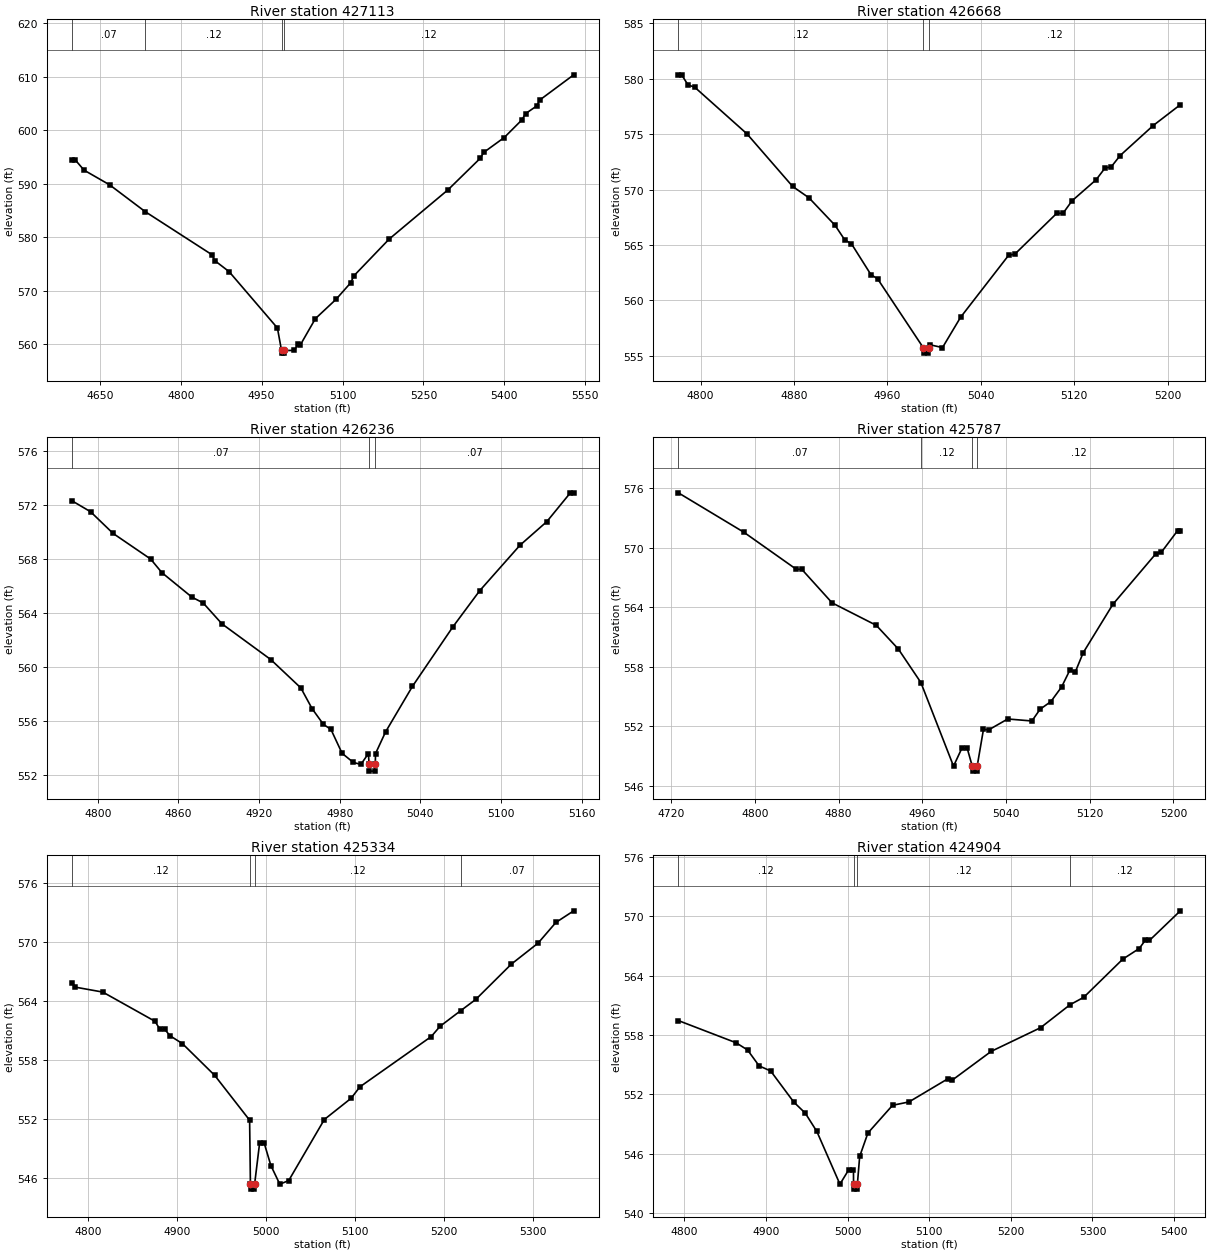
Type RM Length L Ch R = 1 ,427113  ,445,445,445
BEGIN DESCRIPTION:
SANDIES CREEK 4.0
END DESCRIPTION:
XS GIS Cut Line= 3
      2322056.62     13707702.18        2321675.       13707575.
      2321169.57     13707421.75
#Sta/Elev= 30
  4598.1  594.42    4605  594.38  4620.9  592.52  4668.3  589.78  4734.3  584.77
    4858  576.73  4863.3  575.62  4889.7  573.58  4979.3  563.05  4986.9  558.86
  4987.2  558.36  4991.1  558.36  4991.4  558.86  5010.8  558.86  5016.8  559.98
    5022  559.93  5049.7   564.8  5087.8  568.39  5115.3  571.51  5120.7  572.76
  5186.6  579.67  5295.7  588.87  5355.6  594.77  5361.5  595.82  5399.7  598.61
  5432.6  601.92  5439.2  603.07  5460.1  604.52  5465.5  605.61  5528.5  610.32
#Mann= 4 ,-1 , 0
  4598.1     .07       0  4734.3     .12       0  4986.9     .05       0
  4991.4     .12       0
Bank Sta=4986.9,4991.4
XS Rating Curve= 0 ,0
Exp/Cntr=0.3,0.1

Type RM Length L Ch R = 1 ,426668  ,432,432,432
BEGIN DESCRIPTION:
SANDIES CREEK 5.0
END DESCRIPTION:
XS GIS Cut Line= 3
      2322024.97     13707274.98        2321825.       13707175.
      2321625.02     13707125.01
#Sta/Elev= 30
    4781  580.36  4783.8  580.36  4789.3  579.44  4794.9  579.25  4839.7  575.03
  4878.8  570.28  4892.8  569.25  4915.1  566.77  4923.5  565.44  4929.1  565.11
  4945.9   562.3  4951.5  561.94  4990.6  555.72  4990.9  555.22  4994.8  555.22
  4995.2  555.72  4996.2  555.98  5007.1  555.72  5022.6  558.46  5063.8  564.07
    5069  564.16  5105.1  567.87  5110.2  567.84    5118  568.98  5138.6  570.88
  5146.3  571.95  5151.5  572.04  5159.2  573.07  5187.5  575.78  5210.7  577.66
#Mann= 3 ,-1 , 0
    4781     .12       0  4990.6     .05       0  4995.2     .12       0
Bank Sta=4990.6,4995.2
XS Rating Curve= 0 ,0
Exp/Cntr=0.3,0.1

Type RM Length L Ch R = 1 ,426236  ,449,449,449
BEGIN DESCRIPTION:
SANDIES CREEK 6.0
END DESCRIPTION:
XS GIS Cut Line= 3
        2322125.       13706875.        2321925.       13706775.
        2321775.       13706775.
#Sta/Elev= 30
  4780.6  572.31  4794.6  571.49  4811.3  569.89  4839.3  567.99  4847.7  566.98
    4870  565.17  4878.4  564.74  4892.4  563.19  4928.7  560.55  4951.1  558.45
  4959.5  556.91  4967.9  555.75  4973.5  555.38  4981.8  553.61  4990.2  552.93
  4995.8  552.79  5001.4  553.59  5001.9  552.79  5002.2  552.29  5006.2  552.29
  5006.5  552.79  5006.7  553.59  5014.2   555.2  5034.2  558.57  5064.2  562.96
  5084.2  565.64  5114.2  569.01  5134.2  570.76  5151.7  572.89  5154.2  572.89
#Mann= 3 ,-1 , 0
  4780.6     .07       0  5001.9     .05       0  5006.5     .07       0
Bank Sta=5001.9,5006.5
XS Rating Curve= 0 ,0
Exp/Cntr=0.3,0.1

Type RM Length L Ch R = 1 ,425787  ,453,453,453
BEGIN DESCRIPTION:
SANDIES CREEK 7.0
END DESCRIPTION:
XS GIS Cut Line= 4
      2322334.39     13706461.46        2322225.       13706425.
        2322075.       13706375.      2321874.98       13706325.
#Sta/Elev= 30
    4727  575.52  4789.6  571.55  4839.7  567.82  4844.9  567.82  4873.9  564.44
  4916.1  562.18  4937.2  559.79  4958.7  556.42  4989.9     548  4997.8  549.79
    5003  549.79  5007.8     548  5008.1   547.5  5012.1   547.5  5012.5     548
  5018.5   551.7  5023.6  551.66  5041.7  552.75  5064.8  552.55  5072.6  553.73
  5082.9   554.5  5093.2  555.98  5100.9  557.64  5106.1  557.45  5113.8  559.42
  5142.2   564.3  5183.4  569.41  5188.5  569.54    5204  571.71  5206.6  571.71
#Mann= 4 ,-1 , 0
    4727     .07       0  4958.7     .12       0  5007.8     .05       0
  5012.5     .12       0
Bank Sta=5007.8,5012.5
XS Rating Curve= 0 ,0
Exp/Cntr=0.3,0.1

Type RM Length L Ch R = 1 ,425334  ,430,430,430
BEGIN DESCRIPTION:
SANDIES CREEK 8.0
END DESCRIPTION:
XS GIS Cut Line= 4
      2322416.09     13706070.55        2322325.       13706025.
        2322225.       13705975.      2321875.05       13705975.
#Sta/Elev= 30
  4781.7  565.88  4785.7  565.41  4816.5  564.91  4875.2  561.94  4880.8  561.11
  4886.3  561.11  4891.9  560.48  4905.9  559.68  4942.2  556.45  4981.4   551.9
  4982.3   545.4  4982.7   544.9  4986.7   544.9    4987   545.4  4992.6  549.56
  4997.8  549.56  5005.3  547.29  5015.3   545.4  5025.3  545.77  5065.3  551.97
  5095.3  554.12  5105.3  555.29  5185.3  560.39  5195.3  561.44  5218.4  563.02
  5235.3  564.16  5275.3  567.75  5305.3  569.88  5325.3  571.98  5345.3  573.16
#Mann= 4 ,-1 , 0
  4781.7     .12       0  4982.3     .05       0    4987     .12       0
  5218.4     .07       0
Bank Sta=4982.3,4987
XS Rating Curve= 0 ,0
Exp/Cntr=0.3,0.1

Type RM Length L Ch R = 1 ,424904  ,445,445,445
BEGIN DESCRIPTION:
SANDIES CREEK 9.0
END DESCRIPTION:
XS GIS Cut Line= 3
      2322474.98     13705724.98        2322325.       13705575.
      2321925.02       13705525.
#Sta/Elev= 30
  4792.5  559.45  4863.2  557.21  4877.3  556.48  4891.5  554.87  4905.6  554.36
  4933.9  551.22    4948   550.1  4962.2  548.25  4990.5  542.92  5001.1  544.35
  5007.1  544.35  5007.2  542.92  5007.5  542.42  5011.6  542.42  5011.9  542.92
  5014.7  545.72  5024.8  548.09    5055  550.89  5075.1  551.23    5123  553.58
  5128.1  553.43  5175.9  556.34  5236.4  558.73  5272.5  561.05  5289.3   561.8
  5337.2  565.66  5357.3  566.73  5364.9  567.58  5369.9  567.55  5407.7  570.54
#Mann= 4 ,-1 , 0
  4792.5     .12       0  5007.2     .05       0  5011.9     .12       0
  5272.5     .12       0
Bank Sta=5007.2,5011.9
XS Rating Curve= 0 ,0
Exp/Cntr=0.3,0.1

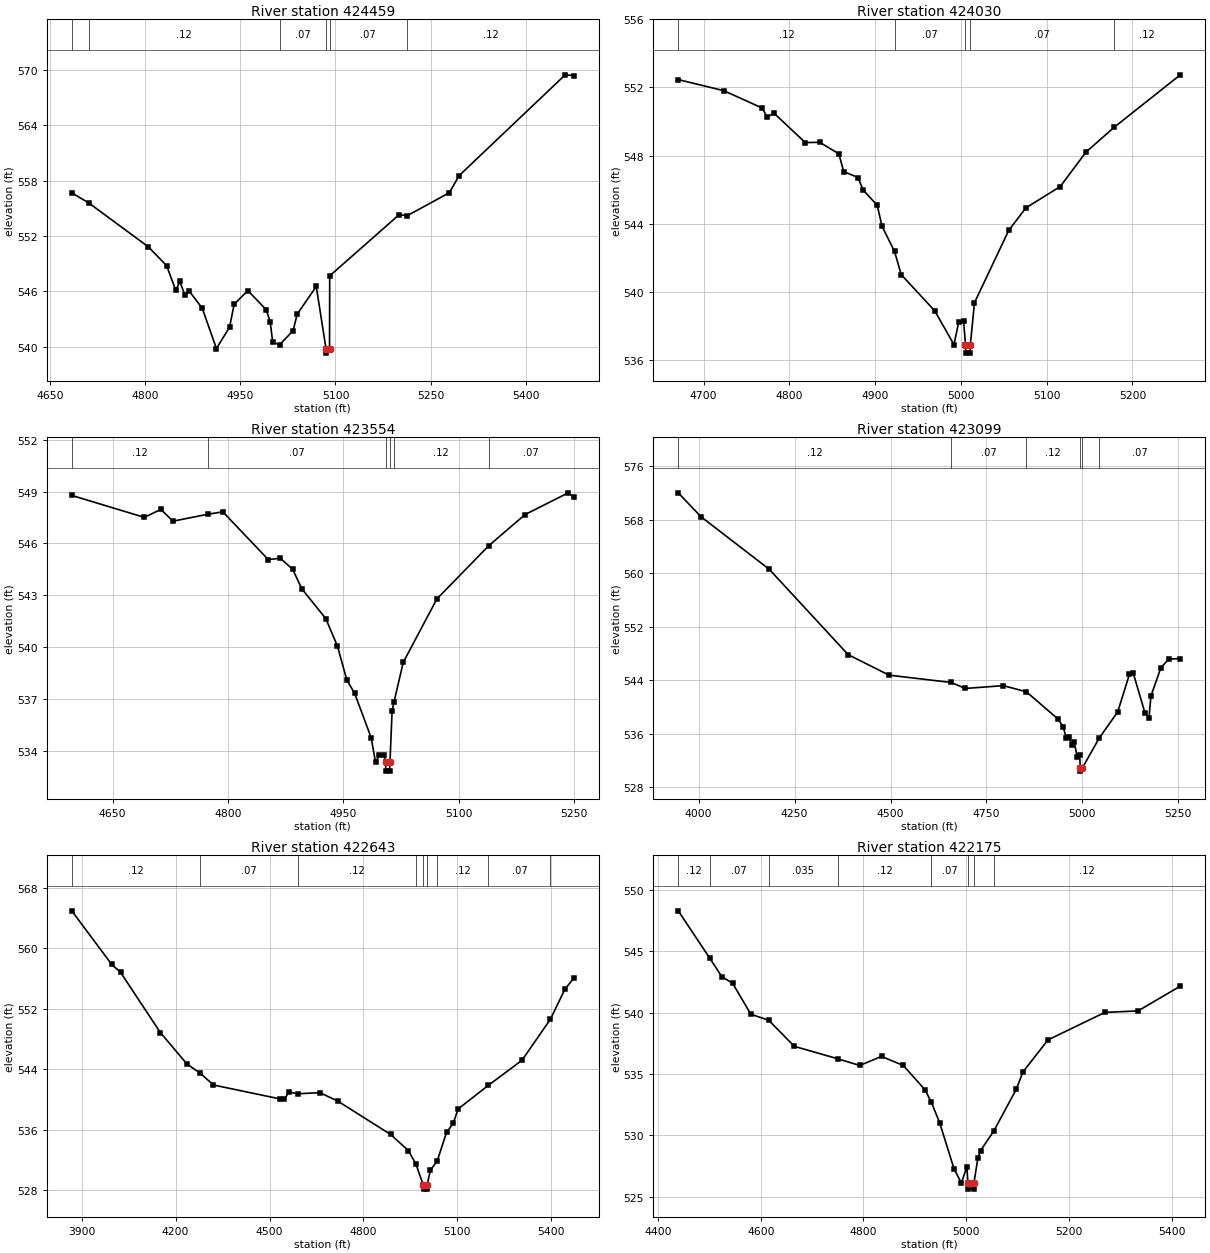
Type RM Length L Ch R = 1 ,424459  ,429,429,429
BEGIN DESCRIPTION:
SANDIES CREEK 10.0
END DESCRIPTION:
XS GIS Cut Line= 3
      2322824.96     13705424.97        2322575.       13705225.
      2322175.01       13704975.
#Sta/Elev= 30
  4684.1  556.69  4711.3  555.57  4804.9  550.83  4833.7  548.79  4848.1  546.11
  4854.5  547.08  4862.5   545.6  4868.9  546.07  4889.8  544.19  4912.2  539.81
    4933  542.13  4940.2  544.61  4961.8  546.09  4990.6  544.03    4997  542.72
    5001  540.48    5012  540.22  5033.1  541.74  5039.6  543.53  5069.7  546.54
    5085  539.81  5085.5  539.31  5090.6  539.81  5090.9  547.69  5200.6  554.33
  5212.9   554.2  5279.6   556.7  5294.9  558.55  5462.3  569.48  5475.9   569.4
#Mann= 6 ,-1 , 0
  4684.1    .035       0  4711.3     .12       0    5012     .07       0
    5085     .05       0  5090.6     .07       0  5212.9     .12       0
Bank Sta=5085,5090.6
XS Rating Curve= 0 ,0
Exp/Cntr=0.3,0.1

Type RM Length L Ch R = 1 ,424030  ,476,476,476
BEGIN DESCRIPTION:
SANDIES CREEK 11.0
END DESCRIPTION:
XS GIS Cut Line= 3
      2322875.02     13705175.03        2322725.       13704875.
      2322475.05       13704875.
#Sta/Elev= 30
  4670.4  552.46  4723.5  551.81  4768.3  550.79  4773.9  550.27  4782.2  550.48
  4818.6  548.76  4835.3  548.78  4857.7   548.1  4863.3  547.06  4880.1  546.71
  4885.7  545.99  4902.4  545.08    4908  543.85  4922.6  542.37  4930.4  541.01
  4969.5  538.88  4991.9   536.9  4997.5  538.24  5003.1  538.28  5005.3   536.9
  5005.8   536.4  5010.5   536.4    5011   536.9  5015.8  539.36  5055.8  543.61
  5075.8  544.93  5115.8  546.18  5145.8   548.2  5178.4  549.65  5255.8  552.74
#Mann= 5 ,-1 , 0
  4670.4     .12       0  4922.6     .07       0  5005.3     .05       0
    5011     .07       0  5178.4     .12       0
Bank Sta=5005.3,5011
XS Rating Curve= 0 ,0
Exp/Cntr=0.3,0.1

Type RM Length L Ch R = 1 ,423554  ,455,455,455
BEGIN DESCRIPTION:
SANDIES CREEK 12.0
END DESCRIPTION:
XS GIS Cut Line= 3
        2323125.       13704825.        2322925.       13704475.
      2322725.01     13704325.01
#Sta/Elev= 30
  4596.9  548.78  4691.2  547.51  4712.8  547.97  4728.6  547.29  4773.9  547.69
  4793.4  547.83  4852.4  545.07  4868.3  545.14  4884.1  544.51  4896.4  543.36
  4927.3  541.65  4942.4  540.07  4954.7  538.09  4964.7  537.34  4986.3  534.76
  4992.1  533.32  4997.1  533.76  5003.1  533.76    5005  533.32  5005.5  532.82
  5010.3  532.82  5010.8  533.32  5013.6  536.32    5016  536.81  5028.1  539.12
  5071.9  542.79  5139.1  545.86  5186.5  547.67  5242.7  548.93    5250  548.66
#Mann= 6 ,-1 , 0
  4596.9     .12       0  4773.9     .07       0    5005     .05       0
  5010.8     .07       0    5016     .12       0  5139.1     .07       0
Bank Sta=5005,5010.8
XS Rating Curve= 0 ,0
Exp/Cntr=0.3,0.1

Type RM Length L Ch R = 1 ,423099  ,456,456,456
BEGIN DESCRIPTION:
SANDIES CREEK 13.0
END DESCRIPTION:
XS GIS Cut Line= 3
      2323880.22     13704753.91        2323075.       13704075.
      2322824.98       13704125.
#Sta/Elev= 30
  3946.9  572.04    4006  568.47  4184.1  560.59  4389.6  547.81  4496.2  544.74
  4657.2  543.65  4695.2  542.75    4794  543.17    4854  542.25  4935.8   538.2
  4950.1     537  4957.8   535.3  4964.4  535.53  4972.1  534.23  4978.7  534.71
  4986.4  532.51    4993  532.74  4994.4  530.87  4994.9  530.37  5000.2  530.87
    5044  535.34  5091.9  539.23  5122.5  544.86  5132.7     545  5163.3  539.03
  5173.5  538.39  5178.6  541.61  5204.1   545.8  5224.5  547.14  5255.1  547.23
#Mann= 6 ,-1 , 0
  3946.9     .12       0  4657.2     .07       0    4854     .12       0
  4994.4     .05       0  5000.2     .12       0    5044     .07       0
Bank Sta=4994.4,5000.2
XS Rating Curve= 0 ,0
Exp/Cntr=0.3,0.1

Type RM Length L Ch R = 1 ,422643  ,468,468,468
BEGIN DESCRIPTION:
SANDIES CREEK 14.0
END DESCRIPTION:
XS GIS Cut Line= 3
      2323924.99     13704474.99        2323125.       13703675.
      2322724.97     13703424.98
#Sta/Elev= 30
  3868.6  564.98  3995.9  557.89  4024.2  556.84  4151.4  548.86  4236.3   544.7
  4278.9  543.46  4321.1  541.91  4533.3  540.07  4547.4     540  4561.6  540.97
  4591.7  540.75  4660.6   540.9  4717.1   539.8  4886.8  535.36  4943.4  533.22
  4967.6  531.43  4991.2  528.62  4991.7  528.12  5002.4  528.12  5002.9  528.62
  5013.5  530.61  5035.5  531.86  5065.4  535.64  5086.6  536.83    5102  538.73
  5198.9  541.87    5306  545.18  5396.7  550.61  5442.8  554.57  5471.7  556.08
#Mann= 9 ,-1 , 0
  3868.6     .12       0  4278.9     .07       0  4591.7     .12       0
  4967.6     .07       0  4991.2     .05       0  5002.9     .07       0
  5035.5     .12       0  5198.9     .07       0  5396.7     .12       0
Bank Sta=4991.2,5002.9
XS Rating Curve= 0 ,0
Exp/Cntr=0.3,0.1

Type RM Length L Ch R = 1 ,422175  ,471,471,471
BEGIN DESCRIPTION:
SANDIES CREEK 15.0
END DESCRIPTION:
XS GIS Cut Line= 3
      2323874.96     13703824.96        2323475.       13703425.
      2323075.04     13703325.01
#Sta/Elev= 30
  4439.2   548.3  4500.3  544.46    4524  542.94  4545.2  542.39  4580.6  539.87
  4615.3  539.38  4665.4  537.25  4750.5  536.23  4792.7  535.69  4835.1  536.43
  4877.6  535.69    4920   533.7  4932.1   532.7  4948.3  531.03  4976.6  527.24
  4990.7  526.11  5001.3  527.43  5003.5  526.11    5004  525.61  5014.7  525.61
  5015.2  526.11  5022.9  528.17    5028  528.75  5053.6  530.33  5097.6  533.75
  5110.5  535.16  5159.5  537.78  5270.3  540.02  5334.7  540.14  5417.1  542.16
#Mann= 8 ,-1 , 0
  4439.2     .12       0  4500.3     .07       0  4615.3    .035       0
  4750.5     .12       0  4932.1     .07       0  5003.5     .05       0
  5015.2     .07       0  5053.6     .12       0
Bank Sta=5003.5,5015.2
XS Rating Curve= 0 ,0
Exp/Cntr=0.3,0.1

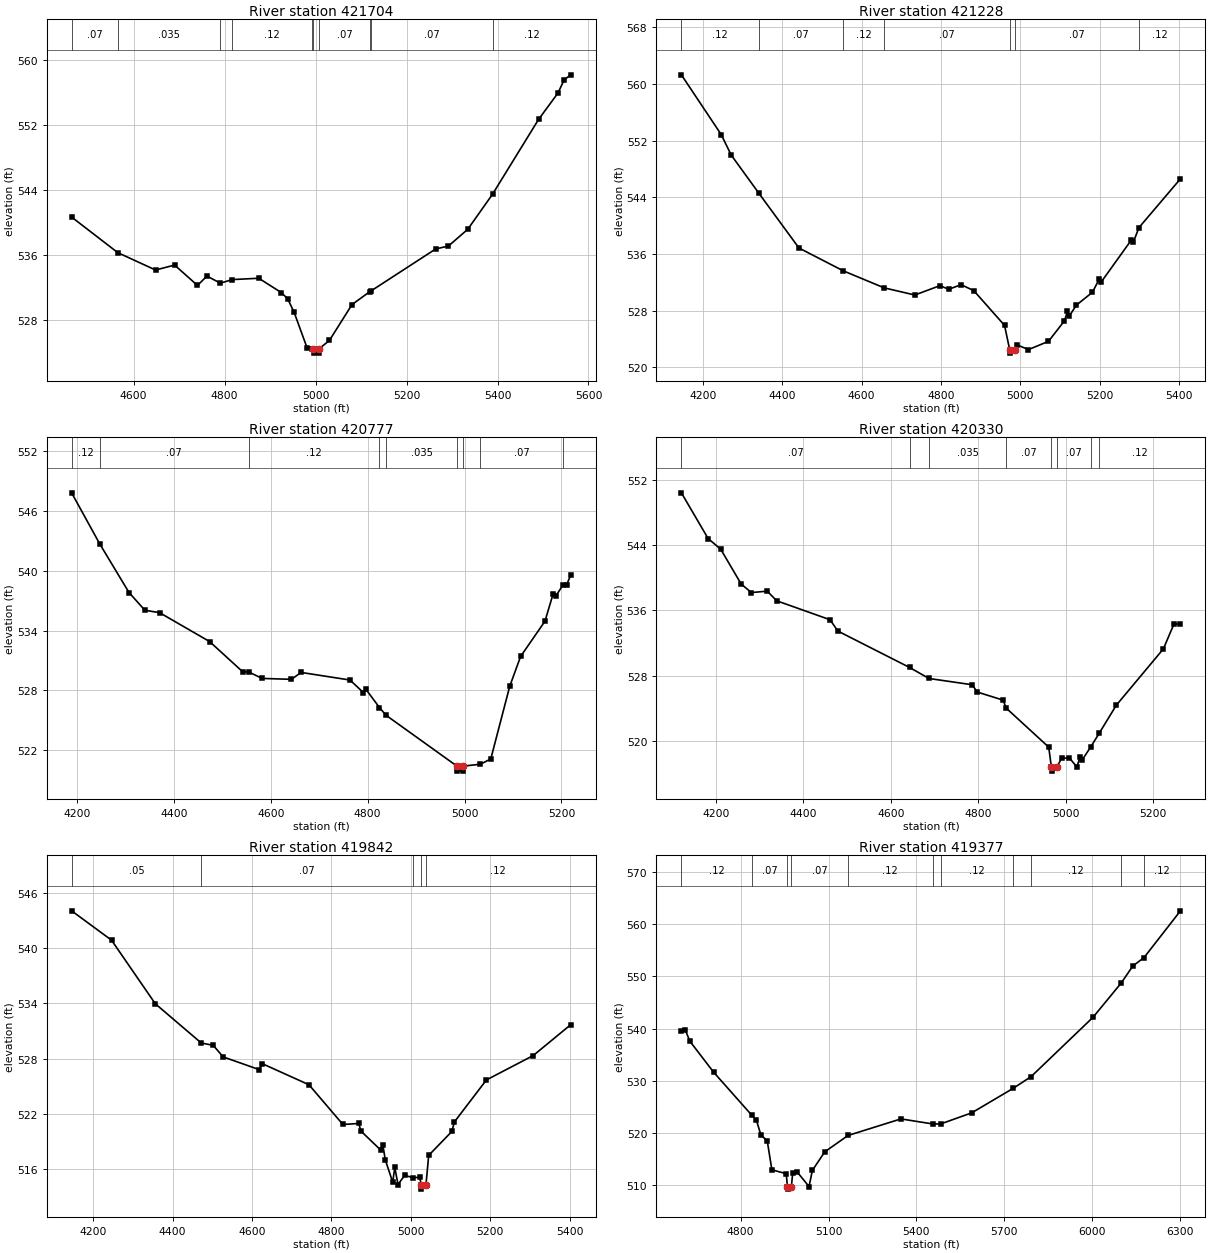
Type RM Length L Ch R = 1 ,421704  ,476,476,476
BEGIN DESCRIPTION:
SANDIES CREEK 16.0
END DESCRIPTION:
XS GIS Cut Line= 3
      2324174.99     13703524.99        2323825.       13703125.
      2323424.99     13702724.99
#Sta/Elev= 30
  4463.7  540.67  4565.3   536.3  4648.3  534.17  4690.1  534.78  4740.4  532.28
  4761.2  533.43  4790.6  532.56  4817.3     533  4875.1  533.16  4924.5  531.41
  4938.7  530.64    4953  528.96  4981.4  524.61  4992.4  524.47  4995.4  524.47
  4995.9  523.97  5006.7  523.97  5007.2  524.47  5030.6  525.54  5080.1  529.93
  5119.6  531.53  5122.1  531.61  5263.9  536.75  5292.2  537.12  5334.6  539.17
    5389  543.47  5490.2  552.65  5532.6  555.87  5546.7  557.52  5560.9  558.13
#Mann= 10 ,-1 , 0
  4463.7     .07       0  4565.3    .035       0  4790.6     .07       0
  4817.3     .12       0  4992.4     .07       0  4995.4     .05       0
  5007.2     .07       0  5119.6     .12       0  5122.1     .07       0
    5389     .12       0
Bank Sta=4995.4,5007.2
XS Rating Curve= 0 ,0
Exp/Cntr=0.3,0.1

Type RM Length L Ch R = 1 ,421228  ,451,451,451
BEGIN DESCRIPTION:
SANDIES CREEK 17.0
END DESCRIPTION:
XS GIS Cut Line= 3
      2324474.98     13703674.96        2324175.       13702875.
        2324225.     13702474.97
#Sta/Elev= 30
  4146.1  561.28  4246.6  552.84  4271.5  549.97  4340.7  544.62  4442.4  536.84
  4554.1  533.62    4657  531.22  4734.3  530.21  4797.5  531.53  4819.8  531.02
  4850.9  531.67    4883  530.82  4960.4  525.92  4973.2  522.51  4973.7  522.01
  4985.6  522.51  4990.7   523.2  5020.6  522.51    5071  523.67  5111.3  526.57
  5118.9  527.89  5123.9  527.28  5141.5  528.79  5181.9   530.6  5199.5  532.53
  5204.5  532.09  5280.1  537.99  5285.2  537.71    5299  539.72  5403.6  546.61
#Mann= 7 ,-1 , 0
  4146.1     .12       0  4340.7     .07       0  4554.1     .12       0
    4657     .07       0  4973.2     .05       0  4985.6     .07       0
    5299     .12       0
Bank Sta=4973.2,4985.6
XS Rating Curve= 0 ,0
Exp/Cntr=0.3,0.1

Type RM Length L Ch R = 1 ,420777  ,447,447,447
BEGIN DESCRIPTION:
SANDIES CREEK 18.0
END DESCRIPTION:
XS GIS Cut Line= 3
        2324475.     13703524.98        2324575.       13702725.
      2324475.01     13702525.01
#Sta/Elev= 30
  4189.2  547.82  4247.3  542.69  4307.6  537.82  4340.3  536.04  4370.6   535.8
  4473.9   532.9  4541.9  529.88  4554.6  529.85  4582.2   529.2  4642.7  529.11
  4662.8   529.8  4763.6  529.04  4791.3  527.78  4796.4  528.11  4824.4  526.28
  4837.8  525.51  4984.4   520.4  4984.9   519.9  4996.3   519.9  4996.8   520.4
  5032.5  520.59  5054.1  521.12  5093.2  528.41  5115.6   531.4  5165.9  534.94
  5182.7  537.68  5188.3  537.48  5203.7  538.61  5210.6  538.59    5219  539.57
#Mann= 9 ,-1 , 0
  4189.2     .12       0  4247.3     .07       0  4554.6     .12       0
  4824.4     .07       0  4837.8    .035       0  4984.4    .035       0
  4996.8    .035       0  5032.5     .07       0  5203.7     .12       0
Bank Sta=4984.4,4996.8
XS Rating Curve= 0 ,0
Exp/Cntr=0.3,0.1

Type RM Length L Ch R = 1 ,420330  ,488,488,488
BEGIN DESCRIPTION:
SANDIES CREEK 19.0
END DESCRIPTION:
XS GIS Cut Line= 3
        2324625.     13703575.01        2324975.       13702775.
      2324874.99     13702524.98
#Sta/Elev= 30
  4120.6  550.39  4181.8  544.79  4210.7  543.48  4257.4  539.22  4280.8  538.17
  4317.1  538.34  4338.9  537.16  4460.9  534.84  4478.9  533.45    4643  528.99
  4687.5  527.64  4786.8  526.87  4797.4  525.99    4857  524.99  4864.2  524.01
  4961.5  519.23  4967.6  516.79  4968.1  516.29  4980.1  516.79  4991.1  517.87
  5008.6  517.92  5026.1  516.79  5032.9  517.99  5038.3  517.68  5057.3  519.22
  5077.3  520.95  5116.3  524.37    5224  531.27  5248.3  534.33  5263.1   534.3
#Mann= 8 ,-1 , 0
  4120.6     .07       0    4643     .12       0  4687.5    .035       0
  4864.2     .07       0  4967.6     .05       0  4980.1     .07       0
  5057.3    .035       0  5077.3     .12       0
Bank Sta=4967.6,4980.1
XS Rating Curve= 0 ,0
Exp/Cntr=0.3,0.1

Type RM Length L Ch R = 1 ,419842  ,465,465,465
BEGIN DESCRIPTION:
SANDIES CREEK 20.0
END DESCRIPTION:
XS GIS Cut Line= 3
      2325125.01     13703574.97        2325425.       13702775.
      2325224.99     13702424.98
#Sta/Elev= 30
  4145.5  544.04    4246  540.86  4356.4  533.96  4472.1  529.71  4502.4  529.45
  4527.3   528.2  4618.1  526.82  4626.1  527.46  4743.5  525.18    4829  520.87
    4869  520.98  4874.4  520.16  4924.2   518.1  4929.6  518.67  4935.8  517.04
  4954.5  514.61  4959.8  516.21  4967.8  514.36  4984.7  515.35  5006.2   515.1
  5022.9  515.15  5025.9  514.36  5026.4  513.86  5038.4  514.36  5045.2  517.52
  5103.5  520.11    5110  521.15  5190.6   525.7  5308.7  528.35    5403  531.69
#Mann= 5 ,-1 , 0
  4145.5     .05       0  4472.1     .07       0  5006.2     .12       0
  5025.9     .05       0  5038.4     .12       0
Bank Sta=5025.9,5038.4
XS Rating Curve= 0 ,0
Exp/Cntr=0.3,0.1

Type RM Length L Ch R = 1 ,419377  ,439,439,439
BEGIN DESCRIPTION:
SANDIES CREEK 21.0
END DESCRIPTION:
XS GIS Cut Line= 3
      2325974.99     13703324.99        2325775.       13702975.
        2326275.       13701775.
#Sta/Elev= 30
  4597.9  539.58  4611.6  539.65  4627.4  537.54    4708  531.65  4838.3  523.42
  4853.4  522.56  4869.3  519.64  4890.9  518.52  4906.7  512.99  4955.6  512.24
  4959.9  509.79  4960.4  509.29  4973.2  509.79    4978  512.47  4993.1  512.56
  5033.5  509.79  5044.9  512.87  5087.1  516.42  5166.5  519.55  5347.1  522.72
  5455.2  521.76  5482.7  521.76  5588.7  523.88  5730.5  528.58  5791.5  530.82
  6002.5  542.15  6098.5  548.69  6138.5  551.97  6176.7  553.58    6301  562.52
#Mann= 11 ,-1 , 0
  4597.9     .12       0  4838.3     .07       0  4959.9     .05       0
  4973.2     .07       0  5166.5     .12       0  5455.2     .07       0
  5482.7     .12       0  5730.5     .07       0  5791.5     .12       0
  6098.5     .07       0  6176.7     .12       0
Bank Sta=4959.9,4973.2
XS Rating Curve= 0 ,0
Exp/Cntr=0.3,0.1