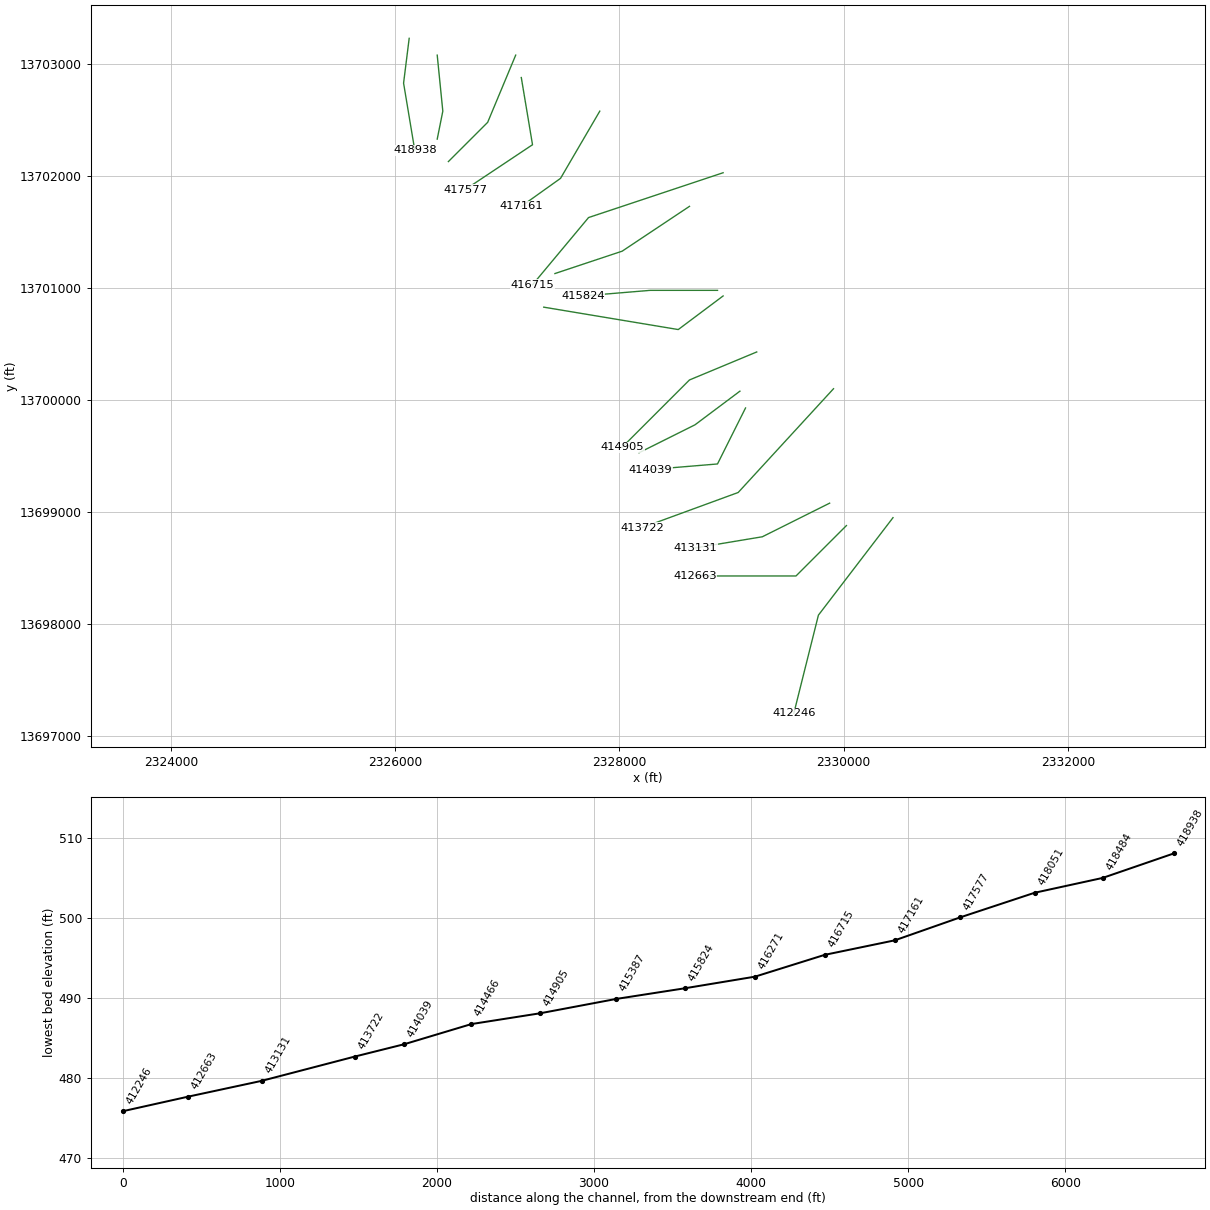
HEC-RAS study SANDIES CREEK.prj: SANDIES CREEK Base Level Engineering

--- SANDIES CREEK.g01 (geometry) --- (continued)

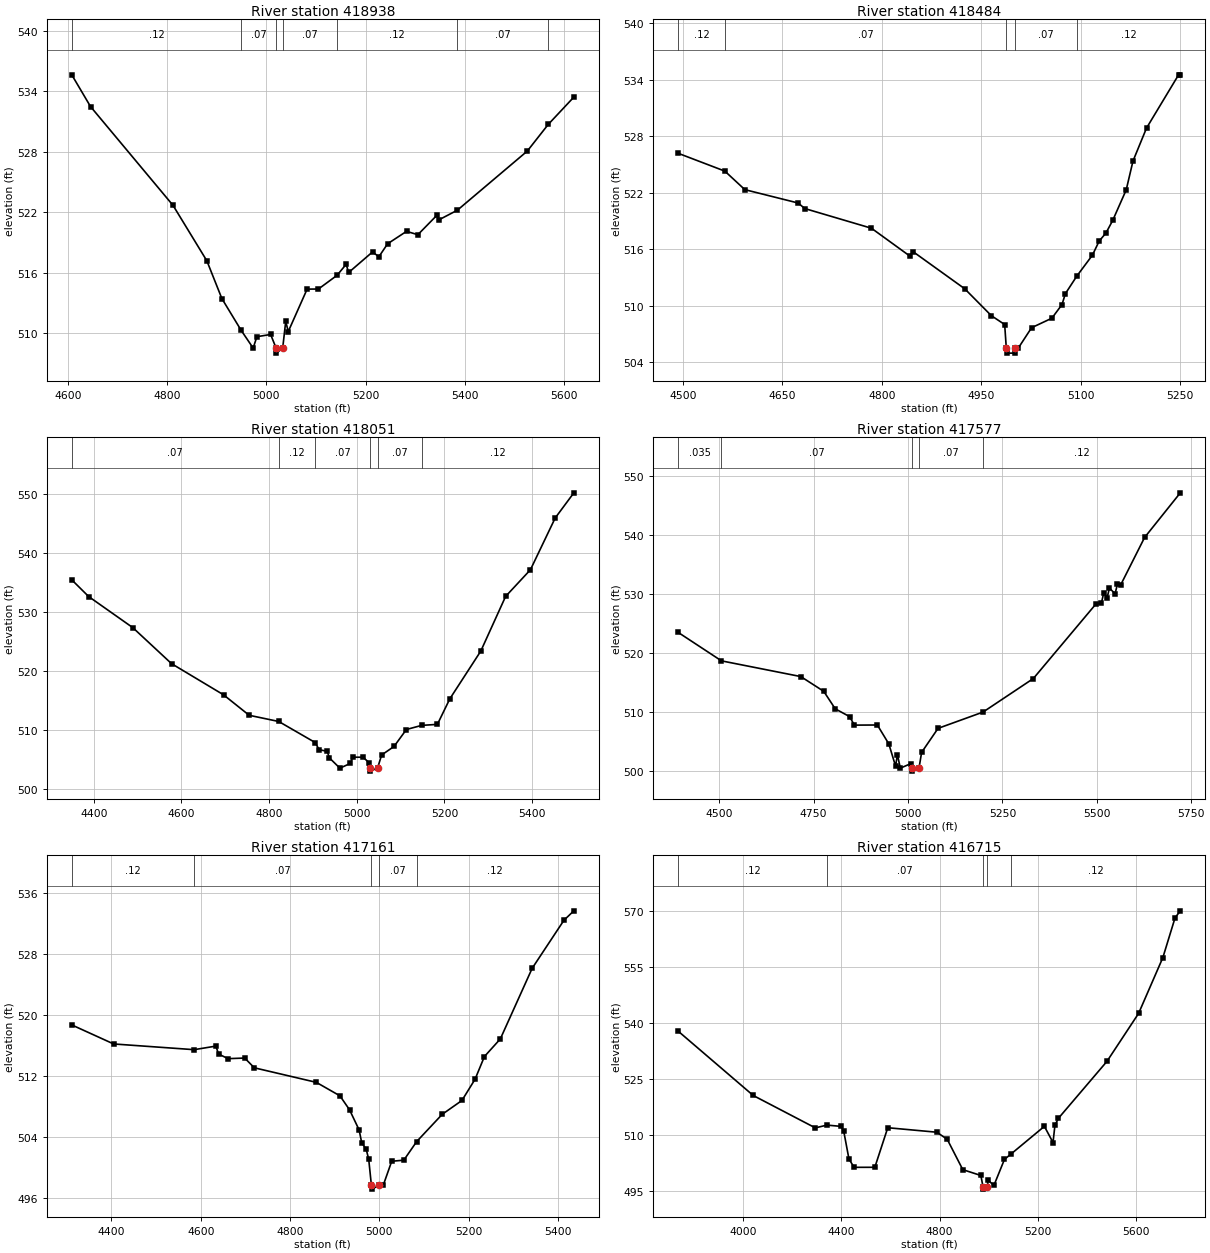
Type RM Length L Ch R = 1 ,418938  ,454,454,454
BEGIN DESCRIPTION:
SANDIES CREEK 22.0
END DESCRIPTION:
XS GIS Cut Line= 3
      2326125.01     13703225.05        2326075.       13702825.
      2326174.99     13702225.03
#Sta/Elev= 30
  4608.2  535.63    4646  532.48  4812.3  522.67  4880.3  517.18  4910.6  513.43
  4949.3  510.29  4973.6  508.52  4981.1  509.65  5008.8  509.87  5019.8  508.52
  5020.3  508.02  5033.1  508.52  5039.2  511.17  5044.3  510.16  5082.3  514.37
  5105.1  514.38  5142.6  515.74  5160.9  516.83    5166  516.02  5214.1  518.06
  5226.8  517.58  5244.5  518.87  5282.5   520.1  5305.4  519.77  5343.4  521.68
  5348.4  521.26    5385   522.2  5525.9  528.07    5568  530.71  5619.6  533.42
#Mann= 7 ,-1 , 0
  4608.2     .12       0  4949.3     .07       0  5019.8     .05       0
  5033.1     .07       0  5142.6     .12       0    5385     .07       0
    5568     .12       0
Bank Sta=5019.8,5033.1
XS Rating Curve= 0 ,0
Exp/Cntr=0.3,0.1

Type RM Length L Ch R = 1 ,418484  ,433,433,433
BEGIN DESCRIPTION:
SANDIES CREEK 23.0
END DESCRIPTION:
XS GIS Cut Line= 3
        2326375.     13703075.02        2326425.       13702575.
      2326374.99     13702324.97
#Sta/Elev= 30
  4492.8  526.19  4563.1   524.3  4593.3  522.33  4673.7  520.91  4683.8  520.32
  4784.3  518.23  4842.1  515.28  4847.1  515.74    4925   511.8  4965.2  508.94
  4985.3     508  4987.8  505.46  4988.3  504.96  5000.7  504.96  5001.2  505.46
  5005.5  505.46  5025.9  507.66  5056.5  508.67  5071.8  510.12  5076.9  511.28
  5094.4  513.17  5117.7  515.37  5127.9  516.87  5138.1  517.72  5148.3  519.06
  5168.7  522.31  5178.9  525.37  5199.3  528.87  5247.7  534.53  5250.3  534.53
#Mann= 5 ,-1 , 0
  4492.8     .12       0  4563.1     .07       0  4987.8     .05       0
  5001.2     .07       0  5094.4     .12       0
Bank Sta=4987.8,5001.2
XS Rating Curve= 0 ,0
Exp/Cntr=0.3,0.1

Type RM Length L Ch R = 1 ,418051  ,474,474,474
BEGIN DESCRIPTION:
SANDIES CREEK 24.0
END DESCRIPTION:
XS GIS Cut Line= 3
        2327075.       13703075.        2326825.       13702475.
      2326474.98     13702124.98
#Sta/Elev= 30
    4350  535.52  4388.5  532.69  4489.2  527.42  4577.5  521.32  4696.1  516.04
  4754.6  512.57    4822  511.52  4905.2  507.95  4913.9  506.75  4932.3  506.47
  4937.7  505.34  4961.5  503.61  4985.4  504.42  4990.8  505.47  5014.1  505.47
  5028.3  504.53  5029.6  503.61  5030.1  503.11  5047.3  503.61  5056.6  505.84
  5084.9  507.29  5113.1  510.16  5147.9  510.86  5183.8  511.03  5212.1  515.35
  5282.8  523.45  5339.4  532.71    5396  537.23  5452.5     546    5495  550.26
#Mann= 6 ,-1 , 0
    4350     .07       0    4822     .12       0  4905.2     .07       0
  5029.6     .05       0  5047.3     .07       0  5147.9     .12       0
Bank Sta=5029.6,5047.3
XS Rating Curve= 0 ,0
Exp/Cntr=0.3,0.1

Type RM Length L Ch R = 1 ,417577  ,416,416,416
BEGIN DESCRIPTION:
SANDIES CREEK 25.0
END DESCRIPTION:
XS GIS Cut Line= 3
      2327124.99     13702875.04        2327225.       13702275.
      2326625.02     13701875.01
#Sta/Elev= 30
  4391.7  523.52  4506.2  518.71  4716.2  516.05    4777  513.55  4807.4  510.59
  4845.4  509.27  4858.1  507.83  4918.9  507.85  4949.3  504.65  4967.1  500.89
  4972.1  502.83  4979.7  500.54  5007.5  501.31  5011.4  500.54  5011.9  500.04
  5029.2  500.54  5036.1  503.21  5079.6  507.28  5198.8  510.04    5332  515.72
  5497.3  528.31  5512.3  528.54  5518.3  530.21  5527.3  529.39  5533.3  531.03
  5548.4  530.07  5554.4  531.64  5563.4  531.59  5626.5   539.6  5721.1  547.16
#Mann= 5 ,-1 , 0
  4391.7    .035       0  4506.2     .07       0  5011.4     .05       0
  5029.2     .07       0  5198.8     .12       0
Bank Sta=5011.4,5029.2
XS Rating Curve= 0 ,0
Exp/Cntr=0.3,0.1

Type RM Length L Ch R = 1 ,417161  ,446,446,446
BEGIN DESCRIPTION:
SANDIES CREEK 26.0
END DESCRIPTION:
XS GIS Cut Line= 3
      2327824.99     13702574.98        2327475.       13701975.
      2327125.02     13701725.01
#Sta/Elev= 30
  4311.1  518.74  4404.9  516.24  4585.2  515.49    4634  515.96  4639.8  514.92
  4661.3  514.31  4698.5  514.39    4720  513.11  4858.9   511.2  4911.8  509.43
  4933.3   507.6  4954.8  504.95  4960.6  503.27  4970.6  502.42  4976.3   501.1
  4982.3  497.68  4982.8  497.18  5000.2  497.68  5008.8  497.68  5027.8  500.84
  5054.9  500.98  5083.8  503.43  5140.9     507  5185.1  508.82  5214.6  511.62
  5235.5  514.59  5271.1   516.9  5342.4  526.17  5413.7  532.49  5435.8  533.72
#Mann= 5 ,-1 , 0
  4311.1     .12       0  4585.2     .07       0  4982.3     .05       0
  5000.2     .07       0  5083.8     .12       0
Bank Sta=4982.3,5000.2
XS Rating Curve= 0 ,0
Exp/Cntr=0.3,0.1

Type RM Length L Ch R = 1 ,416715  ,444,444,444
BEGIN DESCRIPTION:
SANDIES CREEK 27.0
END DESCRIPTION:
XS GIS Cut Line= 3
      2328924.96     13702024.99        2327725.       13701625.
      2327224.99     13701024.99
#Sta/Elev= 30
  3735.1  537.75  4040.7   520.5  4293.7  511.81    4341  512.55  4399.1  512.21
  4409.7  510.84  4430.8  503.44  4451.8  501.22  4536.2  501.23  4588.9  511.85
  4789.1  510.64  4831.3  508.73  4894.6   500.6  4968.3  499.03  4977.4  495.87
  4977.9  495.37  4995.3  495.87  4997.3   497.8  5021.4  496.35  5064.4  503.35
  5090.7  504.77  5227.1  512.22  5262.3  507.88  5270.1  512.51  5284.4  514.39
  5482.2  529.67  5611.1  542.54    5710  557.53  5759.5  568.17    5781  570.06
#Mann= 5 ,-1 , 0
  3735.1     .12       0    4341     .07       0  4977.4     .05       0
  4995.3     .07       0  5090.7     .12       0
Bank Sta=4977.4,4995.3
XS Rating Curve= 0 ,0
Exp/Cntr=0.3,0.1

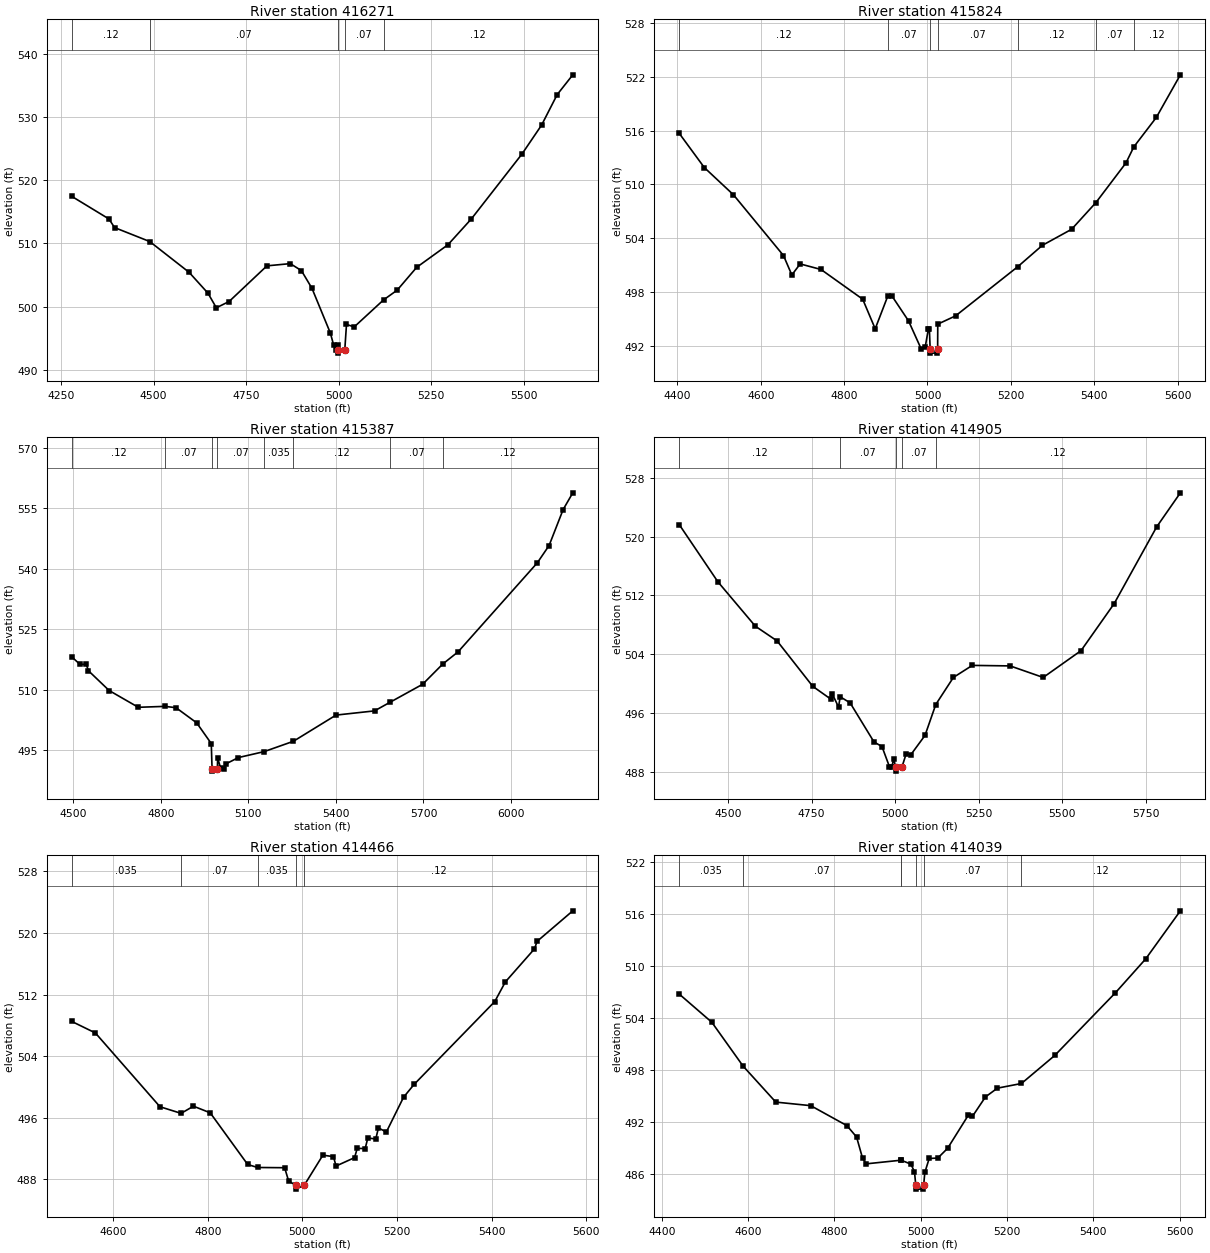
Type RM Length L Ch R = 1 ,416271  ,447,447,447
BEGIN DESCRIPTION:
SANDIES CREEK 28.0
END DESCRIPTION:
XS GIS Cut Line= 3
      2328624.98     13701724.99        2328025.       13701325.
      2327425.04     13701125.01
#Sta/Elev= 30
  4278.9  517.44  4379.5  513.86  4394.6   512.5  4489.7  510.29  4595.9  505.43
  4646.9  502.13  4669.5  499.82    4704  500.81  4806.2  506.45  4869.3   506.8
  4899.3   505.7  4927.9  502.89  4977.5  495.83  4986.5  493.91  4992.5  493.15
    4997  493.92  4998.6  493.15  4999.1  492.65  5016.5  493.15  5021.1  497.18
  5042.1   496.8  5121.1  501.06  5158.1  502.61  5210.8  506.22  5295.1  509.78
  5358.4  513.87  5495.4  524.15  5548.1   528.7  5590.3  533.53  5632.4  536.65
#Mann= 5 ,-1 , 0
  4278.9     .12       0  4489.7     .07       0  4998.6     .05       0
  5016.5     .07       0  5121.1     .12       0
Bank Sta=4998.6,5016.5
XS Rating Curve= 0 ,0
Exp/Cntr=0.3,0.1

Type RM Length L Ch R = 1 ,415824  ,437,437,437
BEGIN DESCRIPTION:
SANDIES CREEK 29.0
END DESCRIPTION:
XS GIS Cut Line= 3
      2328875.04       13700975.        2328275.       13700975.
      2327675.02       13700925.
#Sta/Elev= 30
  4404.6  515.68  4464.6  511.88  4534.6  508.84  4654.6  502.07  4674.6  499.91
  4694.6  501.14  4744.6  500.52  4844.6  497.21  4874.6  493.91  4905.3  497.62
  4914.6  497.58  4954.6  494.79  4984.6   491.7  4994.6  491.89  5002.1  493.87
  5004.6  493.87  5006.4   491.7  5006.9   491.2  5023.9   491.2  5024.4   491.7
  5024.7  494.43  5067.4  495.35  5216.6  500.83  5275.6  503.21  5345.8     505
  5404.2  507.98  5476.3   512.4    5495  514.18    5549  517.46  5606.7  522.21
#Mann= 7 ,-1 , 0
  4404.6     .12       0  4905.3     .07       0  5006.4     .05       0
  5024.4     .07       0  5216.6     .12       0  5404.2     .07       0
    5495     .12       0
Bank Sta=5006.4,5024.4
XS Rating Curve= 0 ,0
Exp/Cntr=0.3,0.1

Type RM Length L Ch R = 1 ,415387  ,482,482,482
BEGIN DESCRIPTION:
SANDIES CREEK 30.0
END DESCRIPTION:
XS GIS Cut Line= 3
        2328925.       13700925.        2328525.       13700625.
      2327324.95     13700825.01
#Sta/Elev= 30
  4494.9  518.18    4523  516.32  4544.9  516.29  4552.2  514.73    4623  509.84
    4723  505.68  4814.6  505.91  4852.2  505.58    4923  501.83    4973   496.7
  4975.7  490.37  4976.2  489.87  4993.9  490.37  4994.9  493.17    5005  490.58
  5015.2  490.37  5022.8  491.65  5065.9  493.23    5154   494.7  5254.3  497.26
  5400.4  503.75  5532.2  504.79    5585  506.91    5697  511.38  5766.1   516.4
  5818.6  519.42  6089.8  541.45  6130.3  545.75  6178.5  554.67  6211.5   558.8
#Mann= 8 ,-1 , 0
  4494.9     .12       0  4814.6     .07       0  4975.7     .05       0
  4993.9     .07       0    5154    .035       0  5254.3     .12       0
    5585     .07       0  5766.1     .12       0
Bank Sta=4975.7,4993.9
XS Rating Curve= 0 ,0
Exp/Cntr=0.3,0.1

Type RM Length L Ch R = 1 ,414905  ,439,439,439
BEGIN DESCRIPTION:
SANDIES CREEK 31.0
END DESCRIPTION:
XS GIS Cut Line= 3
      2329225.04     13700425.02        2328625.       13700175.
      2328024.98     13699574.98
#Sta/Elev= 30
  4354.1  521.61  4469.5  513.84  4581.6   507.8  4646.6   505.8  4753.3  499.62
  4806.4  497.91  4811.9  498.57  4830.3  496.81  4835.4   498.2  4864.9  497.38
  4936.4  492.06  4960.3  491.43  4982.5  488.71  4989.5  488.59  4994.9  489.73
  5001.4  488.59  5001.9  488.09  5019.6  488.59  5032.4  490.41  5046.6  490.32
    5089  492.95  5121.2  497.15  5173.8  500.83  5230.4  502.47  5343.6   502.4
  5442.5  500.83  5555.7  504.48  5654.7  510.87    5782  521.32  5852.7  525.94
#Mann= 5 ,-1 , 0
  4354.1     .12       0  4835.4     .07       0  5001.4     .05       0
  5019.6     .07       0  5121.2     .12       0
Bank Sta=5001.4,5019.6
XS Rating Curve= 0 ,0
Exp/Cntr=0.3,0.1

Type RM Length L Ch R = 1 ,414466  ,427,427,427
BEGIN DESCRIPTION:
SANDIES CREEK 32.0
END DESCRIPTION:
XS GIS Cut Line= 3
      2329075.01     13700075.01        2328675.       13699775.
      2328175.03     13699525.01
#Sta/Elev= 30
  4512.5  508.52  4562.5  507.02    4699  497.44  4743.6  496.58  4769.8  497.51
  4805.2  496.65  4884.4  489.94  4905.3  489.55  4962.5  489.52  4970.8  487.82
  4985.6  487.24  4986.1  486.74  5003.9  487.24  5043.3  491.15  5065.6  490.96
  5071.2  489.74  5110.3  490.83  5115.9  492.03  5132.7  492.01  5138.3  493.38
  5155.1  493.25  5160.7  494.69  5177.4  494.15  5213.8  498.67  5236.1  500.34
  5406.6   511.1    5429  513.65  5490.5  517.94  5496.1  518.92  5571.5  522.88
#Mann= 5 ,-1 , 0
  4512.5    .035       0  4743.6     .07       0  4905.3    .035       0
  4985.6     .05       0  5003.9     .12       0
Bank Sta=4985.6,5003.9
XS Rating Curve= 0 ,0
Exp/Cntr=0.3,0.1

Type RM Length L Ch R = 1 ,414039  ,317,317,317
BEGIN DESCRIPTION:
SANDIES CREEK 33.0
END DESCRIPTION:
XS GIS Cut Line= 3
      2329124.98     13699924.97        2328875.       13699425.
      2328274.96       13699375.
#Sta/Elev= 30
  4440.7  506.75  4516.1   503.5  4588.5  498.44  4664.3  494.28  4745.3  493.87
  4829.2  491.56  4851.5  490.25  4865.5  487.78  4873.9  487.15  4954.5  487.57
  4954.7  487.57  4977.3  487.12  4985.7  486.24  4988.6  484.73  4989.1  484.23
  5006.5  484.23    5007  484.73  5009.7  486.16  5019.8  487.77  5039.8  487.82
  5062.4  488.94  5110.1  492.74  5120.1  492.64  5150.2  494.88  5177.8  495.89
  5233.6  496.43  5310.8  499.67  5451.2   506.9  5521.5  510.82  5601.8  516.37
#Mann= 7 ,-1 , 0
  4440.7    .035       0  4588.5     .07       0  4954.5    .035       0
  4954.7     .07       0  4988.6     .05       0    5007     .07       0
  5233.6     .12       0
Bank Sta=4988.6,5007
XS Rating Curve= 0 ,0
Exp/Cntr=0.3,0.1

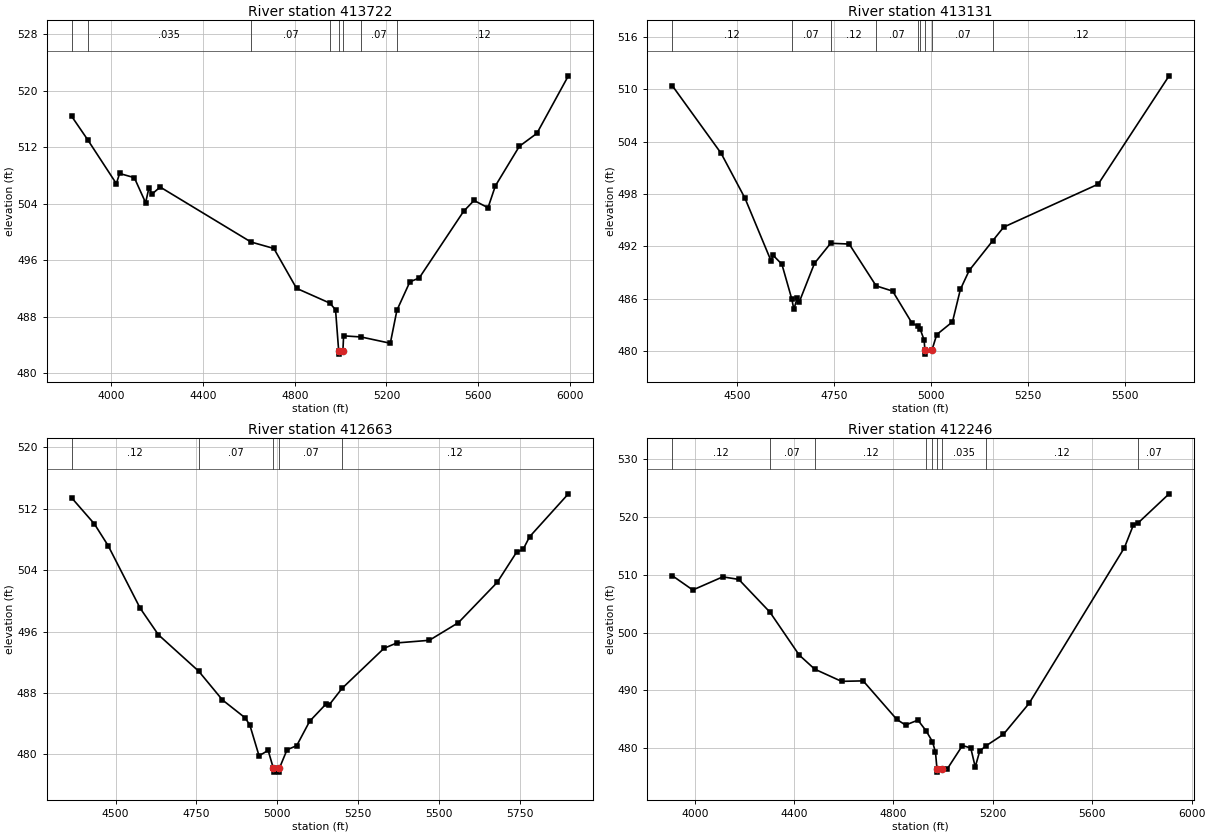
Type RM Length L Ch R = 1 ,413722  ,591,591,591
BEGIN DESCRIPTION:
SANDIES CREEK 34.0
END DESCRIPTION:
XS GIS Cut Line= 3
      2329909.75     13700096.69      2329059.59     13699170.34
       2328206.1     13698857.65
#Sta/Elev= 30
  3826.9  516.39    3897  513.06  4022.4  506.82  4036.6  508.26  4100.7  507.67
    4150  504.12  4164.2  506.19  4178.4  505.36  4213.5  506.34  4609.2  498.56
  4709.3  497.64  4807.9     492  4953.5   489.9  4978.1  488.96  4991.7  483.18
  4992.2  482.68  5010.2  483.18  5013.3  485.27  5089.4  485.11  5216.9  484.22
  5245.7  488.89  5302.1  492.91  5343.1  493.47  5536.4   502.9  5581.9  504.44
  5642.9  503.41  5674.9   506.5  5779.5  512.11  5855.9  513.94  5993.2  522.09
#Mann= 8 ,-1 , 0
  3826.9     .12       0    3897    .035       0  4609.2     .07       0
  4953.5    .035       0  4991.7    .035       0  5010.2    .035       0
  5089.4     .07       0  5245.7     .12       0
Bank Sta=4991.7,5010.2
XS Rating Curve= 0 ,0
Exp/Cntr=0.3,0.1

Type RM Length L Ch R = 1 ,413131  ,468,468,468
BEGIN DESCRIPTION:
SANDIES CREEK 35.0
END DESCRIPTION:
XS GIS Cut Line= 3
      2329875.02     13699075.01        2329275.       13698775.
      2328675.01       13698675.
#Sta/Elev= 30
  4333.5  510.42  4459.3  502.67  4520.8  497.52  4587.9  490.34  4593.5  490.97
  4615.8  489.96  4641.5  485.94  4646.6  484.79    4655  486.04  4660.5  485.63
  4699.7  490.06  4741.3  492.36  4789.1  492.27  4858.4  487.48  4900.9  486.88
  4951.2  483.18  4966.9  482.88  4971.4  482.57    4982  481.28  4983.9  480.16
  4984.4  479.66  5002.4  480.16  5014.5   481.9    5055  483.36  5075.3  487.07
  5098.1  489.25    5159  492.67  5186.8  494.21  5430.1  499.13  5612.6  511.54
#Mann= 9 ,-1 , 0
  4333.5     .12       0  4641.5     .07       0  4741.3     .12       0
  4858.4     .07       0  4966.9    .035       0  4971.4     .07       0
  4983.9     .05       0  5002.4     .07       0    5159     .12       0
Bank Sta=4983.9,5002.4
XS Rating Curve= 0 ,0
Exp/Cntr=0.3,0.1

Type RM Length L Ch R = 1 ,412663  ,417,417,417
BEGIN DESCRIPTION:
SANDIES CREEK 36.0
END DESCRIPTION:
XS GIS Cut Line= 3
      2330025.02     13698875.02        2329575.       13698425.
      2328675.02       13698425.
#Sta/Elev= 30
  4363.8  513.46  4434.5  510.04    4477  507.21    4576  499.06  4632.5  495.59
    4757  490.85  4830.5   487.1  4901.2  484.75  4915.4   483.8  4943.7  479.82
  4971.9  480.52    4988  478.19  4988.5  477.69  5006.1  477.69  5006.6  478.19
  5030.2   480.6  5060.2  481.14  5100.2  484.32  5150.2  486.54  5160.2  486.43
  5200.5  488.61  5330.2  493.83  5370.2  494.53  5470.2  494.87  5560.2  497.17
  5680.2  502.42  5740.2  506.36  5760.2  506.71  5780.2  508.36  5900.2  513.96
#Mann= 5 ,-1 , 0
  4363.8     .12       0    4757     .07       0    4988     .05       0
  5006.6     .07       0  5200.5     .12       0
Bank Sta=4988,5006.6
XS Rating Curve= 0 ,0
Exp/Cntr=0.3,0.1

Type RM Length L Ch R = 1 ,412246  ,475,475,475
BEGIN DESCRIPTION:
SANDIES CREEK 37.0
END DESCRIPTION:
XS GIS Cut Line= 3
      2330440.39     13698945.66        2329775.       13698075.
      2329555.73     13697198.21
#Sta/Elev= 30
  3909.5  509.83  3992.3  507.35  4112.9  509.62  4177.3  509.18  4302.5  503.53
  4420.4  496.11  4482.9  493.67  4590.8  491.56    4678  491.64  4813.1  484.99
  4848.4     484  4898.3  484.86  4931.2  483.01  4956.9  481.13    4969  479.31
  4975.1  476.37  4975.6  475.87  4993.7  476.37  5015.6  476.37  5077.5  480.47
    5111  480.04    5129  476.76    5147   479.5  5170.8  480.37  5242.4   482.4
  5345.5  487.74  5729.3  514.66  5765.4  518.58  5784.3  518.93  5909.1  523.97
#Mann= 9 ,-1 , 0
  3909.5     .12       0  4302.5     .07       0  4482.9     .12       0
  4931.2     .07       0  4956.9    .035       0  4975.1    .035       0
  4993.7    .035       0  5170.8     .12       0  5784.3     .07       0
Bank Sta=4975.1,4993.7
XS Rating Curve= 0 ,0
Exp/Cntr=0.3,0.1