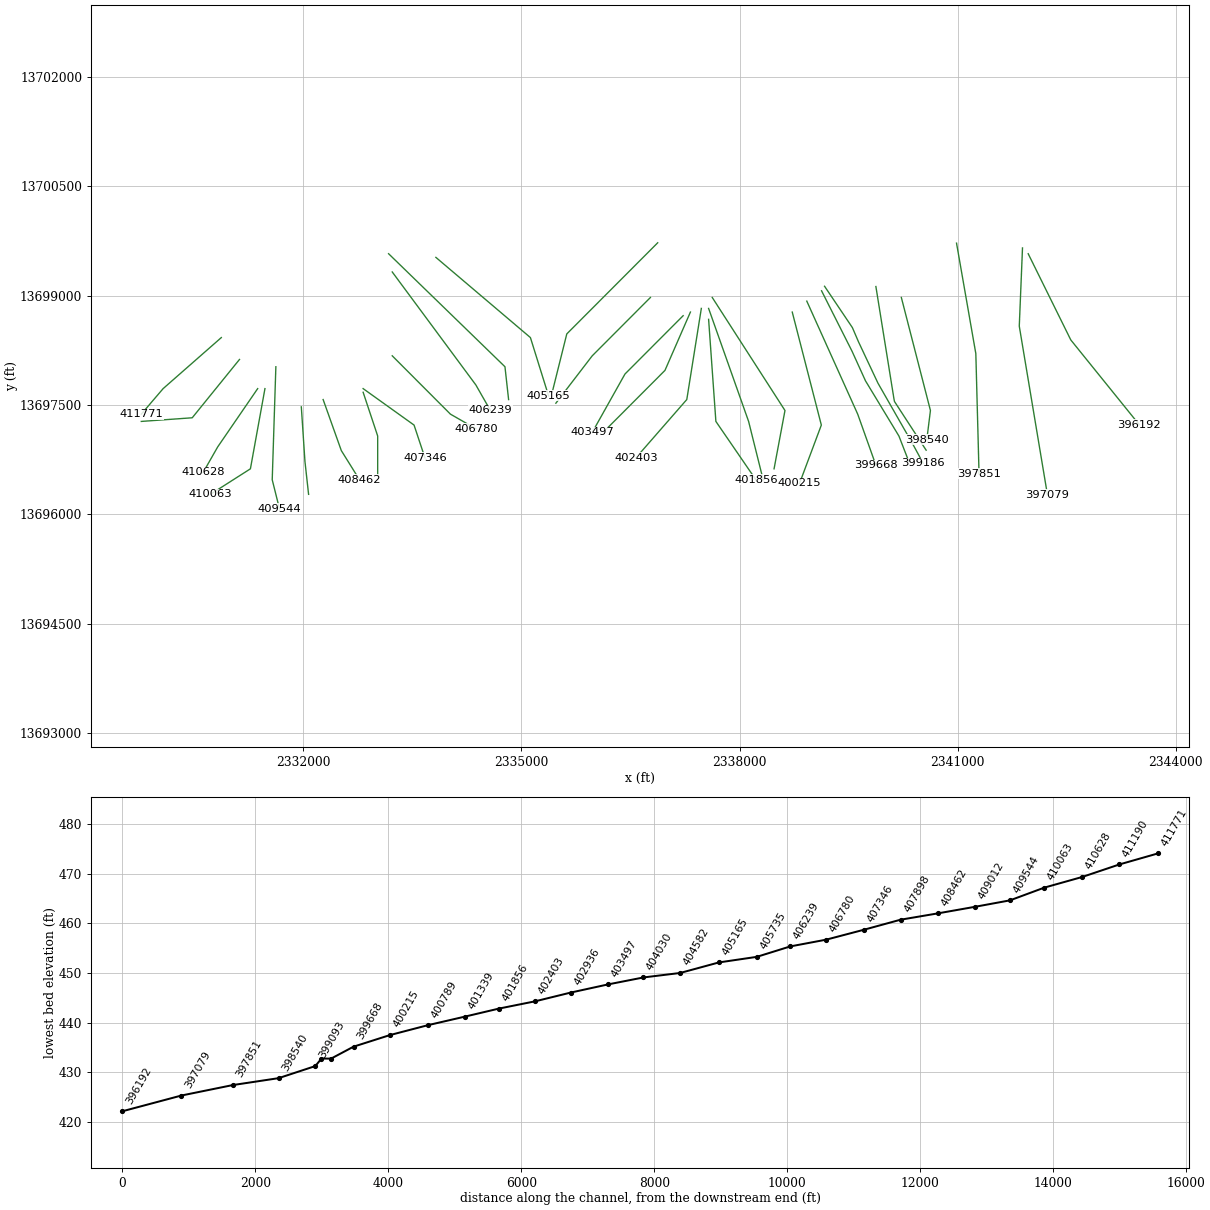
HEC-RAS study SANDIES CREEK.prj: SANDIES CREEK Base Level Engineering

--- SANDIES CREEK.g01 (geometry) --- (continued)

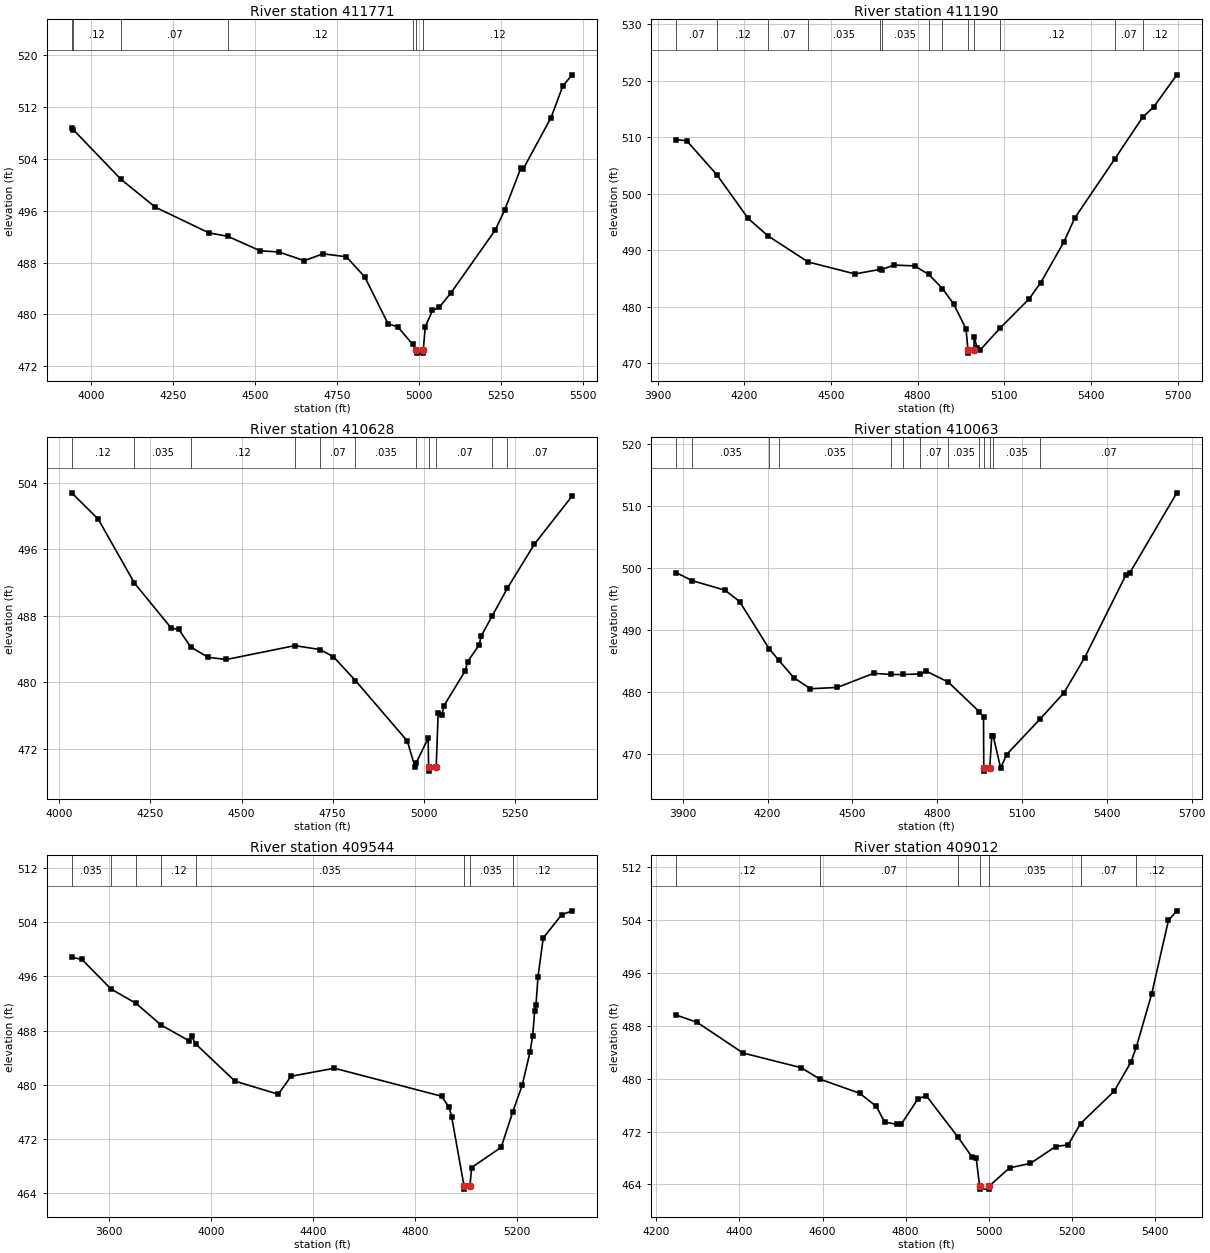
Type RM Length L Ch R = 1 ,411771  ,581,581,581
BEGIN DESCRIPTION:
SANDIES CREEK 38.0
END DESCRIPTION:
XS GIS Cut Line= 3
      2330874.98     13698424.98        2330075.       13697725.
      2329774.98     13697374.97
#Sta/Elev= 30
    3942  508.71  3947.4  508.43  4092.5  500.79  4196.8  496.52  4360.1  492.56
  4417.7  492.03  4515.7  489.81  4572.7  489.62  4650.5  488.28  4707.4  489.34
  4778.6  488.88  4834.6  485.77  4905.8  478.52  4934.3  478.12  4980.4   475.4
  4991.7  474.54  4992.2  474.04  5012.1  474.04  5012.6  474.54  5018.7  478.09
  5040.7  480.61  5061.5  481.12  5097.2  483.33  5231.6  492.98  5260.2  496.03
  5309.6  502.53  5317.2  502.43  5401.8  510.33    5438  515.23    5466  516.91
#Mann= 7 ,-1 , 0
    3942     .07       0  3947.4     .12       0  4092.5     .07       0
  4417.7     .12       0  4980.4    .035       0  4991.7    .035       0
  5012.6     .12       0
Bank Sta=4991.7,5012.6
XS Rating Curve= 0 ,0
Exp/Cntr=0.3,0.1

Type RM Length L Ch R = 1 ,411190  ,562,562,562
BEGIN DESCRIPTION:
SANDIES CREEK 39.0
END DESCRIPTION:
XS GIS Cut Line= 3
      2331125.02     13698125.02        2330475.       13697325.
      2329774.98       13697275.
#Sta/Elev= 30
  3964.6  509.63  4000.6  509.41  4105.3  503.36  4213.2  495.66  4281.6  492.58
  4420.6  487.96  4583.1  485.84  4670.5  486.65  4675.4  486.62  4718.1  487.41
  4789.2  487.26  4838.5  485.75  4885.7  483.26  4924.3  480.55  4967.4  476.12
  4974.1  472.32  4974.6  471.82    4995  472.32  4995.4  474.76  5005.4  472.78
  5015.5  472.32  5084.7  476.22  5185.9  481.42    5226   484.3  5306.2   491.5
  5343.8  495.74  5482.4   506.2  5578.8  513.57    5617  515.39  5697.2  521.09
#Mann= 13 ,-1 , 0
  3964.6     .07       0  4105.3     .12       0  4281.6     .07       0
  4420.6    .035       0  4670.5     .12       0  4675.4    .035       0
  4838.5     .12       0  4885.7    .035       0  4974.1    .035       0
    4995    .035       0  5084.7     .12       0  5482.4     .07       0
  5578.8     .12       0
Bank Sta=4974.1,4995
XS Rating Curve= 0 ,0
Exp/Cntr=0.3,0.1

Type RM Length L Ch R = 1 ,410628  ,565,565,565
BEGIN DESCRIPTION:
SANDIES CREEK 40.0
END DESCRIPTION:
XS GIS Cut Line= 3
      2331374.98     13697724.97        2330825.       13696925.
        2330625.       13696575.
#Sta/Elev= 30
  4033.7  502.82  4106.5  499.65  4205.8  491.96    4307  486.52  4327.9  486.36
  4360.4  484.25  4408.5     483  4458.4  482.74  4646.2  484.41  4715.1  483.94
  4752.1  483.08  4812.8  480.19  4955.1  472.92  4976.1  469.79  4979.4  470.29
  5012.4  473.25  5013.4  469.79  5013.9  469.29  5034.4  469.79  5039.8   476.3
  5049.8  476.06  5055.6  477.16  5114.6   481.4  5120.4  482.47  5152.1  484.47
  5157.8  485.57  5188.8  488.04  5229.4   491.3  5303.9  496.63  5407.6  502.44
#Mann= 11 ,-1 , 0
  4033.7     .12       0  4205.8    .035       0  4360.4     .12       0
  4646.2    .035       0  4715.1     .07       0  4812.8    .035       0
  4979.4     .07       0  5013.4     .05       0  5034.4     .07       0
  5188.8     .12       0  5229.4     .07       0
Bank Sta=5013.4,5034.4
XS Rating Curve= 0 ,0
Exp/Cntr=0.3,0.1

Type RM Length L Ch R = 1 ,410063  ,519,519,519
BEGIN DESCRIPTION:
SANDIES CREEK 41.0
END DESCRIPTION:
XS GIS Cut Line= 3
      2331475.01     13697725.04        2331275.       13696625.
        2330725.       13696275.
#Sta/Elev= 30
  3877.7  499.17  3933.8  497.89  4050.5  496.34  4101.3  494.52  4205.4  486.94
  4239.3  485.08  4293.2  482.24  4351.6  480.46  4446.9  480.67  4575.2  482.94
  4638.2  482.76  4679.3  482.76  4738.8  482.84    4762  483.28  4839.4  481.53
  4949.4  476.74    4964  475.92  4964.9  467.67  4965.4  467.17  4985.9  467.67
  4993.2  472.83  4998.2  472.83  5024.6  467.67  5045.7  469.85  5164.9  475.61
  5248.9  479.83  5321.7  485.47  5467.4   498.8  5481.8  499.18  5647.7  512.06
#Mann= 13 ,-1 , 0
  3877.7     .12       0  3933.8    .035       0  4205.4     .12       0
  4239.3    .035       0  4638.2     .07       0  4679.3    .035       0
  4738.8     .07       0  4839.4    .035       0  4949.4     .07       0
  4964.9    .035       0  4985.9     .07       0  4998.2    .035       0
  5164.9     .07       0
Bank Sta=4964.9,4985.9
XS Rating Curve= 0 ,0
Exp/Cntr=0.3,0.1

Type RM Length L Ch R = 1 ,409544  ,532,532,532
BEGIN DESCRIPTION:
SANDIES CREEK 42.0
END DESCRIPTION:
XS GIS Cut Line= 3
        2331625.       13698025.        2331575.       13696475.
      2331674.99     13696075.02
#Sta/Elev= 30
  3454.3  498.82  3494.3   498.5    3608  494.15  3706.7  492.01  3805.3  488.81
  3914.5   486.5  3924.6  487.14  3941.7  485.99  4094.6  480.54  4264.7   478.6
  4314.8  481.26  4484.8  482.44  4905.1  478.31  4935.1  476.66  4945.1  475.21
  4993.1   465.1  4993.6   464.6  5016.6   465.1  5023.1  467.79  5139.1  470.77
  5184.7  476.03  5221.6  479.95  5252.5  484.89  5262.8  487.27  5270.5  490.96
  5275.7  491.83  5283.4  495.91    5304  501.67  5376.2  505.09  5417.4  505.67
#Mann= 8 ,-1 , 0
  3454.3    .035       0    3608     .12       0  3706.7     .07       0
  3805.3     .12       0  3941.7    .035       0  4993.1    .035       0
  5016.6    .035       0  5184.7     .12       0
Bank Sta=4993.1,5016.6
XS Rating Curve= 0 ,0
Exp/Cntr=0.3,0.1

Type RM Length L Ch R = 1 ,409012  ,550,550,550
BEGIN DESCRIPTION:
SANDIES CREEK 43.0
END DESCRIPTION:
XS GIS Cut Line= 3
        2331975.     13697475.04        2332025.       13696725.
        2332075.     13696274.97
#Sta/Elev= 30
  4248.3  489.64  4298.4  488.54  4408.7   483.9    4549  481.67  4593.6  479.95
  4689.3  477.81  4729.4  475.83  4749.4  473.46  4779.5  473.08  4789.5  473.12
  4829.6  476.94  4849.7  477.44    4925  471.25  4959.9  468.16  4969.9  467.97
  4978.1  463.79  4978.6  463.29  5001.3  463.29  5001.8  463.79  5050.3  466.51
  5100.6  467.19    5161  469.74  5191.2  469.99  5221.1  473.22  5301.8   478.1
  5342.1  482.49  5355.5  484.83  5392.4  492.88  5432.6  503.98  5452.8  505.43
#Mann= 7 ,-1 , 0
  4248.3     .12       0  4593.6     .07       0    4925    .035       0
  4978.1    .035       0  5001.8    .035       0  5221.1     .07       0
  5355.5     .12       0
Bank Sta=4978.1,5001.8
XS Rating Curve= 0 ,0
Exp/Cntr=0.3,0.1

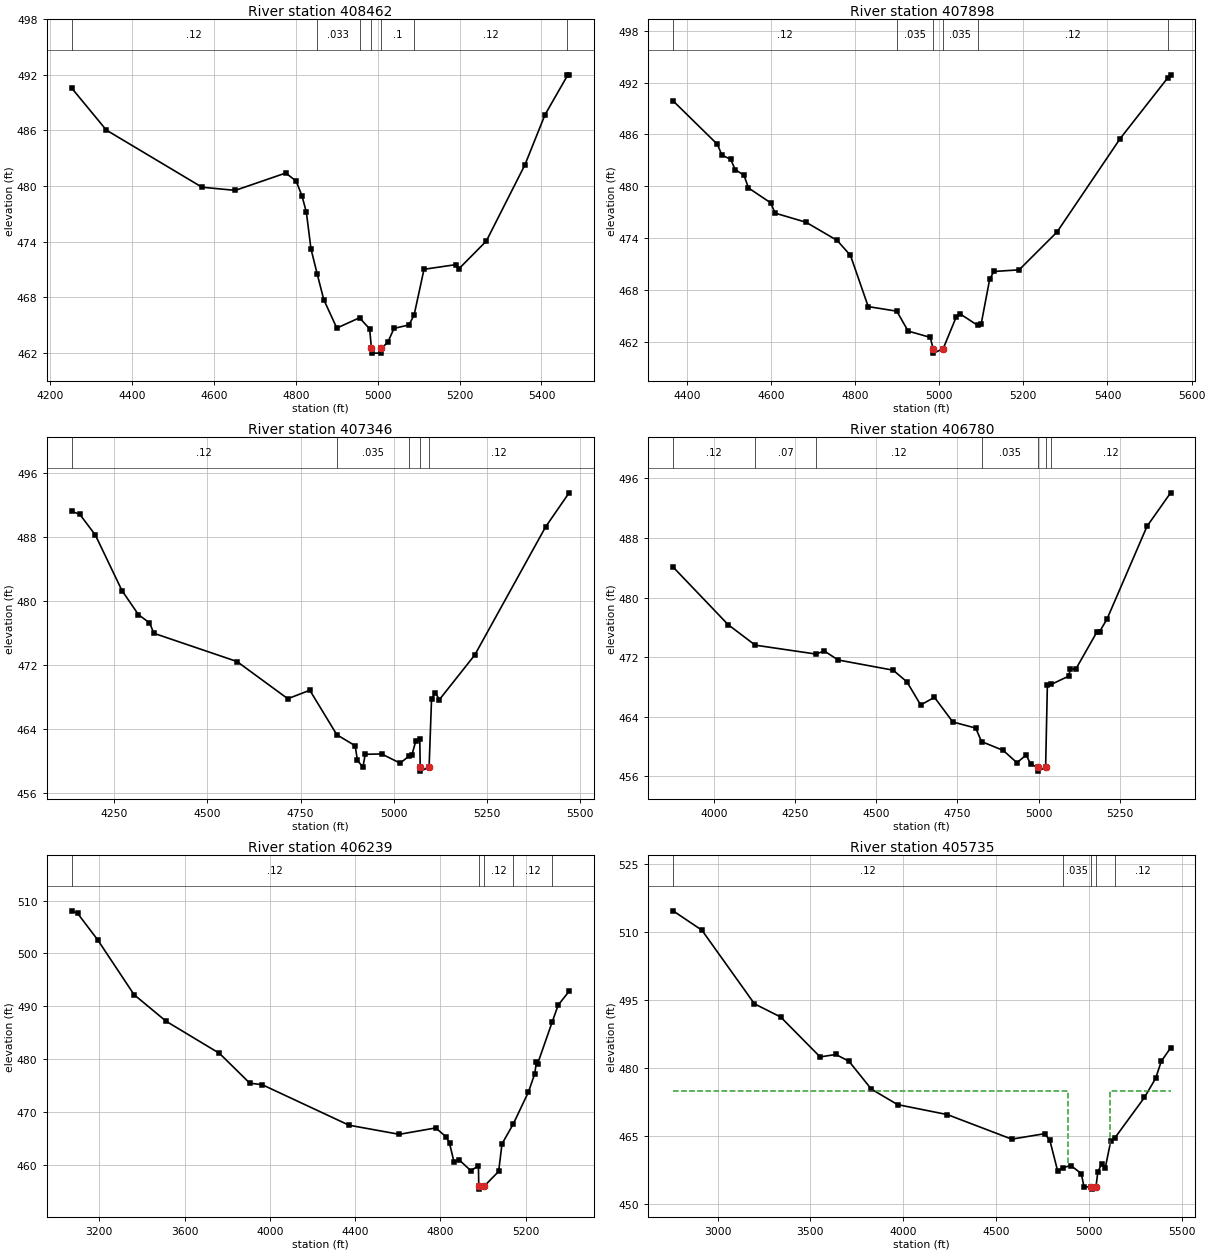
Type RM Length L Ch R = 1 ,408462  ,564,564,564
BEGIN DESCRIPTION:
SANDIES CREEK 44.0
END DESCRIPTION:
XS GIS Cut Line= 3
      2332274.99     13697575.02        2332525.       13696875.
      2332774.99     13696475.02
#Sta/Elev= 30
  4252.4  490.59  4337.4  486.04    4571  479.88  4652.2  479.54  4775.4  481.41
  4800.9  480.55  4815.2  478.93  4825.8  477.19    4837  473.25  4852.2  470.54
  4868.3  467.76  4900.2  464.69  4955.6   465.8  4980.3  464.61  4984.8  462.49
  4985.3  461.99    5008  461.99  5008.5  462.49  5024.6  463.15  5039.9  464.66
  5076.5  465.03  5089.1  466.13  5113.1  471.03  5192.1  471.54    5198  471.07
  5265.2  474.07  5359.5  482.29  5408.5  487.69  5463.5  491.93  5467.4     492
#Mann= 7 ,-1 , 0
  4252.4     .12       0  4852.2    .033       0  4955.6      .1       0
  4984.8     .05       0  5008.5      .1       0  5089.1     .12       0
  5463.5     .07       0
Bank Sta=4984.8,5008.5
XS Rating Curve= 0 ,0
Exp/Cntr=0.3,0.1

Type RM Length L Ch R = 1 ,407898  ,552,552,552
BEGIN DESCRIPTION:
SANDIES CREEK 45.0
END DESCRIPTION:
XS GIS Cut Line= 3
      2332825.01     13697674.98        2333025.       13697075.
        2333025.     13696525.03
#Sta/Elev= 30
  4367.6  489.88    4473  484.85  4483.5  483.62  4504.6  483.11  4515.1  481.94
  4536.2  481.27  4546.8  479.81  4599.5  478.09    4610   476.9  4683.8  475.84
  4757.6  473.74  4789.2  472.01  4831.4  466.09  4899.3  465.56  4926.2  463.26
  4978.9  462.53  4985.6  461.21  4986.1  460.71  5009.4  461.21    5040  464.83
    5050  465.24  5091.2  463.93    5100  464.13    5120  469.25    5130  470.15
    5190  470.34    5280  474.71    5430  485.51  5543.8  492.58    5550  492.89
#Mann= 6 ,-1 , 0
  4367.6     .12       0  4899.3    .035       0  4985.6    .035       0
  5009.4    .035       0  5091.2     .12       0  5543.8     .07       0
Bank Sta=4985.6,5009.4
XS Rating Curve= 0 ,0
Exp/Cntr=0.3,0.1

Type RM Length L Ch R = 1 ,407346  ,566,566,566
BEGIN DESCRIPTION:
SANDIES CREEK 46.0
END DESCRIPTION:
XS GIS Cut Line= 3
      2332824.97     13697725.02        2333525.       13697225.
        2333675.     13696775.01
#Sta/Elev= 30
  4135.6  491.25  4157.8  490.85  4199.5  488.26  4270.8  481.31  4315.1  478.29
  4344.5  477.27  4356.8  475.95  4579.3  472.42  4715.7  467.76  4774.7  468.82
  4847.2  463.25  4896.3  461.87  4902.5  460.03  4917.2  459.19  4923.4   460.8
  4967.6  460.84  5016.9  459.69  5041.9  460.61  5048.6  460.72  5059.1  462.48
  5069.7  462.73  5070.8  459.19  5071.3  458.69  5094.7  459.19  5101.3  467.78
  5111.8  468.47  5122.4  467.65  5217.2  473.24    5407  489.27  5470.2  493.55
#Mann= 5 ,-1 , 0
  4135.6     .12       0  4847.2    .035       0  5041.9     .12       0
  5070.8    .035       0  5094.7     .12       0
Bank Sta=5070.8,5094.7
XS Rating Curve= 0 ,0
Exp/Cntr=0.3,0.1

Type RM Length L Ch R = 1 ,406780  ,541,541,541
BEGIN DESCRIPTION:
SANDIES CREEK 47.0
END DESCRIPTION:
XS GIS Cut Line= 3
      2333225.01     13698174.99        2334025.       13697375.
      2334375.03     13697174.98
#Sta/Elev= 30
  3872.9   484.1  4042.6  476.37  4126.3  473.61    4313  472.42  4339.6  472.82
    4382  471.62  4551.7  470.25  4594.1  468.69  4636.6  465.58    4679  466.61
  4735.6   463.3  4806.3  462.48  4824.2  460.67  4891.1  459.48  4933.5  457.83
  4961.8  458.86    4976  457.64  4997.8   457.2  4998.3   456.7  5021.9   457.2
  5027.3  468.25  5038.7  468.33  5092.8  469.45  5098.6  470.44  5114.4  470.35
  5179.2  475.31  5188.5  475.44  5210.9  477.08  5334.7  489.57  5407.4  494.06
#Mann= 7 ,-1 , 0
  3872.9     .12       0  4126.3     .07       0    4313     .12       0
  4824.2    .035       0  4997.8    .035       0  5021.9    .035       0
  5038.7     .12       0
Bank Sta=4997.8,5021.9
XS Rating Curve= 0 ,0
Exp/Cntr=0.3,0.1

Type RM Length L Ch R = 1 ,406239  ,504,504,504
BEGIN DESCRIPTION:
SANDIES CREEK 48.0
END DESCRIPTION:
XS GIS Cut Line= 3
      2333224.98     13699325.02        2334375.       13697775.
      2334575.02     13697424.97
#Sta/Elev= 30
  3070.2  508.05  3098.4  507.58  3192.3  502.58  3363.4  492.17  3513.6  487.14
    3764  481.05  3905.9  475.41  3964.3  475.12  4371.2  467.45  4606.9  465.72
    4778  466.93  4828.1  465.19  4842.7  464.02  4863.6   460.5  4886.6  460.92
  4942.9  458.83  4978.3  459.77  4979.8  455.84  4980.3  455.34  5003.9  455.84
    5073  458.69  5088.8  463.91  5141.6  467.68  5212.6  473.72  5242.1  477.16
    5250  479.34  5255.8  479.09  5323.8  486.96  5352.3  490.21  5403.4   492.8
#Mann= 5 ,-1 , 0
  3070.2     .12       0  4979.8    .035       0  5003.9     .12       0
  5141.6     .12       0  5323.8     .07       0
Bank Sta=4979.8,5003.9
XS Rating Curve= 0 ,0
Exp/Cntr=0.3,0.1

Type RM Length L Ch R = 1 ,405735  ,570,570,570
BEGIN DESCRIPTION:
SANDIES CREEK 49.0
END DESCRIPTION:
XS GIS Cut Line= 3
      2333174.97     13699575.03        2334775.       13698025.
        2334825.     13697574.98
#Sta/Elev= 30
    2760  514.71  2915.6  510.42  3198.5  494.17    3340  491.25  3552.2  482.44
  3637.1  482.98  3707.6  481.49    3828  475.34  3969.4  471.91    4238   469.7
  4584.5  464.28  4761.5  465.48  4789.8  464.04  4832.2  457.21  4858.3  457.95
  4902.9  458.45  4959.5  456.67  4973.7  453.74  5014.2  453.74  5014.7  453.24
  5038.4  453.74  5048.1  456.96  5068.2   458.8  5088.3  457.89  5118.5  463.97
  5138.4  464.45  5299.6  473.49    5360  477.73  5390.2  481.48  5440.5  484.44
#Mann= 5 ,-1 , 0
    2760     .12       0  4858.3    .035       0  5014.2    .035       0
  5038.4    .035       0  5138.4     .12       0
#XS Ineff= 2 , 0
       0  4887.8  475.01  5112.2       0  475.01
Permanent Ineff=
       F       F
Bank Sta=5014.2,5038.4
XS Rating Curve= 0 ,0
Exp/Cntr=0.3,0.1

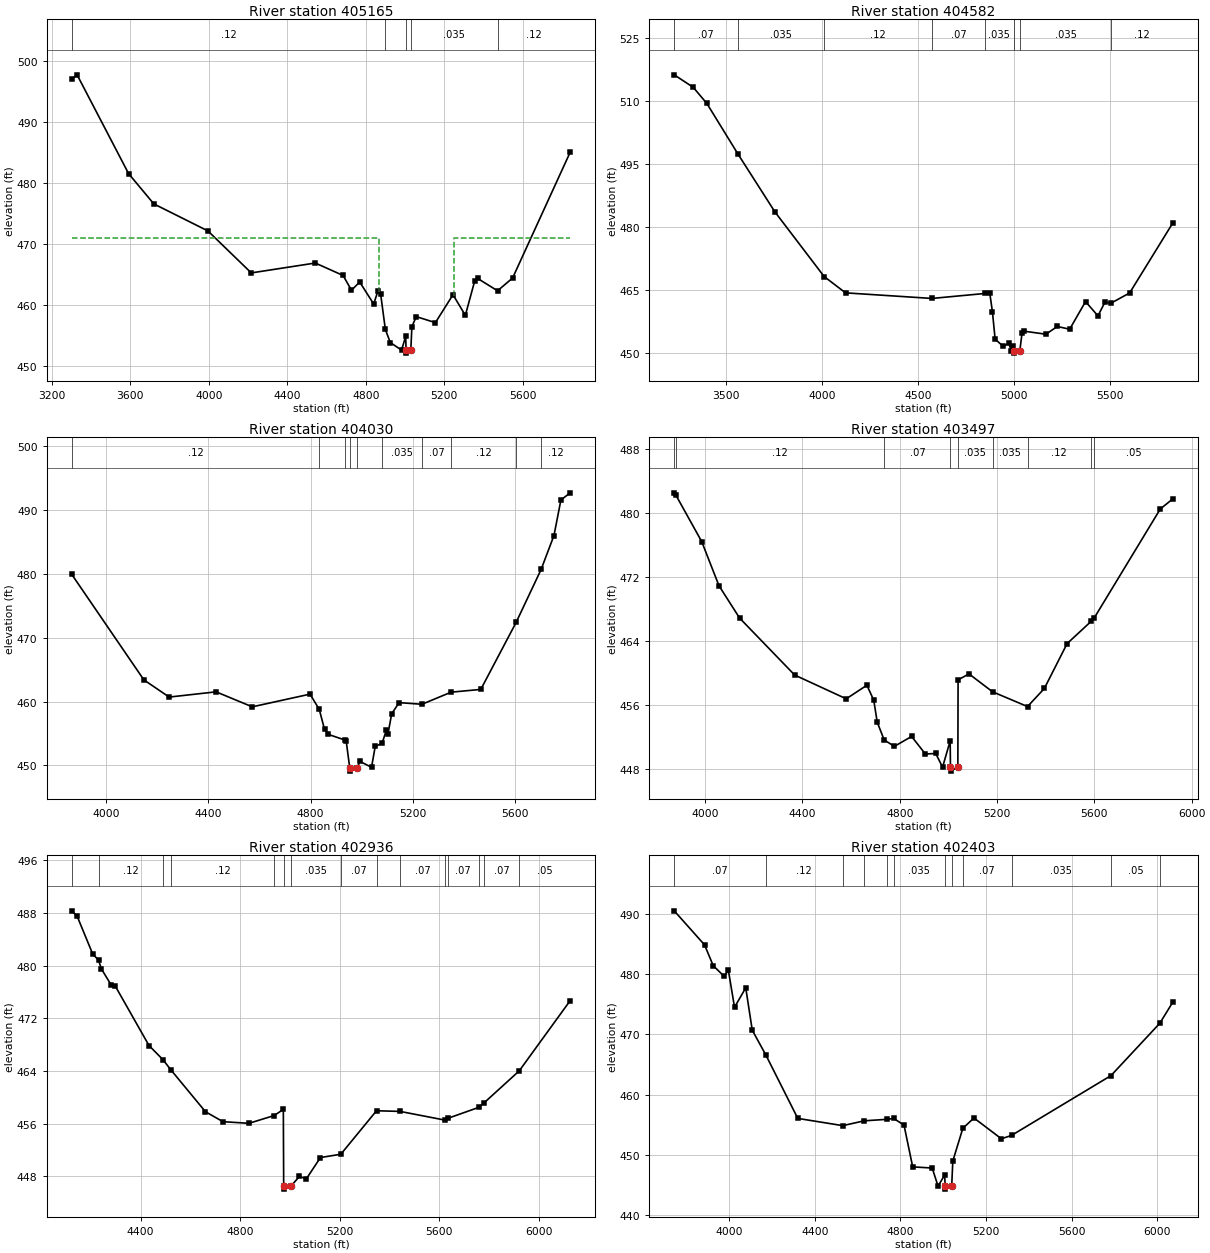
Type RM Length L Ch R = 1 ,405165  ,583,583,583
BEGIN DESCRIPTION:
SANDIES CREEK 50.0
END DESCRIPTION:
XS GIS Cut Line= 3
      2333825.01     13699524.99        2335125.       13698425.
      2335375.01     13697624.98
#Sta/Elev= 30
  3300.9  497.01  3328.9  497.74  3591.5  481.54  3720.1  476.58  3995.8  472.15
  4216.7  465.27    4543  466.89  4684.7  464.85  4727.5  462.42  4769.2  463.79
  4840.7  460.16  4861.5  462.24  4875.8  461.86    4900  456.01  4925.2  453.86
  4982.4  452.62  5003.8  454.85  5005.5  452.62    5006  452.12  5029.8  452.62
  5035.3  456.46  5057.8   458.1  5155.2  457.12  5244.8   461.7  5307.7  458.31
  5355.3  463.93  5370.5  464.36  5471.9  462.34  5548.6  464.43    5842  485.05
#Mann= 5 ,-1 , 0
  3300.9     .12       0    4900    .035       0  5005.5    .035       0
  5029.8    .035       0  5471.9     .12       0
#XS Ineff= 2 , 0
       0  4866.6     471  5248.6       0     471
Permanent Ineff=
       F       F
Bank Sta=5005.5,5029.8
XS Rating Curve= 0 ,0
Exp/Cntr=0.3,0.1

Type RM Length L Ch R = 1 ,404582  ,552,552,552
BEGIN DESCRIPTION:
SANDIES CREEK 51.0
END DESCRIPTION:
XS GIS Cut Line= 3
      2336874.98     13699724.98        2335625.       13698475.
      2335424.99     13697674.96
#Sta/Elev= 30
  3232.3  516.21  3331.3  513.24    3402   509.4  3564.7   497.3  3755.5  483.63
  4011.9  468.22  4123.2  464.34  4572.1  463.01  4847.6  464.19  4872.8  464.39
  4886.9  459.85    4901  453.32  4943.5  451.59  4971.7  452.33  4985.9   450.5
  4996.5  451.78  4999.1   450.5  4999.6     450  5029.2   450.5  5041.3   454.9
  5051.6  455.22    5165   454.5  5224.2  456.34  5288.6  455.69  5371.1  462.26
  5435.5  458.87  5471.6  462.08  5504.9  461.92  5600.5  464.32  5824.7  480.96
#Mann= 8 ,-1 , 0
  3232.3     .07       0  3564.7    .035       0  4011.9     .12       0
  4572.1     .07       0  4847.6    .035       0  4999.1    .035       0
  5029.2    .035       0  5504.9     .12       0
Bank Sta=4999.1,5029.2
XS Rating Curve= 0 ,0
Exp/Cntr=0.3,0.1

Type RM Length L Ch R = 1 ,404030  ,533,533,533
BEGIN DESCRIPTION:
SANDIES CREEK 52.0
END DESCRIPTION:
XS GIS Cut Line= 3
      2336774.97     13698974.97        2335975.       13698175.
        2335475.     13697524.99
#Sta/Elev= 30
  3864.3  479.98  4147.1  463.41  4246.1  460.71  4429.9  461.53  4571.4  459.18
  4797.6  461.17  4833.7  458.77  4854.2  455.66  4868.4  454.87  4933.6  453.98
  4939.1   453.8    4953   449.6  4953.5   449.1  4983.1   449.6  4992.1  450.64
  5038.2   449.7  5052.7  452.98  5079.8  453.46  5096.2  455.54  5102.6  454.93
  5117.1  458.08  5146.1  459.84  5235.4  459.58  5349.9  461.48  5465.9  461.91
  5604.1  472.41  5701.9  480.71  5752.3  486.04  5779.4   491.6  5815.7  492.73
#Mann= 10 ,-1 , 0
  3864.3     .12       0  4833.7     .07       0  4933.6    .035       0
    4953     .05       0  4983.1    .035       0  5079.8    .035       0
  5235.4     .07       0  5349.9     .12       0  5604.1     .07       0
  5701.9     .12       0
Bank Sta=4953,4983.1
XS Rating Curve= 0 ,0
Exp/Cntr=0.3,0.1

Type RM Length L Ch R = 1 ,403497  ,561,561,561
BEGIN DESCRIPTION:
SANDIES CREEK 53.0
END DESCRIPTION:
XS GIS Cut Line= 3
      2337225.02     13698725.02        2336425.       13697925.
      2335974.99     13697124.99
#Sta/Elev= 30
  3873.1  482.53  3879.7  482.26  3986.3  476.42    4057  470.91  4141.8  466.86
  4368.1  459.73  4580.2  456.75  4665.1  458.45  4693.4  456.57  4707.5  453.83
  4736.2   451.6  4778.2   450.8  4848.9  452.04  4905.5  449.84  4947.9  449.91
  4976.2   448.2  5007.4  451.49  5008.6   448.2  5009.1   447.7    5039   448.2
  5039.9  459.12  5084.8  459.87  5181.5  457.63  5325.4  455.78  5394.6  458.05
    5488  463.66  5586.3  466.43  5598.7  466.83  5871.1  480.51  5922.4  481.77
#Mann= 9 ,-1 , 0
  3873.1     .07       0  3879.7     .12       0  4736.2     .07       0
  5008.6     .05       0    5039    .035       0  5181.5    .035       0
  5325.4     .12       0  5586.3     .07       0  5598.7     .05       0
Bank Sta=5008.6,5039
XS Rating Curve= 0 ,0
Exp/Cntr=0.3,0.1

Type RM Length L Ch R = 1 ,402936  ,533,533,533
BEGIN DESCRIPTION:
SANDIES CREEK 54.0
END DESCRIPTION:
XS GIS Cut Line= 3
      2337324.98     13698774.96        2336975.       13697975.
      2336175.03     13697175.03
#Sta/Elev= 30
  4122.4  488.35  4144.2  487.58  4206.9  481.82  4230.6  480.85  4242.4  479.51
  4282.6  477.02    4297  476.98  4433.8  467.87  4489.8  465.73  4520.8  464.22
  4660.7  457.82  4730.9  456.31  4835.4  456.06  4936.6  457.24  4973.7  458.17
  4975.1  446.56  4975.6  446.06  5005.5  446.56    5038  447.98  5066.3  447.62
  5122.8  450.86  5204.8  451.36  5348.3  457.97  5442.9  457.87  5623.2  456.55
  5635.2  456.82  5758.5  458.47  5778.7   459.1  5922.1  464.03  6126.9   474.7
#Mann= 15 ,-1 , 0
  4122.4     .07       0  4230.6     .12       0  4489.8     .07       0
  4520.8     .12       0  4936.6    .035       0  4975.1    .035       0
  5005.5    .035       0  5204.8     .07       0  5348.3    .035       0
  5442.9     .07       0  5623.2    .035       0  5635.2     .07       0
  5758.5     .12       0  5778.7     .07       0  5922.1     .05       0
Bank Sta=4975.1,5005.5
XS Rating Curve= 0 ,0
Exp/Cntr=0.3,0.1

Type RM Length L Ch R = 1 ,402403  ,547,547,547
BEGIN DESCRIPTION:
SANDIES CREEK 55.0
END DESCRIPTION:
XS GIS Cut Line= 3
      2337475.01     13698825.05        2337275.       13697575.
      2336574.97     13696774.97
#Sta/Elev= 30
  3743.3  490.47  3885.1  484.82  3925.6  481.37  3976.3  479.62  3996.5  480.59
    4025  474.47  4077.5   477.7  4107.9  470.67  4171.2  466.57  4320.6  456.04
  4530.7  454.84  4631.1  455.64    4738  455.89  4768.6  456.03  4816.8  454.93
  4857.3     448  4948.5  447.81  4975.7  444.81  5006.7  446.64  5009.1  444.81
  5009.6  444.31  5039.5  444.81  5044.8  448.97  5091.6   454.4  5143.5  456.11
  5271.7  452.66  5319.1  453.22  5783.6  463.14  6011.9  471.83  6072.3  475.32
#Mann= 12 ,-1 , 0
  3743.3     .07       0  4171.2     .12       0  4530.7     .07       0
  4631.1     .12       0    4738     .07       0  4768.6    .035       0
  5009.1    .035       0  5039.5    .035       0  5091.6     .07       0
  5319.1    .035       0  5783.6     .05       0  6011.9    .035       0
Bank Sta=5009.1,5039.5
XS Rating Curve= 0 ,0
Exp/Cntr=0.3,0.1

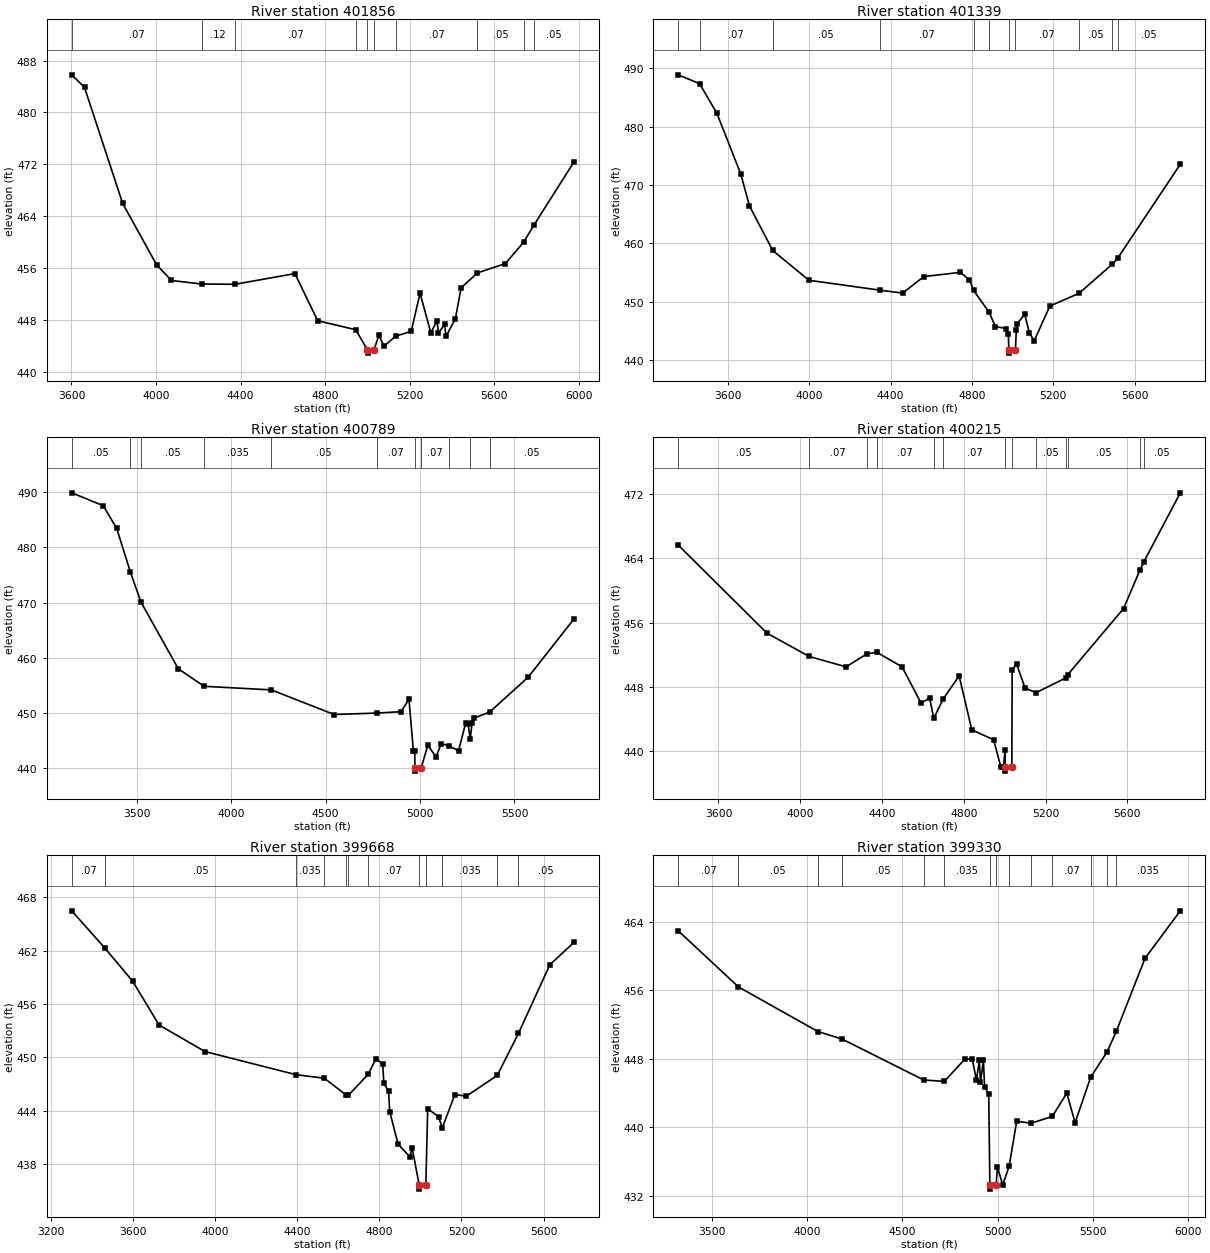
Type RM Length L Ch R = 1 ,401856  ,517,517,517
BEGIN DESCRIPTION:
SANDIES CREEK 56.0
END DESCRIPTION:
XS GIS Cut Line= 3
        2337575.     13698675.05        2337675.       13697275.
      2338224.98     13696475.03
#Sta/Elev= 30
  3601.5  485.81  3661.7  483.87  3842.2  465.95  4002.6  456.49  4072.7  454.06
  4215.5  453.51  4373.2  453.47  4656.7  455.12  4764.5  447.84  4944.7  446.45
  4999.7  443.34  5000.2  442.84  5030.2  443.34  5054.5   445.6  5077.9   443.9
    5133  445.46  5206.7   446.2  5248.6  452.09  5299.4     446  5329.2  447.82
  5335.3  445.93    5365  447.28  5371.1  445.41  5415.8  448.16  5442.8  452.92
  5520.1  455.23  5651.9  456.66  5738.2  459.96  5786.7  462.57  5975.9  472.34
#Mann= 10 ,-1 , 0
  3601.5     .07       0  4215.5     .12       0  4373.2     .07       0
  4944.7    .035       0  4999.7    .035       0  5030.2    .035       0
    5133     .07       0  5520.1     .05       0  5738.2     .07       0
  5786.7     .05       0
Bank Sta=4999.7,5030.2
XS Rating Curve= 0 ,0
Exp/Cntr=0.3,0.1

Type RM Length L Ch R = 1 ,401339  ,550,550,550
BEGIN DESCRIPTION:
SANDIES CREEK 57.0
END DESCRIPTION:
XS GIS Cut Line= 3
      2337575.01     13698824.98        2338125.       13697275.
        2338325.     13696474.99
#Sta/Elev= 30
  3355.3  488.88  3460.2  487.36  3545.3   482.3    3663  471.88  3705.4  466.45
  3819.8   458.8  3997.7  453.69  4346.1     452  4458.8  451.49    4563  454.32
  4742.9  455.05  4787.7  453.74    4808  451.95  4884.2  448.21  4915.1  445.76
  4968.1  445.42  4978.7  444.44  4981.4  441.71  4981.9  441.21  5013.5  441.71
    5018  445.11  5023.2  446.28  5059.2  447.87  5082.4  444.68  5105.6   443.3
  5182.9  449.27  5326.9  451.46    5489  456.41  5515.9  457.44  5824.6  473.57
#Mann= 11 ,-1 , 0
  3355.3     .05       0  3460.2     .07       0  3819.8     .05       0
  4346.1     .07       0    4808     .05       0  4884.2     .07       0
  4981.4     .05       0  5013.5     .07       0  5326.9     .05       0
    5489     .07       0  5515.9     .05       0
Bank Sta=4981.4,5013.5
XS Rating Curve= 0 ,0
Exp/Cntr=0.3,0.1

Type RM Length L Ch R = 1 ,400789  ,574,574,574
BEGIN DESCRIPTION:
SANDIES CREEK 58.0
END DESCRIPTION:
XS GIS Cut Line= 3
      2337625.01     13698974.98        2338625.       13697425.
        2338475.       13696625.
#Sta/Elev= 30
    3156  489.84  3322.6  487.51    3394   483.4  3466.8  475.46  3522.2  470.09
  3719.9  458.02  3856.8  454.85  4212.8   454.2  4545.5  449.75  4770.8  450.01
  4899.3  450.26  4941.5  452.51  4964.9  443.18  4971.9  443.07  4973.2  440.01
  4973.7  439.51  5005.4  440.01  5041.3   444.2  5084.5  442.06  5112.5  444.47
  5151.7  444.11    5204  443.17  5242.2   448.3  5254.9  447.96    5266  445.32
  5275.3  448.19  5285.4  449.09  5369.3  450.21  5572.9  456.51  5814.5     467
#Mann= 11 ,-1 , 0
    3156     .05       0  3466.8     .07       0  3522.2     .05       0
  3856.8    .035       0  4212.8     .05       0  4770.8     .07       0
  4973.2     .05       0  5005.4     .07       0  5151.7     .12       0
    5266     .07       0  5369.3     .05       0
Bank Sta=4973.2,5005.4
XS Rating Curve= 0 ,0
Exp/Cntr=0.3,0.1

Type RM Length L Ch R = 1 ,400215  ,547,547,547
BEGIN DESCRIPTION:
SANDIES CREEK 59.0
END DESCRIPTION:
XS GIS Cut Line= 3
        2338725.     13698774.99        2339125.       13697225.
      2338824.99     13696424.97
#Sta/Elev= 30
  3403.4  465.64  3837.1  454.69  4043.9  451.78  4224.1  450.49  4325.6   452.1
  4374.5   452.3  4498.1  450.49  4591.1  445.96  4632.4  446.63  4653.1  444.08
    4700  446.54    4777  449.35  4838.9  442.65  4945.8  441.41  4981.3  438.01
  4993.8  438.04  5001.6  440.12  5002.6  438.01  5003.1  437.51  5034.8  438.01
  5036.2  450.07  5057.6  450.86  5099.4  447.86  5152.5  447.27  5298.3  449.11
  5307.6   449.5  5580.9  457.74  5661.5  462.55  5680.5  463.58  5858.6  472.15
#Mann= 13 ,-1 , 0
  3403.4     .05       0  4043.9     .07       0  4325.6     .05       0
  4374.5     .07       0  4653.1     .12       0    4700     .07       0
  5002.6     .05       0  5034.8     .07       0  5152.5     .05       0
  5298.3     .12       0  5307.6     .05       0  5661.5     .07       0
  5680.5     .05       0
Bank Sta=5002.6,5034.8
XS Rating Curve= 0 ,0
Exp/Cntr=0.3,0.1

Type RM Length L Ch R = 1 ,399668  ,338,338,338
BEGIN DESCRIPTION:
SANDIES CREEK 60.0
END DESCRIPTION:
XS GIS Cut Line= 3
      2338925.01     13698924.99        2339625.       13697375.
      2339874.99     13696675.02
#Sta/Elev= 30
  3303.2  466.47  3465.9  462.24  3599.4  458.56  3728.4  453.63  3951.5  450.65
  4394.2  448.05  4532.3  447.65  4638.9  445.76  4649.9  445.73  4745.5  448.08
  4784.5  449.85  4816.8  449.22  4822.3  447.08  4845.4  446.17  4850.9   443.9
  4891.6  440.24  4949.1  438.81    4960  439.84    4994  435.68  4994.6  435.18
  5026.7  435.68  5035.8  444.22  5088.9  443.32  5106.5  442.05    5168  445.81
  5224.3  445.64  5374.1  447.96  5477.6  452.69  5630.4  460.41  5747.2  462.91
#Mann= 12 ,-1 , 0
  3303.2     .07       0  3465.9     .05       0  4394.2    .035       0
  4532.3     .05       0  4638.9     .12       0  4649.9    .035       0
  4745.5     .07       0    4994     .05       0  5026.7     .07       0
  5106.5    .035       0  5374.1     .07       0  5477.6     .05       0
Bank Sta=4994,5026.7
XS Rating Curve= 0 ,0
Exp/Cntr=0.3,0.1

Type RM Length L Ch R = 1 ,399330  ,144,144,144
BEGIN DESCRIPTION:
SAND21666
END DESCRIPTION:
XS GIS Cut Line= 5
      2339128.14     13699066.58       2339547.3     13698237.28
      2339732.09     13697831.65       2340191.8     13697074.47
      2340327.01     13696727.43
#Sta/Elev= 30
  3323.9  462.94  3639.5  456.39  4055.9  451.18  4183.2   450.3  4611.5  445.52
  4719.5  445.36  4829.6  448.02  4866.4  447.94  4887.7  445.51  4903.2   447.8
  4909.1   445.3  4924.6   447.8  4930.4  444.73  4952.3  443.87  4958.3  433.28
  4958.8  432.78    4991  433.28  4998.2  435.34  5025.4  433.28  5059.1  435.43
    5099   440.7  5175.5  440.48  5285.5  441.26  5361.8  443.99  5405.2  440.53
    5487  445.84  5574.1  448.84  5621.9  451.23  5772.2  459.73  5957.1  465.27
#Mann= 14 ,-1 , 0
  3323.9     .07       0  3639.5     .05       0  4055.9    .035       0
  4183.2     .05       0  4611.5    .063       0  4719.5    .035       0
  4958.3    .035       0    4991    .035       0  5059.1     .07       0
  5175.5    .063       0  5285.5     .07       0    5487    .035       0
  5574.1     .07       0  5621.9    .035       0
Bank Sta=4958.3,4991
XS Rating Curve= 0 ,0
Exp/Cntr=0.3,0.1

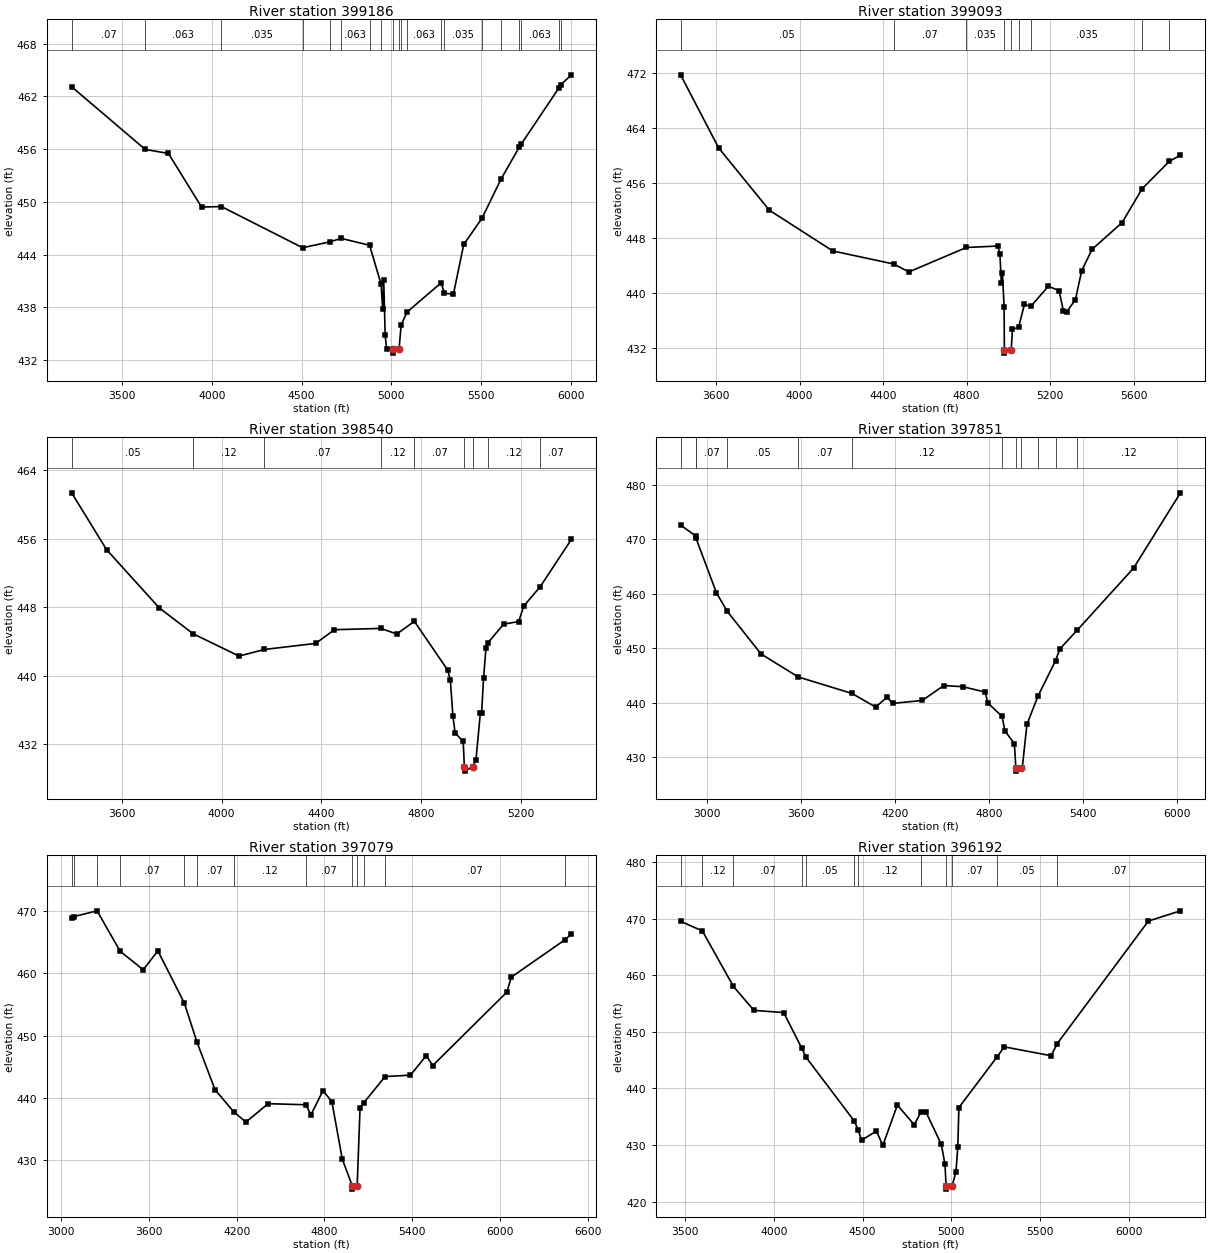
Type RM Length L Ch R = 1 ,399186  ,93,93,93
BEGIN DESCRIPTION:
SAND21667
END DESCRIPTION:
XS GIS Cut Line= 6
      2339169.38     13699128.67      2339551.81     13698561.78
      2339637.44     13698363.47      2339903.35      13697800.1
       2340381.1      13696966.3      2340525.33     13696700.37
#Sta/Elev= 30
  3217.8  463.09    3628  455.96  3757.2  455.51  3941.7  449.41  4052.7  449.46
  4505.5  444.78  4657.4  445.45  4720.3  445.84  4878.7  445.06  4942.8  440.63
  4951.7  437.78  4957.4  441.09  4965.5  434.86  4973.2  433.29  5010.3  433.29
  5010.9  432.79  5043.2  433.29  5054.4  435.98  5087.3  437.46  5277.6  440.79
    5296  439.61  5345.8  439.49  5403.4  445.15  5504.6  448.11  5612.5  452.63
  5713.8  456.25  5723.8  456.56    5932   462.9  5944.4  463.32  6004.1  464.45
#Mann= 20 ,-1 , 0
  3217.8     .07       0    3628    .063       0  4052.7    .035       0
  4505.5    .063       0  4657.4    .035       0  4720.3    .063       0
  4878.7    .035       0  4942.8    .063       0  5010.3    .063       0
  5043.2    .063       0  5054.4    .035       0  5087.3    .063       0
  5277.6     .07       0    5296    .035       0  5504.6    .035       0
  5612.5    .063       0  5713.8    .035       0  5723.8    .063       0
    5932    .035       0  5944.4    .063       0
Bank Sta=5010.3,5043.2
XS Rating Curve= 0 ,0
Exp/Cntr=0.3,0.1

Type RM Length L Ch R = 1 ,399093  ,553,553,553
BEGIN DESCRIPTION:
SANDIES CREEK 61.0
END DESCRIPTION:
XS GIS Cut Line= 4
        2339875.     13699124.98        2340125.       13697575.
      2340130.75     13697548.14      2340565.91     13696880.63
#Sta/Elev= 30
    3430  471.74  3612.3  461.11  3855.4  452.05  4159.3  446.13    4450  444.24
  4523.9  443.09  4799.2  446.64  4949.4  446.85  4959.5  445.73  4966.6  441.45
  4971.6  442.86  4979.7  437.97    4981  431.78  4981.5  431.28  5013.9  431.78
  5019.6  434.75  5048.8  435.01    5077  438.36  5107.9  438.09  5191.6  440.99
    5243  440.38  5264.1  437.35  5279.2  437.25  5321.4  439.07  5351.6  443.28
  5401.3  446.38  5544.7  450.25  5641.1  455.19  5770.8  459.15  5824.3  460.06
#Mann= 9 ,-1 , 0
    3430     .05       0    4450     .07       0  4799.2    .035       0
    4981    .035       0  5013.9    .035       0  5048.8    .063       0
  5107.9    .035       0  5641.1     .07       0  5770.8    .035       0
Bank Sta=4981,5013.9
XS Rating Curve= 0 ,0
Exp/Cntr=0.3,0.1

Type RM Length L Ch R = 1 ,398540  ,689,689,689
BEGIN DESCRIPTION:
SANDIES CREEK 62.0
END DESCRIPTION:
XS GIS Cut Line= 3
      2340224.99     13698975.04        2340625.       13697425.
        2340575.     13697025.04
#Sta/Elev= 30
  3399.1  461.34  3538.9  454.71  3750.3  447.91  3886.3  444.88  4070.4  442.28
    4171  443.05  4377.4  443.76  4452.6  445.36  4638.3  445.51  4702.7  444.86
    4773  446.34    4907  440.63  4917.3  439.48  4927.6  435.31  4936.3  433.31
  4968.9  432.31  4973.5  429.35  4974.1  428.85  5006.5  429.35  5020.1  430.17
  5037.7  435.67  5042.8  435.61  5050.3  439.67  5060.4  443.28    5067   443.8
  5130.9  446.01  5191.4  446.31  5211.6  448.12  5277.6  450.38    5403  455.92
#Mann= 9 ,-1 , 0
  3399.1     .05       0  3886.3     .12       0    4171     .07       0
  4638.3     .12       0    4773     .07       0  4973.5     .05       0
  5006.5     .07       0    5067     .12       0  5277.6     .07       0
Bank Sta=4973.5,5006.5
XS Rating Curve= 0 ,0
Exp/Cntr=0.3,0.1

Type RM Length L Ch R = 1 ,397851  ,772,772,772
BEGIN DESCRIPTION:
C20483
END DESCRIPTION:
XS GIS Cut Line= 3
      2340983.71     13699720.23      2341249.16     13698204.93
      2341293.41      13696556.6
#Sta/Elev= 30
  2833.5  472.56  2929.1   470.6  2931.9  470.15  3062.2  460.14  3130.8  456.76
  3346.4  448.94    3584  444.72  3926.5   441.7  4077.4   439.2  4149.2  440.99
  4189.1  439.89  4374.3  440.41  4511.9  443.15  4631.9  442.94  4776.4  441.95
    4792  439.98  4883.3  437.49    4902  434.81    4962  432.49  4971.5  427.96
  4972.1  427.46  5004.5  427.96    5012  427.96    5042  436.02  5112.3  441.21
  5224.5  447.72  5252.1  449.87  5363.3  453.32  5722.3  464.69  6020.8  478.48
#Mann= 12 ,-1 , 0
  2833.5     .07       0  2929.1     .12       0  2931.9     .07       0
  3130.8     .05       0    3584     .07       0  3926.5     .12       0
  4883.3     .07       0  4971.5     .05       0  5004.5     .07       0
  5112.3     .12       0  5224.5     .07       0  5363.3     .12       0
Bank Sta=4971.5,5004.5
XS Rating Curve= 0 ,0
Exp/Cntr=0.3,0.1

Type RM Length L Ch R = 1 ,397079  ,887,887,887
BEGIN DESCRIPTION:
C20482
END DESCRIPTION:
XS GIS Cut Line= 3
       2341890.8     13699654.15      2341846.55     13698581.07
      2342233.75     13696268.96
#Sta/Elev= 30
  3071.1  468.83  3085.8  469.12    3245  470.05  3402.6  463.56  3560.7  460.59
  3660.8  463.62  3841.5  455.25  3927.7     449  4051.1  441.35  4178.5   437.8
  4262.8  436.12  4414.9  439.08  4673.1  438.91  4707.4  437.29    4790  441.18
  4850.9  439.38  4921.8  430.19  4990.6  425.86  4991.2  425.36  5023.7  425.86
  5043.5  438.45  5070.1  439.26  5214.7  443.44  5388.2  443.66  5496.3   446.8
  5540.3   445.2  6047.6     457  6077.7   459.4  6446.6  465.43  6489.4  466.35
#Mann= 13 ,-1 , 0
  3071.1     .12       0  3085.8     .07       0    3245     .12       0
  3402.6     .07       0  3841.5     .12       0  3927.7     .07       0
  4178.5     .12       0  4673.1     .07       0  4990.6     .05       0
  5023.7     .07       0  5070.1     .12       0  5214.7     .07       0
  6446.6    .035       0
Bank Sta=4990.6,5023.7
XS Rating Curve= 0 ,0
Exp/Cntr=0.3,0.1

Type RM Length L Ch R = 1 ,396192  ,947,947,947
BEGIN DESCRIPTION:
C20481
END DESCRIPTION:
XS GIS Cut Line= 3
      2341969.13     13699574.93      2342554.58       13698393.
      2343494.93     13697231.39
#Sta/Elev= 30
  3475.6  469.56    3598  467.87  3773.1  458.04  3888.5  453.81  4055.8  453.43
  4156.3  447.21    4182  445.51  4453.1  434.25  4474.4  432.74    4494  430.85
  4578.1  432.46  4613.8  429.92  4695.8  437.07  4790.7  433.58  4827.4  435.77
  4856.8  435.82  4943.1  430.13  4963.9  426.58  4969.9   422.7  4970.5   422.2
  5003.1   422.7  5025.7  425.26  5035.8  429.64  5042.2  436.63  5256.7  445.58
    5298  447.36  5561.8  445.79  5594.5  447.89  6108.6  469.61  6289.1  471.42
#Mann= 12 ,-1 , 0
  3475.6     .07       0    3598     .12       0  3773.1     .07       0
  4156.3     .12       0    4182     .05       0  4453.1     .07       0
  4474.4     .12       0  4827.4     .07       0  4969.9     .05       0
  5003.1     .07       0  5256.7     .05       0  5594.5     .07       0
Bank Sta=4969.9,5003.1
XS Rating Curve= 0 ,0
Exp/Cntr=0.3,0.1