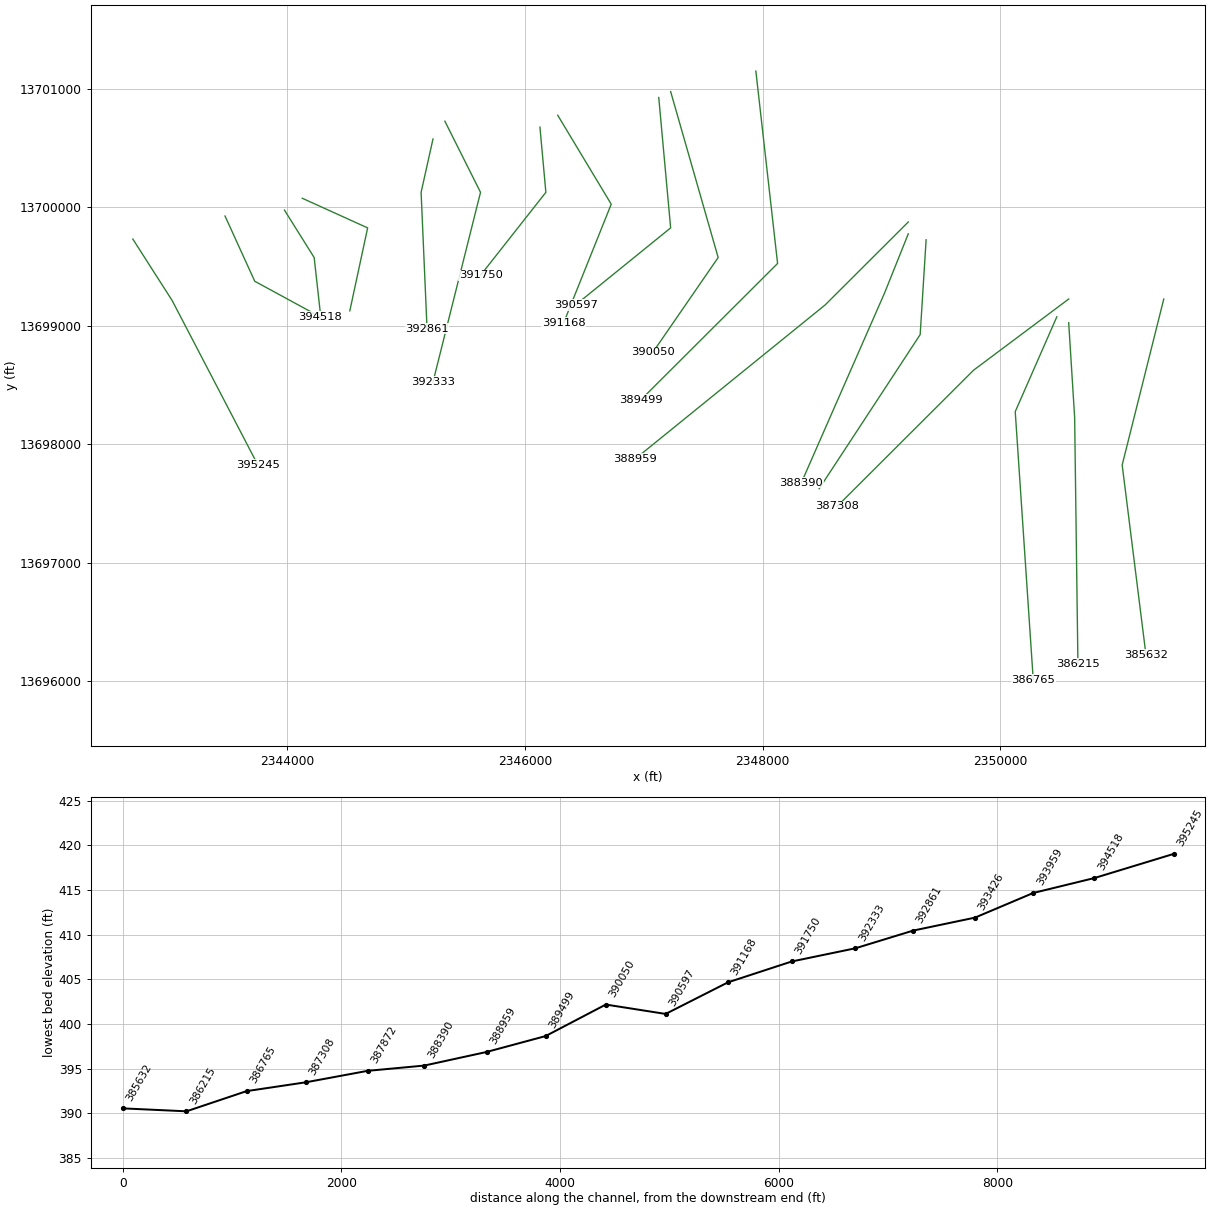
HEC-RAS study SANDIES CREEK.prj: SANDIES CREEK Base Level Engineering

--- SANDIES CREEK.g01 (geometry) --- (continued)

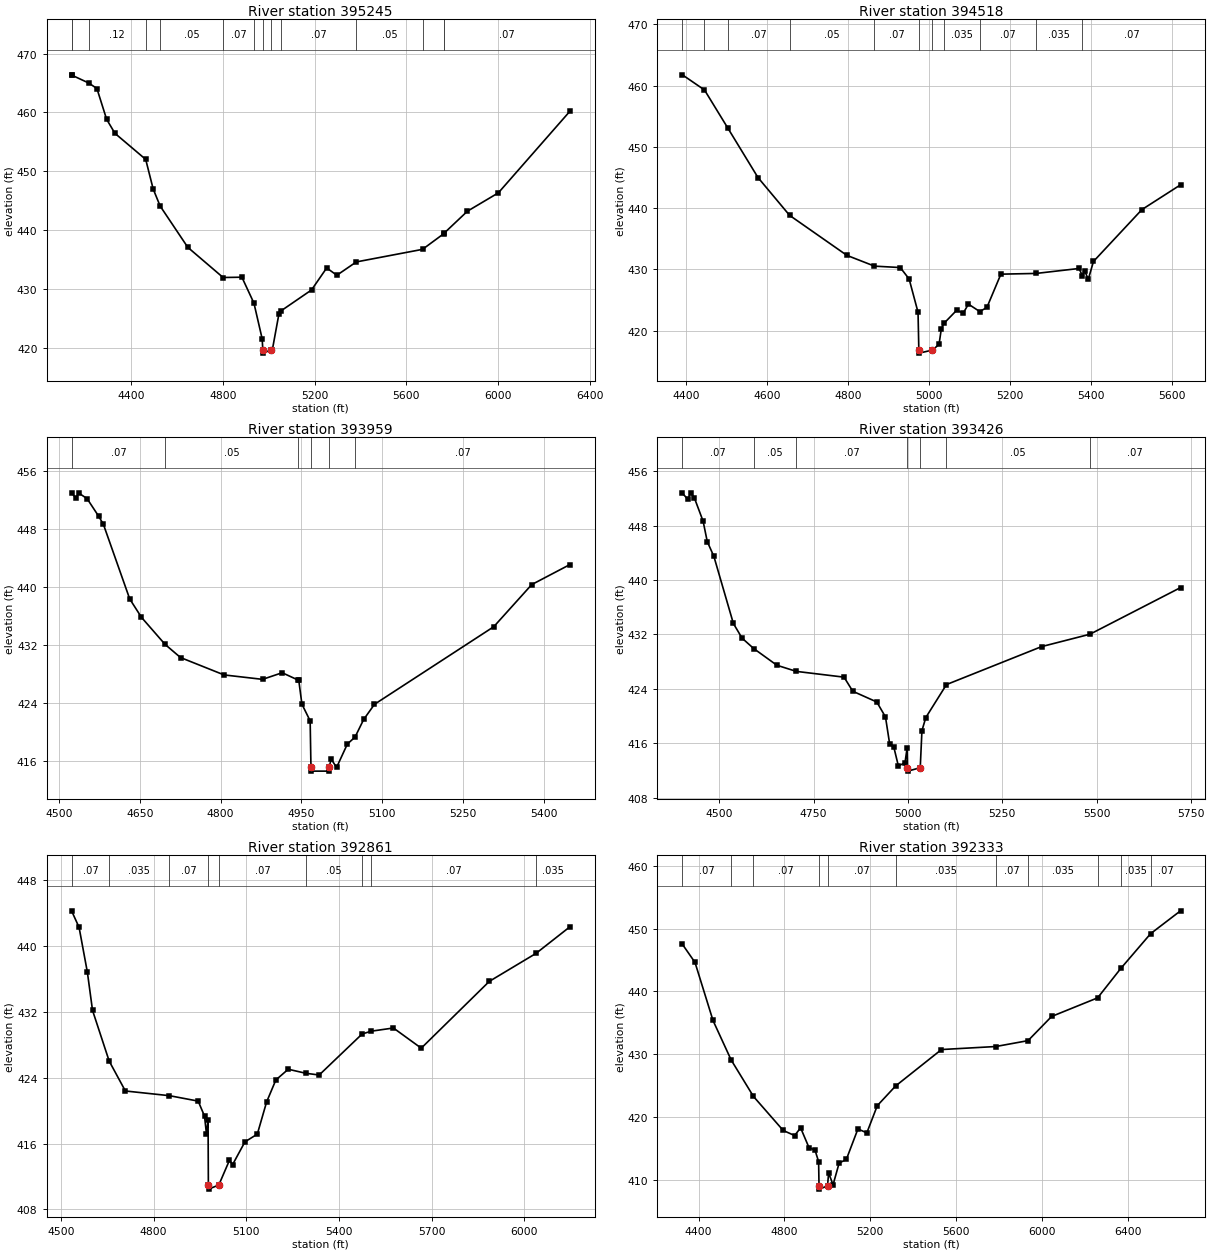
Type RM Length L Ch R = 1 ,395245  ,727,727,727
BEGIN DESCRIPTION:
C20480
END DESCRIPTION:
XS GIS Cut Line= 3
      2342698.88     13699730.84      2343030.28     13699211.65
      2343749.37     13697828.78
#Sta/Elev= 30
  4138.8  466.41  4140.5  466.34  4214.6     465  4249.5  464.07  4291.8  458.84
  4328.2  456.45  4462.4  452.02  4494.9     447  4525.3  444.09  4646.3  437.05
  4800.3  431.92  4882.4  431.97    4935  427.55  4970.8   421.5  4973.8  419.55
  4974.4  419.05  5007.4  419.55    5015  419.55    5044  425.72  5051.6   426.2
  5186.3   429.8  5252.6  433.55  5296.8   432.3  5381.9  434.57  5670.9  436.71
  5762.8  439.35    5765  439.45  5866.8   443.2  6002.1  446.33  6313.4  460.17
#Mann= 14 ,-1 , 0
  4138.8     .12       0  4140.5     .07       0  4214.6     .12       0
  4462.4     .07       0  4525.3     .05       0  4800.3     .07       0
    4935     .05       0  4973.8     .05       0  5007.4     .05       0
  5051.6     .07       0  5381.9     .05       0  5670.9     .07       0
  5762.8     .05       0    5765     .07       0
Bank Sta=4973.8,5007.4
XS Rating Curve= 0 ,0
Exp/Cntr=0.3,0.1

Type RM Length L Ch R = 1 ,394518  ,559,559,559
BEGIN DESCRIPTION:
SANDIES CREEK 69.0
END DESCRIPTION:
XS GIS Cut Line= 3
      2343474.99     13699925.02        2343725.       13699375.
      2344275.03     13699074.98
#Sta/Elev= 30
  4390.5  461.77  4445.1   459.3  4503.2  453.03  4577.3     445  4655.4  438.83
  4796.9   432.3  4865.1  430.54  4928.8  430.31  4950.7  428.44  4972.7  423.01
  4974.7  416.84  4975.4  416.34  5008.4  416.84  5024.6  417.77  5030.3  420.32
  5036.7   421.2  5068.2  423.34  5084.4  422.87  5097.2  424.34  5125.1  423.13
  5142.8  423.79  5177.4  429.23  5264.6  429.35  5370.6  430.16  5378.6  428.98
  5384.3  429.81  5393.3  428.38  5406.2  431.31  5525.8  439.77  5621.2  443.81
#Mann= 11 ,-1 , 0
  4390.5     .07       0  4445.1     .12       0  4503.2     .07       0
  4655.4     .05       0  4865.1     .07       0  4974.7     .05       0
  5008.4     .07       0  5036.7    .035       0  5125.1     .07       0
  5264.6    .035       0  5378.6     .07       0
Bank Sta=4974.7,5008.4
XS Rating Curve= 0 ,0
Exp/Cntr=0.3,0.1

Type RM Length L Ch R = 1 ,393959  ,533,533,533
BEGIN DESCRIPTION:
SANDIES CREEK 70.0
END DESCRIPTION:
XS GIS Cut Line= 3
      2343975.01     13699974.99        2344225.       13699575.
        2344275.     13699124.96
#Sta/Elev= 30
  4523.5  452.94  4531.2  452.24  4537.1   452.9  4552.4  452.13  4573.6  449.74
  4582.5  448.62  4631.4  438.35  4653.2  435.82    4697   432.1  4725.7  430.29
  4806.5   427.9  4877.9  427.29  4914.4   428.2    4944  427.19  4945.1   427.2
    4951  423.88  4966.3  421.58  4967.8  415.17  4968.5  414.67  5000.9  414.67
  5001.5  415.17  5005.3  416.34  5015.3  415.17  5035.4   418.4  5049.6  419.35
  5065.6  421.77  5085.7  423.86  5307.1  434.53  5377.5  440.32    5448  443.06
#Mann= 6 ,-1 , 0
  4523.5     .07       0    4697     .05       0    4944    .035       0
  4967.8    .035       0  5001.5    .035       0  5049.6     .07       0
Bank Sta=4967.8,5001.5
XS Rating Curve= 0 ,0
Exp/Cntr=0.3,0.1

Type RM Length L Ch R = 1 ,393426  ,565,565,565
BEGIN DESCRIPTION:
SANDIES CREEK 71.0
END DESCRIPTION:
XS GIS Cut Line= 3
      2344125.01       13700075.        2344675.       13699825.
      2344525.01     13699125.03
#Sta/Elev= 30
  4402.2  452.75  4416.5  451.87  4424.2  452.81    4434  452.06  4457.1  448.64
  4468.1  445.65  4485.7  443.46  4537.3  433.61  4560.4  431.45  4591.1  429.93
  4652.6  427.47    4704  426.57  4830.6  425.72  4853.7  423.65  4917.4  422.07
  4940.4  419.87  4951.4  415.93  4962.4  415.46  4974.5  412.68  4992.1  413.14
  4997.6  415.27  4998.7  412.41  4999.4  411.91  5032.5  412.41    5037  417.86
  5047.3  419.79    5102  424.63  5354.1  430.21  5482.2  432.03  5722.2  438.88
#Mann= 7 ,-1 , 0
  4402.2     .07       0  4591.1     .05       0    4704     .07       0
  4998.7     .05       0  5032.5     .07       0    5102     .05       0
  5482.2     .07       0
Bank Sta=4998.7,5032.5
XS Rating Curve= 0 ,0
Exp/Cntr=0.3,0.1

Type RM Length L Ch R = 1 ,392861  ,528,528,528
BEGIN DESCRIPTION:
SANDIES CREEK 72.0
END DESCRIPTION:
XS GIS Cut Line= 3
      2345224.99     13700574.97        2345125.       13700125.
        2345175.     13698975.03
#Sta/Elev= 30
  4534.7  444.26    4559  442.25  4585.9  436.79  4602.5  432.17  4656.4  426.01
  4708.8  422.38  4851.3  421.81  4944.4  421.15  4964.9  419.33  4971.3  417.14
  4976.4  418.85  4977.4  410.96  4978.1  410.46  5011.2  410.96  5045.7  413.97
  5055.7  413.43  5095.7   416.2  5135.8  417.14  5165.8  421.04  5195.8  423.72
  5235.9  425.02  5292.8  424.53    5336  424.32  5474.9   429.3  5504.1  429.64
  5576.2  430.03  5666.3  427.58  5886.5  435.69  6037.7  439.09  6146.7   442.3
#Mann= 9 ,-1 , 0
  4534.7     .07       0  4656.4    .035       0  4851.3     .07       0
  4977.4     .05       0  5011.2     .07       0  5292.8     .05       0
  5474.9    .035       0  5504.1     .07       0  6037.7    .035       0
Bank Sta=4977.4,5011.2
XS Rating Curve= 0 ,0
Exp/Cntr=0.3,0.1

Type RM Length L Ch R = 1 ,392333  ,583,583,583
BEGIN DESCRIPTION:
SANDIES CREEK 73.0
END DESCRIPTION:
XS GIS Cut Line= 3
      2345324.99     13700725.01        2345625.       13700125.
      2345224.99     13698524.98
#Sta/Elev= 30
  4324.9  447.51  4383.6  444.62  4467.5  435.36    4552  429.07    4656  423.25
  4794.5  417.83  4847.6  417.02  4875.5  418.25  4914.7  415.09  4942.6   414.7
  4959.4  412.86  4961.3  408.98  4962.3  408.48  5000.9  408.98    5006  411.06
  5026.7  409.17    5055  412.64  5088.5  413.21  5142.6  418.08  5183.9  417.44
  5232.8  421.79    5318  424.92  5531.7  430.73  5784.4  431.21  5934.9  432.15
  6044.6     436    6259  438.97  6366.7  443.65  6505.8   449.2    6645  452.84
#Mann= 11 ,-1 , 0
  4324.9     .07       0    4552    .035       0    4656     .07       0
  4961.3     .05       0  5000.9     .07       0    5318    .035       0
  5784.4     .07       0  5934.9    .035       0    6259     .07       0
  6366.7    .035       0  6505.8     .07       0
Bank Sta=4961.3,5000.9
XS Rating Curve= 0 ,0
Exp/Cntr=0.3,0.1

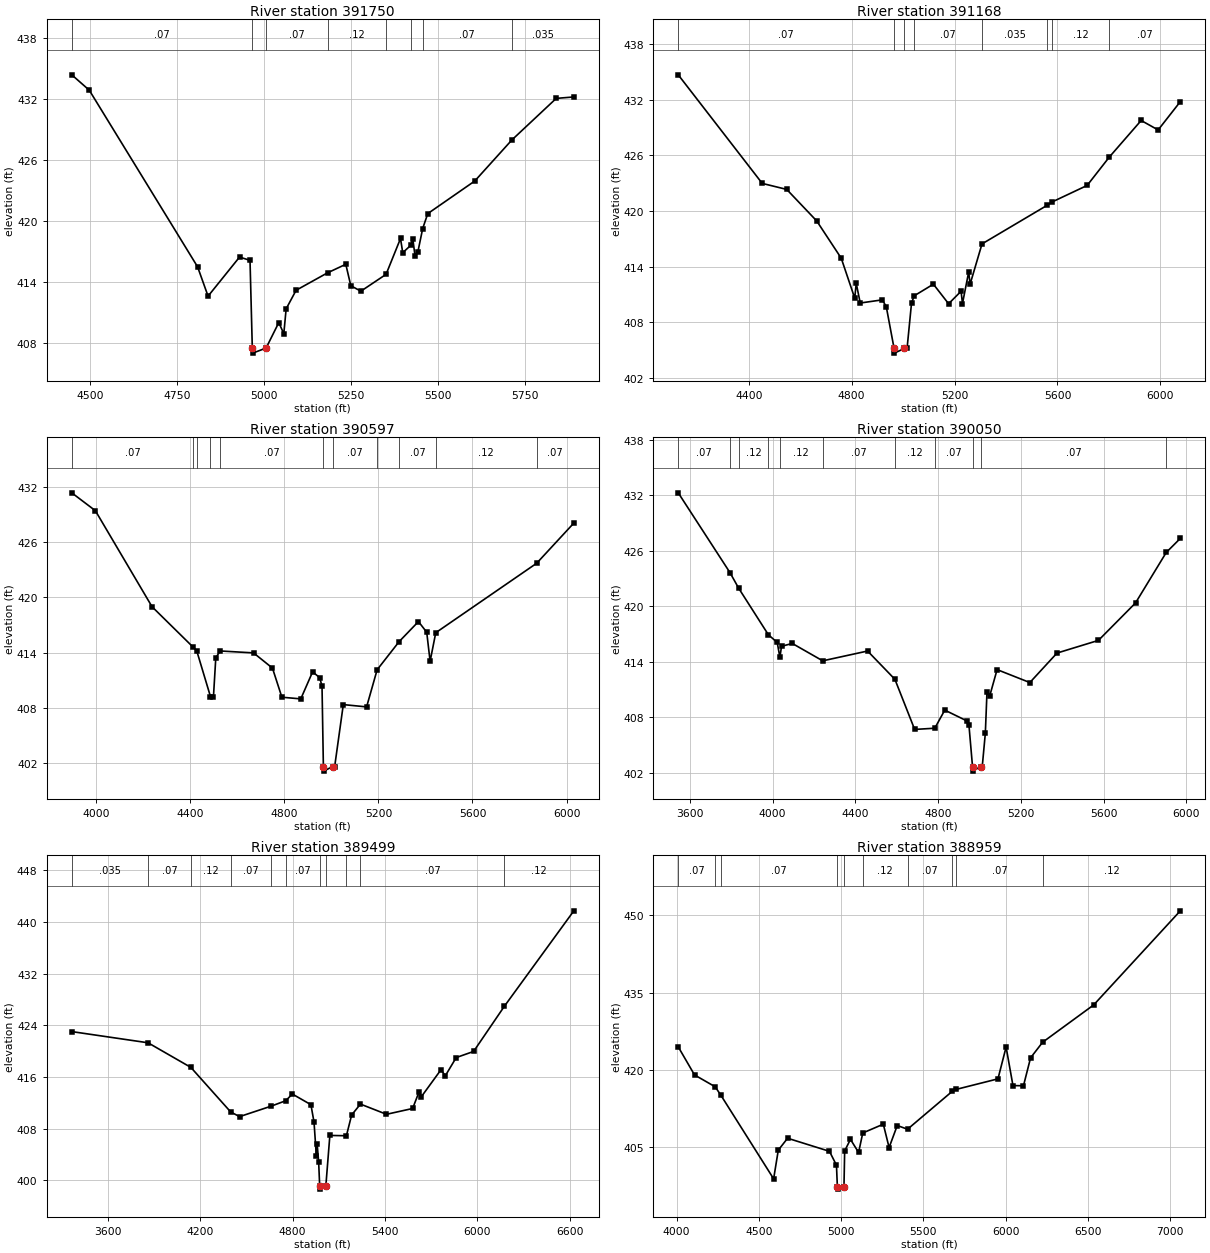
Type RM Length L Ch R = 1 ,391750  ,582,582,582
BEGIN DESCRIPTION:
SANDIES CREEK 74.0
END DESCRIPTION:
XS GIS Cut Line= 3
        2346125.     13700675.02        2346175.       13700125.
      2345625.01     13699425.01
#Sta/Elev= 30
  4447.8  434.41    4498   432.9  4809.3   415.5  4839.4  412.61  4929.8  416.46
  4959.9  416.14  4966.5   407.5  4967.5     407  5006.1   407.5  5042.6  410.01
    5057  408.91  5063.7  411.36  5092.3  413.19  5182.7  414.91  5235.1  415.75
  5249.5  413.64  5278.4   413.1  5350.8  414.76  5392.3  418.29  5398.7  416.89
  5421.5  417.61  5427.6  418.25  5433.9  416.61    5442  416.94    5456  419.27
  5470.6  420.74  5605.6  423.95  5712.4     428  5839.7  432.09  5890.3  432.23
#Mann= 8 ,-1 , 0
  4447.8     .07       0  4966.5     .05       0  5006.1     .07       0
  5182.7     .12       0  5350.8     .07       0  5421.5     .12       0
    5456     .07       0  5712.4    .035       0
Bank Sta=4966.5,5006.1
XS Rating Curve= 0 ,0
Exp/Cntr=0.3,0.1

Type RM Length L Ch R = 1 ,391168  ,571,571,571
BEGIN DESCRIPTION:
SANDIES CREEK 75.0
END DESCRIPTION:
XS GIS Cut Line= 3
        2346275.       13700775.        2346725.       13700025.
      2346324.99     13699024.98
#Sta/Elev= 30
  4125.8  434.66  4452.3  422.96  4547.6  422.31  4664.2  418.91  4759.4   414.9
  4811.9  410.59  4817.7  412.19  4833.3  410.07  4918.8  410.41  4934.4  409.69
  4964.9  405.17  4965.9  404.67  5004.6  405.17  5015.3  405.17  5032.8  410.11
  5043.9  410.86  5117.6   412.1  5176.8  409.99  5225.3  411.34  5230.7  410.01
  5254.9  413.42  5260.3  412.09  5306.6  416.44  5561.1  420.62  5577.6  420.94
  5715.3  422.74  5801.6   425.8  5925.3  429.74  5991.3  428.72  6077.5  431.77
#Mann= 8 ,-1 , 0
  4125.8     .07       0  4964.9    .035       0  5004.6     .07       0
  5043.9     .07       0  5306.6    .035       0  5561.1     .07       0
  5577.6     .12       0  5801.6     .07       0
Bank Sta=4964.9,5004.6
XS Rating Curve= 0 ,0
Exp/Cntr=0.3,0.1

Type RM Length L Ch R = 1 ,390597  ,547,547,547
BEGIN DESCRIPTION:
SANDIES CREEK 76.0
END DESCRIPTION:
XS GIS Cut Line= 3
        2347125.     13700924.96        2347225.       13699825.
      2346424.98     13699174.98
#Sta/Elev= 30
  3895.9  431.33  3996.3  429.39  4237.3  418.97  4412.1  414.58  4427.3  414.19
  4485.9  409.21  4498.3  409.12  4508.4  413.42  4526.9  414.17    4669  413.96
  4749.4  412.31  4789.5  409.15  4869.9  408.97  4920.1   411.9  4950.2  411.28
  4960.2  410.35    4966  401.63    4967  401.13    5006  401.63    5014  401.63
  5050.7  408.35  5149.8   408.1  5194.6  412.13    5288  415.18  5370.3  417.36
  5405.5   416.2  5419.9  413.05  5443.9  416.15  5873.2  423.69  6031.2  428.05
#Mann= 11 ,-1 , 0
  3895.9     .07       0  4412.1     .12       0  4427.3     .07       0
  4485.9     .12       0  4526.9     .07       0    4966     .05       0
    5006     .07       0  5194.6     .12       0    5288     .07       0
  5443.9     .12       0  5873.2     .07       0
Bank Sta=4966,5006
XS Rating Curve= 0 ,0
Exp/Cntr=0.3,0.1

Type RM Length L Ch R = 1 ,390050  ,551,551,551
BEGIN DESCRIPTION:
SANDIES CREEK 77.0
END DESCRIPTION:
XS GIS Cut Line= 3
      2347225.01     13700974.97        2347625.       13699575.
      2347075.01     13698775.01
#Sta/Elev= 30
    3544  432.28  3793.8  423.66  3836.2  421.96  3979.7  416.93  4022.4   416.1
  4035.4  414.49  4043.2  415.68  4095.2  415.99  4242.4  414.11  4459.2  415.17
  4591.3  412.11  4686.7  406.69  4784.1  406.82  4832.3  408.78  4937.6  407.63
  4949.3  407.12  4966.4  402.68  4967.4  402.18  5006.5  402.68  5013.5  402.68
  5028.4  406.29  5036.4  410.76  5049.4   410.3  5085.2  413.16  5243.5  411.76
  5374.8  414.95    5575  416.32  5754.3  420.37  5902.8  425.83  5970.8  427.35
#Mann= 11 ,-1 , 0
    3544     .07       0  3793.8    .035       0  3836.2     .12       0
  3979.7     .07       0  4035.4     .12       0  4242.4     .07       0
  4591.3     .12       0  4784.1     .07       0  4966.4     .05       0
  5006.5     .07       0  5902.8     .12       0
Bank Sta=4966.4,5006.5
XS Rating Curve= 0 ,0
Exp/Cntr=0.3,0.1

Type RM Length L Ch R = 1 ,389499  ,540,540,540
BEGIN DESCRIPTION:
SANDIES CREEK 78.0
END DESCRIPTION:
XS GIS Cut Line= 3
      2347942.18     13701147.67        2348125.       13699525.
      2346974.99     13698374.99
#Sta/Elev= 30
  3367.1  423.03  3862.1   421.3  4140.2  417.49  4398.9  410.59  4456.6  409.87
  4662.6   411.5    4756  412.33  4798.8  413.37  4919.5  411.72  4939.7  409.03
  4955.1   403.7  4960.1  405.63  4969.9  402.79  4976.4  399.15  4977.4  398.65
  5016.5  399.15  5042.5  406.96  5149.9  406.91  5183.9  410.12    5241  411.81
  5410.2  410.23  5579.9  411.13  5622.3  413.75  5636.4  412.95  5763.7  417.12
    5792  416.19  5862.7  419.01  5975.8  419.96  6175.1  426.94  6626.4  441.72
#Mann= 11 ,-1 , 0
  3367.1    .035       0  3862.1     .07       0  4140.2     .12       0
  4398.9     .07       0  4662.6     .12       0    4756     .07       0
  4976.4     .05       0  5016.5     .07       0  5149.9     .12       0
    5241     .07       0  6175.1     .12       0
Bank Sta=4976.4,5016.5
XS Rating Curve= 0 ,0
Exp/Cntr=0.3,0.1

Type RM Length L Ch R = 1 ,388959  ,569,569,569
BEGIN DESCRIPTION:
SANDIES CREEK 79.0
END DESCRIPTION:
XS GIS Cut Line= 3
        2349225.       13699875.        2348525.       13699175.
        2346925.       13697875.
#Sta/Elev= 30
  4009.8  424.49  4108.8  419.04  4234.4  416.74  4268.9   415.1  4589.6  398.87
  4617.9  404.44  4674.5  406.75    4929  404.21  4971.5  401.51  4976.9  397.37
  4977.9  396.87  5017.1  397.37  5021.3  404.29  5056.5  406.53    5106  403.99
  5131.3  407.77  5256.2  409.48  5291.4  404.94  5340.9  409.22  5403.5   408.5
    5675  415.85  5698.5  416.23    5953  418.28  6002.5  424.45  6044.2  416.97
  6108.1  416.94  6151.2  422.36  6224.6  425.39  6534.8  432.63  7061.3   450.9
#Mann= 10 ,-1 , 0
  4009.8     .07       0  4234.4    .035       0  4268.9     .07       0
  4976.9     .05       0  5017.1     .07       0  5131.3     .12       0
  5403.5     .07       0    5675     .12       0  5698.5     .07       0
  6224.6     .12       0
Bank Sta=4976.9,5017.1
XS Rating Curve= 0 ,0
Exp/Cntr=0.3,0.1

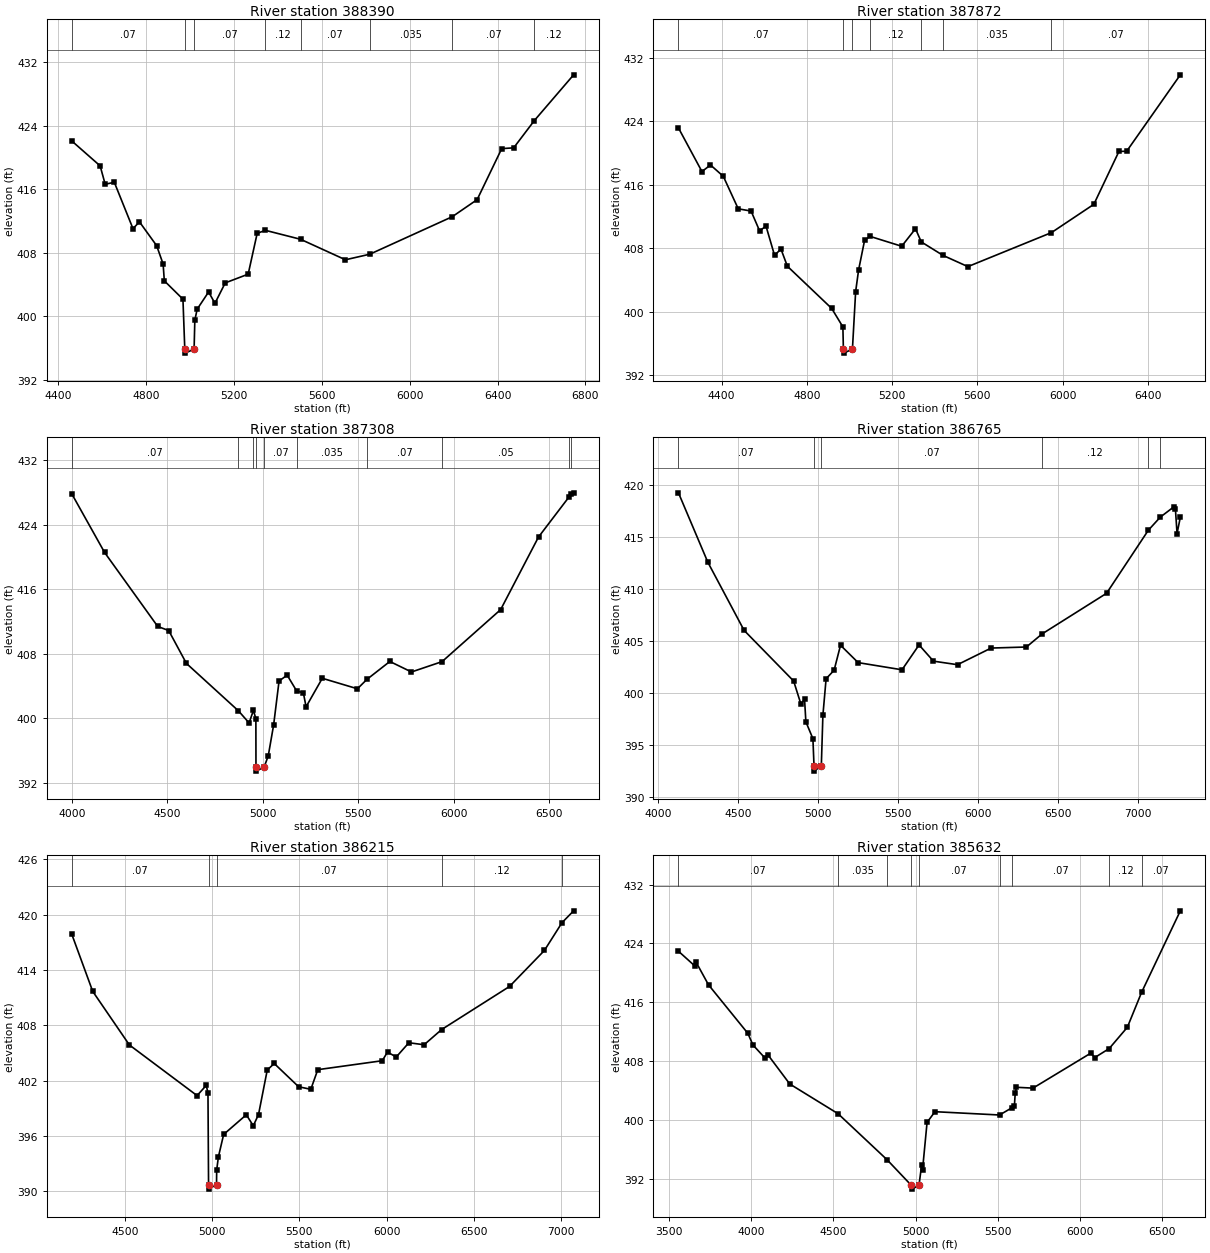
Type RM Length L Ch R = 1 ,388390  ,518,518,518
BEGIN DESCRIPTION:
SANDIES CREEK 80.0
END DESCRIPTION:
XS GIS Cut Line= 3
      2349224.99     13699774.98        2349025.       13699275.
      2348325.01     13697675.02
#Sta/Elev= 30
  4461.5  422.06  4590.7  418.92  4613.6  416.61  4655.3  416.85  4740.2  411.02
  4769.8  411.87  4847.9  408.88  4877.5  406.56  4882.9  404.45  4967.7  402.14
  4976.1  395.85  4977.1  395.35  5018.5  395.85  5021.8  399.49  5032.4  400.88
  5084.6  403.05  5113.4  401.62  5160.2  404.19  5264.7  405.29  5305.6  410.42
  5342.7  410.81  5503.2  409.68  5707.5   407.1  5818.4   407.8  6193.8  412.52
  6307.1  414.67    6419  421.09  6473.5  421.19  6567.8  424.63  6746.4  430.38
#Mann= 8 ,-1 , 0
  4461.5     .07       0  4976.1     .05       0  5018.5     .07       0
  5342.7     .12       0  5503.2     .07       0  5818.4    .035       0
  6193.8     .07       0  6567.8     .12       0
Bank Sta=4976.1,5018.5
XS Rating Curve= 0 ,0
Exp/Cntr=0.3,0.1

Type RM Length L Ch R = 1 ,387872  ,564,564,564
BEGIN DESCRIPTION:
SANDIES CREEK 81.0
END DESCRIPTION:
XS GIS Cut Line= 3
        2349375.     13699724.99        2349325.       13698925.
      2348474.99     13697624.98
#Sta/Elev= 30
  4197.9  423.16  4308.1  417.66  4348.2  418.49  4408.3  417.06  4478.4  412.96
  4538.6  412.68  4578.6  410.18  4608.7  410.78  4648.8  407.09  4678.8  407.89
  4708.9  405.72  4916.8   400.4  4969.4  398.07  4971.8  395.26  4972.8  394.76
  5014.2  395.26  5029.3  402.53  5043.2  405.26  5071.1  408.97  5096.3  409.49
  5245.3  408.24  5310.1  410.45  5337.1  408.79    5439  407.09  5555.9  405.67
    5948  409.96    6147  413.53  6264.7   420.2  6300.9  420.22  6552.7  429.86
#Mann= 7 ,-1 , 0
  4197.9     .07       0  4971.8     .05       0  5014.2     .07       0
  5096.3     .12       0  5337.1     .07       0    5439    .035       0
    5948     .07       0
Bank Sta=4971.8,5014.2
XS Rating Curve= 0 ,0
Exp/Cntr=0.3,0.1

Type RM Length L Ch R = 1 ,387308  ,543,543,543
BEGIN DESCRIPTION:
SANDIES CREEK 82.0
END DESCRIPTION:
XS GIS Cut Line= 3
      2350574.96     13699224.97        2349775.       13698625.
        2348625.       13697475.
#Sta/Elev= 30
  4000.3   427.8  4172.1  420.54  4450.3  411.38  4507.5  410.88  4600.3  406.81
  4872.5  400.94  4928.4  399.44  4950.9     401  4963.8  399.96  4964.3  393.98
  4965.3  393.48  5006.9  393.98  5028.5  395.36  5056.8  399.21  5085.1  404.63
  5127.5  405.36    5177  403.41  5212.4  403.16  5226.5  401.44  5311.4  404.97
  5495.2  403.67  5544.7  404.83  5664.9  407.05  5778.1  405.75  5938.1  407.03
  6244.8  413.47  6442.8  422.45  6602.9  427.42  6611.7  427.73  6626.6  427.92
#Mann= 10 ,-1 , 0
  4000.3     .07       0  4872.5     .12       0  4950.9     .07       0
  4964.3     .05       0  5006.9     .07       0    5177    .035       0
  5544.7     .07       0  5938.1     .05       0  6602.9     .07       0
  6611.7     .12       0
Bank Sta=4964.3,5006.9
XS Rating Curve= 0 ,0
Exp/Cntr=0.3,0.1

Type RM Length L Ch R = 1 ,386765  ,550,550,550
BEGIN DESCRIPTION:
SANDIES CREEK 83.0
END DESCRIPTION:
XS GIS Cut Line= 3
      2350475.02     13699075.04        2350125.       13698275.
      2350276.44     13696014.53
#Sta/Elev= 30
  4126.8  419.24  4310.5  412.57  4537.3  406.02  4847.2  401.15  4892.1  398.96
  4915.5  399.38  4923.7  397.23  4967.7  395.61  4974.6  392.99  4975.6  392.49
  5020.3  392.99  5030.1  397.85  5050.2  401.37  5100.3  402.19  5140.4  404.59
  5250.6  402.92    5525  402.23  5631.5  404.62  5721.7  403.06    5872  402.72
  6082.5  404.32    6303  404.42  6401.2  405.68  6804.1  409.58  7065.3  415.64
  7140.7  416.91    7225  417.89  7235.1  417.65  7245.1  415.33  7265.6  416.89
#Mann= 6 ,-1 , 0
  4126.8     .07       0  4974.6     .05       0  5020.3     .07       0
  6401.2     .12       0  7065.3     .07       0  7140.7     .12       0
Bank Sta=4974.6,5020.3
XS Rating Curve= 0 ,0
Exp/Cntr=0.3,0.1

Type RM Length L Ch R = 1 ,386215  ,583,583,583
BEGIN DESCRIPTION:
SANDIES CREEK 84.0
END DESCRIPTION:
XS GIS Cut Line= 3
        2350575.     13699024.97        2350625.       13698225.
      2350652.58     13696147.21
#Sta/Elev= 30
  4194.1  417.87  4314.3  411.67  4524.7  405.86    4913  400.37  4965.6  401.47
  4975.6  400.68    4979  390.73    4980  390.23  5024.7  390.73  5025.6   392.3
  5035.6  393.74  5065.6  396.16  5195.6  398.29  5235.7   397.1  5265.7  398.32
  5315.7  403.14  5355.7  403.85  5495.7  401.33  5565.7  401.05  5605.7  403.18
  5975.7  404.15  6005.7  405.09  6055.7  404.55  6128.3   406.1  6215.7  405.88
  6316.3  407.53  6705.8   412.2  6905.8   416.1  7007.1  419.12  7073.6   420.4
#Mann= 5 ,-1 , 0
  4194.1     .07       0    4979     .05       0  5024.7     .07       0
  6316.3     .12       0  7007.1     .07       0
Bank Sta=4979,5024.7
XS Rating Curve= 0 ,0
Exp/Cntr=0.3,0.1

Type RM Length L Ch R = 1 ,385632  ,583,583,583
BEGIN DESCRIPTION:
SANDIES CREEK 85.0
END DESCRIPTION:
XS GIS Cut Line= 3
      2351374.99     13699224.97        2351025.       13697825.
        2351225.     13696225.01
#Sta/Elev= 30
  3556.5  422.94    3657  420.92  3662.1  421.52  3739.4  418.37  3979.1  411.76
    4010  410.18  4082.2  408.43  4102.8  408.79  4234.2  404.87  4528.5  400.82
  4826.6  394.56    4975  391.06    4976  390.56  5020.8  391.06  5037.3  393.89
  5042.4  393.17  5070.1  399.64    5118   401.1  5511.3  400.65  5587.9  401.65
  5601.7  401.87  5606.7   403.6  5614.3  404.42  5715.1  404.31  6067.8  409.08
  6090.5  408.46  6178.8  409.69  6289.5  412.59  6376.3  417.35    6612  428.44
#Mann= 9 ,-1 , 0
  3556.5     .07       0  4528.5    .035       0  4826.6     .07       0
    4975     .05       0  5020.8     .07       0  5511.3    .035       0
  5587.9     .07       0  6178.8     .12       0  6376.3     .07       0
Bank Sta=4975,5020.8
XS Rating Curve= 0 ,0
Exp/Cntr=0.3,0.1