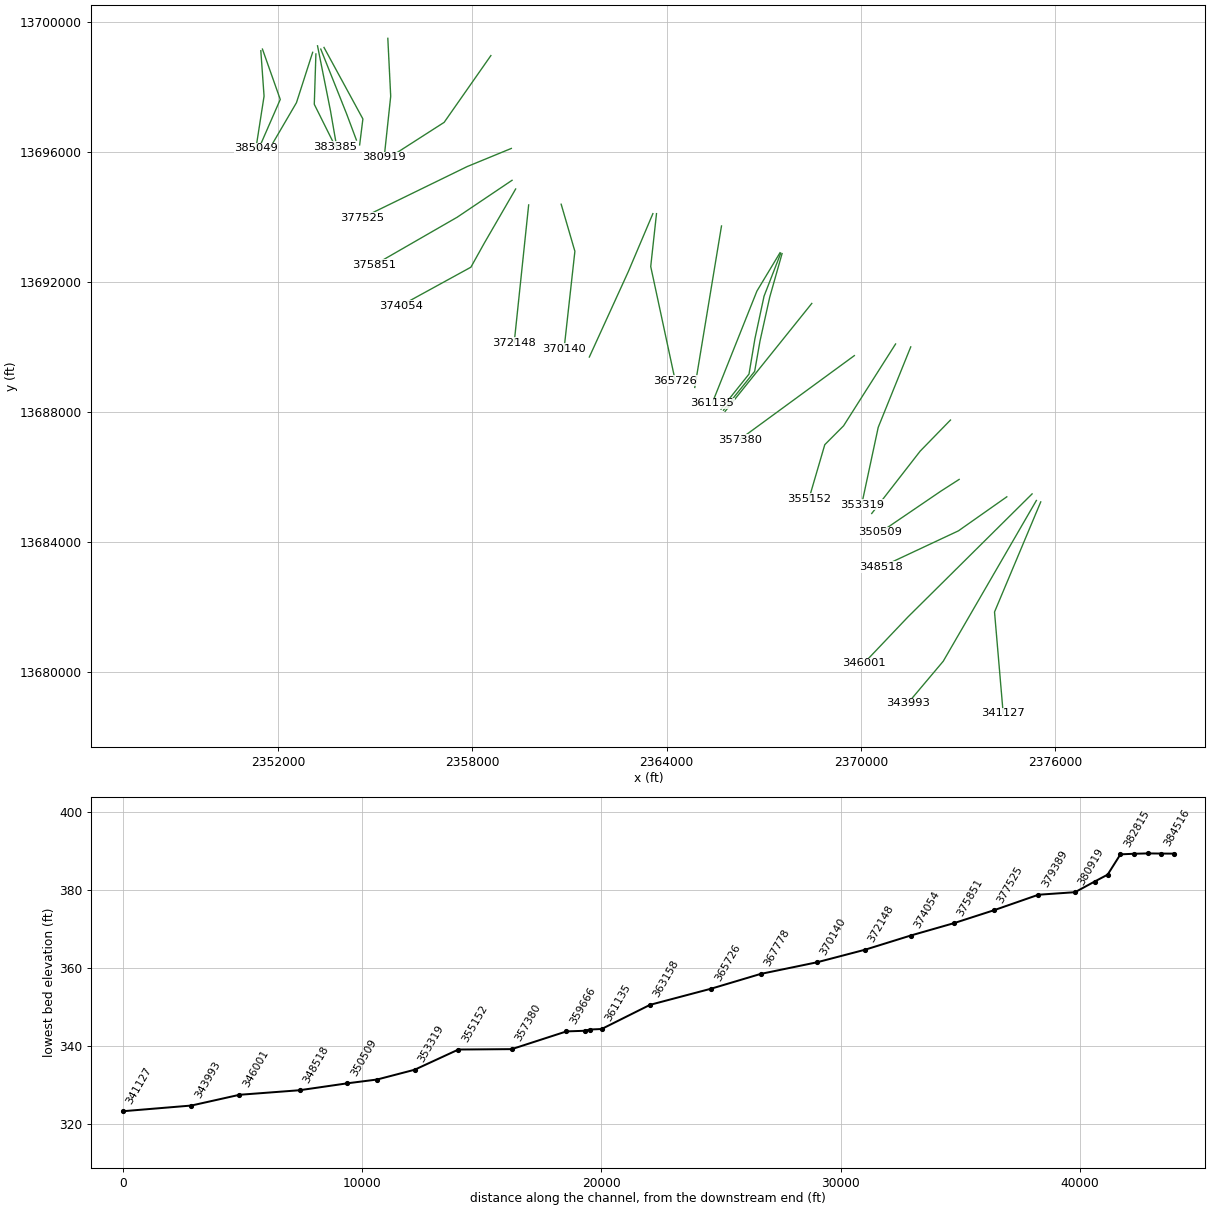
HEC-RAS study SANDIES CREEK.prj: SANDIES CREEK Base Level Engineering

--- SANDIES CREEK.g01 (geometry) --- (continued)

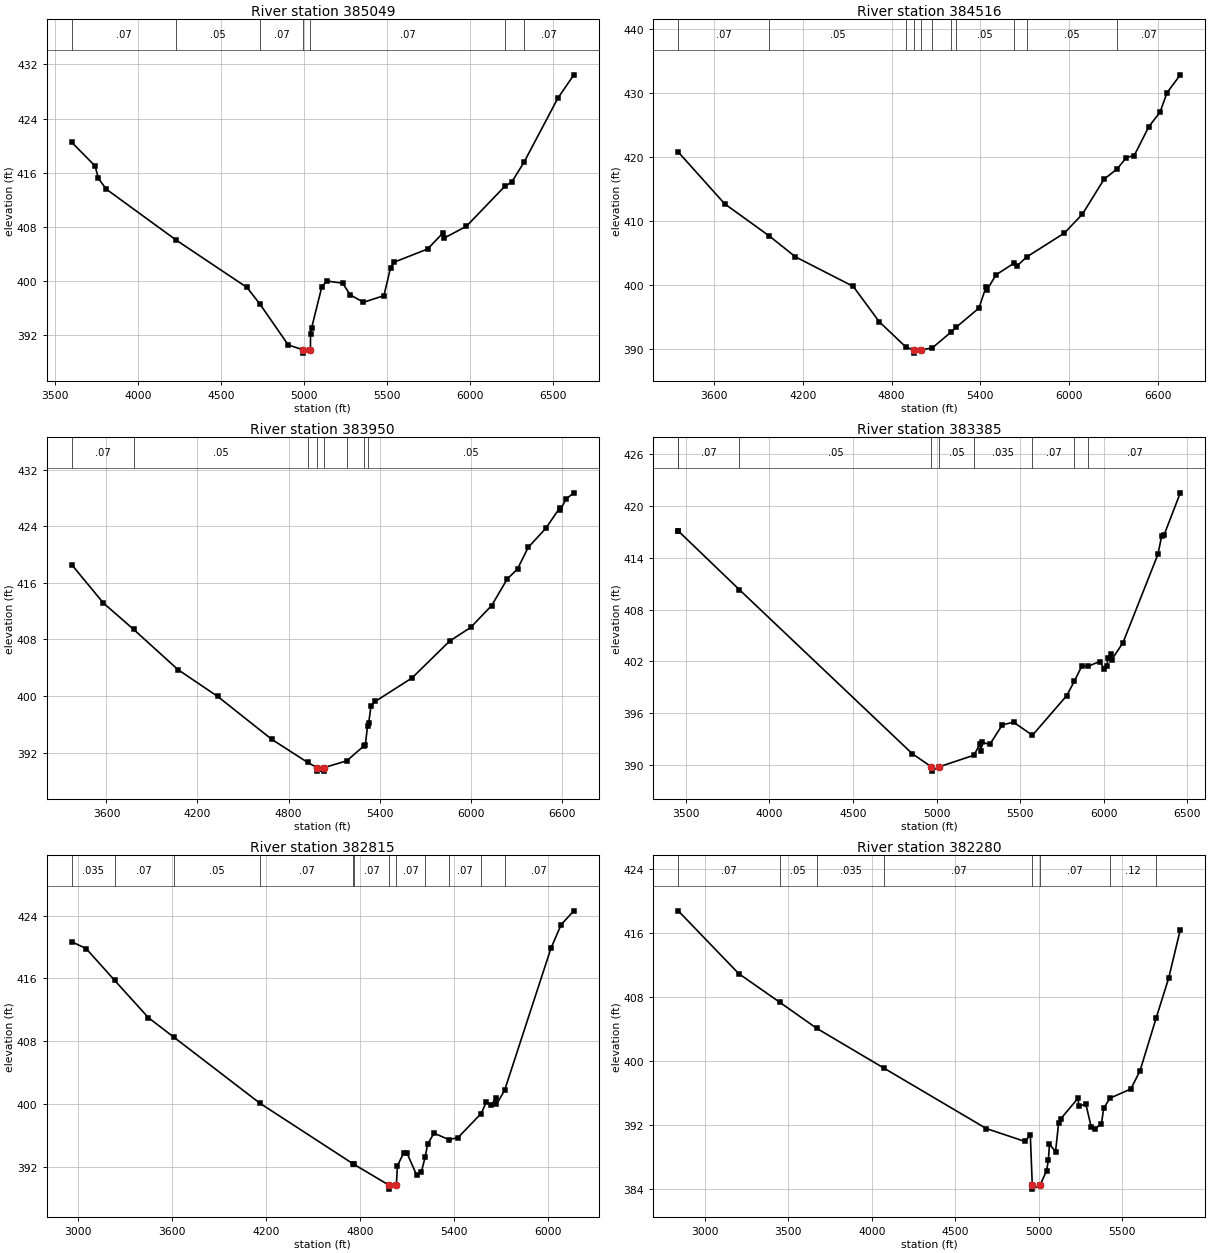
Type RM Length L Ch R = 1 ,385049  ,533,533,533
BEGIN DESCRIPTION:
SANDIES CREEK 86.0
END DESCRIPTION:
XS GIS Cut Line= 3
        2351475.     13699124.99        2351575.       13697725.
      2351324.99     13696124.97
#Sta/Elev= 30
  3601.2  420.49  3741.5     417  3761.6  415.16  3809.2  413.57  4231.4  406.02
  4656.4  399.04  4734.3  396.58  4904.5  390.55  4992.4  389.84  4993.4  389.34
  5038.2  389.84  5038.7  392.14  5045.2  393.05  5106.5  399.12  5136.3     400
    5232  399.68    5278  397.95  5357.5  396.86  5480.5  397.83  5520.9  401.99
  5541.2  402.77  5743.6  404.73  5834.7  407.06  5844.8  406.37  5976.4  408.07
  6209.2  414.01  6249.7   414.6  6324.4  417.56  6527.5     427  6624.2  430.47
#Mann= 7 ,-1 , 0
  3601.2     .07       0  4231.4     .05       0  4734.3     .07       0
  4992.4     .05       0  5038.2     .07       0  6209.2     .12       0
  6324.4     .07       0
Bank Sta=4992.4,5038.2
XS Rating Curve= 0 ,0
Exp/Cntr=0.3,0.1

Type RM Length L Ch R = 1 ,384516  ,566,566,566
BEGIN DESCRIPTION:
SANDIES CREEK 87.0
END DESCRIPTION:
XS GIS Cut Line= 3
        2351525.     13699175.01        2352075.       13697625.
      2351375.01     13696025.02
#Sta/Elev= 30
  3359.3  420.81  3672.8  412.71  3972.4  407.71  4150.8  404.42  4541.5  399.79
  4716.1  394.29  4898.6  390.27  4951.2  389.86  4952.2  389.36  4997.1  389.86
    5075  390.17  5202.9  392.67  5235.8  393.39  5391.1  396.42  5437.9  399.72
  5443.3  399.21  5506.1  401.61  5628.2  403.44    5648  403.01  5713.5  404.41
  5967.3  408.13  6089.7  411.11  6235.5  416.56  6323.4  418.16  6386.7  419.95
    6439  420.25    6538  424.78  6613.6  427.05  6660.4  430.07  6750.4  432.88
#Mann= 11 ,-1 , 0
  3359.3     .07       0  3972.4     .05       0  4898.6     .07       0
  4951.2     .05       0  4997.1     .07       0    5075     .05       0
  5202.9     .07       0  5235.8     .05       0  5628.2     .07       0
  5713.5     .05       0  6323.4     .07       0
Bank Sta=4951.2,4997.1
XS Rating Curve= 0 ,0
Exp/Cntr=0.3,0.1

Type RM Length L Ch R = 1 ,383950  ,565,565,565
BEGIN DESCRIPTION:
SANDIES CREEK 88.0
END DESCRIPTION:
XS GIS Cut Line= 3
      2353075.01     13699075.03        2352575.       13697525.
      2351724.98     13696074.97
#Sta/Elev= 30
  3371.3  418.56  3579.6  413.15  3778.3  409.44  4070.9  403.75  4332.5  399.96
  4690.3  393.88  4926.1  390.63  4987.3   389.9  4988.3   389.4  5032.8   389.4
  5033.8   389.9  5183.5  390.85  5298.1  392.98  5306.8  393.15  5320.9  395.79
  5328.3  396.17    5344  398.65  5371.3  399.24  5614.3  402.57  5861.9  407.77
  6000.6   409.7  6139.4   412.8    6241  416.52  6309.5  417.97  6379.7     421
    6497  423.73    6587  426.57  6592.8  426.34    6630  427.86  6680.8  428.72
#Mann= 8 ,-1 , 0
  3371.3     .07       0  3778.3     .05       0  4926.1     .07       0
  4987.3    .035       0  5033.8     .07       0  5183.5     .05       0
  5298.1     .07       0  5320.9     .05       0
Bank Sta=4987.3,5033.8
XS Rating Curve= 0 ,0
Exp/Cntr=0.3,0.1

Type RM Length L Ch R = 1 ,383385  ,570,570,570
BEGIN DESCRIPTION:
SANDIES CREEK 89.0
END DESCRIPTION:
XS GIS Cut Line= 3
        2353175.     13699024.96        2353125.       13697475.
      2353774.99     13696175.01
#Sta/Elev= 30
  3454.2  417.07  3455.4  417.07  3819.3  410.31  4854.9  391.32  4968.9  389.81
  4969.9  389.31  5015.5  389.81  5223.6  391.15  5259.3  392.43  5264.9  391.65
  5273.3  392.65    5318  392.39  5393.5  394.66  5460.6  394.97  5573.7  393.46
  5779.2  398.05  5824.5  399.72  5868.6  401.44    5909  401.46  5974.9  401.98
  6002.8  401.17  6019.6  401.47  6025.2  402.43  6041.9  402.85  6047.5   402.2
  6114.6  404.13  6324.2  414.37  6346.6  416.48  6360.6  416.59  6458.4   421.5
#Mann= 9 ,-1 , 0
  3454.2    .035       0  3455.4     .07       0  3819.3     .05       0
  4968.9     .05       0  5015.5     .05       0  5223.6    .035       0
  5573.7     .07       0  5824.5     .05       0    5909     .07       0
Bank Sta=4968.9,5015.5
XS Rating Curve= 0 ,0
Exp/Cntr=0.3,0.1

Type RM Length L Ch R = 1 ,382815  ,535,535,535
BEGIN DESCRIPTION:
SANDIES CREEK 90.0
END DESCRIPTION:
XS GIS Cut Line= 3
        2353225.     13699274.99        2353625.       13697275.
      2353825.01     13696124.96
#Sta/Elev= 30
  2960.4  420.67  3052.2   419.8  3234.7  415.74  3449.9     411  3612.7  408.51
  4164.4  400.07    4756   392.4  4764.3   392.3  4986.9  389.66  4987.9  389.16
  5033.5  389.66  5040.6  392.14  5081.2  393.81  5101.5  393.75  5162.4  390.99
  5192.9   391.3  5217.2  393.22  5233.5  394.89  5274.1  396.29    5367  395.48
  5426.3   395.7  5574.9  398.78  5608.4  400.26  5639.5  399.87    5668  400.71
  5673.1  399.96  5725.2  401.76  6020.7  419.82  6086.1  422.85  6167.3  424.61
#Mann= 12 ,-1 , 0
  2960.4    .035       0  3234.7     .07       0  3612.7     .05       0
  4164.4     .07       0    4756     .05       0  4764.3     .07       0
  4986.9     .05       0  5033.5     .07       0  5217.2     .12       0
    5367     .07       0  5574.9     .12       0  5725.2     .07       0
Bank Sta=4986.9,5033.5
XS Rating Curve= 0 ,0
Exp/Cntr=0.3,0.1

Type RM Length L Ch R = 1 ,382280  ,545,545,545
BEGIN DESCRIPTION:
SANDIES CREEK 91.0
END DESCRIPTION:
XS GIS Cut Line= 3
      2353325.01     13699174.98        2354125.       13697175.
      2354424.99     13696375.04
#Sta/Elev= 30
  2839.9  418.78    3202  410.93  3448.8  407.33  3669.5  404.08  4075.6  399.06
  4685.6  391.54  4918.5  389.92  4949.5  390.79  4961.3  384.46  4962.3  383.96
  5008.1  384.46  5047.3  386.28    5058  387.62  5064.3  389.59  5100.7  388.65
  5119.4  392.28  5132.8  392.78  5235.1  395.32  5240.5  394.36  5282.3  394.59
  5314.3  391.76  5335.7  391.48  5375.8  392.13  5389.1  394.08  5426.6  395.34
    5552  396.49  5607.2  398.79    5704   405.4    5778  410.32  5848.3  416.43
#Mann= 8 ,-1 , 0
  2839.9     .07       0  3448.8     .05       0  3669.5    .035       0
  4075.6     .07       0  4961.3     .05       0  5008.1     .07       0
  5426.6     .12       0    5704     .07       0
Bank Sta=4961.3,5008.1
XS Rating Curve= 0 ,0
Exp/Cntr=0.3,0.1

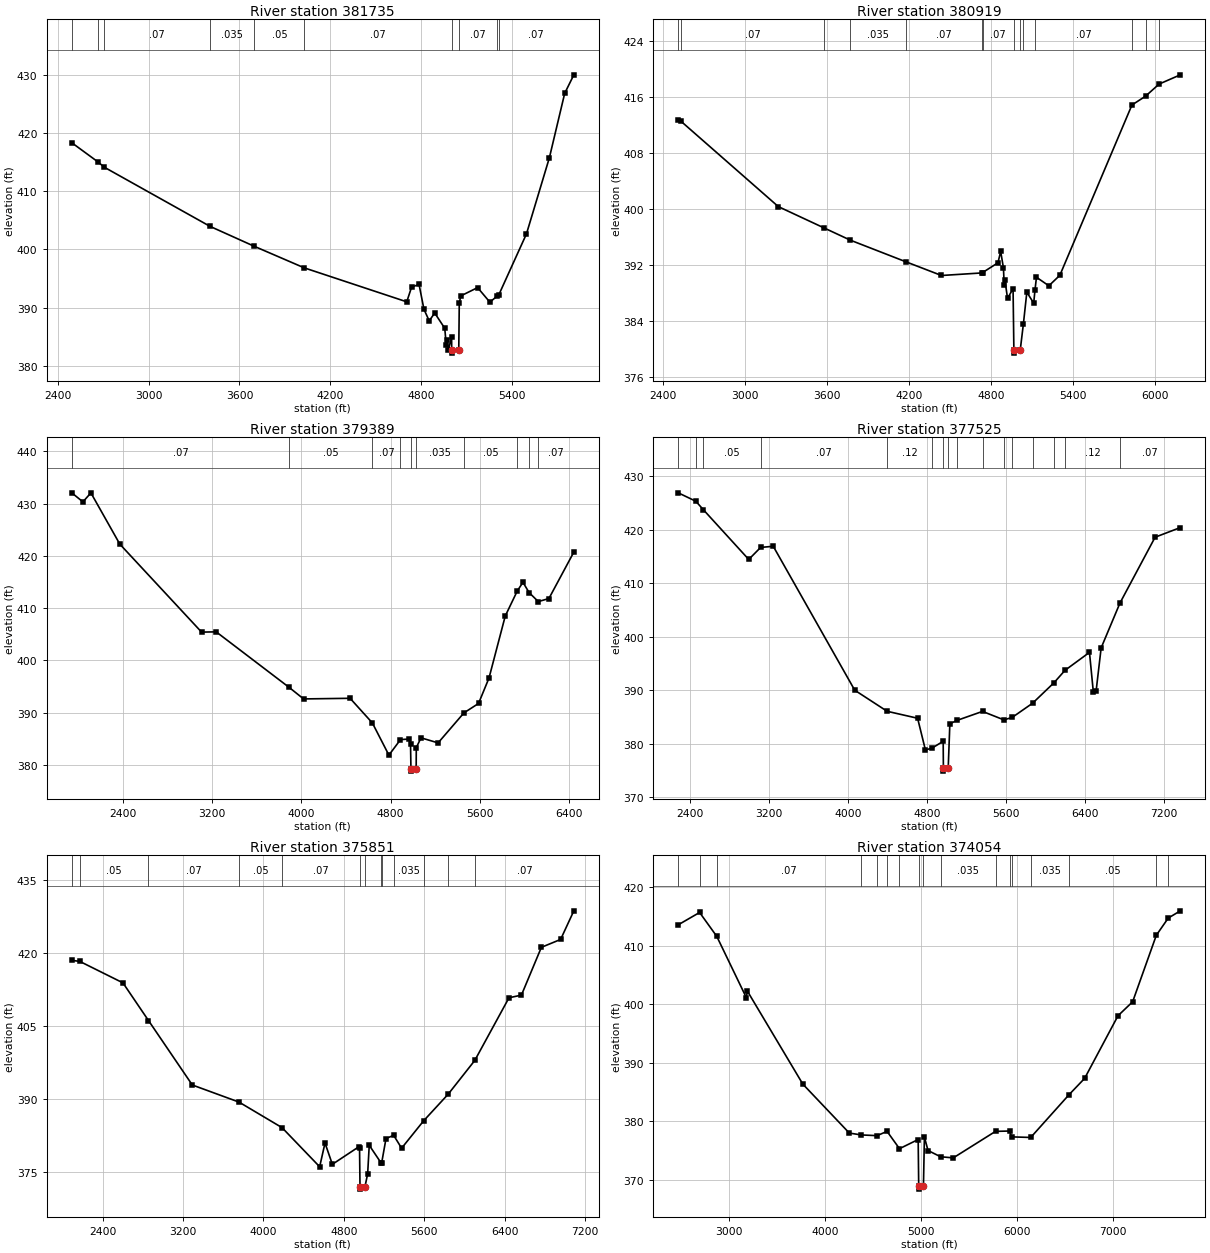
Type RM Length L Ch R = 1 ,381735  ,816,816,816
BEGIN DESCRIPTION:
SANDIES CREEK 92.0
END DESCRIPTION:
XS GIS Cut Line= 3
      2353424.99     13699225.02        2354625.       13697025.
      2354525.01     13696225.04
#Sta/Elev= 30
  2493.6  418.32  2666.7  415.02  2708.4  414.11  3406.3  403.95    3698  400.53
  4027.6  396.83  4703.5     391  4735.3  393.52  4784.6  393.99  4816.9  389.72
  4851.5  387.74  4888.1  389.07  4954.1  386.46    4964  383.66  4969.7  384.39
  4976.8  382.69  4999.6  384.93  4999.8  382.69  5000.8  382.19  5046.6  382.69
    5050  390.79  5060.1  392.02  5170.9  393.44  5251.6  390.95  5299.6  391.97
  5310.5  392.18  5493.4  402.68  5644.6  415.76  5745.4   426.8  5805.8  429.98
#Mann= 10 ,-1 , 0
  2493.6     .07       0  2666.7    .035       0  2708.4     .07       0
  3406.3    .035       0    3698     .05       0  4027.6     .07       0
  4999.8     .05       0  5046.6     .07       0  5299.6     .12       0
  5310.5     .07       0
Bank Sta=4999.8,5046.6
XS Rating Curve= 0 ,0
Exp/Cntr=0.3,0.1

Type RM Length L Ch R = 1 ,380919  ,1530,1530,1530
BEGIN DESCRIPTION:
C20479
END DESCRIPTION:
XS GIS Cut Line= 3
      2355394.41     13699505.59      2355483.58     13697722.29
      2355282.95     13695849.84
#Sta/Elev= 30
  2513.6  412.77  2530.3  412.62  3245.1  400.38  3582.2  397.31  3771.5  395.59
  4177.8   392.5  4437.2  390.55  4735.6  390.92  4736.9  390.96  4849.6  392.36
  4869.7  393.98  4889.8  391.64  4895.4  389.26  4900.4  389.92    4920  387.27
  4960.2  388.69  4966.1  379.97  4967.1  379.47    5013  379.97  5035.9  383.68
  5060.8  388.17    5111   386.6  5120.2  388.44  5131.2   390.3  5221.7  389.08
  5302.1  390.58  5828.7  414.88    5928  416.14  6027.3  417.87  6182.3  419.19
#Mann= 14 ,-1 , 0
  2513.6    .035       0  2530.3     .07       0  3582.2     .05       0
  3771.5    .035       0  4177.8     .07       0  4735.6    .035       0
  4736.9     .07       0  4966.1     .05       0    5013     .07       0
  5035.9     .12       0  5120.2     .07       0  5828.7    .035       0
    5928     .05       0  6027.3     .07       0
Bank Sta=4966.1,5013
XS Rating Curve= 0 ,0
Exp/Cntr=0.3,0.1

Type RM Length L Ch R = 1 ,379389  ,1864,1864,1864
BEGIN DESCRIPTION:
SANDIES CREEK 95.0
END DESCRIPTION:
XS GIS Cut Line= 3
        2358575.     13698975.01      2357133.09     13696919.82
      2355461.31     13695849.88
#Sta/Elev= 30
  1945.7  432.05  2045.5  430.32    2117  432.04  2375.8  422.24  3107.9  405.41
  3238.7  405.46  3892.8  394.82  4021.3  392.63  4437.7  392.75    4637  388.04
  4785.2  381.88    4889  384.85  4964.5  384.96  4978.8  384.02  4982.5  379.32
  4983.5  378.82  5029.4  379.32  5030.4  383.32  5072.7  385.19  5225.7  384.22
  5456.9  389.96  5587.7  391.76  5681.6  396.64    5827  408.49  5935.5  413.32
  5985.6  414.93  6040.5  412.97  6122.7  411.25  6217.7  411.83  6441.1  420.72
#Mann= 10 ,-1 , 0
  1945.7     .07       0  3892.8     .05       0    4637     .07       0
    4889    .035       0  4982.5    .035       0  5029.4    .035       0
  5456.9     .05       0  5935.5     .07       0  6040.5     .05       0
  6122.7     .07       0
Bank Sta=4982.5,5029.4
XS Rating Curve= 0 ,0
Exp/Cntr=0.3,0.1

Type RM Length L Ch R = 1 ,377525  ,1674,1674,1674
BEGIN DESCRIPTION:
C20478
END DESCRIPTION:
XS GIS Cut Line= 3
       2359206.1     13696117.34       2357846.4     13695560.08
      2354591.97     13693977.45
#Sta/Elev= 30
  2281.9  426.89  2459.8  425.32  2535.1  423.76  2996.4  414.43    3117  416.68
  3244.9  416.89  4070.8  389.97  4399.1  386.03  4707.8  384.73  4787.1  378.78
  4857.9  379.19    4967  380.42  4969.1  375.34  4970.1  374.84  5017.9  375.34
  5034.6   383.7  5108.9  384.34  5365.5  386.01  5581.8  384.43  5665.1  384.87
    5873  387.54    6091  391.39  6201.4  393.69  6449.6  397.05  6488.4  389.69
  6517.3  389.89  6567.9  397.89  6758.4  406.27  7114.7  418.59  7370.2  420.39
#Mann= 16 ,-1 , 0
  2281.9     .05       0  2459.8     .07       0  2535.1     .05       0
    3117     .07       0  4399.1     .12       0  4857.9    .035       0
  4969.1     .05       0  5017.9    .035       0  5108.9     .05       0
  5365.5    .035       0  5581.8     .05       0  5665.1     .07       0
    5873     .05       0    6091     .07       0  6201.4     .12       0
  6758.4     .07       0
Bank Sta=4969.1,5017.9
XS Rating Curve= 0 ,0
Exp/Cntr=0.3,0.1

Type RM Length L Ch R = 1 ,375851  ,1797,1797,1797
BEGIN DESCRIPTION:
C20477
END DESCRIPTION:
XS GIS Cut Line= 3
      2359228.41     13695136.55      2357534.33     13693999.73
      2354970.87     13692528.52
#Sta/Elev= 30
  2092.4  418.48  2172.2  418.26  2601.5  413.86  2855.7  406.13  3291.7   392.9
  3756.7  389.39  4184.5  384.15    4559  376.12  4612.2     381  4685.2  376.62
  4950.2  380.24  4955.9   379.9  4960.4  372.03  4961.4  371.53  5009.7  372.03
  5036.5  374.66  5052.3  380.53  5171.7  376.86  5175.4  376.85  5219.1  381.91
  5295.3  382.57  5374.4  379.93    5594  385.56  5836.8  390.99  6102.6  397.94
  6442.9   410.8  6566.6  411.34  6765.1  421.15  6956.6  422.77  7088.2  428.64
#Mann= 13 ,-1 , 0
  2092.4    .035       0  2172.2     .05       0  2855.7     .07       0
  3756.7     .05       0  4184.5     .07       0  4960.4     .05       0
  5009.7     .07       0  5171.7    .035       0  5175.4     .07       0
  5295.3    .035       0    5594     .07       0  5836.8    .035       0
  6102.6     .07       0
Bank Sta=4960.4,5009.7
XS Rating Curve= 0 ,0
Exp/Cntr=0.3,0.1

Type RM Length L Ch R = 1 ,374054  ,1906,1906,1906
BEGIN DESCRIPTION:
C20476
END DESCRIPTION:
XS GIS Cut Line= 4
       2359339.9     13694869.09      2358381.38     13693219.55
      2357957.85     13692461.66      2355795.67     13691280.26
#Sta/Elev= 30
    2467  413.55    2690  415.66    2869  411.58  3177.2  401.12    3189  402.21
  3767.1  386.33  4252.6  377.96  4377.7  377.64  4541.8  377.52  4646.4  378.25
  4776.2  375.29  4971.1  376.86  4976.7  368.88  4977.7  368.38  5026.1  368.88
  5036.2  377.28  5073.9  374.98  5205.3  373.91  5337.4  373.72  5778.3  378.25
  5924.8  378.31  5946.3  377.31  6145.6  377.21  6545.7  384.52  6708.5  387.31
  7056.7  398.01  7209.4   400.4  7456.7  411.77  7580.9   414.7  7706.9  415.94
#Mann= 17 ,-1 , 0
    2467     .07       0    2690     .05       0    2869     .07       0
  4377.7    .035       0  4541.8     .07       0  4646.4    .035       0
  4776.2     .07       0  4976.7     .05       0  5026.1     .07       0
  5205.3    .035       0  5778.3     .12       0  5924.8     .07       0
  5946.3     .12       0  6145.6    .035       0  6545.7     .05       0
  7456.7    .035       0  7580.9     .05       0
Bank Sta=4976.7,5026.1
XS Rating Curve= 0 ,0
Exp/Cntr=0.3,0.1

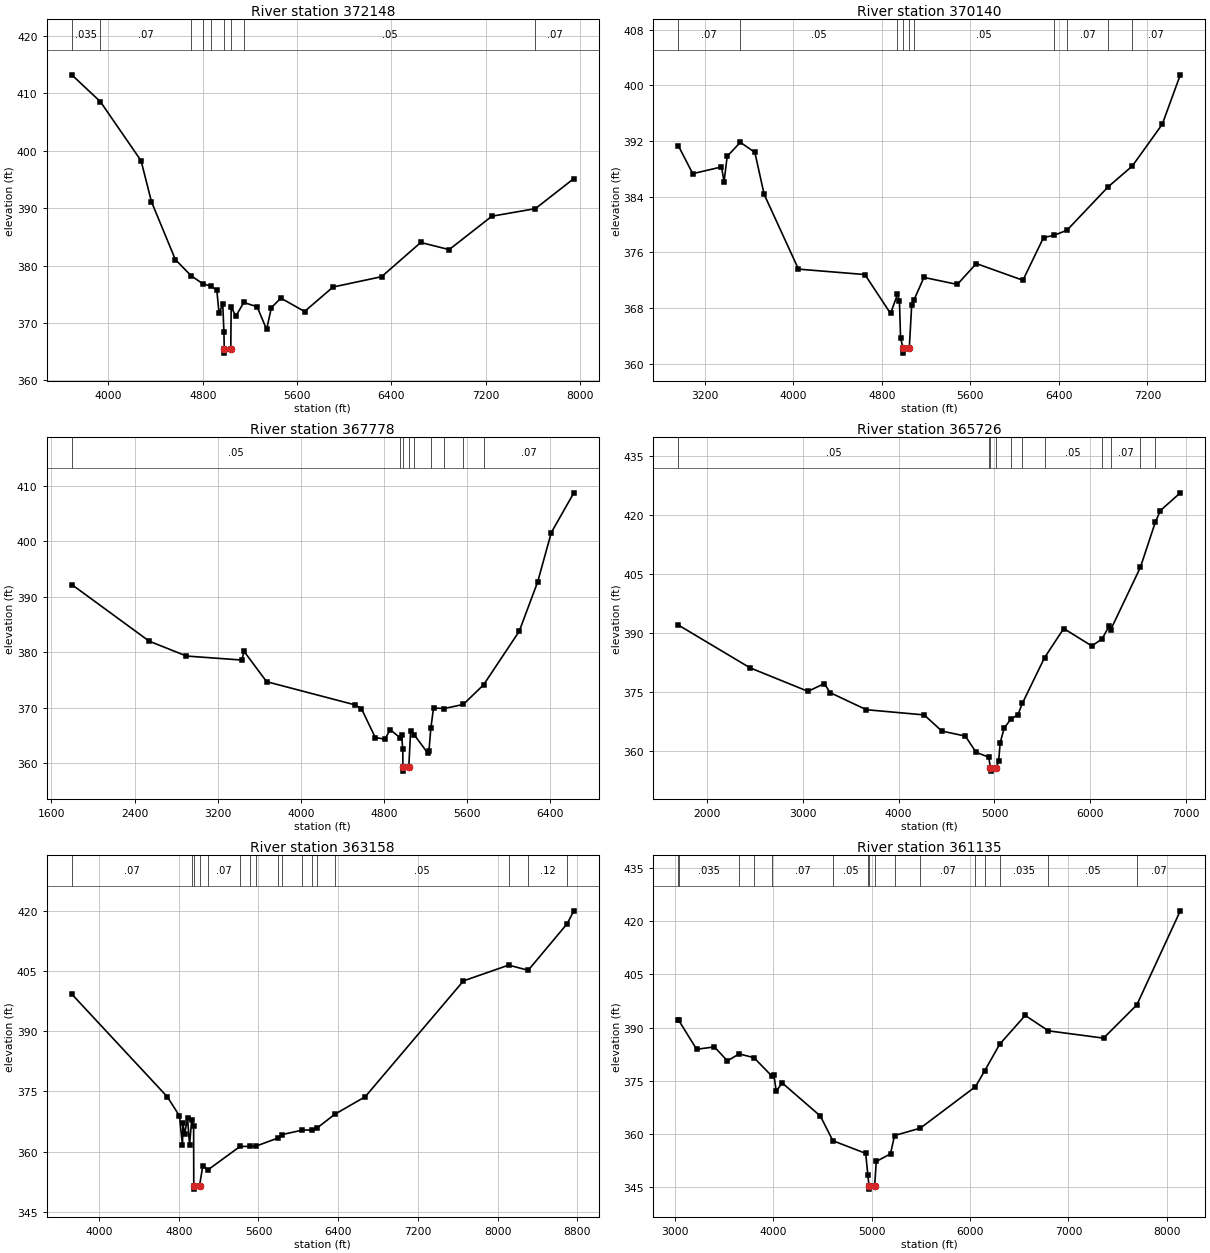
Type RM Length L Ch R = 1 ,372148  ,2008,2008,2008
BEGIN DESCRIPTION:
C20475
END DESCRIPTION:
XS GIS Cut Line= 2
      2359741.12      13694378.7       2359295.3      13690143.4
#Sta/Elev= 30
  3689.1  413.25  3931.9  408.57    4277  398.27    4365  391.14  4567.6  381.06
  4700.3  378.26  4799.6  376.85  4871.3  376.39  4919.6  375.71  4938.1  371.73
  4969.8  373.26  4979.9  368.35  4982.2  365.45  4983.4  364.75  5037.9  365.45
  5041.2   372.8  5080.4   371.2  5148.5  373.58  5261.4  372.83  5341.9  368.87
  5382.1  372.68  5462.5  374.34  5663.7     372    5905  376.27  6317.2  378.07
  6649.1  384.03  6890.4  382.79  7252.4  388.61  7621.7  389.93  7947.8  395.17
#Mann= 9 ,-1 , 0
  3689.1    .035       0  3931.9     .07       0  4700.3     .12       0
  4799.6     .07       0  4871.3     .12       0  4982.2     .05       0
  5037.9     .12       0  5148.5     .05       0  7621.7     .07       0
Bank Sta=4982.2,5037.9
XS Rating Curve= 0 ,0
Exp/Cntr=0.3,0.1

Type RM Length L Ch R = 1 ,370140  ,2362,2362,2362
BEGIN DESCRIPTION:
C20474
END DESCRIPTION:
XS GIS Cut Line= 3
       2360744.5     13694399.96      2361167.73     13692952.06
      2360833.37     13689942.77
#Sta/Elev= 30
  2960.9  391.36  3091.9  387.32  3351.6  388.28  3375.1  386.19  3403.3  389.81
  3521.8  391.82  3653.1  390.38    3737  384.35  4047.1   373.6  4647.5  372.82
    4879  367.23  4941.9  369.96  4959.4  369.08  4969.5  363.75  4992.5  362.23
  4993.7  361.53  5048.4  362.23  5070.1  368.41  5091.5   369.2  5180.8  372.41
  5482.6   371.4  5653.7   374.4    6075     372  6261.2  378.13  6358.2  378.47
  6473.1  379.19  6844.1  385.41  7062.7   388.4    7334  394.41  7497.2  401.52
#Mann= 10 ,-1 , 0
  2960.9     .07       0  3521.8     .05       0  4941.9     .07       0
  4992.5     .05       0  5048.4     .07       0  5091.5     .05       0
  6358.2    .035       0  6473.1     .07       0  6844.1     .12       0
  7062.7     .07       0
Bank Sta=4992.5,5048.4
XS Rating Curve= 0 ,0
Exp/Cntr=0.3,0.1

Type RM Length L Ch R = 1 ,367778  ,2052,2052,2052
BEGIN DESCRIPTION:
C20473
END DESCRIPTION:
XS GIS Cut Line= 3
      2363574.91     13694110.63      2362817.25     13692327.92
      2361613.55      13689697.6
#Sta/Elev= 30
  1796.2  392.17  2541.2  381.96  2899.8  379.28  3432.2  378.56  3453.9  380.11
  3670.4  374.66  4521.2  370.48  4583.2  369.78  4716.3  364.57  4808.4  364.32
  4859.9  366.01  4951.9  364.59  4968.2     365  4980.5  362.51  4981.5  359.34
  4982.8  358.54  5038.3  359.34  5056.1  365.85  5088.6  365.14  5221.6  361.76
  5232.1  362.16  5250.1  366.25  5276.1  369.92  5379.3  369.82  5562.3  370.56
  5757.8   374.1  6100.6  383.75  6278.1  392.66  6408.8  401.53  6625.9   408.7
#Mann= 9 ,-1 , 0
  1796.2     .05       0  4951.9     .07       0  4981.5     .05       0
  5038.3     .07       0  5088.6     .05       0  5250.1    .035       0
  5379.3     .07       0  5562.3     .05       0  5757.8     .07       0
Bank Sta=4981.5,5038.3
XS Rating Curve= 0 ,0
Exp/Cntr=0.3,0.1

Type RM Length L Ch R = 1 ,365726  ,2568,2568,2568
BEGIN DESCRIPTION:
C20472
END DESCRIPTION:
XS GIS Cut Line= 3
      2363686.52     13694110.55      2363508.27     13692483.95
      2364266.15     13688962.01
#Sta/Elev= 30
  1700.1  392.01  2450.1  381.09  3053.7  375.11  3224.2  377.08  3285.1  374.78
  3662.7  370.43  4266.2  369.11  4450.3     365  4695.8  363.71  4808.3  359.58
  4939.9  358.35  4958.2  355.59  4959.5  354.79  5015.3  355.59  5043.6  357.34
  5058.9  361.96  5101.7  365.83  5172.8  368.07  5244.6  369.15  5290.6  372.05
  5522.2  383.68  5722.6  391.11  6015.3  386.67  6121.8  388.44  6195.5  391.69
  6212.2  390.78  6522.2  406.68  6677.9  418.17  6731.4  421.16    6939  425.67
#Mann= 11 ,-1 , 0
  1700.1     .05       0  4939.9     .07       0  4958.2     .05       0
  5015.3     .07       0  5172.8    .035       0  5290.6     .07       0
  5522.2     .05       0  6121.8    .035       0  6212.2     .07       0
  6522.2     .12       0  6677.9     .07       0
Bank Sta=4958.2,5015.3
XS Rating Curve= 0 ,0
Exp/Cntr=0.3,0.1

Type RM Length L Ch R = 1 ,363158  ,2023,2023,2023
BEGIN DESCRIPTION:
C20471
END DESCRIPTION:
XS GIS Cut Line= 2
      2365692.58      13693731.1        2364868.     13688761.34
#Sta/Elev= 30
  3726.8   399.2  4685.8  373.61  4807.5  368.86  4837.5  361.54  4842.6  367.01
  4858.2  364.25  4888.6  368.24  4908.8   361.7    4930  367.79  4949.4   366.3
  4950.9  351.43  4952.2  350.63  5008.5  351.43  5040.6   356.3  5094.6  355.45
  5416.3  361.28  5516.6  361.25    5575  361.33  5798.7  363.39  5840.4  364.23
  6040.8  365.33  6141.5  365.36  6191.8  365.92  6366.3  369.28  6671.3  373.64
  7656.8  402.49  8110.7  406.42  8306.6  405.13  8697.7  416.74  8764.5  419.94
#Mann= 17 ,-1 , 0
  3726.8     .07       0    4930      .1       0  4950.9     .05       0
  5008.5      .1       0  5094.6     .07       0  5416.3    .035       0
  5516.6     .07       0    5575     .05       0  5798.7     .07       0
  5840.4     .05       0  6040.8     .07       0  6141.5     .05       0
  6191.8     .07       0  6366.3     .05       0  8110.7     .07       0
  8306.6     .12       0  8697.7     .07       0
Bank Sta=4950.9,5008.5
XS Rating Curve= 0 ,0
Exp/Cntr=0.3,0.1

Type RM Length L Ch R = 1 ,361135  ,503,503,503
BEGIN DESCRIPTION:
C20470
END DESCRIPTION:
XS GIS Cut Line= 3
      2367498.33     13692907.49      2366785.02     13691726.07
      2365402.99     13688270.99
#Sta/Elev= 30
  3034.8  392.07  3039.2  392.07  3221.9  383.89  3402.4  384.55  3534.4  380.62
    3653  382.58  3803.7  381.53  3988.4  376.26  4007.3  376.61  4030.6  371.98
    4089  374.45  4478.7  365.06  4605.5   358.1  4939.2  354.52  4961.9   348.3
  4972.7  345.34  4974.1  344.44  5030.5  345.34  5046.9  352.24  5191.5  354.39
  5232.4  359.56  5493.9  361.63  6054.7  373.34    6149  377.85  6301.7  385.34
  6560.1  393.44  6795.8  389.09  7356.3  387.03  7694.1   396.4  8136.1  422.94
#Mann= 16 ,-1 , 0
  3034.8     .05       0  3039.2    .035       0    3653     .07       0
  3803.7    .035       0  3988.4     .07       0  4605.5     .05       0
  4961.9     .07       0  4972.7     .05       0  5030.5     .07       0
  5232.4     .12       0  5493.9     .07       0  6054.7    .035       0
    6149     .07       0  6301.7    .035       0  6795.8     .05       0
  7694.1     .07       0
Bank Sta=4972.7,5030.5
XS Rating Curve= 0 ,0
Exp/Cntr=0.3,0.1

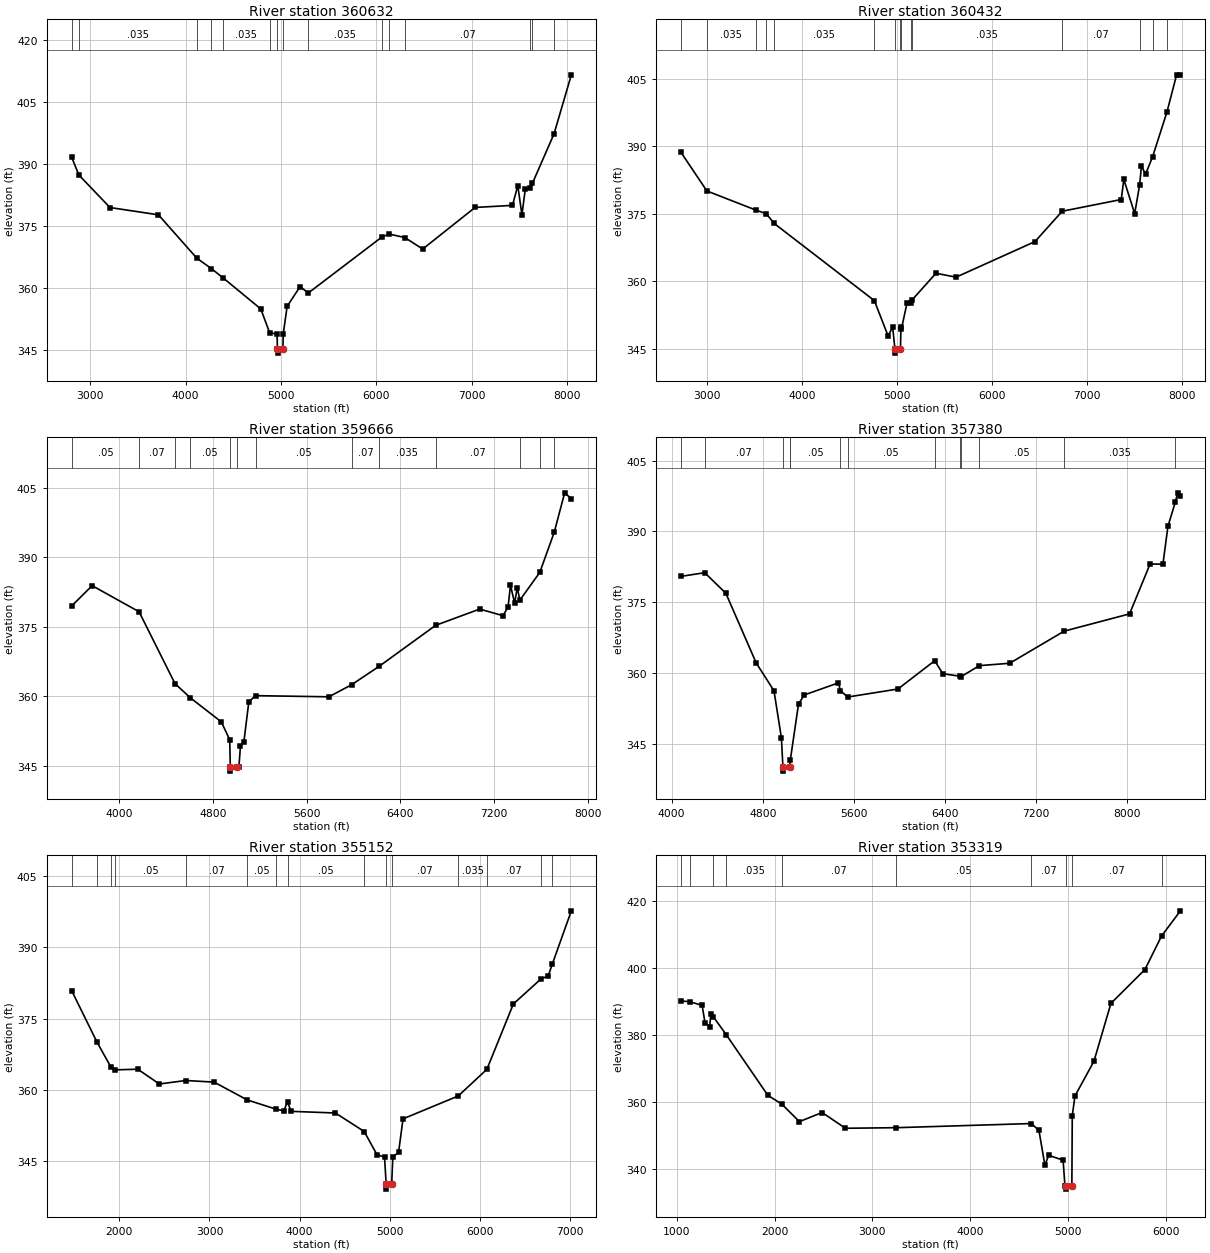
Type RM Length L Ch R = 1 ,360632  ,200,200,200
BEGIN DESCRIPTION:
SAND21669
END DESCRIPTION:
XS GIS Cut Line= 5
      2367520.11      13692889.7      2367006.25     13691571.88
      2366723.96      13690260.1      2366541.31     13689172.49
      2365677.87     13688093.18
#Sta/Elev= 30
  2804.3   391.6  2880.5  387.29  3206.5  379.45  3714.6  377.69    4117  367.23
  4268.8  364.73  4388.7  362.55  4788.4  354.97  4880.5  349.26  4959.3  348.91
  4962.4  345.21  4963.8  344.31  5020.2  345.21  5023.7  348.94  5064.6  355.61
  5200.9  360.38    5286  358.81  6059.9  372.36  6136.1  373.04  6298.6  372.21
  6486.8  369.43  7035.8  379.47    7428  379.97  7484.1  384.73  7527.3  377.69
  7562.5  383.83  7615.4  384.11  7637.4   385.3  7864.4  397.25  8045.6  411.48
#Mann= 15 ,-1 , 0
  2804.3     .05       0  2880.5    .035       0    4117     .07       0
  4268.8     .05       0  4388.7    .035       0  4880.5     .07       0
  4962.4     .05       0  5020.2     .07       0    5286    .035       0
  6059.9     .07       0  6136.1    .035       0  6298.6     .07       0
  7615.4     .05       0  7637.4    .035       0  7864.4     .07       0
Bank Sta=4962.4,5020.2
XS Rating Curve= 0 ,0
Exp/Cntr=0.3,0.1

Type RM Length L Ch R = 1 ,360432  ,766,766,766
BEGIN DESCRIPTION:
SAND21668
END DESCRIPTION:
XS GIS Cut Line= 5
      2367561.99     13692881.84       2367180.6     13691538.67
      2366881.71     13690193.68      2366715.66     13689255.51
       2365752.6     13688059.98
#Sta/Elev= 30
  2720.1  388.69  2995.3  380.03  3511.4  375.78  3620.7  374.98  3703.4  372.82
  4758.7  355.66  4903.3  347.83  4951.9  349.74  4975.6  344.89    4977  343.99
  5033.5  344.89    5039  349.72  5044.4  349.39  5103.5   355.2  5145.9  355.16
  5159.9   355.9  5407.8  361.74  5619.3  360.87  6450.5  368.78  6736.8  375.52
  7358.7  378.13  7385.9  382.59  7500.5  374.99  7552.8  381.44  7571.5  385.62
  7614.6  383.73    7689  387.63  7840.4  397.59    7941  405.78  7982.1  405.84
#Mann= 15 ,-1 , 0
  2720.1     .05       0  2995.3    .035       0  3511.4     .07       0
  3620.7     .05       0  3703.4    .035       0  4758.7    .063       0
  4975.6    .063       0  5033.5    .063       0  5044.4    .035       0
  5145.9     .05       0  5159.9    .035       0  6736.8     .07       0
  7552.8     .05       0    7689    .035       0  7840.4     .07       0
Bank Sta=4975.6,5033.5
XS Rating Curve= 0 ,0
Exp/Cntr=0.3,0.1

Type RM Length L Ch R = 1 ,359666  ,2286,2286,2286
BEGIN DESCRIPTION:
C20469
END DESCRIPTION:
XS GIS Cut Line= 2
       2368479.1      13691347.1      2365804.23      13688025.8
#Sta/Elev= 30
  3594.8  379.51  3769.8  383.91  4170.2  378.27  4476.6  362.75  4606.1  359.71
  4871.9  354.48  4943.9   350.6  4948.8  344.73  4950.1  343.83  5006.7  344.73
  5022.3  344.73  5035.6  349.29  5063.9  350.02  5107.1  358.83  5164.7  360.14
  5790.1  359.89  5983.4  362.49  6219.9  366.49  6701.1  375.33  7077.1  378.85
  7276.1  377.42  7319.3  379.28  7340.1     384  7375.3  380.15  7397.7  383.47
  7420.3  380.78    7590  386.77  7713.6  395.46  7802.4  403.97  7859.3  402.71
#Mann= 13 ,-1 , 0
  3594.8     .05       0  4170.2     .07       0  4476.6    .035       0
  4606.1     .05       0  4948.8     .05       0  5006.7     .05       0
  5164.7     .05       0  5983.4     .07       0  6219.9    .035       0
  6701.1     .07       0  7420.3     .05       0    7590    .035       0
  7713.6     .07       0
Bank Sta=4948.8,5006.7
XS Rating Curve= 0 ,0
Exp/Cntr=0.3,0.1

Type RM Length L Ch R = 1 ,357380  ,2228,2228,2228
BEGIN DESCRIPTION:
C20468
END DESCRIPTION:
XS GIS Cut Line= 2
      2369792.74     13689741.07      2366250.05     13687156.46
#Sta/Elev= 30
  4080.9  380.49  4291.1  381.27  4476.7  376.92  4742.4  362.21  4899.2  356.28
  4964.1  346.35  4977.6  340.19    4979  339.29  5035.6  340.19  5042.6  341.66
  5114.7  353.51  5164.9   355.4  5464.5  357.96  5482.2   356.3  5546.2  354.97
  5986.8  356.66  6309.7  362.65  6380.5  359.91    6536  359.35  6542.4  359.31
  6702.2  361.61  6967.8  362.11  7446.1  368.91  8019.8  372.56  8199.8  383.11
  8312.6  383.08  8356.6   391.1  8420.9  396.17  8442.4  398.17  8466.2   397.4
#Mann= 13 ,-1 , 0
  4080.9     .05       0  4291.1     .07       0  4977.6     .05       0
  5035.6     .07       0  5042.6     .05       0  5482.2    .035       0
  5546.2     .05       0  6309.7     .07       0    6536     .05       0
  6542.4     .07       0  6702.2     .05       0  7446.1    .035       0
  8420.9     .12       0
Bank Sta=4977.6,5035.6
XS Rating Curve= 0 ,0
Exp/Cntr=0.3,0.1

Type RM Length L Ch R = 1 ,355152  ,1833,1833,1833
BEGIN DESCRIPTION:
C20467
END DESCRIPTION:
XS GIS Cut Line= 4
      2371064.84     13690098.83      2369459.91     13687579.98
      2368880.35     13687000.41      2368389.95     13685328.59
#Sta/Elev= 30
  1469.4  380.91  1751.4  370.07  1903.6   364.9  1952.1  364.26  2203.7  364.39
  2443.2  361.29  2738.2  362.02    3051  361.68  3419.9  357.93  3740.1  355.99
  3825.4  355.64  3866.3  357.56  3904.7  355.54  4398.5  355.19  4718.1   351.3
  4859.1  346.45  4943.9  345.92  4961.9  340.19  4963.4  339.19    5023  340.19
  5035.9  345.98  5099.5  346.89    5149  353.96  5762.1  358.77  6080.2  364.37
  6374.4  378.11  6678.7  383.33  6761.2  384.01  6808.6  386.58    7018  397.68
#Mann= 15 ,-1 , 0
  1469.4     .07       0  1751.4     .05       0  1903.6    .035       0
  1952.1     .05       0  2738.2     .07       0  3419.9     .05       0
  3740.1     .07       0  3866.3     .05       0  4718.1     .07       0
  4961.9     .05       0    5023     .07       0  5762.1    .035       0
  6080.2     .07       0  6678.7    .035       0  6808.6     .07       0
Bank Sta=4961.9,5023
XS Rating Curve= 0 ,0
Exp/Cntr=0.3,0.1

Type RM Length L Ch R = 1 ,353319  ,1566,1566,1566
BEGIN DESCRIPTION:
C20464
END DESCRIPTION:
XS GIS Cut Line= 3
      2371532.97     13690009.71      2370529.87     13687535.39
      2370017.19     13685150.29
#Sta/Elev= 30
  1041.2  390.25  1131.1  390.02  1259.4  388.95  1288.9  383.79  1337.1  382.54
  1348.4  386.21  1375.6  385.48  1506.5  380.15    1932  362.04  2074.3  359.42
  2254.8  354.19  2486.6  356.91  2725.1   352.2  3247.2  352.37  4625.8  353.61
  4703.7  351.57    4765  341.11  4802.9  344.12    4951  342.66  4969.6  335.04
  4979.4  335.01  4980.9  334.01  5040.5  335.01  5044.6  355.91  5071.9  361.84
  5266.2  372.21  5440.1  389.53  5787.9  399.64  5957.7  409.66  6150.7  417.18
#Mann= 10 ,-1 , 0
  1041.2     .07       0  1131.1    .035       0  1375.6     .07       0
  1506.5    .035       0  2074.3     .07       0  3247.2     .05       0
  4625.8     .07       0  4979.4     .05       0  5040.5     .07       0
  5957.7    .035       0
Bank Sta=4979.4,5040.5
XS Rating Curve= 0 ,0
Exp/Cntr=0.3,0.1

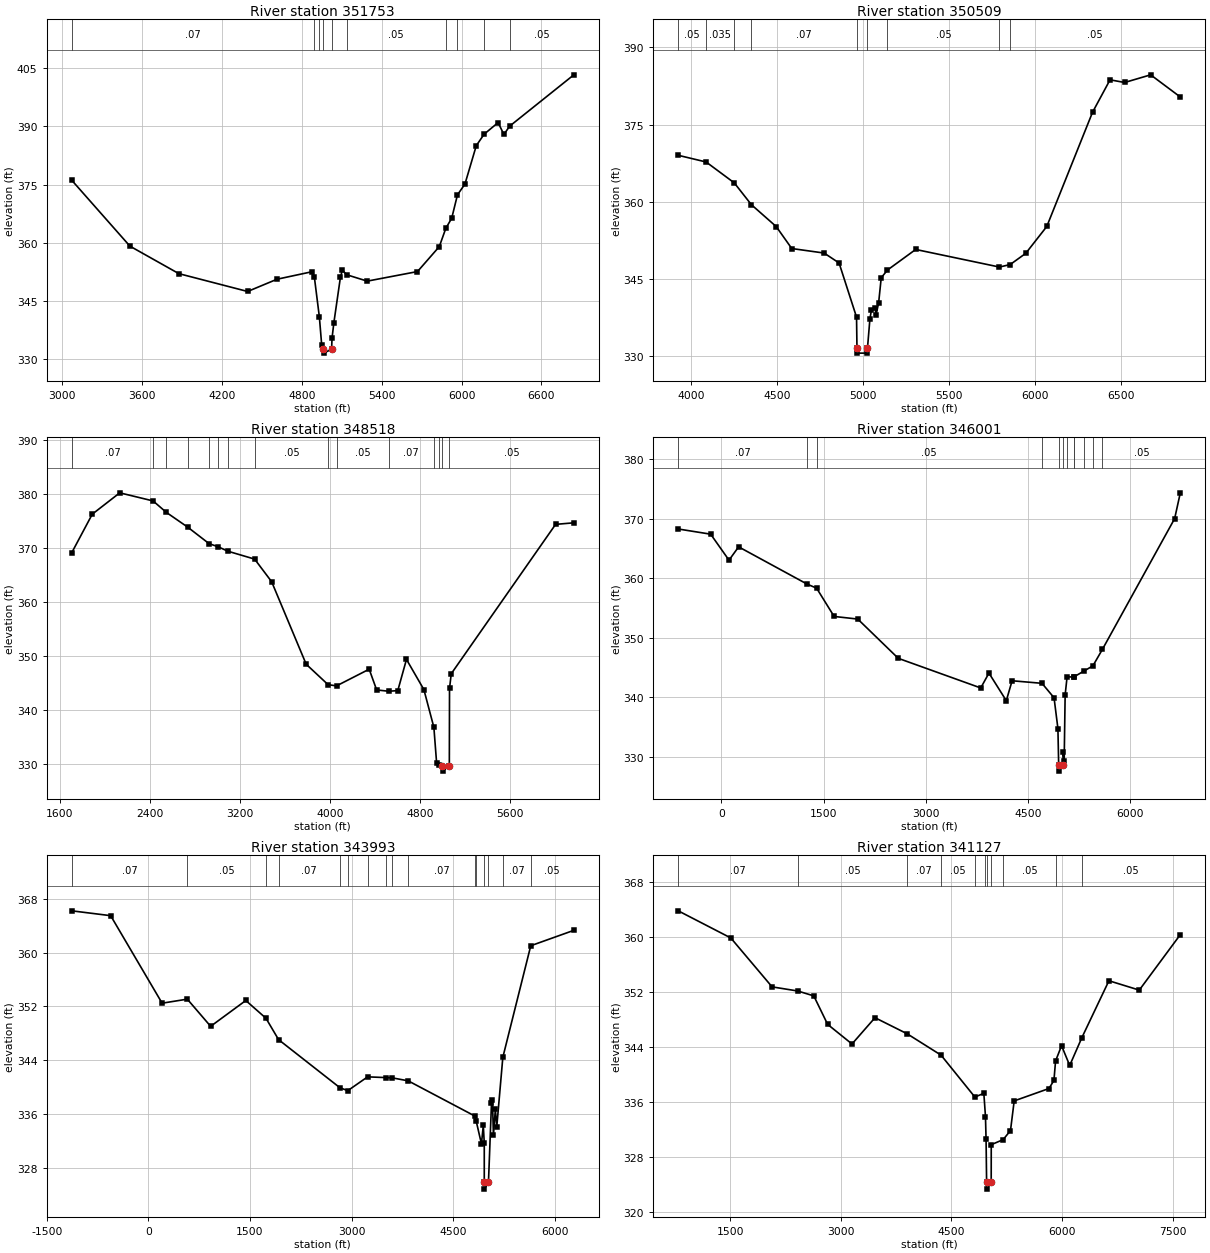
Type RM Length L Ch R = 1 ,351753  ,1244,1244,1244
BEGIN DESCRIPTION:
C20465
END DESCRIPTION:
XS GIS Cut Line= 3
      2372758.96     13687758.31      2371822.74      13686799.8
      2370329.24     13684882.77
#Sta/Elev= 30
  3073.5  376.12  3510.1  359.12  3877.7  352.02  4393.9  347.42  4614.5  350.58
  4877.8  352.52    4895  351.16  4932.7  340.84  4950.2  333.56  4963.1  332.51
  4964.6  331.51  5024.3  332.51  5027.9  335.41  5041.5  339.34  5091.3  351.22
  5105.8  352.92  5136.5  351.75  5292.1  350.09  5669.4  352.56  5833.2     359
  5882.4  363.74  5926.3  366.31  5969.6  372.36  6025.9  375.15  6110.9  385.05
  6169.6     388  6274.7  391.01  6318.1  387.94  6362.1   390.1  6843.5  403.33
#Mann= 10 ,-1 , 0
  3073.5     .07       0    4895     .12       0  4932.7     .07       0
  4963.1     .05       0  5024.3     .07       0  5136.5     .05       0
  5882.4     .07       0  5969.6     .05       0  6169.6     .07       0
  6362.1     .05       0
Bank Sta=4963.1,5024.3
XS Rating Curve= 0 ,0
Exp/Cntr=0.3,0.1

Type RM Length L Ch R = 1 ,350509  ,1991,1991,1991
BEGIN DESCRIPTION:
C20466
END DESCRIPTION:
XS GIS Cut Line= 3
      2373026.11     13685930.24      2372469.17      13685573.8
      2370596.78     13684303.25
#Sta/Elev= 30
    3924  369.01  4086.4  367.71  4250.3  363.65  4350.2   359.4  4494.4  355.16
  4585.2  350.88  4773.8     350  4860.7  348.07  4962.4  337.54  4964.9  331.54
  4966.4  330.54  5024.7  330.54  5026.2  331.54  5040.3   337.2  5049.3  338.94
  5070.2  339.27  5076.3  337.97  5091.2  340.36  5106.2   345.2  5142.6   346.7
  5306.9   350.7  5794.5  347.28  5856.9  347.76  5947.7  349.94  6070.4  355.17
  6336.9  377.39  6438.7  383.69  6523.9  383.17  6675.3  384.66    6848  380.35
#Mann= 9 ,-1 , 0
    3924     .05       0  4086.4    .035       0  4250.3     .05       0
  4350.2     .07       0  4964.9     .05       0  5026.2     .07       0
  5142.6     .05       0  5794.5     .07       0  5856.9     .05       0
Bank Sta=4964.9,5026.2
XS Rating Curve= 0 ,0
Exp/Cntr=0.3,0.1

Type RM Length L Ch R = 1 ,348518  ,2517,2517,2517
BEGIN DESCRIPTION:
C20463
END DESCRIPTION:
XS GIS Cut Line= 3
       2374497.6     13685395.45      2373004.15     13684347.81
      2370619.07     13683233.28
#Sta/Elev= 30
  1708.6  369.21  1890.6  376.34  2134.6  380.29  2430.3  378.79  2548.2  376.67
  2738.2  373.93  2927.7  370.88  3008.5   370.3  3094.5  369.48  3331.9  368.02
    3483  363.83  3789.4  348.56  3983.7  344.78  4058.7  344.55  4348.7  347.64
    4415   343.8  4520.7  343.56  4602.6  343.67  4679.7  349.45  4834.4  343.86
    4923  336.87  4947.6   330.2  4965.2  329.94  4998.8  329.77  5000.3  328.77
  5060.2  329.77  5061.9  344.07  5077.2   346.8  6003.4  374.45  6165.5  374.74
#Mann= 15 ,-1 , 0
  1708.6     .07       0  2430.3    .035       0  2548.2     .07       0
  2738.2     .05       0  2927.7    .035       0  3008.5     .05       0
  3094.5    .035       0  3331.9     .05       0  3983.7     .07       0
  4058.7     .05       0  4520.7     .07       0    4923     .12       0
  4965.2     .07       0  4998.8     .05       0  5060.2     .05       0
Bank Sta=4998.8,5060.2
XS Rating Curve= 0 ,0
Exp/Cntr=0.3,0.1

Type RM Length L Ch R = 1 ,346001  ,2008,2008,2008
BEGIN DESCRIPTION:
C20462
END DESCRIPTION:
XS GIS Cut Line= 3
      2375277.81     13685484.63      2371443.79      13681695.2
      2370084.05     13680268.59
#Sta/Elev= 30
  -630.4   368.3  -154.9  367.43   113.8  363.06   255.2   365.3  1263.5  359.01
    1398  358.36  1655.3   353.6  2001.8  353.16  2595.8  346.56  3804.9  341.58
  3925.2  344.08  4179.8  339.44  4264.6  342.79  4703.1  342.36  4879.9  339.93
  4936.5  334.76  4947.7   328.6  4949.2   327.6  5009.4   328.6  5014.2  330.74
  5028.3  329.34  5042.5  340.41  5071.2  343.47  5165.3   343.4  5174.2  343.46
  5314.8   344.4  5449.5   345.3  5589.5  348.08  6648.1  370.05  6731.1  374.38
#Mann= 12 ,-1 , 0
  -630.4     .07       0  1263.5    .035       0    1398     .05       0
  4703.1     .07       0  4947.7     .05       0  5009.4     .07       0
  5071.2    .035       0  5165.3     .07       0  5174.2    .035       0
  5314.8     .07       0  5449.5    .035       0  5589.5     .05       0
Bank Sta=4947.7,5009.4
XS Rating Curve= 0 ,0
Exp/Cntr=0.3,0.1

Type RM Length L Ch R = 1 ,343993  ,2866,2866,2866
BEGIN DESCRIPTION:
C20461
END DESCRIPTION:
XS GIS Cut Line= 3
      2375410.78     13685282.68      2372536.04     13680335.46
      2371443.79     13679042.59
#Sta/Elev= 30
 -1131.9  366.22  -557.6   365.5   202.2  352.49   574.2  353.09     919  349.05
    1438  352.89  1735.8  350.25  1922.3  347.07  2828.4  339.92  2944.2  339.49
    3237  341.54  3508.6  341.43  3600.9  341.39  3835.6  340.95  4819.2  335.72
  4840.8  334.95  4917.8  331.58  4945.3  334.31  4959.6  331.67  4959.7  325.85
  4961.2  324.85  5021.5  325.85  5066.2  337.59  5080.5   338.1  5094.8  332.87
  5123.4  336.72  5144.2  334.12  5233.7  344.44  5646.1  361.03  6282.4  363.32
#Mann= 16 ,-1 , 0
 -1131.9     .07       0   574.2     .05       0  1735.8    .035       0
  1922.3     .07       0  2828.4    .035       0  2944.2     .07       0
    3237     .05       0  3508.6     .07       0  3600.9     .05       0
  3835.6     .07       0  4819.2     .05       0  4840.8     .07       0
  4959.7     .05       0  5021.5     .07       0  5233.7     .07       0
  5646.1     .05       0
Bank Sta=4959.7,5021.5
XS Rating Curve= 0 ,0
Exp/Cntr=0.3,0.1

Type RM Length L Ch R = 1 ,341127  ,2348,2348,2348
BEGIN DESCRIPTION:
C20460
END DESCRIPTION:
XS GIS Cut Line= 3
       2375545.3     13685239.43      2374118.69     13681851.24
      2374386.18     13678730.56
#Sta/Elev= 30
   796.4  363.83  1508.9  359.89    2069  352.78  2417.2  352.18  2634.6  351.47
  2822.4  347.33  3152.7  344.48  3464.6   348.3    3901  345.96  4360.3  342.86
    4819  336.77  4940.6  337.31  4962.6  333.94  4970.7  330.67    4978  324.39
  4979.5  323.39  5040.3  324.39    5041  329.85  5201.9  330.58  5301.9   331.9
  5352.1  336.21  5823.9  338.01  5891.1  339.19  5913.2  342.01  5994.5  344.23
  6104.9  341.36  6270.7  345.42  6636.8  353.67  7048.3  352.31  7604.8  360.37
#Mann= 11 ,-1 , 0
   796.4     .07       0  2417.2     .05       0    3901     .07       0
  4360.3     .05       0    4819     .07       0  4962.6     .12       0
    4978     .05       0  5040.3     .12       0  5201.9     .05       0
  5913.2     .07       0  6270.7     .05       0
Bank Sta=4978,5040.3
XS Rating Curve= 0 ,0
Exp/Cntr=0.3,0.1