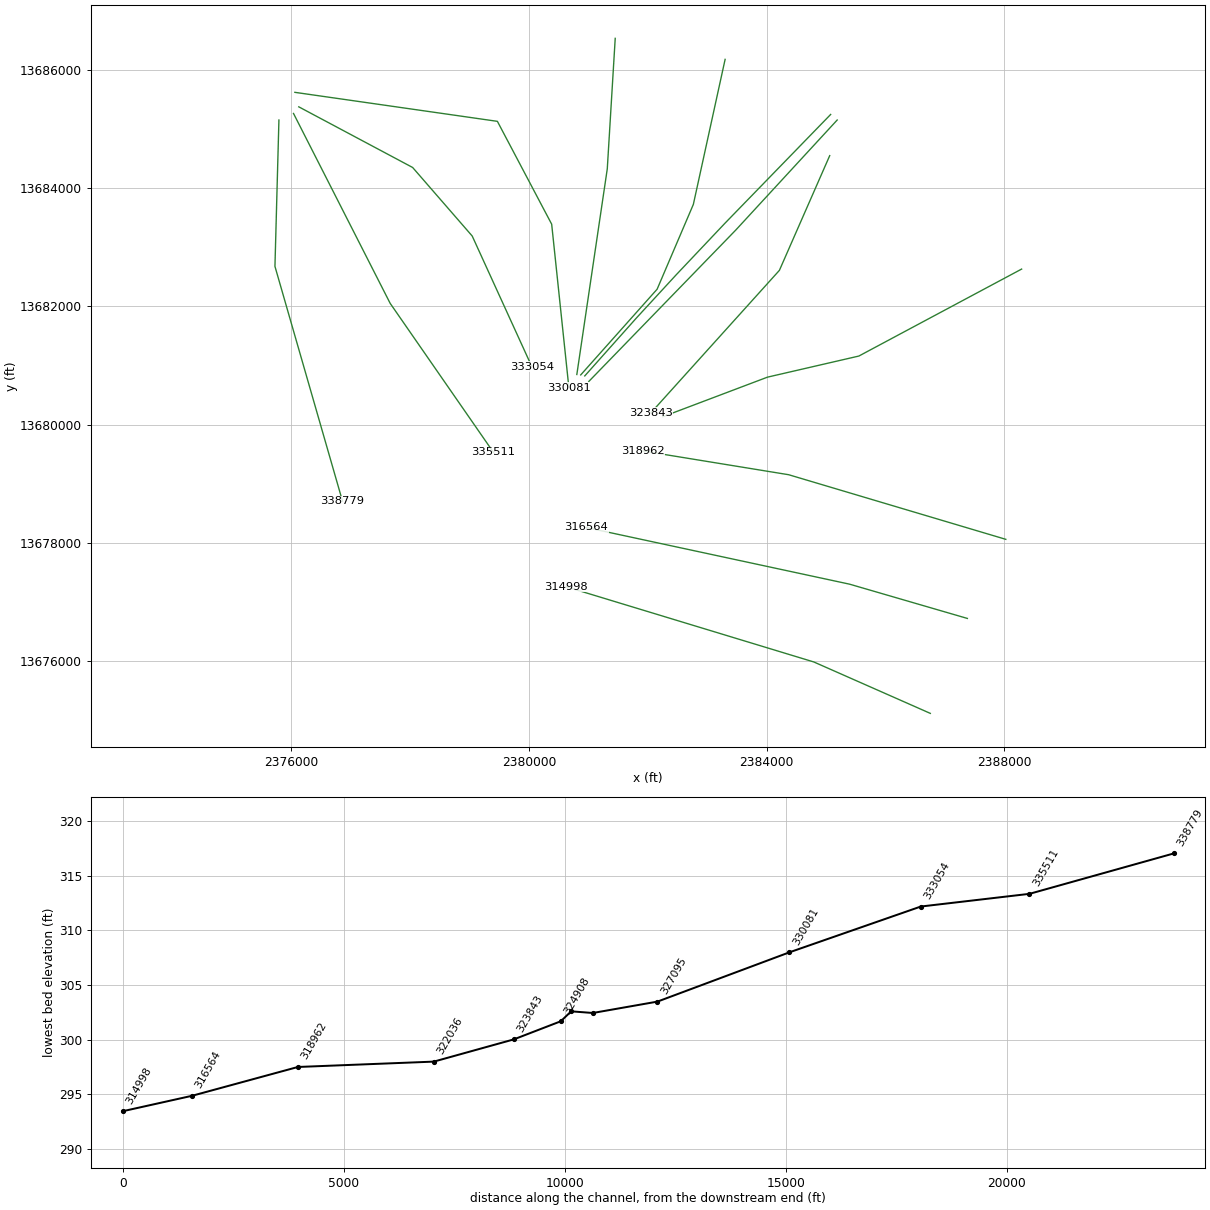
HEC-RAS study SANDIES CREEK.prj: SANDIES CREEK Base Level Engineering

--- SANDIES CREEK.g01 (geometry) --- (continued)

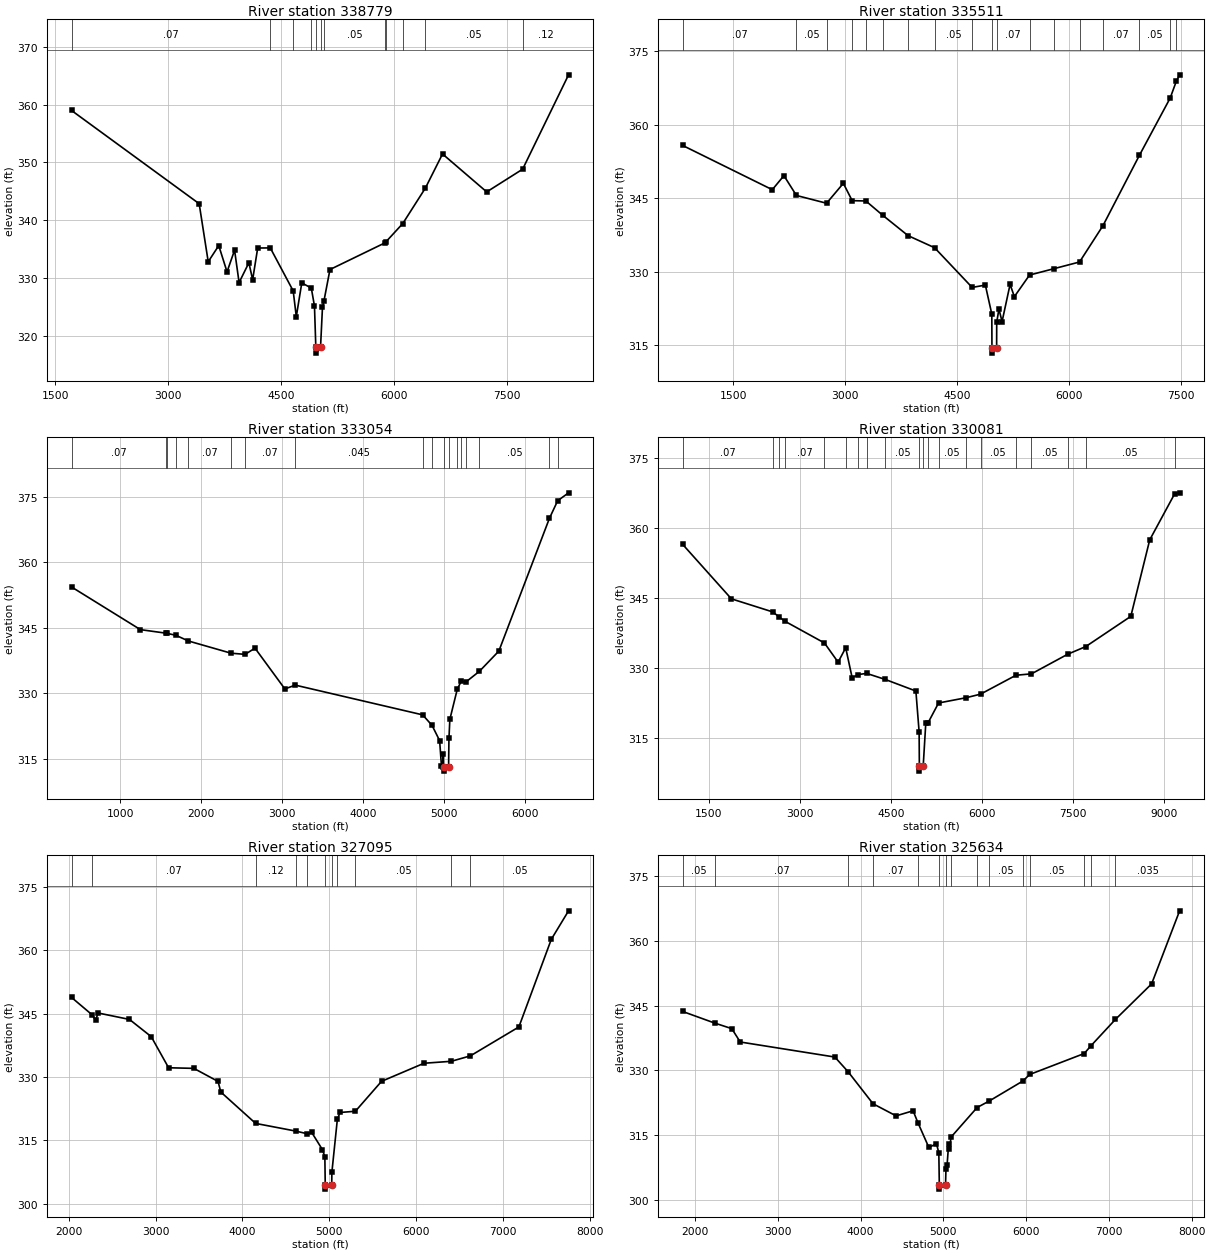
Type RM Length L Ch R = 1 ,338779  ,3268,3268,3268
BEGIN DESCRIPTION:
C20459
END DESCRIPTION:
XS GIS Cut Line= 3
       2375790.5     13685150.09      2375723.63       13682676.
      2376860.46     13678708.25
#Sta/Elev= 30
  1714.4  358.99  3410.1  342.87  3530.2  332.84  3670.2  335.63  3780.2  331.09
  3880.3  334.84  3940.3  329.24  4070.4  332.66  4120.4  329.73  4187.4  335.21
  4354.7  335.23  4658.9   327.8  4700.2  323.35    4773  329.18  4899.6  328.29
  4941.6  325.18  4959.7  318.04  4961.2  317.04  5022.1  318.04  5048.1     325
  5068.6  326.13  5147.5  331.49  5875.9  336.09  5886.6  336.22  6114.5  339.44
  6414.8  345.57  6642.6  351.47  7229.5  344.91  7706.9  348.84  8316.8  365.15
#Mann= 12 ,-1 , 0
  1714.4     .07       0  4354.7     .05       0  4658.9      .1       0
  4899.6     .07       0  4959.7     .05       0  5022.1     .07       0
  5068.6     .05       0  5875.9     .07       0  5886.6     .05       0
  6114.5     .07       0  6414.8     .05       0  7706.9     .12       0
Bank Sta=4959.7,5022.1
XS Rating Curve= 0 ,0
Exp/Cntr=0.3,0.1

Type RM Length L Ch R = 1 ,335511  ,2457,2457,2457
BEGIN DESCRIPTION:
C20458
END DESCRIPTION:
XS GIS Cut Line= 3
      2376036.15     13685260.85      2377662.93     13682051.85
      2379401.59     13679533.03
#Sta/Elev= 30
     823   355.8  2024.7  346.75  2180.6  349.62  2347.9  345.57  2751.7  343.98
  2976.7  348.05  3094.9  344.51  3278.5  344.44  3501.7  341.55  3843.3  337.36
  4198.6  334.89  4702.1  326.77    4879  327.25  4965.6  321.29  4967.3  314.34
  4968.8  313.34  5029.9  314.34  5031.2  319.63  5060.9  322.35  5102.8  319.78
  5210.3   327.4  5267.5  324.88  5470.7   329.3  5794.7  330.59  6140.7  331.97
  6454.5   339.4  6942.8  353.78    7355  365.49  7437.1  368.92  7481.4  370.23
#Mann= 18 ,-1 , 0
     823     .07       0  2347.9     .05       0  2751.7     .07       0
  3094.9     .12       0  3278.5     .07       0  3501.7     .05       0
  3843.3     .07       0  4198.6     .05       0  4702.1     .07       0
  4967.3     .05       0  5029.9     .07       0  5470.7     .05       0
  5794.7     .07       0  6140.7     .05       0  6454.5     .07       0
  6942.8     .05       0    7355    .035       0  7437.1    .063       0
Bank Sta=4967.3,5029.9
XS Rating Curve= 0 ,0
Exp/Cntr=0.3,0.1

Type RM Length L Ch R = 1 ,333054  ,2973,2973,2973
BEGIN DESCRIPTION:
C20457
END DESCRIPTION:
XS GIS Cut Line= 4
      2376124.85     13685373.19      2378041.87     13684347.81
      2379044.96     13683188.69      2380048.05     13680981.88
#Sta/Elev= 30
   400.7  354.34  1250.6  344.57  1570.9  343.75    1574  343.74  1687.4  343.28
  1842.9  341.97  2367.7  339.18  2541.6  338.91    2664  340.33  3032.5  330.99
  3160.3  331.87  4731.9  325.06  4847.5  322.66  4941.2  319.17  4964.3  313.29
  4979.4  313.18  4987.4  316.12  4989.2  313.18  4990.7  312.18  5051.9  313.18
  5056.3  319.68  5067.5  324.04    5159  330.93  5206.3  332.71  5265.7  332.59
  5431.9  335.03  5671.7  339.66  6296.4  370.09  6397.4  374.08  6531.7  375.89
#Mann= 18 ,-1 , 0
   400.7     .07       0  1570.9     .12       0    1574     .07       0
  1687.4     .12       0  1842.9     .07       0  2367.7     .12       0
  2541.6     .07       0  3160.3    .045       0  4731.9     .07       0
  4847.5      .1       0  4989.2     .05       0  5051.9      .1       0
    5159     .07       0  5206.3    .035       0  5265.7     .07       0
  5431.9     .05       0  6296.4    .035       0  6397.4     .05       0
Bank Sta=4989.2,5051.9
XS Rating Curve= 0 ,0
Exp/Cntr=0.3,0.1

Type RM Length L Ch R = 1 ,330081  ,2986,2986,2986
BEGIN DESCRIPTION:
C20456
END DESCRIPTION:
XS GIS Cut Line= 4
      2376058.99     13685618.24      2379468.49     13685127.99
      2380382.41      13683389.3      2380672.19     13680625.26
#Sta/Elev= 30
  1067.1  356.56  1871.3  344.88  2552.1  342.08  2659.3  340.99  2759.1  340.04
  3403.9  335.43  3629.2  331.32  3754.3   334.4  3860.8  327.97  3957.4  328.67
  4100.5  328.91  4407.8  327.61  4910.4  325.14  4963.8  316.39  4967.7  308.99
  4969.2  307.99  5030.6  308.99    5074  318.36    5105  318.19    5284  322.58
  5735.2   323.7  5975.1  324.47    6559  328.52  6814.2  328.82  7411.2  333.02
  7708.9  334.66    8451  341.13  8762.7  357.51  9173.2  367.37  9255.1  367.58
#Mann= 20 ,-1 , 0
  1067.1     .07       0  2552.1     .12       0  2659.3    .035       0
  2759.1     .07       0  3403.9     .12       0  3754.3     .07       0
  3957.4     .12       0  4100.5     .07       0  4407.8     .05       0
  4967.7     .05       0  5030.6     .07       0    5105     .07       0
    5284     .05       0  5735.2     .07       0  5975.1     .05       0
    6559    .035       0  6814.2     .05       0  7411.2     .05       0
  7708.9     .05       0  9173.2    .035       0
Bank Sta=4967.7,5030.6
XS Rating Curve= 0 ,0
Exp/Cntr=0.3,0.1

Type RM Length L Ch R = 1 ,327095  ,1461,1461,1461
BEGIN DESCRIPTION:
C20455
END DESCRIPTION:
XS GIS Cut Line= 3
       2381452.3     13686531.14      2381318.62     13684325.52
      2380805.94     13680848.18
#Sta/Elev= 30
    2031  348.85  2272.2  344.66  2307.6  343.41  2337.7  345.16  2698.4  343.64
  2948.8  339.57  3149.2   332.2  3439.7  332.06  3718.6  328.97  3750.3  326.46
  4151.5  319.03  4612.6  317.22  4742.8   316.6  4797.1  316.91  4920.2  312.84
  4948.8  311.17  4953.2  304.48  4954.7  303.48  5027.9  304.48  5029.6  307.45
  5092.7     320  5124.1  321.62  5300.3  321.91  5601.6  328.99    6091  333.27
    6405  333.73  6625.2  335.02  7183.5  341.86  7556.7  362.59  7755.6  369.34
#Mann= 11 ,-1 , 0
    2031    .045       0  2272.2     .07       0  4151.5     .12       0
  4612.6     .05       0  4742.8      .1       0  4953.2     .05       0
  5027.9      .1       0  5092.7     .07       0  5300.3     .05       0
    6405     .07       0  6625.2     .05       0
Bank Sta=4953.2,5027.9
XS Rating Curve= 0 ,0
Exp/Cntr=0.3,0.1

Type RM Length L Ch R = 1 ,325634  ,490,490,490
BEGIN DESCRIPTION:
C20454
END DESCRIPTION:
XS GIS Cut Line= 4
       2383302.5     13686175.62      2382767.53     13683723.67
      2382157.75     13682290.16      2380871.63     13680841.42
#Sta/Elev= 30
  1850.3  343.67  2237.4  340.98  2444.6  339.68  2546.9  336.58  3689.9  333.09
  3851.7  329.64    4151  322.25  4429.7  319.44  4635.1  320.62  4694.2  317.82
  4825.8   312.1  4916.9  312.98    4946   310.9  4951.9  303.44  4953.4  302.44
    5027  303.44  5032.2  307.16    5046  308.07  5064.2  312.82  5069.6  311.64
  5095.4  314.55  5408.7  321.38    5557  322.91  5959.9  327.51  6044.4  329.05
  6702.5  333.91  6784.5  335.72  7078.6  341.81  7516.8  350.07    7855  367.02
#Mann= 15 ,-1 , 0
  1850.3     .05       0  2237.4     .07       0  3851.7     .05       0
    4151     .07       0  4694.2      .1       0  4951.9     .05       0
    5027      .1       0  5095.4     .05       0  5408.7    .035       0
    5557     .05       0  5959.9    .035       0  6044.4     .05       0
  6702.5    .035       0  6784.5     .05       0  7078.6    .035       0
Bank Sta=4951.9,5027
XS Rating Curve= 0 ,0
Exp/Cntr=0.3,0.1

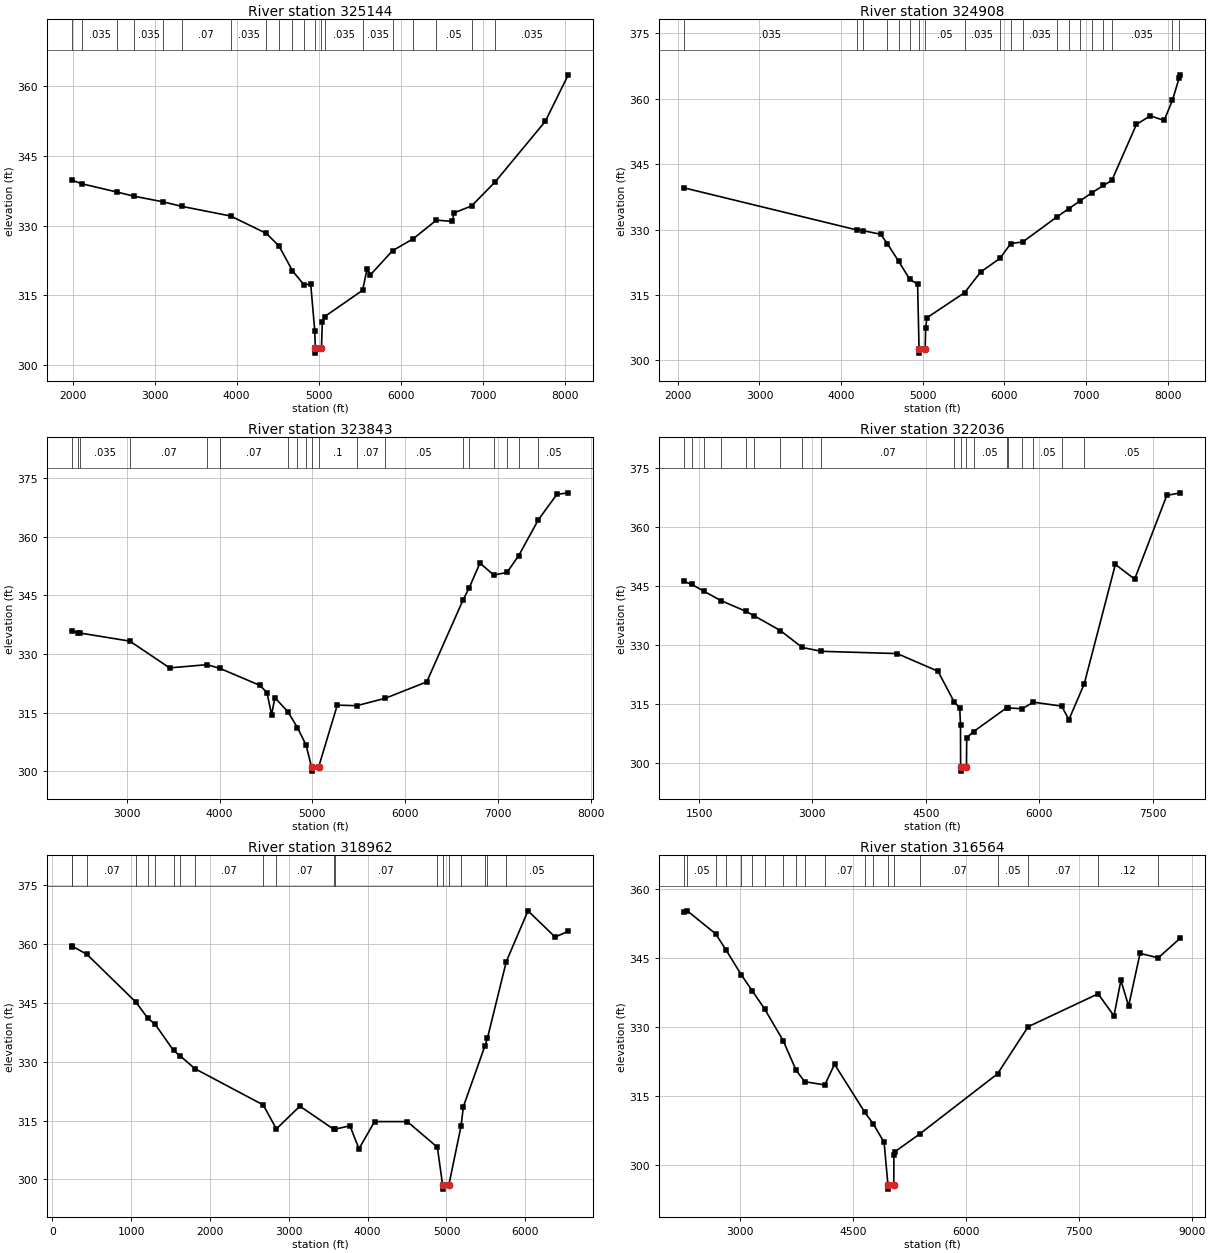
Type RM Length L Ch R = 1 ,325144  ,236,236,236
BEGIN DESCRIPTION:
SAND21670
END DESCRIPTION:
XS GIS Cut Line= 5
      2385079.11      13685244.4      2383302.62     13683408.41
      2382478.11      13682532.9      2381815.11      13681810.4
       2380939.6     13680824.39
#Sta/Elev= 30
  1987.5  339.76  2120.4  338.94  2543.4  337.19  2752.4  336.29  3107.4  335.08
  3334.5  334.11    3927  332.05  4362.8  328.31  4517.3  325.61  4681.4  320.28
  4820.7  317.29    4904  317.41  4953.3  307.36  4959.7  303.59  4961.2  302.59
  5034.9  303.59  5045.2  309.28    5074  310.44  5536.2  316.09  5590.2   320.6
  5632.2  319.42  5901.4  324.59  6152.6  327.15  6437.4  331.17  6630.3  330.88
  6651.4  332.73  6865.4  334.21  7153.9   339.4  7763.2  352.37  8044.1  362.38
#Mann= 20 ,-1 , 0
  1987.5    .035       0  2120.4    .035       0  2543.4    .035       0
  2752.4    .035       0  3107.4    .035       0  3334.5     .07       0
    3927    .035       0  4362.8     .07       0  4517.3    .035       0
  4681.4     .07       0  4820.7      .1       0  4959.7     .05       0
  5034.9    .063       0    5074    .035       0  5536.2    .035       0
  5901.4     .05       0  6152.6    .035       0  6437.4     .05       0
  6865.4    .035       0  7153.9    .035       0
Bank Sta=4959.7,5034.9
XS Rating Curve= 0 ,0
Exp/Cntr=0.3,0.1

Type RM Length L Ch R = 1 ,324908  ,1065,1065,1065
BEGIN DESCRIPTION:
SAND21671
END DESCRIPTION:
XS GIS Cut Line= 3
      2385189.22     13685150.47      2383481.12     13683289.41
       2381007.6     13680730.88
#Sta/Elev= 30
  2071.1   339.6  4193.3  329.92  4262.4  329.78  4484.2  328.94  4565.8   326.8
  4704.1  322.76  4841.6  318.58  4937.1  317.49  4954.7  302.68  4956.2  301.68
    5030  302.68  5035.9  307.34  5050.1  309.78  5513.3  315.55  5707.9  320.25
  5944.8   323.4  6078.9   326.8  6226.7  327.19  6649.5     333  6790.4  334.82
  6931.4  336.64  7072.3  338.46  7213.3  340.12  7316.2  341.28  7617.4  354.12
  7787.2  356.09  7956.7  355.03  8058.9  359.68  8141.1   364.8  8155.9  365.49
#Mann= 20 ,-1 , 0
  2071.1    .035       0  4193.3    .063       0  4262.4    .035       0
  4565.8    .035       0  4704.1    .063       0  4841.6    .035       0
  4954.7    .035       0    5030     .05       0  5513.3    .035       0
  5944.8    .035       0  6078.9    .063       0  6226.7    .035       0
  6649.5    .035       0  6790.4    .035       0  6931.4    .035       0
  7072.3     .05       0  7213.3     .05       0  7316.2    .035       0
  8058.9     .07       0  8141.1    .063       0
Bank Sta=4954.7,5030
XS Rating Curve= 0 ,0
Exp/Cntr=0.3,0.1

Type RM Length L Ch R = 1 ,323843  ,1807,1807,1807
BEGIN DESCRIPTION:
C20453
END DESCRIPTION:
XS GIS Cut Line= 3
      2385063.47     13684548.39      2384216.43     13682609.12
      2382054.25     13680201.75
#Sta/Elev= 30
    2405  335.89  2473.3   335.5  2495.6  335.37  3033.2  333.29  3462.3  326.44
  3865.7  327.27  4003.8  326.32  4435.1  321.96  4510.8  320.12  4560.5  314.48
  4595.7  318.82  4735.6  315.24  4839.5  311.16  4931.6  306.71  4991.4  301.02
  4992.9  300.02  5066.7  301.02  5268.4  316.91  5477.6  316.77  5782.3  318.64
    6232  322.86  6625.2  343.93  6690.3  346.97  6805.3  353.27  6953.7  350.21
  7096.4  350.87    7223  355.19  7434.9  364.36  7633.5  370.85    7757  371.25
#Mann= 19 ,-1 , 0
    2405    .035       0  2473.3     .07       0  2495.6    .035       0
  3033.2     .07       0  3865.7     .05       0  4003.8     .07       0
  4735.6      .1       0  4839.5     .12       0  4931.6      .1       0
  4991.4     .05       0  5066.7      .1       0  5477.6     .07       0
  5782.3     .05       0  6625.2    .035       0  6690.3     .05       0
  6953.7    .035       0  7096.4     .05       0    7223    .035       0
  7434.9     .05       0
Bank Sta=4991.4,5066.7
XS Rating Curve= 0 ,0
Exp/Cntr=0.3,0.1

Type RM Length L Ch R = 1 ,322036  ,3074,3074,3074
BEGIN DESCRIPTION:
C20452
END DESCRIPTION:
XS GIS Cut Line= 4
      2388294.37     13682630.73      2385553.88     13681160.22
      2384015.81     13680803.57      2382254.88     13680134.86
#Sta/Elev= 30
  1296.1  346.22  1404.6  345.43  1569.6  343.64  1789.6  341.33  2119.6   338.6
  2229.6  337.46  2576.3   333.7  2864.4  329.42  3120.1  328.43  4121.2  327.86
  4661.7  323.37  4874.1  315.62  4949.1  314.04  4959.4  309.74  4960.8  298.99
  4962.3  297.99  5038.4  298.99  5041.5  306.48  5133.6  308.05  5570.6  314.09
  5590.6  314.03    5776  313.85  5924.7  315.51  6298.2   314.5  6393.6  311.07
  6596.3  320.15  7008.3  350.51  7263.4  346.77  7688.6  368.04  7868.7   368.7
#Mann= 19 ,-1 , 0
  1296.1     .07       0  1404.6     .05       0  1569.6     .07       0
  1789.6     .05       0  2119.6    .035       0  2229.6     .05       0
  2576.3     .07       0  2864.4     .05       0  3120.1     .07       0
  4874.1      .1       0  4960.8     .05       0  5038.4      .1       0
  5133.6     .05       0  5570.6     .07       0  5590.6     .05       0
    5776     .07       0  5924.7     .05       0  6298.2     .07       0
  6596.3     .05       0
Bank Sta=4960.8,5038.4
XS Rating Curve= 0 ,0
Exp/Cntr=0.3,0.1

Type RM Length L Ch R = 1 ,318962  ,2398,2398,2398
BEGIN DESCRIPTION:
C20451
END DESCRIPTION:
XS GIS Cut Line= 3
      2388028.12     13678061.81      2384372.46     13679154.05
      2381920.51     13679555.28
#Sta/Elev= 30
   244.5  359.33   253.1   359.5   440.9  357.41  1064.6  345.15  1210.7  341.15
  1305.4  339.57  1538.1  332.89  1621.3  331.52  1810.5  328.23  2676.2  318.98
  2842.3  312.87  3140.7  318.67  3570.1  312.78  3586.3   312.8  3775.4  313.66
  3890.2   307.8  4087.7  314.74  4503.1  314.73    4884   308.2  4951.2   298.5
  4952.7   297.5  5029.2   298.5    5184  313.54  5214.4  318.58  5487.5  334.07
    5519  336.02  5758.3  355.57  6033.2  368.53  6377.7  361.84  6544.4  363.32
#Mann= 20 ,-1 , 0
   244.5     .07       0   253.1    .035       0   440.9     .07       0
  1064.6     .05       0  1210.7     .07       0  1305.4     .05       0
  1538.1     .07       0  1621.3     .05       0  1810.5     .07       0
  2676.2     .12       0  2842.3     .07       0  3570.1     .05       0
  3586.3     .07       0    4884      .1       0  4951.2     .05       0
  5029.2      .1       0    5184     .07       0  5487.5     .05       0
    5519     .07       0  5758.3     .05       0
Bank Sta=4951.2,5029.2
XS Rating Curve= 0 ,0
Exp/Cntr=0.3,0.1

Type RM Length L Ch R = 1 ,316564  ,1566,1566,1566
BEGIN DESCRIPTION:
C20450
END DESCRIPTION:
XS GIS Cut Line= 3
      2387380.86      13676724.6      2385397.84     13677303.91
      2380962.02     13678262.41
#Sta/Elev= 30
  2245.8  355.06  2294.1  355.25  2672.2  350.25  2811.1  346.72  3010.2  341.42
  3160.8  337.83  3323.3  333.95  3570.9  327.02  3741.8  320.63  3855.9  318.17
  4121.9  317.47  4252.2  321.95  4654.8  311.53  4766.6  309.02  4910.9  305.02
  4961.7  295.86  4963.2  294.86  5039.9  295.86    5041  302.31  5053.5  302.97
    5382   306.8  6418.6  319.88  6825.6   330.1  7755.7  337.24    7967  332.46
  8059.1  340.17  8161.4   334.6  8313.7  346.02    8556  345.05  8849.9  349.35
#Mann= 20 ,-1 , 0
  2245.8    .035       0  2294.1     .05       0  2672.2     .07       0
  2811.1     .05       0  3010.2     .05       0  3160.8     .07       0
  3323.3     .05       0  3570.9     .07       0  3741.8    .035       0
  3855.9    .033       0  4121.9     .07       0  4654.8    .035       0
  4766.6      .1       0  4961.7     .05       0  5039.9      .1       0
    5382     .07       0  6418.6     .05       0  6825.6     .07       0
  7755.7     .12       0    8556    .035       0
Bank Sta=4961.7,5039.9
XS Rating Curve= 0 ,0
Exp/Cntr=0.3,0.1

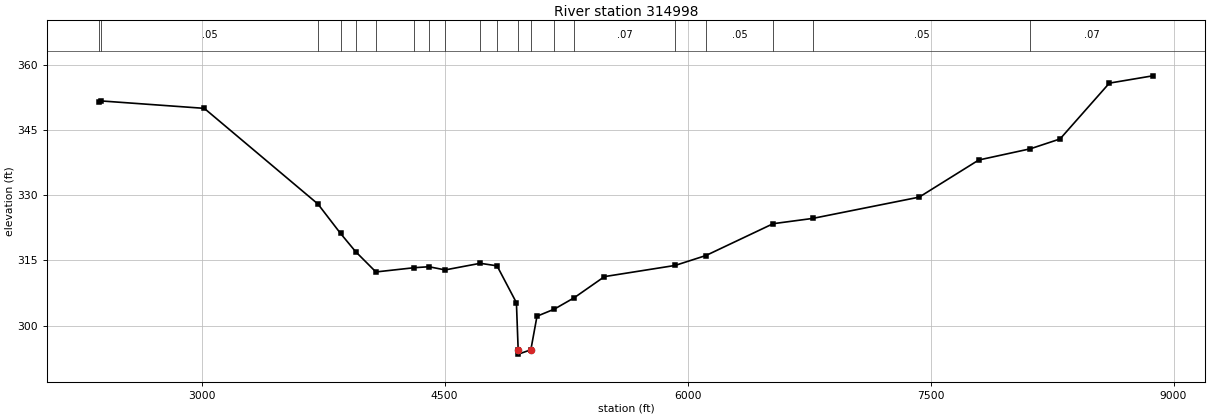
Type RM Length L Ch R = 1 ,314998  ,2570,2570,2570
BEGIN DESCRIPTION:
C20449
END DESCRIPTION:
XS GIS Cut Line= 3
      2386756.94     13675119.69      2384795.99     13675988.75
      2380627.63     13677259.32
#Sta/Elev= 30
  2369.1   351.5  2378.7  351.69  3016.8  349.98  3718.4  327.98  3858.2   321.2
    3951  317.03  4076.3  312.35  4313.7  313.33  4403.5  313.55  4503.8  312.82
  4720.2  314.34    4824  313.76  4943.7  305.28  4954.5  294.45    4956  293.45
  5032.8  294.45  5070.7  302.17  5177.7   303.8    5300  306.41  5487.3  311.28
  5923.4  313.85  6113.6  316.13  6528.4  323.45  6772.2  324.66    7430  329.56
  7797.7   338.1  8116.3  340.68  8299.5  342.94  8603.8  355.78  8871.7  357.46
#Mann= 20 ,-1 , 0
  2369.1     .07       0  2378.7     .05       0  3718.4     .07       0
  3858.2     .05       0    3951     .12       0  4076.3    .035       0
  4313.7     .05       0  4403.5     .12       0  4503.8     .05       0
  4720.2     .12       0    4824      .1       0  4954.5     .05       0
  5032.8      .1       0  5177.7    .035       0    5300     .07       0
  5923.4     .05       0  6113.6     .05       0  6528.4     .07       0
  6772.2     .05       0  8116.3     .07       0
Bank Sta=4954.5,5032.8
XS Rating Curve= 0 ,0
Exp/Cntr=0.3,0.1