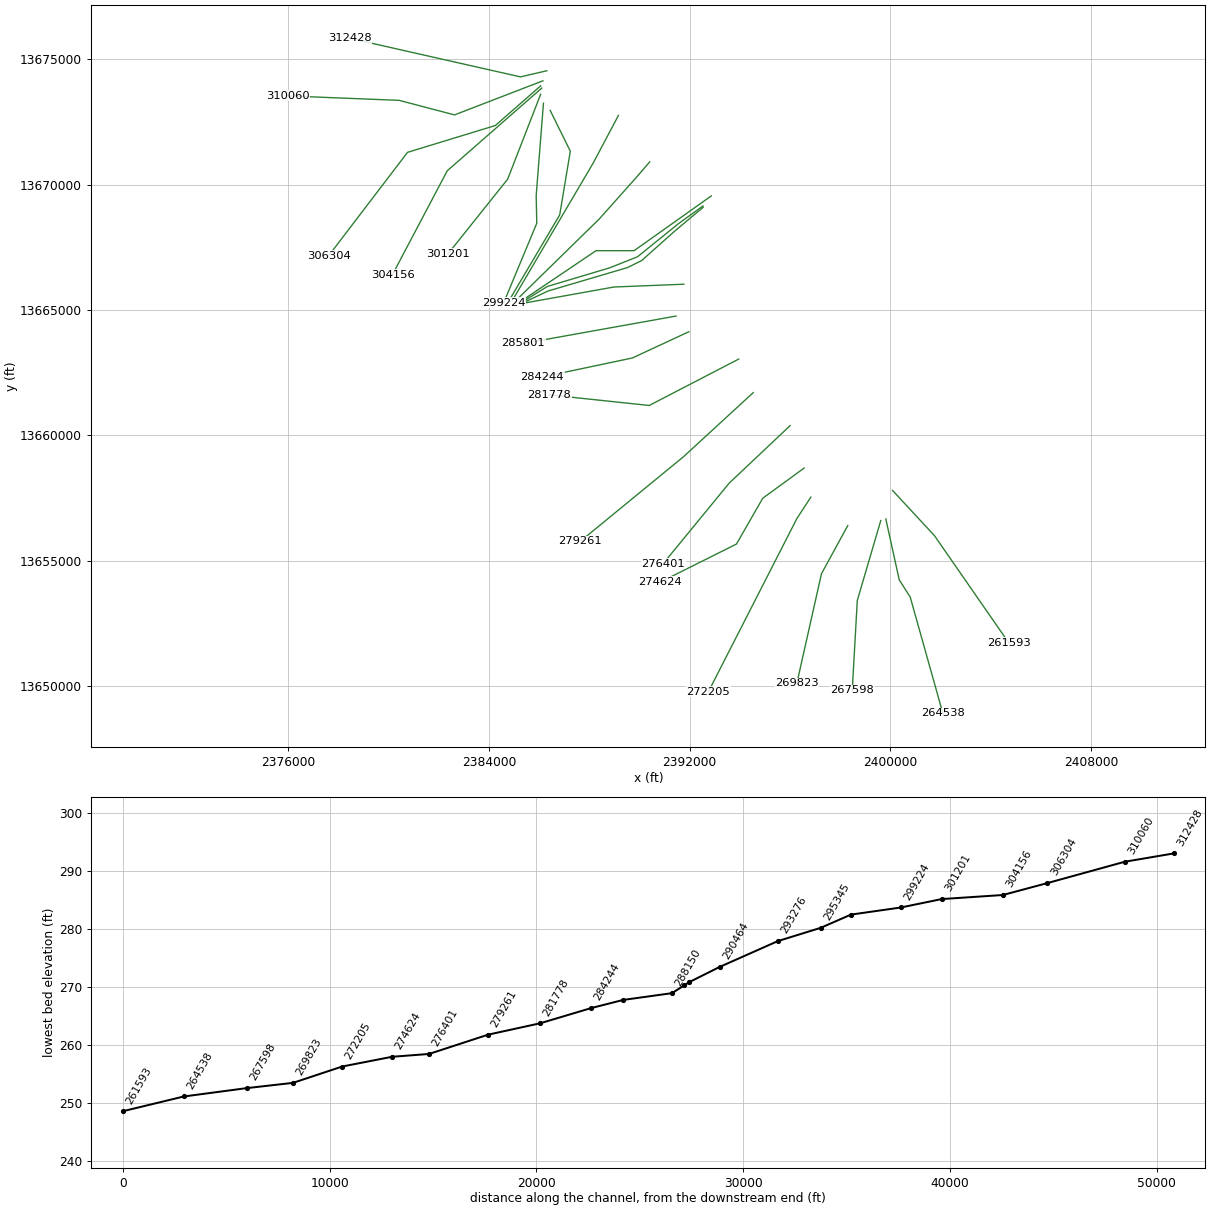
HEC-RAS study SANDIES CREEK.prj: SANDIES CREEK Base Level Engineering

--- SANDIES CREEK.g01 (geometry) --- (continued)

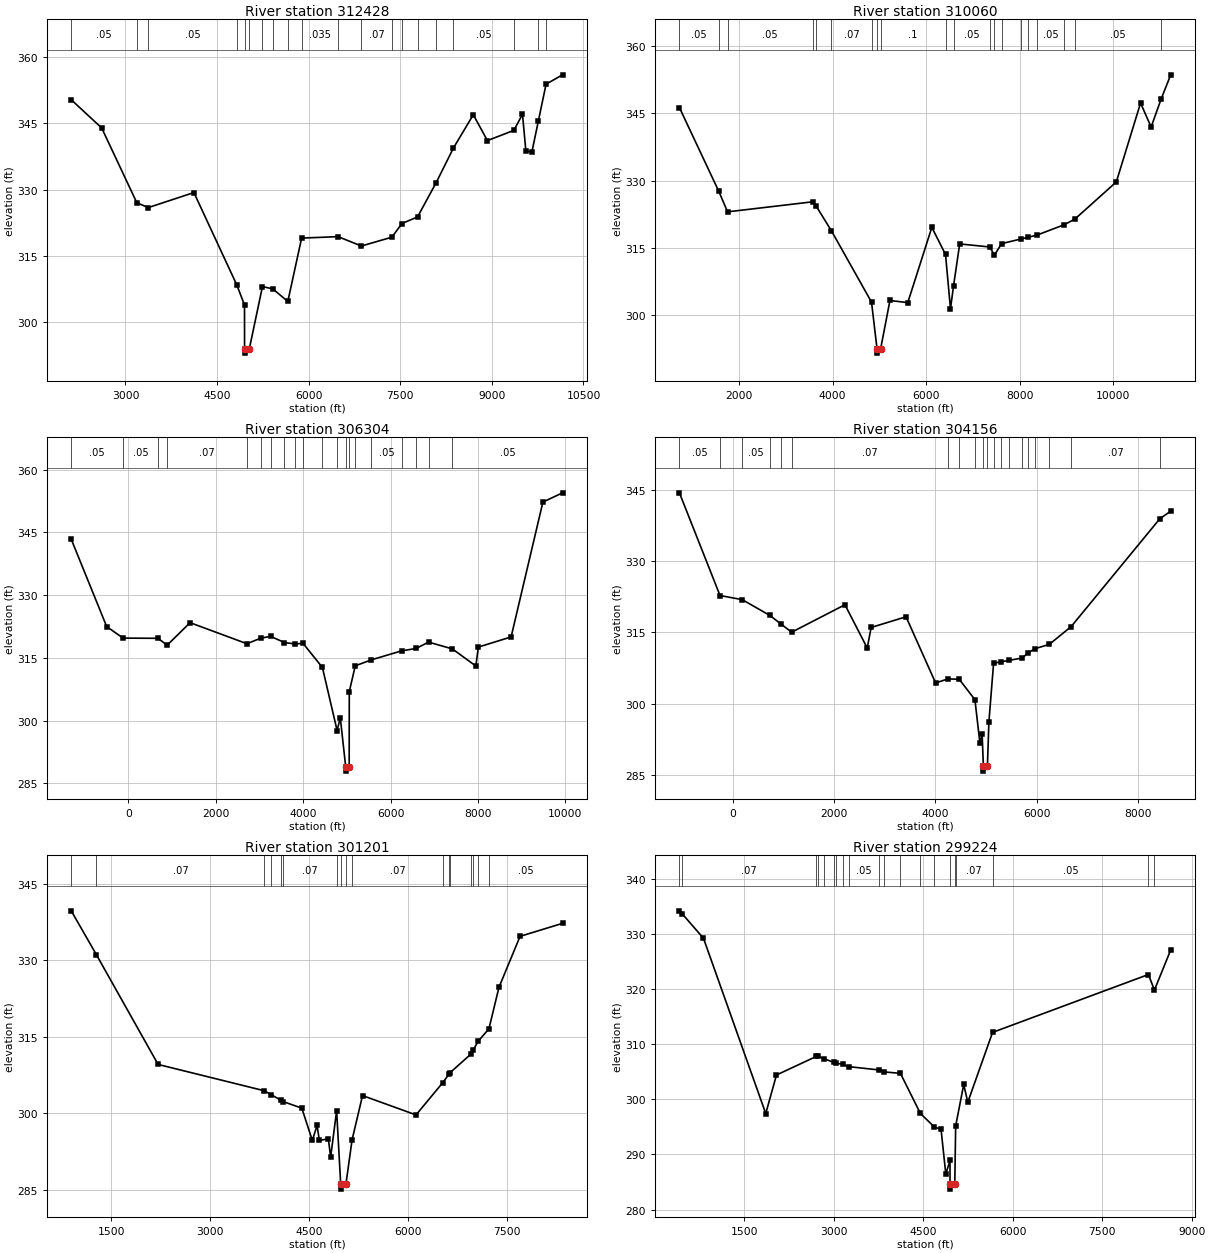
Type RM Length L Ch R = 1 ,312428  ,2368,2368,2368
BEGIN DESCRIPTION:
C20448
END DESCRIPTION:
XS GIS Cut Line= 3
      2386310.87     13674539.64       2385264.1     13674294.65
      2378465.36     13675832.73
#Sta/Elev= 30
  2111.6  350.32  2610.6  343.93  3185.8  327.02  3373.4  325.93  4120.6  329.33
  4823.5  308.42  4949.2   303.9  4950.1  294.02  4951.6  293.02  5028.5  294.02
  5242.9  308.07  5411.6  307.55  5658.5  304.71  5884.4  319.03  6481.5  319.36
  6863.6  317.24  7362.8  319.24  7527.5  322.33  7782.2  323.81  8086.9  331.55
  8371.3  339.42  8695.6  346.92  8927.2  341.08    9360  343.39  9501.4  347.03
  9556.7  338.74  9655.2  338.49  9762.5  345.59  9887.3  353.84 10157.2  355.95
#Mann= 20 ,-1 , 0
  2111.6     .05       0  3185.8     .07       0  3373.4     .05       0
  4823.5      .1       0  4950.1     .05       0  5028.5      .1       0
  5242.9     .05       0  5411.6     .07       0  5658.5     .05       0
  5884.4    .035       0  6481.5     .07       0  6863.6     .07       0
  7362.8    .035       0  7527.5     .07       0  7782.2     .05       0
  8086.9    .035       0  8371.3     .05       0    9360     .05       0
  9762.5    .035       0  9887.3     .05       0
Bank Sta=4950.1,5028.5
XS Rating Curve= 0 ,0
Exp/Cntr=0.3,0.1

Type RM Length L Ch R = 1 ,310060  ,3756,3756,3756
BEGIN DESCRIPTION:
C20447
END DESCRIPTION:
XS GIS Cut Line= 4
       2386155.7     13674138.61      2382633.78     13672778.88
      2380426.99     13673358.44      2375991.08     13673536.77
#Sta/Elev= 30
   729.4  346.25  1570.2  327.62    1758  323.04  3573.2  325.27  3644.2  324.44
  3973.4  318.88  4833.7  302.94  4950.7  292.59  4952.2  291.59  5029.2  292.59
  5227.2  303.31    5608  302.83  6122.3  319.59  6414.4  313.55  6520.8  301.46
  6585.1   306.5  6717.4   315.9  7360.2  315.22  7458.8  313.39  7612.1  315.96
  8026.2     317  8166.3  317.35  8367.7  317.86  8947.8  320.16  9178.9  321.43
 10063.7   329.7 10581.4  347.26 10807.5  341.92   11019   348.1 11225.8  353.54
#Mann= 20 ,-1 , 0
   729.4     .05       0  1570.2     .07       0    1758     .05       0
  3573.2    .035       0  3644.2     .05       0  3973.4     .07       0
  4833.7      .1       0  4950.7     .05       0  5029.2      .1       0
  6414.4     .07       0  6585.1     .05       0  7360.2     .07       0
  7458.8    .035       0  7612.1     .07       0  8026.2    .035       0
  8166.3     .07       0  8367.7     .05       0  8947.8     .07       0
  9178.9     .05       0   11019     .07       0
Bank Sta=4950.7,5029.2
XS Rating Curve= 0 ,0
Exp/Cntr=0.3,0.1

Type RM Length L Ch R = 1 ,306304  ,2148,2148,2148
BEGIN DESCRIPTION:
C20446
END DESCRIPTION:
XS GIS Cut Line= 4
      2386066.57       13673938.      2384261.01     13672355.35
      2380761.35     13671285.39      2377618.33     13667161.56
#Sta/Elev= 30
   -1308  343.39  -496.6  322.49    -122  319.73   677.3  319.68   887.3  318.03
    1413  323.42  2715.1  318.38  3025.3   319.7  3255.7  320.15  3571.6  318.67
  3813.8  318.33  3998.3  318.47  4441.4   312.7  4777.6  297.62  4850.6  300.65
  4974.7   288.9  4976.2   287.9  5053.9   288.9  5056.4  306.92    5193  313.09
  5554.5   314.5  6254.9  316.68    6586  317.25  6870.6  318.77  7417.1  317.14
  7954.1  313.04  8010.3  317.58  8760.6  320.01  9488.2  352.28  9937.6  354.49
#Mann= 20 ,-1 , 0
   -1308     .05       0    -122     .05       0   677.3     .07       0
   887.3     .07       0  2715.1     .07       0  3025.3     .07       0
  3255.7     .05       0  3571.6     .05       0  3813.8    .035       0
  3998.3     .05       0  4441.4     .05       0  4777.6      .1       0
  4974.7     .05       0  5053.9      .1       0    5193    .035       0
  5554.5     .05       0  6254.9     .07       0    6586    .035       0
  6870.6     .07       0  7417.1     .05       0
Bank Sta=4974.7,5053.9
XS Rating Curve= 0 ,0
Exp/Cntr=0.3,0.1

Type RM Length L Ch R = 1 ,304156  ,2955,2955,2955
BEGIN DESCRIPTION:
C20445
END DESCRIPTION:
XS GIS Cut Line= 3
      2386110.61     13673848.37        2382344.      13670549.8
      2380159.48     13666403.67
#Sta/Elev= 30
 -1052.3  344.31  -251.5  322.74     187  321.87   731.6  318.56     946   316.8
    1162  315.03  2213.6   320.8    2653  311.71  2730.8  316.03  3418.9  318.27
  4002.7  304.36  4241.9  305.22    4468  305.15  4778.1  300.85  4875.5  291.79
  4920.7  293.56  4944.7  286.85  4946.2  285.85  5024.3  286.85  5053.9  296.23
  5146.4  308.53  5282.7  308.79  5454.6  309.12  5711.6  309.62  5824.7  310.66
  5962.3  311.57  6246.2  312.48  6677.4  316.22  8426.4  338.87  8640.9  340.46
#Mann= 20 ,-1 , 0
 -1052.3     .05       0  -251.5     .07       0     187     .05       0
   731.6    .035       0     946     .05       0    1162     .07       0
  4241.9    .035       0    4468     .07       0  4778.1      .1       0
  4944.7     .05       0  5024.3      .1       0  5146.4     .07       0
  5282.7     .05       0  5454.6     .05       0  5711.6     .05       0
  5824.7     .07       0  5962.3     .05       0  6246.2     .05       0
  6677.4     .07       0  8426.4     .05       0
Bank Sta=4944.7,5024.3
XS Rating Curve= 0 ,0
Exp/Cntr=0.3,0.1

Type RM Length L Ch R = 1 ,301201  ,1977,1977,1977
BEGIN DESCRIPTION:
C20444
END DESCRIPTION:
XS GIS Cut Line= 3
      2386065.87     13673601.84      2384751.41     13670215.43
      2382366.27     13667228.44
#Sta/Elev= 30
     893  339.68  1275.1  331.08  2211.2  309.58  3824.4  304.42  3931.3  303.63
  4068.6  302.61  4112.4  302.28  4391.6  301.02  4551.7  294.68    4623  297.62
  4658.3   294.7  4794.4     295  4829.6  291.45  4920.1  300.51  4981.7  286.15
  4983.2  285.15  5061.3  286.15  5154.5  294.81  5313.1  303.48  6124.9  299.69
  6530.3  306.01  6623.2  307.64  6642.6  307.98  6959.5  311.63  6993.2  312.41
  7067.4  314.12  7230.9  316.56  7383.4  324.69  7703.6  334.68    8348  337.23
#Mann= 17 ,-1 , 0
     893     .05       0  1275.1     .07       0  3824.4    .035       0
  3931.3     .07       0  4068.6     .05       0  4112.4     .07       0
  4920.1      .1       0  4981.7     .05       0  5061.3      .1       0
  5154.5     .07       0  6530.3     .05       0  6623.2     .07       0
  6642.6     .05       0  6959.5     .07       0  6993.2     .05       0
  7067.4    .035       0  7230.9     .05       0
Bank Sta=4981.7,5061.3
XS Rating Curve= 0 ,0
Exp/Cntr=0.3,0.1

Type RM Length L Ch R = 1 ,299224  ,2416,2416,2416
BEGIN DESCRIPTION:
C20443
END DESCRIPTION:
XS GIS Cut Line= 4
      2386178.02     13673247.02      2385888.24       13669569.
      2385910.53     13668454.46      2384595.38     13665289.19
#Sta/Elev= 30
   416.3  334.18   462.1  333.65   819.6   329.2  1862.8  297.41  2042.3   304.4
  2710.2  307.77  2738.3  307.78  2842.2  307.34  3001.4  306.69  3040.3  306.59
  3153.1  306.31  3252.7  305.92  3763.7  305.31  3848.9  304.96  4119.2   304.7
  4454.2  297.42  4687.9  294.97  4799.9  294.55  4879.9  286.43  4949.9  288.91
  4950.2   284.7  4951.7   283.7    5030   284.7    5045  295.17  5179.9  302.68
  5247.9  299.46  5663.2  312.13  8274.9  322.63  8374.7   319.8  8648.1  327.09
#Mann= 20 ,-1 , 0
   416.3     .05       0   462.1     .07       0  2710.2    .035       0
  2738.3     .07       0  2842.2     .05       0  3001.4     .07       0
  3040.3     .05       0  3153.1     .07       0  3252.7     .05       0
  3763.7     .07       0  3848.9     .05       0  4119.2     .07       0
  4454.2     .12       0  4687.9      .1       0  4950.2     .05       0
    5030      .1       0    5045     .07       0  5663.2     .05       0
  8274.9     .07       0  8374.7     .07       0
Bank Sta=4950.2,5030
XS Rating Curve= 0 ,0
Exp/Cntr=0.3,0.1

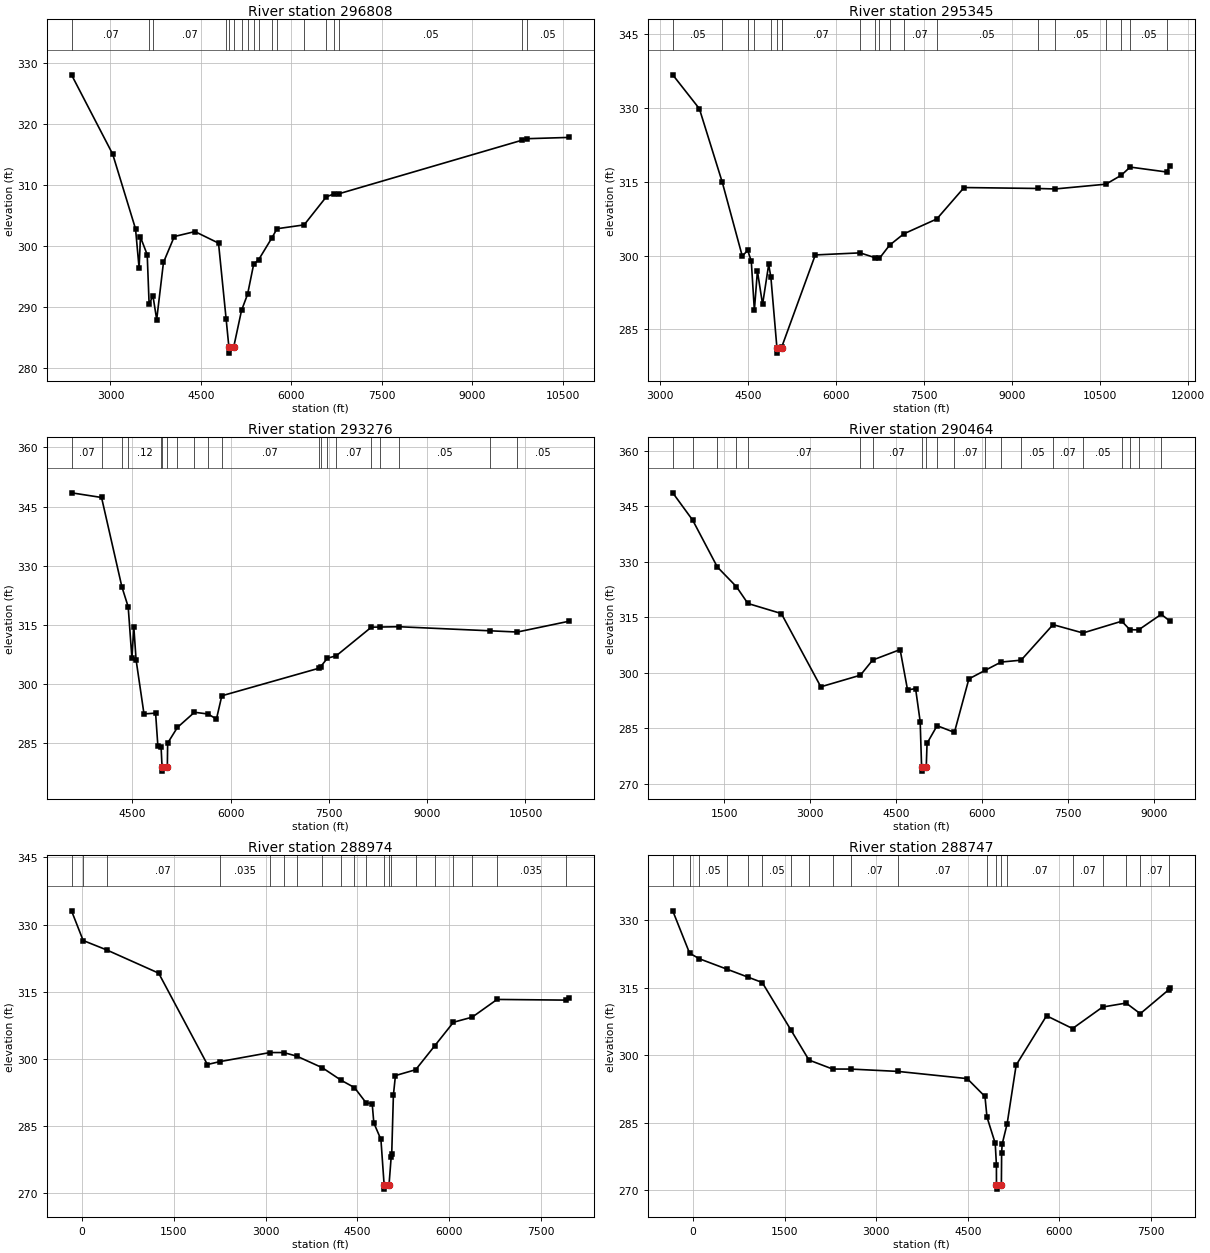
Type RM Length L Ch R = 1 ,296808  ,1463,1463,1463
BEGIN DESCRIPTION:
C20442
END DESCRIPTION:
XS GIS Cut Line= 4
      2386445.49     13672957.24      2387247.98     13671329.98
      2386824.45     13668788.82      2384862.87     13665467.51
#Sta/Elev= 30
  2354.9  328.13  3037.5  315.12  3416.6  302.85  3475.5  296.42  3497.9  301.51
  3610.2  298.62  3641.8  290.47  3705.1  291.89  3767.4  287.97  3879.6  297.35
  4059.3   301.6  4401.4  302.41  4792.7  300.52  4919.3  288.04  4964.6  283.47
  4966.1  282.47  5044.5  283.47  5174.5  289.48  5274.9  292.14  5375.2  297.03
    5459  297.81  5681.7  301.44  5762.8  302.88  6212.5  303.51  6579.2   308.1
  6703.6  308.58  6797.6  308.64  9832.6  317.42  9907.8  317.65 10602.8  317.86
#Mann= 18 ,-1 , 0
  2354.9     .07       0  3641.8     .12       0  3705.1     .07       0
  4919.3      .1       0  4964.6     .05       0  5044.5      .1       0
  5174.5     .12       0  5274.9      .1       0  5375.2     .12       0
    5459     .07       0  5681.7    .035       0  5762.8     .07       0
  6212.5    .035       0  6579.2     .05       0  6703.6    .035       0
  6797.6     .05       0  9832.6     .07       0  9907.8     .05       0
Bank Sta=4964.6,5044.5
XS Rating Curve= 0 ,0
Exp/Cntr=0.3,0.1

Type RM Length L Ch R = 1 ,295345  ,2069,2069,2069
BEGIN DESCRIPTION:
C20441
END DESCRIPTION:
XS GIS Cut Line= 3
      2389164.98     13672756.56       2388161.9     13670861.87
      2384952.05     13665400.66
#Sta/Elev= 30
  3210.5  336.76  3664.6  329.87  4055.7  314.89  4395.7  299.92  4488.8  301.08
  4549.7  298.87  4602.1  288.87    4654  296.89    4742  290.09  4846.4  298.21
  4883.5  295.65  4987.1  281.19  4988.6  280.19  5067.4  281.19  5069.3  281.45
  5640.7  300.15  6405.2  300.57    6667  299.56    6733  299.44  6907.3  302.13
  7148.8  304.43  7712.2  307.46  8177.7  313.85  9430.3  313.66  9729.5  313.56
 10594.6  314.53 10856.9  316.34 11008.6  318.01 11630.2  317.01   11689  318.32
#Mann= 20 ,-1 , 0
  3210.5     .05       0  4055.7     .07       0  4488.8     .12       0
  4602.1     .07       0  4883.5      .1       0  4987.1     .05       0
  5067.4      .1       0  5069.3     .07       0  6405.2     .07       0
    6667    .035       0    6733     .07       0  6907.3     .05       0
  7148.8     .07       0  7712.2     .05       0  9430.3     .07       0
  9729.5     .05       0 10594.6     .07       0 10856.9     .07       0
 11008.6     .05       0 11630.2    .035       0
Bank Sta=4987.1,5067.4
XS Rating Curve= 0 ,0
Exp/Cntr=0.3,0.1

Type RM Length L Ch R = 1 ,293276  ,2812,2812,2812
BEGIN DESCRIPTION:
C20440
END DESCRIPTION:
XS GIS Cut Line= 4
      2390413.26     13670906.43        2389856.     13670260.02
       2388407.1     13668632.79      2385152.66     13665445.22
#Sta/Elev= 30
  3573.5   348.5  4031.5  347.32  4341.3  324.69  4437.9  319.58    4495  306.51
  4523.5  314.57  4558.6  306.12    4679  292.42  4856.2  292.62  4891.4  284.16
  4940.2  283.93  4954.8  278.91  4956.3  277.91  5035.1  278.91  5040.2  285.02
  5188.9  288.99  5449.5  292.84  5656.4   292.4  5784.4  291.11  5866.6  297.02
  7344.2  303.99  7373.5  304.39  7478.2  306.56  7612.1  307.16    8148  314.42
  8281.9  314.46  8563.4  314.54  9963.2   313.5   10375  313.19 11161.2  315.92
#Mann= 20 ,-1 , 0
  3573.5     .07       0  4031.5     .12       0  4341.3     .07       0
  4437.9     .12       0  4940.2      .1       0  4954.8     .05       0
  5035.1      .1       0  5188.9      .1       0  5449.5    .035       0
  5656.4     .05       0  5866.6     .07       0  7344.2    .035       0
  7373.5     .07       0  7478.2    .035       0  7612.1     .07       0
    8148     .05       0  8281.9     .07       0  8563.4     .05       0
  9963.2     .07       0   10375     .05       0
Bank Sta=4954.8,5035.1
XS Rating Curve= 0 ,0
Exp/Cntr=0.3,0.1

Type RM Length L Ch R = 1 ,290464  ,1490,1490,1490
BEGIN DESCRIPTION:
C20439
END DESCRIPTION:
XS GIS Cut Line= 4
      2392865.24     13669546.69      2389789.13     13667362.21
      2388273.36     13667362.21      2385464.72     13665467.49
#Sta/Elev= 30
   600.3  348.68   948.2  341.29  1378.5  328.63  1711.4  323.31  1910.9  318.78
    2495  316.05  3183.8  296.25  3874.7  299.39  4088.2  303.48  4567.3  306.31
  4697.3   295.4  4837.3  295.77  4917.3  286.86  4942.5  274.46    4944  273.46
    5023  274.46  5037.3  280.99  5212.7  285.74  5514.6  283.93  5767.3  298.39
  6047.1  300.67    6329  302.94  6678.4  303.45  7235.3  313.05  7757.6   310.8
  8434.7  313.98  8576.2  311.68  8728.8  311.64  9123.5  315.85  9276.9  313.97
#Mann= 20 ,-1 , 0
   600.3     .07       0   948.2     .07       0  1378.5    .035       0
  1711.4     .07       0  1910.9     .07       0  3874.7     .05       0
  4088.2     .07       0  4942.5     .05       0    5023      .1       0
  5212.7     .07       0  5514.6     .07       0  6047.1    .035       0
    6329     .07       0  6678.4     .05       0  7235.3     .07       0
  7757.6     .05       0  8434.7     .05       0  8576.2     .07       0
  8728.8    .035       0  9123.5     .05       0
Bank Sta=4942.5,5023
XS Rating Curve= 0 ,0
Exp/Cntr=0.3,0.1

Type RM Length L Ch R = 1 ,288974  ,227,227,227
BEGIN DESCRIPTION:
SAND21672
END DESCRIPTION:
XS GIS Cut Line= 6
      2392533.93     13669145.67      2391546.46     13668431.52
      2389924.26     13667117.88       2388813.4     13666677.07
        2386336.     13665936.49      2385454.36     13665389.88
#Sta/Elev= 30
  -170.7  333.06    19.2  326.42   404.6  324.31  1253.1  319.12  2049.3  298.68
  2248.4  299.32  3071.4  301.36  3294.6  301.36  3509.4  300.56  3927.7  297.96
  4236.3  295.15  4452.9  293.52  4644.6  290.08  4742.1  289.96  4769.1  285.61
    4885  281.92    4937  271.81  4938.5  270.81  5017.6  271.81    5052  277.91
  5061.4  278.66  5088.9  291.84    5122  296.21  5452.8  297.52  5764.8  302.88
  6070.3  308.14  6375.8  309.27  6783.2  313.24  7904.9  313.09  7955.5  313.63
#Mann= 20 ,-1 , 0
  -170.7     .07       0    19.2     .05       0   404.6     .07       0
  2248.4    .035       0  3071.4    .035       0  3294.6    .035       0
  3509.4    .035       0  3927.7    .035       0  4236.3    .035       0
  4452.9     .07       0  4644.6    .035       0    4937     .05       0
  5017.6     .07       0    5052    .035       0  5452.8     .07       0
  5764.8    .035       0  6070.3    .035       0  6375.8    .035       0
  6783.2    .035       0  7904.9     .07       0
Bank Sta=4937,5017.6
XS Rating Curve= 0 ,0
Exp/Cntr=0.3,0.1

Type RM Length L Ch R = 1 ,288747  ,597,597,597
BEGIN DESCRIPTION:
SAND21673
END DESCRIPTION:
XS GIS Cut Line= 6
      2392541.36     13669091.62      2391414.22      13668149.4
      2390091.77     13666968.01       2389518.7     13666685.88
      2386353.63     13665751.35      2385480.79     13665336.97
#Sta/Elev= 30
  -333.9  332.12   -57.9  322.71   101.2  321.47   552.6  319.16   905.8  317.35
  1132.1  316.19  1603.9   305.6  1897.5  298.96  2284.9  296.96  2585.3  296.95
  3357.3  296.43  4490.4  294.83  4781.5  290.86  4814.4  286.28  4949.4  280.46
  4969.1  275.63  4969.7  271.27  4971.2  270.27  5050.3  271.27  5054.5   278.3
    5063  280.26  5144.7   284.8  5292.4  297.84  5790.2   308.8  6216.5  305.96
  6709.2  310.74  7094.4  311.62  7325.9  309.26  7792.9  314.59  7813.6   314.9
#Mann= 20 ,-1 , 0
  -333.9     .07       0   -57.9     .07       0   101.2     .05       0
   552.6     .05       0   905.8     .07       0  1132.1     .05       0
  1603.9     .07       0  1897.5     .05       0  2284.9     .05       0
  2585.3     .07       0  3357.3     .07       0  4814.4     .12       0
  4969.7     .05       0  5050.3     .12       0  5144.7     .07       0
  6216.5     .07       0  6709.2     .07       0  7094.4     .05       0
  7325.9     .07       0  7792.9    .035       0
Bank Sta=4969.7,5050.3
XS Rating Curve= 0 ,0
Exp/Cntr=0.3,0.1

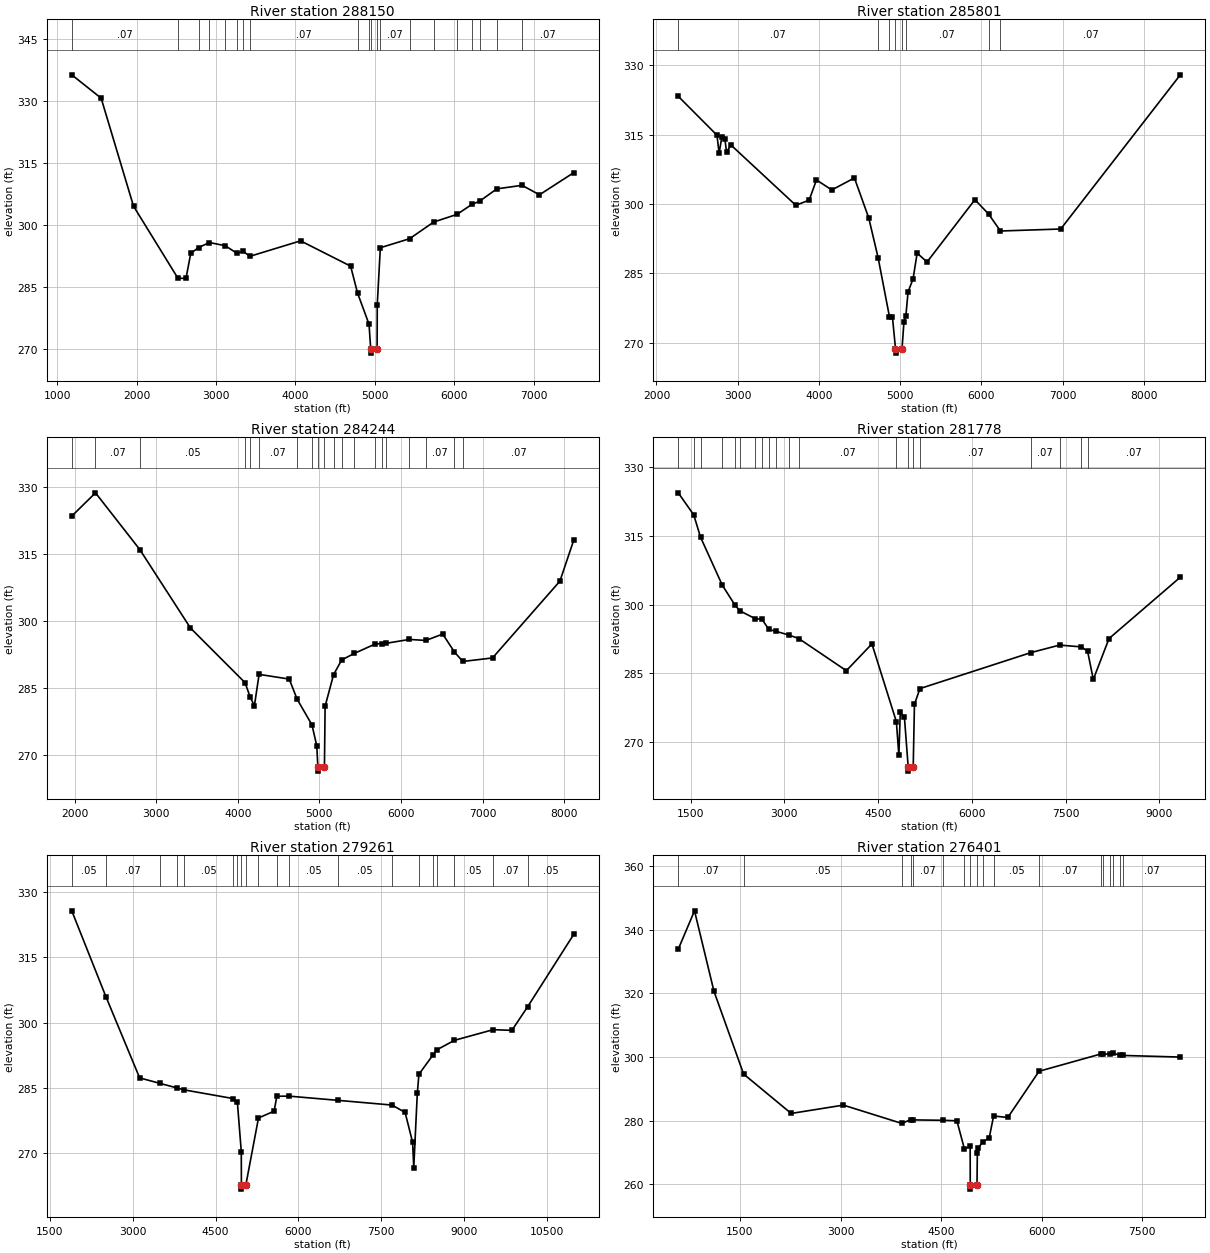
Type RM Length L Ch R = 1 ,288150  ,2349,2349,2349
BEGIN DESCRIPTION:
C20438
END DESCRIPTION:
XS GIS Cut Line= 3
      2391771.51      13666024.7      2388986.66     13665913.31
      2385509.31     13665289.17
#Sta/Elev= 30
  1184.7  336.28  1554.5  330.63  1961.8   304.5  2520.4  287.07  2622.4  287.01
  2682.4  293.08    2781  294.48  2917.5   295.7  3115.3  294.93  3264.3  293.09
  3342.3  293.56  3426.7  292.36  4064.9   296.1  4694.8  289.98  4782.3  283.45
  4926.8  275.91  4947.6  269.93  4949.1  268.93  5028.2  269.93  5030.1  280.67
  5068.9  294.44  5436.3  296.61  5741.1  300.66  6032.8   302.5  6219.9   304.9
  6319.4  305.71  6535.1  308.68  6852.5  309.54  7072.2  307.25  7504.7  312.62
#Mann= 20 ,-1 , 0
  1184.7     .07       0  2520.4     .05       0    2781     .07       0
  2917.5     .05       0  3115.3     .07       0  3264.3     .05       0
  3342.3    .035       0  3426.7     .07       0  4782.3     .12       0
  4926.8      .1       0  4947.6     .05       0  5028.2      .1       0
  5068.9     .07       0  5436.3    .035       0  5741.1     .07       0
  6032.8    .035       0  6219.9     .05       0  6319.4     .07       0
  6535.1     .05       0  6852.5     .07       0
Bank Sta=4947.6,5028.2
XS Rating Curve= 0 ,0
Exp/Cntr=0.3,0.1

Type RM Length L Ch R = 1 ,285801  ,1557,1557,1557
BEGIN DESCRIPTION:
C20437
END DESCRIPTION:
XS GIS Cut Line= 2
      2391460.51     13664754.11      2385375.55     13663661.94
#Sta/Elev= 30
  2267.9  323.29    2745  314.88  2771.3  310.96  2803.7  314.41  2842.5  314.02
  2862.8  311.22  2916.2  312.77  3716.2  299.72    3880  300.85  3970.2  305.21
  4158.6  303.04  4437.3  305.64  4613.6     297  4729.1  288.39  4869.1   275.6
  4904.9  275.68    4943  268.77  4944.5  267.77  5023.8  268.77  5047.1  274.53
  5070.8  275.83  5097.9  281.04  5158.9  283.77  5209.7  289.38  5331.6  287.47
  5920.9  300.94  6089.4  297.84  6235.3  294.17  6977.5   294.6  8450.1  327.93
#Mann= 8 ,-1 , 0
  2267.9     .07       0  4729.1     .12       0  4869.1      .1       0
    4943     .05       0  5023.8      .1       0  5070.8     .07       0
  6089.4    .035       0  6235.3     .07       0
Bank Sta=4943,5023.8
XS Rating Curve= 0 ,0
Exp/Cntr=0.3,0.1

Type RM Length L Ch R = 1 ,284244  ,2466,2466,2466
BEGIN DESCRIPTION:
C20436
END DESCRIPTION:
XS GIS Cut Line= 3
       2391973.6     13664130.03      2389722.26     13663082.38
      2386133.47      13662324.5
#Sta/Elev= 30
  1966.5  323.52  2257.1  328.74  2800.9     316  3420.9  298.43  4089.2  286.19
  4154.4  282.87    4204  281.01  4261.5  288.05  4630.8  286.99    4727   282.5
  4909.1  276.73  4968.1  272.04  4981.2  267.36  4982.7  266.36  5062.1  267.36
  5070.3   280.9  5173.8  287.98  5273.7  291.29  5429.8  292.76  5685.9  294.87
    5767  294.95  5814.3     295  6104.1  295.88  6303.6  295.65  6511.4  297.08
  6655.4  293.04  6757.8  290.94  7121.3  291.73  7946.6  308.94  8117.6   318.2
#Mann= 20 ,-1 , 0
  1966.5     .05       0  2257.1     .07       0  2800.9     .05       0
  4089.2     .07       0  4154.4     .12       0  4261.5     .07       0
    4727     .12       0  4909.1      .1       0  4981.2     .05       0
  5062.1      .1       0  5173.8     .05       0  5273.7     .07       0
  5429.8     .05       0  5685.9     .07       0    5767     .05       0
  5814.3     .07       0  6104.1    .035       0  6303.6     .07       0
  6655.4    .035       0  6757.8     .07       0
Bank Sta=4981.2,5062.1
XS Rating Curve= 0 ,0
Exp/Cntr=0.3,0.1

Type RM Length L Ch R = 1 ,281778  ,2517,2517,2517
BEGIN DESCRIPTION:
SANDIES CREEK 189.0
END DESCRIPTION:
XS GIS Cut Line= 3
      2393957.52      13663037.8      2390390.98     13661187.66
      2386400.95     13661611.18
#Sta/Elev= 30
  1303.4  324.33  1550.9  319.55  1660.2  314.67  2007.7  304.23  2213.2  299.84
  2293.5  298.61    2534  296.94  2643.2   296.8  2752.4  294.58  2861.6   294.2
  3082.6  293.33  3231.8   292.6  3992.3  285.61  4401.3  291.44  4792.3   274.5
  4832.3  267.17  4854.7  276.55    4921  275.46  4980.8  264.74  4982.3  263.74
  5061.7  264.74  5081.5   278.3  5169.5  281.71  6945.2  289.55  7402.6  291.18
  7751.4  290.79  7850.7  289.84  7941.9   283.7  8193.3   292.6  9333.7  305.96
#Mann= 20 ,-1 , 0
  1303.4     .07       0  1550.9     .07       0  1660.2     .12       0
  2007.7     .07       0  2213.2     .07       0  2293.5     .12       0
    2534     .07       0  2643.2     .07       0  2752.4     .05       0
  2861.6     .05       0  3082.6     .05       0  3231.8     .07       0
  4792.3      .1       0  4980.8     .05       0  5061.7      .1       0
  5169.5     .07       0  6945.2     .07       0  7402.6     .05       0
  7751.4    .035       0  7850.7     .07       0
Bank Sta=4980.8,5061.7
XS Rating Curve= 0 ,0
Exp/Cntr=0.3,0.1

Type RM Length L Ch R = 1 ,279261  ,2860,2860,2860
BEGIN DESCRIPTION:
SANDIES CREEK 191.0
END DESCRIPTION:
XS GIS Cut Line= 3
      2394536.89     13661700.18      2391750.72      13659136.9
      2387649.23     13655771.01
#Sta/Elev= 30
  1894.9  325.64  2512.9  305.95  3124.1   287.3  3497.9  286.03  3793.1  285.02
    3924  284.57    4818  282.56  4894.2  281.66  4964.4  270.39  4966.6  262.78
  4968.1  261.78  5047.7  262.78  5275.9   278.1  5558.8  279.67  5608.5  283.09
  5829.8  283.12    6715  282.15  7694.1  281.07  7931.4  279.38    8067   272.5
  8087.8  266.69  8151.7  283.75  8181.4  288.14  8440.7  292.65  8502.9  293.73
  8823.5  295.92  9526.1  298.37  9864.6  298.21 10148.8  303.61 10986.6  320.28
#Mann= 20 ,-1 , 0
  1894.9     .05       0  2512.9     .07       0  3497.9     .12       0
  3793.1     .07       0    3924     .05       0    4818     .07       0
  4894.2      .1       0  4966.6     .05       0  5047.7      .1       0
  5275.9     .12       0  5608.5     .07       0  5829.8     .05       0
    6715     .05       0  7694.1      .1       0  8181.4     .07       0
  8440.7     .05       0  8502.9    .035       0  8823.5     .05       0
  9526.1     .07       0 10148.8     .05       0
Bank Sta=4966.6,5047.7
XS Rating Curve= 0 ,0
Exp/Cntr=0.3,0.1

Type RM Length L Ch R = 1 ,276401  ,1777,1777,1777
BEGIN DESCRIPTION:
C20435
END DESCRIPTION:
XS GIS Cut Line= 3
      2396008.25     13660385.18      2393578.57     13658089.23
      2390948.24     13654879.35
#Sta/Elev= 30
   578.4  333.86   821.3  345.93  1111.3  320.66    1554  294.62  2264.3  282.24
  3042.7  284.86  3916.1   279.1    4048  280.32  4077.9  280.21  4530.4  280.09
  4737.1  279.92  4849.7  271.06  4935.2  271.99  4936.2  259.75  4937.7  258.45
  5036.9  259.75  5042.1  269.82    5050  271.29  5124.1  273.28  5219.6  274.61
  5284.9  281.44  5497.1  280.97  5962.9   295.5  6885.3  300.93  6914.7  300.86
  7015.8  300.95  7064.7  301.13  7172.6  300.58  7217.2  300.47  8071.2  299.96
#Mann= 18 ,-1 , 0
   578.4     .07       0    1554     .05       0  3916.1     .07       0
    4048     .05       0  4077.9     .07       0  4530.4     .12       0
  4849.7      .1       0  4936.2     .05       0  5036.9      .1       0
  5124.1     .07       0  5284.9     .05       0  5962.9     .07       0
  6885.3     .05       0  6914.7     .07       0  7015.8     .05       0
  7064.7     .07       0  7172.6     .05       0  7217.2     .07       0
Bank Sta=4936.2,5036.9
XS Rating Curve= 0 ,0
Exp/Cntr=0.3,0.1

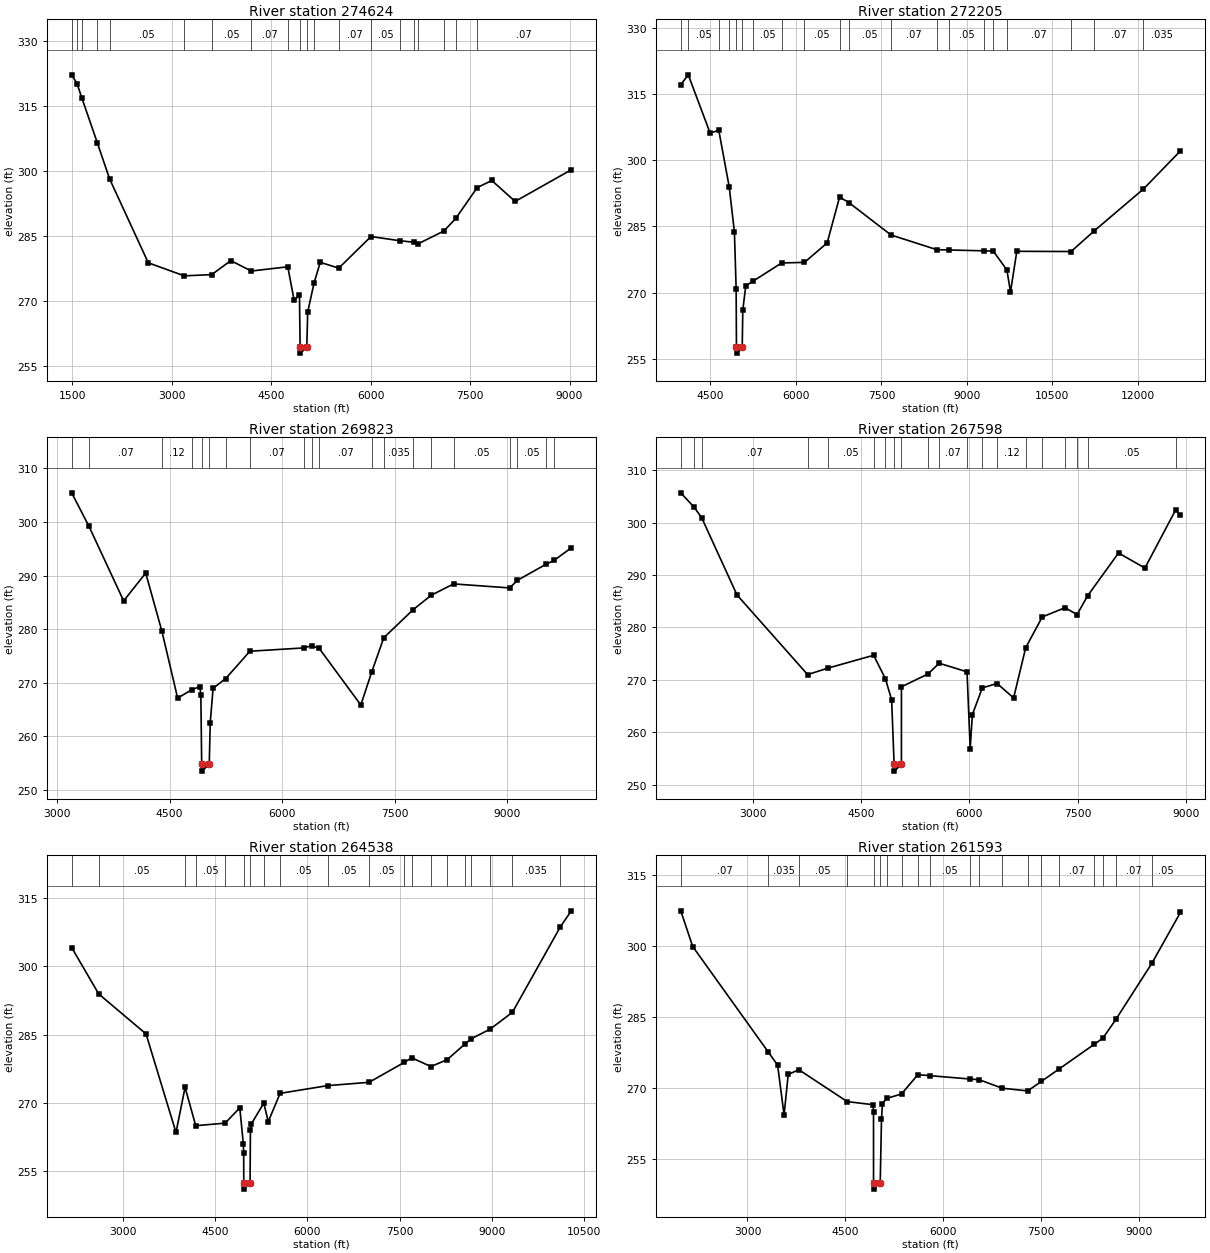
Type RM Length L Ch R = 1 ,274624  ,2419,2419,2419
BEGIN DESCRIPTION:
C20434
END DESCRIPTION:
XS GIS Cut Line= 4
      2396564.79     13658690.54      2394916.02     13657487.38
      2393868.35     13655659.54      2390836.77     13654143.75
#Sta/Elev= 30
  1490.1  322.18  1570.9  320.17  1644.7  316.81    1878  306.47  2062.8  298.16
    2646  278.81  3188.6   275.8    3603  276.08  3891.2  279.32  4198.9  276.91
  4750.4  277.89  4846.3  270.14  4926.8  271.38  4936.4  259.27  4937.9  257.97
  5037.2  259.27  5050.6  267.42  5145.1  274.05  5239.8  278.92  5519.2  277.58
  6005.6  284.87  6446.1  283.89  6647.2  283.57  6712.2  283.16  7105.7  286.15
  7285.5  289.07  7607.4  296.16  7827.9   297.8  8179.7  292.97  9027.4  300.28
#Mann= 20 ,-1 , 0
  1490.1     .05       0  1570.9     .07       0  1644.7     .05       0
    1878     .07       0  2062.8     .05       0  3188.6     .07       0
    3603     .05       0  4198.9     .07       0  4750.4     .12       0
  4936.4     .05       0  5037.2      .1       0  5145.1     .05       0
  5519.2     .07       0  6005.6     .05       0  6446.1     .07       0
  6647.2     .05       0  6712.2     .07       0  7105.7    .035       0
  7285.5     .05       0  7607.4     .07       0
Bank Sta=4936.4,5037.2
XS Rating Curve= 0 ,0
Exp/Cntr=0.3,0.1

Type RM Length L Ch R = 1 ,272205  ,2382,2382,2382
BEGIN DESCRIPTION:
SANDIES CREEK 196.0
END DESCRIPTION:
XS GIS Cut Line= 3
       2396832.4       13657531.        2396275.       13656675.
      2392753.82     13649774.79
#Sta/Elev= 30
  3979.1   317.1  4110.8  319.32    4495   306.1  4645.9  306.78  4829.6  293.92
  4920.6  283.71  4950.8  270.91  4956.5  257.59    4958  256.29  5057.4  257.59
  5067.9  266.09    5120  271.54    5250  272.61  5749.7  276.71  6149.7  276.84
  6547.9  281.25  6765.9  291.64  6927.4   290.4  7669.7  283.04  8472.6  279.72
  8693.3  279.65  9301.1  279.46  9463.4   279.4  9701.9  275.13    9765  270.16
  9876.1  279.35 10828.2   279.3 11238.6  284.02 12097.5  293.45 12747.3  302.09
#Mann= 20 ,-1 , 0
  3979.1    .035       0  4110.8     .05       0  4645.9     .07       0
  4829.6     .12       0  4956.5     .05       0  5057.4     .12       0
    5250     .05       0  5749.7     .07       0  6149.7     .05       0
  6765.9     .07       0  6927.4     .05       0  7669.7     .07       0
  8472.6     .07       0  8693.3     .05       0  9301.1     .05       0
  9463.4     .07       0  9701.9     .07       0 10828.2     .05       0
 11238.6     .07       0 12097.5    .035       0
Bank Sta=4956.5,5057.4
XS Rating Curve= 0 ,0
Exp/Cntr=0.3,0.1

Type RM Length L Ch R = 1 ,269823  ,2225,2225,2225
BEGIN DESCRIPTION:
SANDIES CREEK 197.0
END DESCRIPTION:
XS GIS Cut Line= 3
      2398304.22     13656395.13      2397256.55     13654478.12
      2396275.77     13650109.17
#Sta/Elev= 30
  3194.8  305.44  3423.7  299.25  3888.1  285.26  4182.2  290.46    4398  279.61
    4608  267.11  4796.4  268.67  4904.3  269.25  4917.5  267.72  4928.6  254.77
  4930.1  253.47  5029.6  254.77  5042.7  262.52  5080.6  268.94  5248.3  270.75
  5571.5  275.86    6292  276.48  6393.6   276.9  6495.2  276.39  7050.5  265.82
  7195.1  271.95  7356.7  278.38  7748.1  283.62  7991.1  286.33  8287.7  288.43
  9035.5  287.68  9137.1  289.09  9514.5  292.06  9625.9  292.81  9857.1  295.17
#Mann= 20 ,-1 , 0
  3194.8    .035       0  3423.7     .07       0    4398     .12       0
  4796.4      .1       0  4928.6     .05       0  5029.6      .1       0
  5248.3     .07       0  5571.5     .07       0    6292     .07       0
  6393.6    .063       0  6495.2     .07       0  7195.1     .07       0
  7356.7    .035       0  7748.1     .05       0  7991.1     .05       0
  8287.7     .05       0  9035.5    .035       0  9137.1     .05       0
  9514.5    .035       0  9625.9     .05       0
Bank Sta=4928.6,5029.6
XS Rating Curve= 0 ,0
Exp/Cntr=0.3,0.1

Type RM Length L Ch R = 1 ,267598  ,3060,3060,3060
BEGIN DESCRIPTION:
SANDIES CREEK 198.0
END DESCRIPTION:
XS GIS Cut Line= 3
      2399619.37     13656595.73      2398683.16     13653408.16
      2398482.55     13649819.37
#Sta/Elev= 30
  2006.8  305.68  2191.7  302.93  2295.2  300.96  2785.3  286.19    3763  270.99
  4049.9  272.25  4676.6  274.68  4838.7  270.23  4925.8   266.2    4960  253.87
  4961.5  252.57  5061.1  253.87  5061.4  268.66  5427.6   271.1  5584.6  273.16
  5969.2  271.52  6013.2  256.88  6043.3  263.36    6181  268.46  6386.2  269.29
  6614.2  266.54  6781.5  276.12  7010.6  281.99  7326.5  283.76  7492.3  282.44
  7639.9  286.06  8066.4   294.2  8431.8  291.33  8856.6   302.4  8923.4  301.37
#Mann= 20 ,-1 , 0
  2006.8     .07       0  2191.7    .035       0  2295.2     .07       0
    3763     .12       0  4049.9     .05       0  4676.6     .12       0
  4838.7      .1       0    4960     .05       0  5061.1      .1       0
  5427.6     .12       0  5584.6     .07       0  5969.2      .1       0
    6181      .1       0  6386.2     .12       0  6781.5     .07       0
  7010.6     .05       0  7326.5     .07       0  7492.3     .12       0
  7639.9     .05       0  8856.6     .05       0
Bank Sta=4960,5061.1
XS Rating Curve= 0 ,0
Exp/Cntr=0.3,0.1

Type RM Length L Ch R = 1 ,264538  ,2945,2945,2945
BEGIN DESCRIPTION:
C20433
END DESCRIPTION:
XS GIS Cut Line= 4
      2399820.29      13656661.3      2400354.97     13654232.92
      2400792.79     13653544.93      2402093.67     13648905.39
#Sta/Elev= 30
  2167.2  304.15  2607.4  293.95  3375.9  285.19  3863.2  263.55  4010.5  273.46
  4183.5  265.04  4660.9   265.6  4899.8  268.96  4957.3  261.06  4963.3  258.95
  4964.4  252.52  4965.9  251.12  5066.8  252.52  5072.5  264.02  5087.7  265.43
  5289.5  269.99  5362.5  265.94    5555  272.14  6328.6  273.84  7000.3  274.56
  7574.9  278.95  7693.8  279.94  8006.6  278.03    8270  279.53  8561.1  282.99
  8662.5  284.13  8965.2  286.21  9329.9  289.92 10111.7  308.74 10287.7   312.2
#Mann= 20 ,-1 , 0
  2167.2     .07       0  2607.4     .05       0  4010.5     .05       0
  4183.5     .05       0  4660.9      .1       0  4964.4     .05       0
  5066.8      .1       0  5289.5     .05       0    5555     .05       0
  6328.6     .05       0  7000.3     .05       0  7574.9     .07       0
  7693.8     .05       0  8006.6     .07       0    8270     .05       0
  8561.1    .035       0  8662.5     .05       0  8965.2     .07       0
  9329.9    .035       0 10111.7    .063       0
Bank Sta=4964.4,5066.8
XS Rating Curve= 0 ,0
Exp/Cntr=0.3,0.1

Type RM Length L Ch R = 1 ,261593  ,2831,2831,2831
BEGIN DESCRIPTION:
C20432
END DESCRIPTION:
XS GIS Cut Line= 3
      2400088.75     13657798.08       2401759.3      13655993.9
      2404723.98     13651714.05
#Sta/Elev= 30
    1977  307.43  2160.3  299.88    3318   277.6  3462.7   274.8  3561.9  264.26
  3625.4  272.83  3788.3  273.83  4530.2  267.09    4928  266.43    4934  264.83
  4934.3  249.98  4935.8  248.58  5036.8  249.98  5056.3  263.38  5071.2  266.68
  5135.5  267.76  5363.5   268.7  5614.2  272.78  5801.4  272.57  6418.7  271.86
  6555.9  271.71  6908.3  269.92  7299.2  269.35  7508.3  271.35  7776.2  273.94
  8317.9  279.19  8452.9   280.5  8655.3  284.54  9203.2  296.32  9642.2  307.09
#Mann= 20 ,-1 , 0
    1977     .07       0    3318    .035       0  3788.3     .05       0
  4530.2      .1       0  4934.3     .05       0  5036.8      .1       0
  5135.5     .12       0  5363.5     .12       0  5614.2     .07       0
  5801.4     .05       0  6418.7    .035       0  6555.9     .05       0
  6908.3     .12       0  7299.2     .07       0  7508.3     .12       0
  7776.2     .07       0  8317.9     .07       0  8452.9     .12       0
  8655.3     .07       0  9203.2     .05       0
Bank Sta=4934.3,5036.8
XS Rating Curve= 0 ,0
Exp/Cntr=0.3,0.1