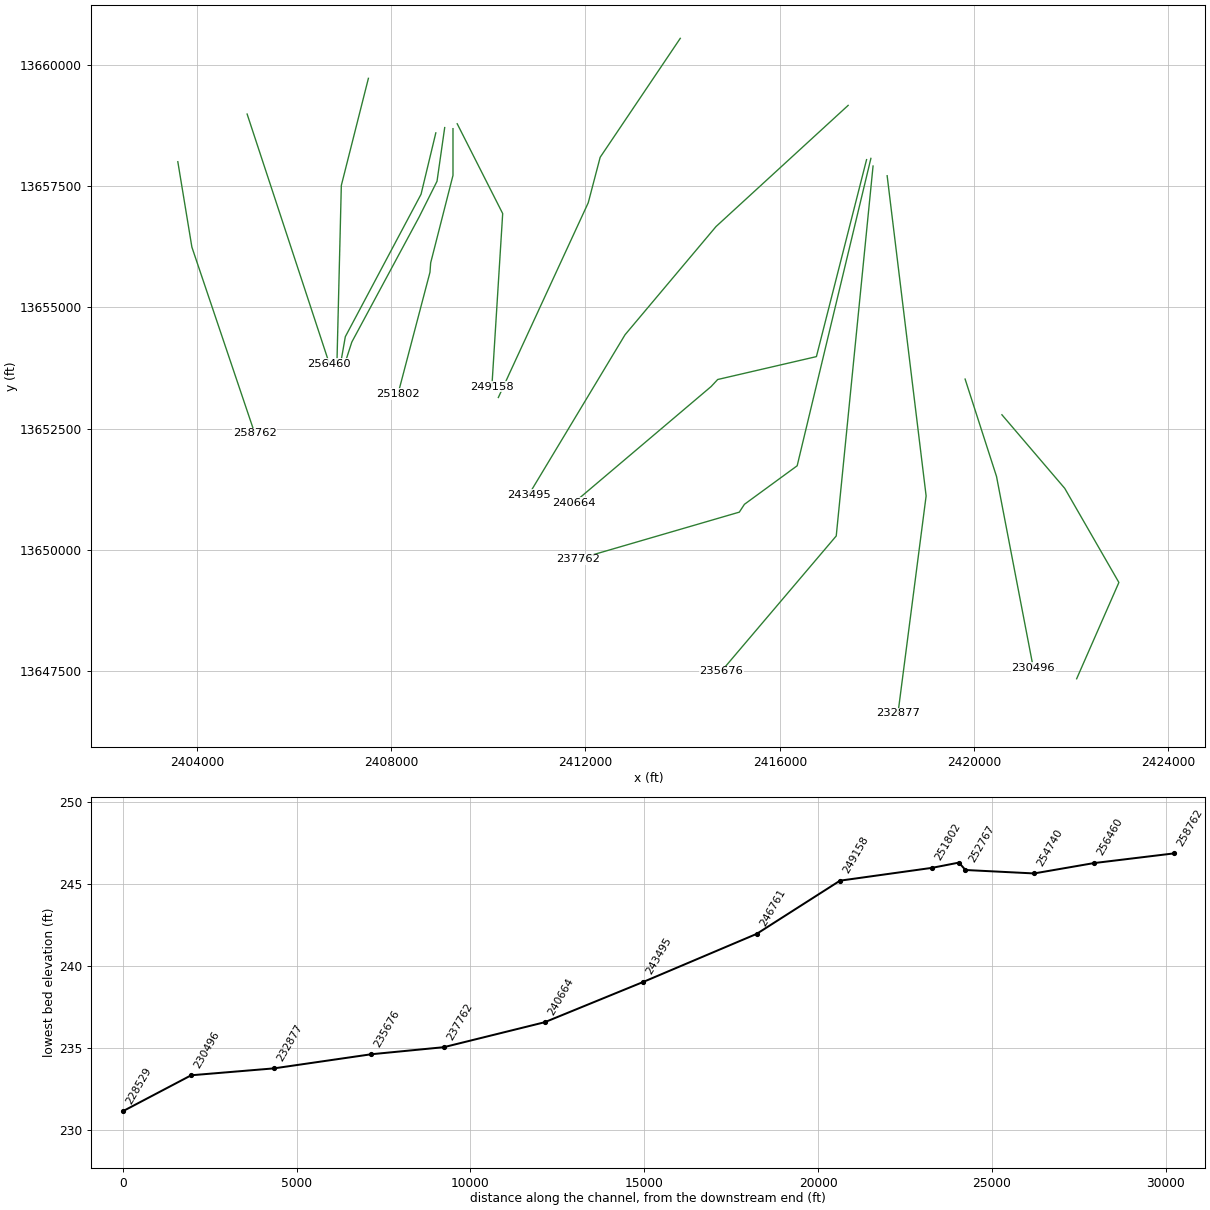
HEC-RAS study SANDIES CREEK.prj: SANDIES CREEK Base Level Engineering

--- SANDIES CREEK.g01 (geometry) --- (continued)

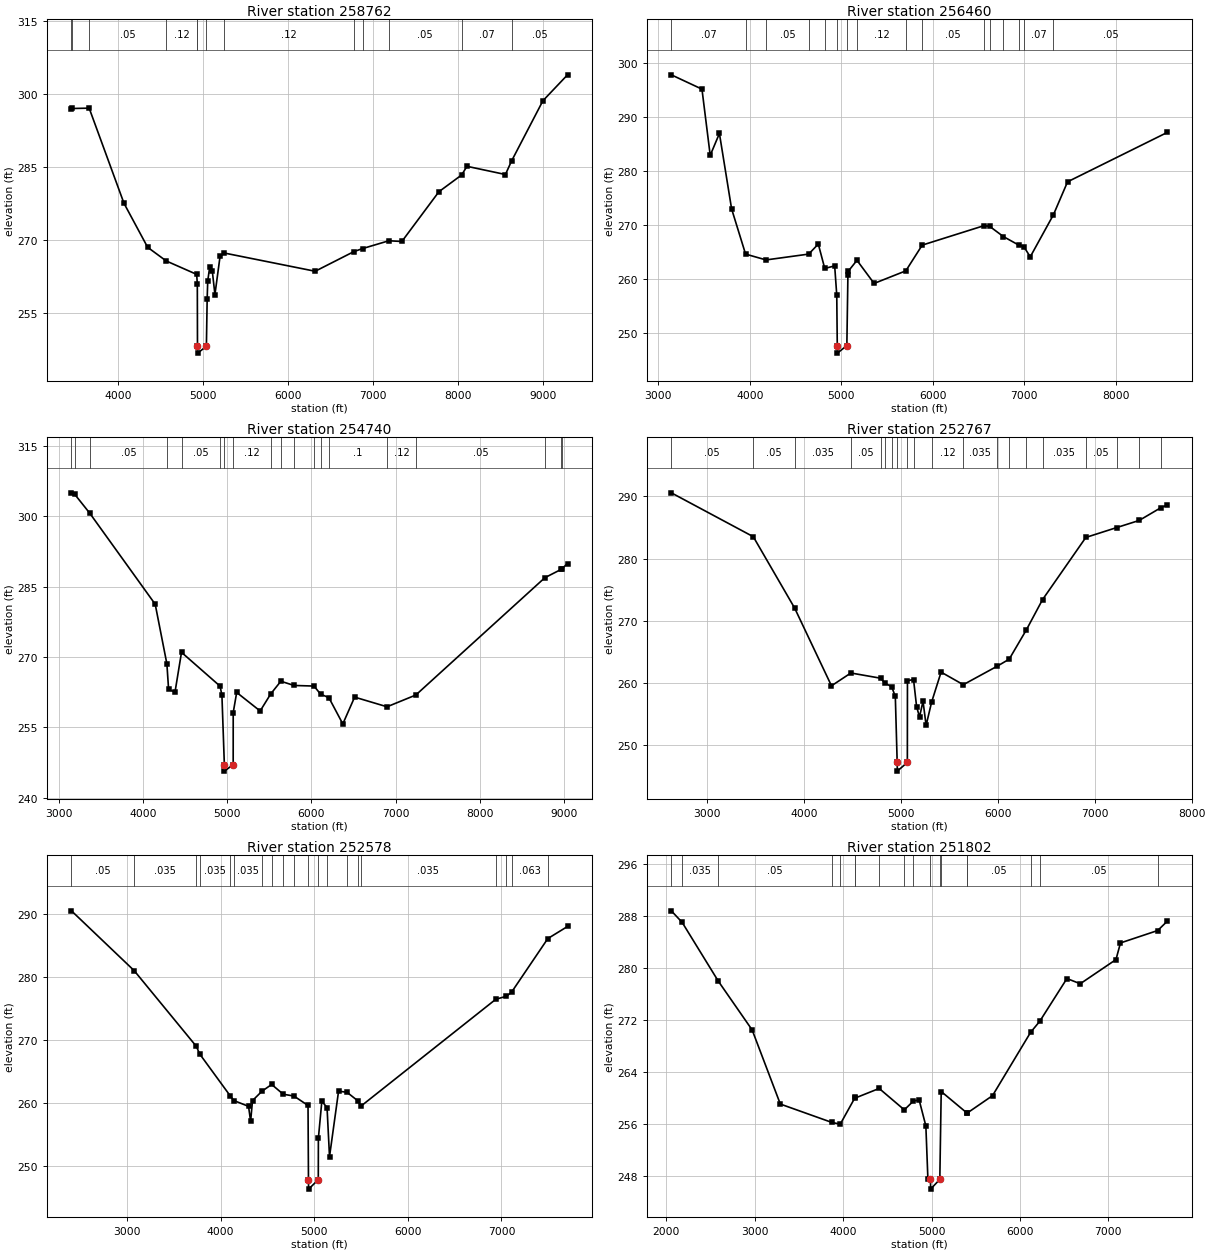
Type RM Length L Ch R = 1 ,258762  ,2302,2302,2302
BEGIN DESCRIPTION:
C20431
END DESCRIPTION:
XS GIS Cut Line= 3
      2403609.72      13657998.3      2403899.21      13656239.1
      2405192.08     13652405.07
#Sta/Elev= 30
  3456.5  296.97  3465.5     297  3664.5  297.07  4073.5  277.57  4351.7  268.55
  4570.1  265.75  4927.8     263  4935.3  261.01  4937.2  248.26  4938.7  246.86
  5041.9  248.26    5051  258.03  5057.7  261.66  5081.4  264.59  5111.8  263.61
  5142.2  258.87    5203  266.76    5254  267.37  6320.1  263.64  6774.1  267.66
  6877.1  268.29  7185.9  269.89  7338.6  269.74    7774  279.94  8041.5  283.38
  8103.6  285.15  8555.7  283.47  8627.2  286.22  8996.3  298.59  9285.5   303.9
#Mann= 13 ,-1 , 0
  3456.5     .05       0  3465.5     .07       0  3664.5     .05       0
  4570.1     .12       0  4927.8      .1       0  4937.2     .05       0
  5041.9      .1       0    5254     .12       0  6774.1    .035       0
  6877.1     .07       0  7185.9     .05       0  8041.5     .07       0
  8627.2     .05       0
Bank Sta=4937.2,5041.9
XS Rating Curve= 0 ,0
Exp/Cntr=0.3,0.1

Type RM Length L Ch R = 1 ,256460  ,1720,1720,1720
BEGIN DESCRIPTION:
C20430
END DESCRIPTION:
XS GIS Cut Line= 2
      2405036.17     13658980.47      2406730.15     13653831.68
#Sta/Elev= 30
  3143.2  297.78    3478  295.13  3568.1  282.87  3668.7  286.93  3801.7  272.98
  3954.4   264.6  4178.4  263.52  4644.1   264.6  4749.1  266.46  4819.6  261.94
  4928.1  262.42  4950.8  257.01  4956.4  247.67  4957.9  246.27  5061.1  247.67
  5072.7  260.68    5078  261.46  5171.6  263.45  5358.9  259.17  5705.4   261.5
  5884.4  266.26  6557.5  269.85  6620.3  269.75  6771.7  267.84  6937.1  266.29
    6994     266  7065.1  264.09  7318.5  271.89  7472.8  277.98  8563.5  287.13
#Mann= 16 ,-1 , 0
  3143.2     .07       0  3954.4     .12       0  4178.4     .05       0
  4644.1     .12       0  4819.6      .1       0  4956.4     .05       0
  5061.1      .1       0  5171.6     .12       0  5705.4     .07       0
  5884.4     .05       0  6557.5     .07       0  6620.3     .05       0
  6771.7     .07       0  6937.1     .12       0    6994     .07       0
  7318.5     .05       0
Bank Sta=4956.4,5061.1
XS Rating Curve= 0 ,0
Exp/Cntr=0.3,0.1

Type RM Length L Ch R = 1 ,254740  ,1973,1973,1973
BEGIN DESCRIPTION:
C20429
END DESCRIPTION:
XS GIS Cut Line= 3
      2407532.61     13659716.46      2406975.34     13657509.67
      2406886.18     13653898.54
#Sta/Elev= 30
  3152.9  305.02  3192.1  304.69    3370  300.67  4146.8  281.25  4285.5  268.53
  4305.8  263.08  4381.8  262.49    4459  270.99  4916.8  263.77  4938.7  261.85
  4967.6  247.04  4969.1  245.64  5072.5  247.04  5072.8  258.13  5114.1  262.43
  5392.5  258.47  5518.3  262.12  5638.4  264.82  5794.3  263.92  6031.6  263.79
  6109.9  262.07  6208.5  261.31  6373.9  255.71    6514  261.43  6898.7  259.37
  7240.5  261.88  8772.1  286.91  8969.3  288.72  8969.7  288.75  9041.2  289.93
#Mann= 19 ,-1 , 0
  3152.9     .05       0  3192.1     .07       0    3370     .05       0
  4285.5     .07       0    4459     .05       0  4916.8     .12       0
  4967.6     .05       0  5072.5     .12       0  5518.3     .07       0
  5638.4    .035       0  5794.3     .07       0  6031.6     .12       0
  6109.9     .07       0  6208.5      .1       0  6898.7     .12       0
  7240.5     .05       0  8772.1    .035       0  8969.3    .063       0
  8969.7    .035       0
Bank Sta=4967.6,5072.5
XS Rating Curve= 0 ,0
Exp/Cntr=0.3,0.1

Type RM Length L Ch R = 1 ,252767  ,189,189,189
BEGIN DESCRIPTION:
SAND21674
END DESCRIPTION:
XS GIS Cut Line= 4
      2408920.28     13658592.84      2408616.15     13657327.66
      2407057.51     13654393.04      2406972.27     13653905.92
#Sta/Elev= 30
  2630.9  290.57  3476.6  283.52  3903.7  272.04  4283.4  259.56  4483.7  261.62
  4790.4  260.78  4836.7  259.96  4903.6  259.44  4942.2  257.85  4961.4  247.25
  4962.9  245.85  5066.3  247.25  5067.4  260.39  5130.2  260.56    5162  256.19
    5192  254.56    5228  257.08  5259.9   253.2  5316.6  256.94  5414.5  261.76
  5643.7  259.74  5992.2   262.7  6117.2  263.84  6295.4  268.58  6461.2  273.41
  6907.9   283.4    7227  284.99  7458.2  286.13  7681.2  288.17  7749.5  288.64
#Mann= 20 ,-1 , 0
  2630.9     .05       0  3476.6     .05       0  3903.7    .035       0
  4483.7     .05       0  4790.4    .035       0  4836.7      .1       0
  4903.6    .035       0  4961.4    .035       0  5066.3    .063       0
  5130.2    .063       0  5316.6     .12       0  5643.7    .035       0
  5992.2     .12       0  6117.2    .035       0  6295.4     .05       0
  6461.2    .035       0  6907.9     .05       0    7227    .035       0
  7458.2    .063       0  7681.2    .063       0
Bank Sta=4961.4,5066.3
XS Rating Curve= 0 ,0
Exp/Cntr=0.3,0.1

Type RM Length L Ch R = 1 ,252578  ,776,776,776
BEGIN DESCRIPTION:
SAND21675
END DESCRIPTION:
XS GIS Cut Line= 5
      2409102.97     13658701.84      2408944.92     13657595.55
      2408579.62     13656864.94      2407191.46     13654283.45
       2407057.5      13653869.4
#Sta/Elev= 30
  2405.6  290.44  3075.8  280.95  3740.6  268.93  3774.4  267.76  4104.2  261.05
  4140.1  260.35  4297.6  259.43  4319.9  257.06    4340  260.34  4441.1  261.83
  4544.9   262.9  4668.3  261.35  4781.9  261.07  4933.2  259.57    4938   247.8
  4939.5   246.3    5043   247.8  5043.9  254.37  5080.9  260.24  5136.5  259.24
  5162.9  251.45  5259.6  261.84  5349.9  261.66  5463.5  260.33  5499.4  259.47
  6940.3  276.42  7053.9  276.89  7108.6  277.55  7495.5  286.04  7706.2  287.96
#Mann= 20 ,-1 , 0
  2405.6     .05       0  3075.8    .035       0  3740.6     .07       0
  3774.4    .035       0  4104.2     .05       0  4140.1    .035       0
  4441.1     .05       0  4544.9    .035       0  4668.3     .07       0
  4781.9    .063       0    4938    .063       0    5043    .063       0
  5136.5    .063       0  5349.9    .035       0  5463.5     .05       0
  5499.4    .035       0  6940.3    .063       0  7053.9     .05       0
  7108.6    .063       0  7495.5     .05       0
Bank Sta=4938,5043
XS Rating Curve= 0 ,0
Exp/Cntr=0.3,0.1

Type RM Length L Ch R = 1 ,251802  ,2644,2644,2644
BEGIN DESCRIPTION:
C20428
END DESCRIPTION:
XS GIS Cut Line= 5
       2409273.7     13658679.29       2409273.7     13657717.32
      2408814.39     13655914.89      2408799.76     13655720.24
      2408141.24     13653211.84
#Sta/Elev= 30
    2057   288.8  2179.6  287.02  2589.7  277.95  2971.3  270.47  3289.7  259.07
    3873  256.24  3967.7  255.98  4135.3  260.08  4139.4  260.01  4407.8  261.47
  4692.2  258.18  4794.6  259.53  4859.8   259.7  4935.8  255.71  4959.1  247.48
  4988.1  247.48  4989.6  245.98  5093.7  247.48  5109.4     261  5402.7  257.67
    5403  257.68  5689.6  260.36  6121.3  270.12  6223.9   271.8  6531.3  278.38
  6682.1  277.58  7086.1   281.3    7137  283.86  7557.9  285.77  7667.6  287.22
#Mann= 18 ,-1 , 0
    2057     .05       0  2179.6    .035       0  2589.7     .05       0
    3873     .12       0  3967.7     .05       0  4135.3     .07       0
  4139.4     .05       0  4407.8     .07       0  4692.2     .12       0
  4794.6      .1       0  4988.1     .05       0  5093.7      .1       0
  5109.4     .05       0  5402.7    .035       0    5403     .05       0
  6121.3    .035       0  6223.9     .05       0  7557.9     .07       0
Bank Sta=4988.1,5093.7
XS Rating Curve= 0 ,0
Exp/Cntr=0.3,0.1

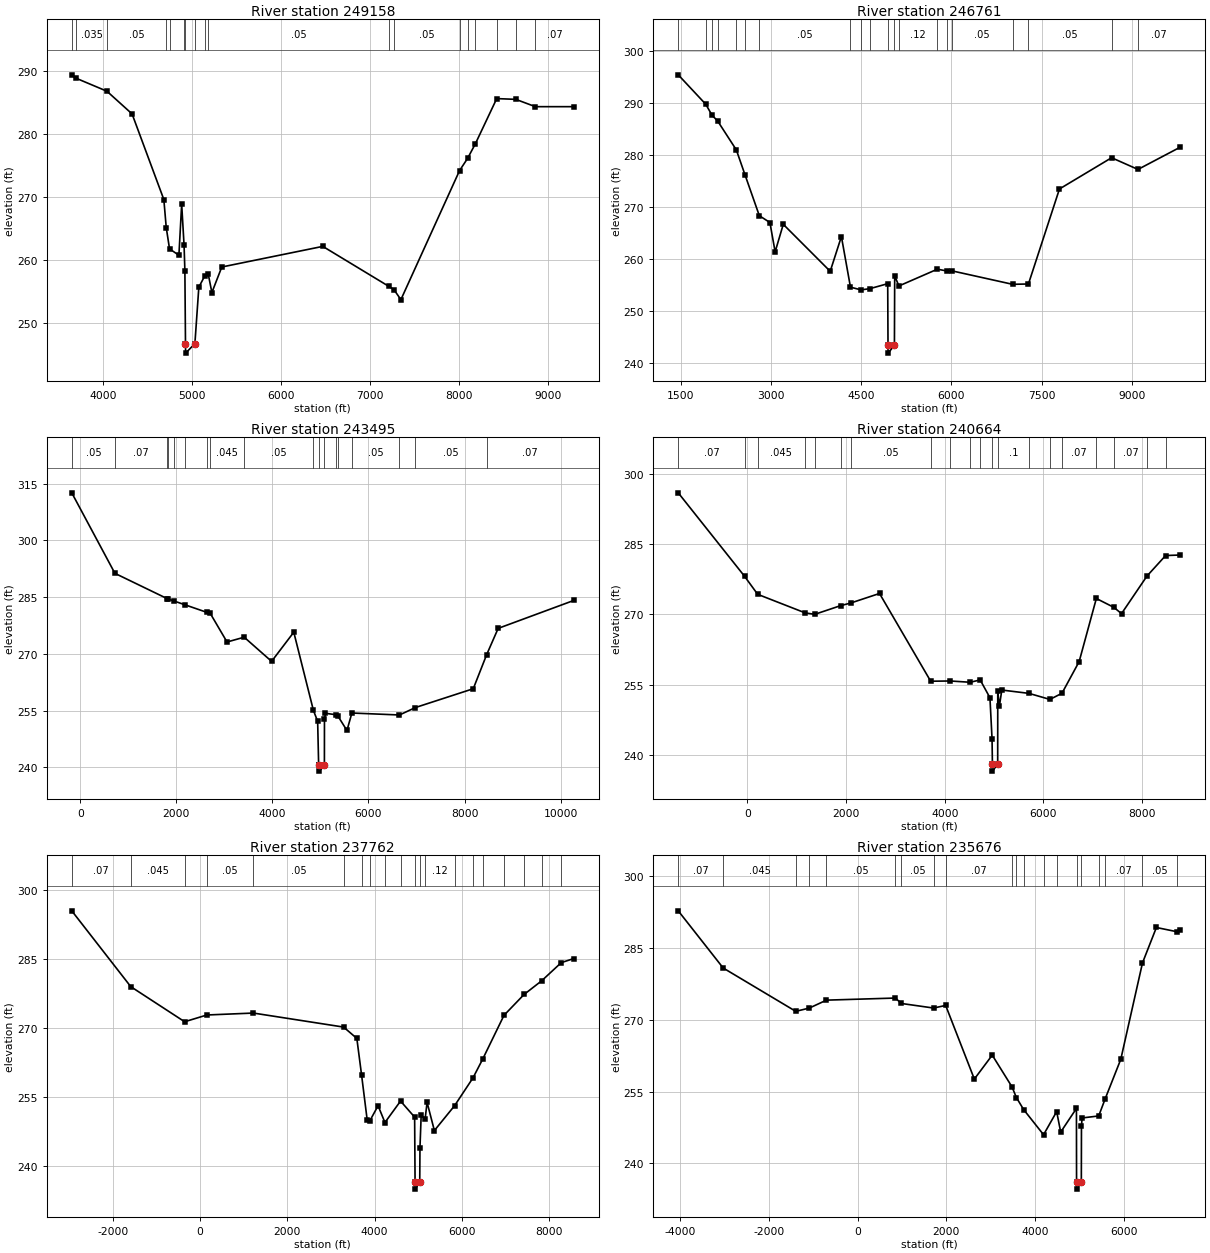
Type RM Length L Ch R = 1 ,249158  ,2397,2397,2397
BEGIN DESCRIPTION:
C20427
END DESCRIPTION:
XS GIS Cut Line= 3
      2409360.51     13658780.15      2410296.68     13656930.11
      2410073.77     13653363.59
#Sta/Elev= 30
  3646.4  289.34  3698.4  288.78  4041.8  286.74  4324.6  283.14  4681.9  269.56
  4708.9  265.12  4745.9  261.74  4851.4  260.72  4882.5  268.83  4909.3  262.33
  4918.6  258.28  4925.4   246.7  4926.9   245.2  5031.1   246.7  5075.5  255.66
  5140.5   257.4  5181.1  257.75  5222.3  254.81  5333.7  258.86  6469.7  262.13
  7213.5  255.78  7270.5  255.26  7348.1  253.68  8008.2  274.16  8097.5  276.07
  8185.6   278.4  8425.9  285.57  8640.3  285.45  8860.5  284.29  9293.3  284.29
#Mann= 18 ,-1 , 0
  3646.4     .05       0  3698.4    .035       0  4041.8     .05       0
  4708.9     .07       0  4745.9     .05       0  4909.3     .07       0
  4925.4     .05       0  5031.1     .07       0  5140.5     .07       0
  5181.1     .05       0  7213.5    .035       0  7270.5     .05       0
  8008.2    .035       0  8097.5     .07       0  8185.6     .05       0
  8425.9    .035       0  8640.3     .05       0  8860.5     .07       0
Bank Sta=4925.4,5031.1
XS Rating Curve= 0 ,0
Exp/Cntr=0.3,0.1

Type RM Length L Ch R = 1 ,246761  ,3266,3266,3266
BEGIN DESCRIPTION:
C20426
END DESCRIPTION:
XS GIS Cut Line= 4
      2413951.94     13660540.58      2412302.85     13658089.23
      2412057.65     13657153.02       2410207.5     13653140.65
#Sta/Elev= 30
  1462.1   295.5  1919.9  289.83  2023.1  287.73  2114.8  286.65  2427.1  281.06
  2573.2   276.2  2809.2   268.4  2984.9  267.09  3071.8  261.44  3206.9  266.74
  3986.7   257.7  4172.7  264.39  4323.2  254.65  4497.9  254.13  4645.2  254.36
  4941.9  255.32    4947  243.46  4948.5  241.96  5053.4  243.46    5058  256.83
  5127.7  254.88  5767.3  258.11    5931  257.75  6008.4  257.79  7015.8   255.2
  7279.7  255.26    7795  273.54  8661.3  279.55  9099.5   277.3  9802.7  281.59
#Mann= 20 ,-1 , 0
  1462.1     .05       0  1919.9    .035       0  2023.1     .05       0
  2114.8    .035       0  2427.1    .035       0  2573.2    .035       0
  2809.2     .05       0  4323.2      .1       0  4497.9     .05       0
  4645.2      .1       0    4947     .05       0  5053.4      .1       0
  5127.7     .12       0  5767.3     .05       0    5931     .12       0
  6008.4     .05       0  7015.8     .12       0  7279.7     .05       0
  8661.3    .035       0  9099.5     .07       0
Bank Sta=4947,5053.4
XS Rating Curve= 0 ,0
Exp/Cntr=0.3,0.1

Type RM Length L Ch R = 1 ,243495  ,2831,2831,2831
BEGIN DESCRIPTION:
C20425
END DESCRIPTION:
XS GIS Cut Line= 4
      2417407.46     13659159.21      2414687.96     13656662.62
      2412815.54     13654433.54      2410831.68     13651134.54
#Sta/Elev= 30
  -176.6  312.59   721.4  291.31  1808.5  284.63  1823.9  284.56  1960.1  283.96
  2187.9  282.96  2639.8  280.98  2700.9  280.84  3055.7  273.16  3412.6  274.43
  3983.5  268.04  4445.3  275.75  4854.1  255.08  4942.2  252.19    4963  240.61
  4975.8  240.53  4977.3  239.03  5082.7  240.53    5084   252.7  5105.3  254.32
  5322.7  253.94  5366.9  253.53  5552.2  249.77  5654.7  254.39  6645.6  253.87
    6978  255.84    8182  260.81  8460.2   269.8    8700  276.76 10275.8  284.15
#Mann= 18 ,-1 , 0
  -176.6     .05       0   721.4     .07       0  1808.5     .12       0
  1823.9     .07       0  1960.1     .12       0  2187.9     .07       0
  2639.8    .035       0  2700.9    .045       0  3412.6     .05       0
  4854.1     .12       0  4975.8     .05       0  5082.7     .12       0
  5322.7     .05       0  5366.9     .12       0  5654.7     .05       0
  6645.6     .07       0    6978     .05       0  8460.2     .07       0
Bank Sta=4975.8,5082.7
XS Rating Curve= 0 ,0
Exp/Cntr=0.3,0.1

Type RM Length L Ch R = 1 ,240664  ,2902,2902,2902
BEGIN DESCRIPTION:
C20424
END DESCRIPTION:
XS GIS Cut Line= 5
      2417786.51      13658041.3      2416754.15     13653982.58
      2414722.22     13653510.99      2414586.17      13653365.4
      2411760.59     13650969.47
#Sta/Elev= 30
 -1402.3  295.92     -59  278.14     208  274.28  1171.4  270.32  1364.2  270.01
  1888.1  271.86  2092.9  272.42  2677.8  274.46  3715.3  255.75  4112.3   255.8
    4514  255.53  4718.8  256.02  4916.4  252.23  4958.9   243.5  4966.6  238.08
  4968.1  236.58  5073.6  238.08  5074.9  253.58  5107.6  250.41  5157.1  253.87
  5707.2  253.16    6132  251.87  6376.3  253.18  6724.6  259.93  7073.3  273.39
  7430.1  271.49  7583.6  270.16  8100.1  278.18  8477.9  282.55  8775.5  282.66
#Mann= 20 ,-1 , 0
 -1402.3     .07       0     -59    .045       0     208    .045       0
  1171.4     .07       0  1364.2    .035       0  1888.1    .035       0
  2092.9     .05       0  3715.3     .12       0  4112.3     .05       0
    4514    .045       0  4718.8     .12       0  4966.6     .05       0
  5073.6      .1       0  5707.2     .12       0    6132     .12       0
  6376.3     .07       0  7073.3    .035       0  7430.1     .07       0
  8100.1    .035       0  8477.9     .07       0
Bank Sta=4966.6,5073.6
XS Rating Curve= 0 ,0
Exp/Cntr=0.3,0.1

Type RM Length L Ch R = 1 ,237762  ,2086,2086,2086
BEGIN DESCRIPTION:
C20423
END DESCRIPTION:
XS GIS Cut Line= 5
      2417875.55     13658066.94      2416358.06     13651733.35
      2415272.07     13650939.05      2415167.04     13650778.12
      2411845.48     13649809.49
#Sta/Elev= 30
 -2941.5  295.55 -1588.8  279.07  -353.8  271.44   156.1  272.91  1221.5  273.33
  3290.9  270.28  3593.8  267.82  3703.2  259.82  3830.1  250.17  3891.3   249.9
    4081  253.19  4237.8  249.54    4596   254.2  4918.7  250.71  4928.9  236.56
  4930.4  235.06  5035.9  236.56  5041.1  244.03  5068.9  251.13  5158.5  250.27
  5204.5  253.91  5371.5  247.79  5834.4  253.19  6257.9  259.26  6480.3  263.34
  6967.7  272.84    7428  277.37  7832.2  280.35  8280.2  284.29  8568.9  285.18
#Mann= 20 ,-1 , 0
 -2941.5     .07       0 -1588.8    .045       0  -353.8     .07       0
   156.1     .05       0  1221.5     .05       0  3290.9     .07       0
  3703.2     .12       0  3891.3     .07       0  4237.8     .07       0
    4596     .12       0  4928.9     .05       0  5035.9      .1       0
  5158.5     .12       0  5834.4     .07       0  6257.9    .035       0
  6480.3     .05       0  6967.7     .05       0    7428    .035       0
  7832.2     .07       0  8280.2     .12       0
Bank Sta=4928.9,5035.9
XS Rating Curve= 0 ,0
Exp/Cntr=0.3,0.1

Type RM Length L Ch R = 1 ,235676  ,2799,2799,2799
BEGIN DESCRIPTION:
C20422
END DESCRIPTION:
XS GIS Cut Line= 3
      2417920.02     13657909.77      2417162.24     13650287.45
      2414799.42      13647501.1
#Sta/Elev= 30
 -4043.1  292.74 -3030.1   280.8 -1394.4  271.75 -1088.6  272.44  -703.3  274.09
     852  274.53   981.1   273.4    1711  272.44  1982.6  272.99    2629  257.61
  3032.2  262.61  3477.8  255.98  3577.1  253.74  3740.8  251.23  4188.8  245.99
  4484.1  250.82  4574.7  246.54  4929.5  251.48  4932.2  236.13  4933.7  234.63
  5039.7  236.13  5042.7  247.82    5057  249.49  5431.3  249.91  5578.4  253.52
  5929.1  261.75  6417.9  281.87    6731  289.26  7197.1  288.37  7270.1  288.65
#Mann= 20 ,-1 , 0
 -4043.1     .07       0 -3030.1    .045       0 -1394.4     .07       0
 -1088.6    .035       0  -703.3     .05       0     852    .035       0
   981.1     .05       0    1711    .035       0  1982.6     .07       0
  3477.8     .05       0  3577.1     .07       0  3740.8     .12       0
  4188.8      .1       0  4484.1     .12       0  4932.2     .05       0
  5039.7     .12       0  5431.3     .07       0  5578.4     .07       0
  6417.9     .05       0  7197.1    .035       0
Bank Sta=4932.2,5039.7
XS Rating Curve= 0 ,0
Exp/Cntr=0.3,0.1

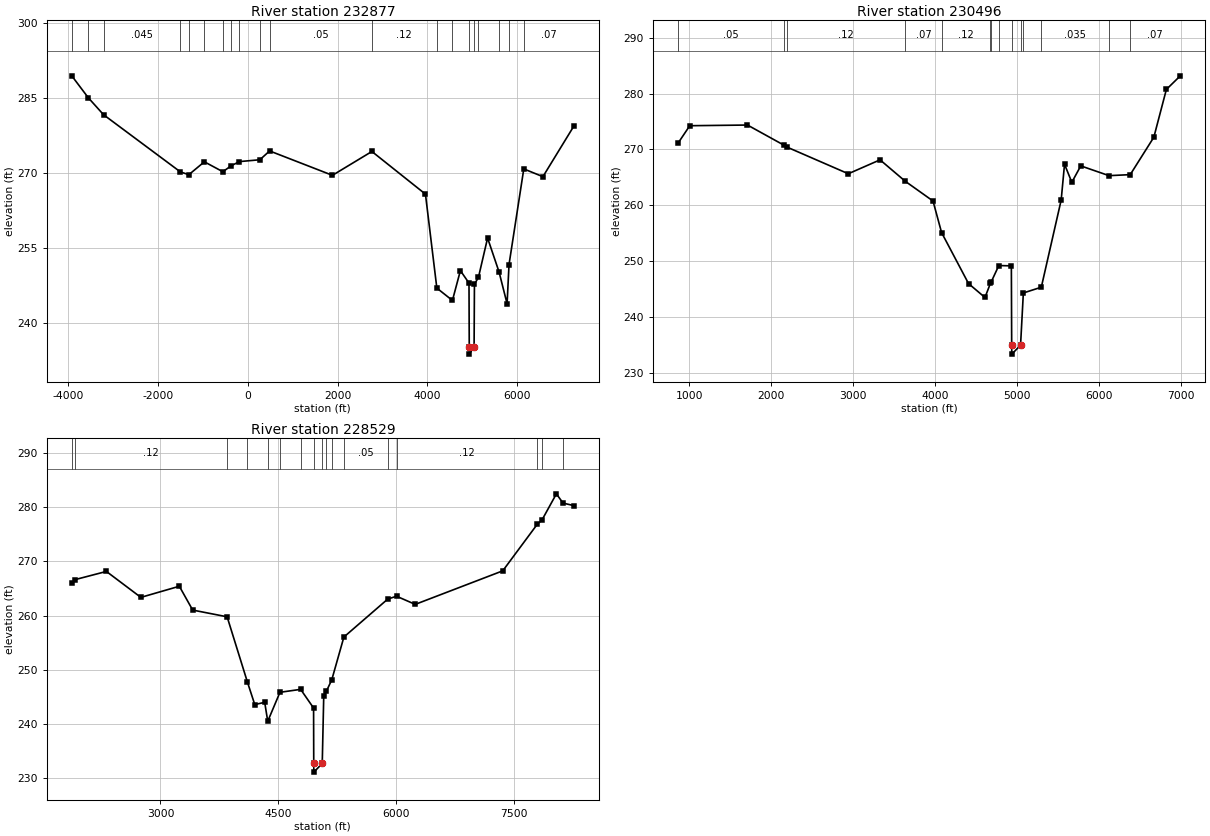
Type RM Length L Ch R = 1 ,232877  ,2381,2381,2381
BEGIN DESCRIPTION:
C20421
END DESCRIPTION:
XS GIS Cut Line= 3
      2418209.97     13657709.78      2419012.38     13651112.21
      2418432.82     13646631.73
#Sta/Elev= 30
 -3908.7  289.35 -3540.4  284.96 -3201.8  281.58 -1491.8  270.15 -1305.5  269.61
  -960.9  272.18    -550   270.2  -361.5   271.4  -181.6  272.22   273.9  272.59
   489.9  274.35  1886.5  269.48  2763.9  274.24  3954.8  265.72  4207.9  246.96
  4554.5  244.49  4731.2  250.45  4922.8  247.96  4928.5  235.27    4930  233.77
  5036.2  235.27  5043.8  247.72  5133.2  249.11  5336.2  256.96  5591.9  250.16
  5769.8  243.83  5812.7  251.66    6141  270.76  6566.3  269.21  7255.3  279.33
#Mann= 20 ,-1 , 0
 -3908.7     .07       0 -3540.4    .045       0 -3201.8    .045       0
 -1491.8    .035       0 -1305.5     .07       0  -960.9     .05       0
    -550     .05       0  -361.5     .07       0  -181.6     .05       0
   273.9    .035       0   489.9     .05       0  2763.9     .12       0
  4207.9      .1       0  4554.5     .12       0  4928.5     .05       0
  5036.2      .1       0  5133.2     .12       0  5591.9      .1       0
  5812.7     .12       0    6141     .07       0
Bank Sta=4928.5,5036.2
XS Rating Curve= 0 ,0
Exp/Cntr=0.3,0.1

Type RM Length L Ch R = 1 ,230496  ,1967,1967,1967
BEGIN DESCRIPTION:
C20420
END DESCRIPTION:
XS GIS Cut Line= 3
      2419814.85     13653519.63      2420461.28     13651513.45
      2421219.18     13647567.94
#Sta/Elev= 30
   867.4  271.15  1008.8  274.24  1712.8  274.36  2163.3  270.71  2194.9  270.41
  2942.8  265.64    3330  268.13  3638.8  264.28  3976.1  260.76  4080.6  255.11
  4409.4  245.98  4609.8  243.49  4676.9  246.04  4683.8  246.21  4778.9  249.21
  4931.8  249.15  4935.8  234.95  4937.3  233.35    5044  234.95  5078.1   244.3
  5297.3  245.33  5539.6  260.94  5580.4  267.34  5669.4  264.11  5778.4  267.05
  6123.1   265.3  6381.9  265.48  6669.9  272.18  6822.7  280.73  6992.8  283.17
#Mann= 14 ,-1 , 0
   867.4     .05       0  2163.3     .07       0  2194.9     .12       0
  3638.8     .07       0  4080.6     .12       0  4676.9    .035       0
  4683.8      .1       0  4778.9    .035       0  4935.8    .035       0
    5044    .035       0  5078.1     .07       0  5297.3    .035       0
  6123.1    .033       0  6381.9     .07       0
Bank Sta=4935.8,5044
XS Rating Curve= 0 ,0
Exp/Cntr=0.3,0.1

Type RM Length L Ch R = 1 ,228529  ,2177,2177,2177
BEGIN DESCRIPTION:
C20419
END DESCRIPTION:
XS GIS Cut Line= 4
      2420572.71     13652784.06      2421865.61     13651268.25
      2422980.15     13649328.95      2422110.79     13647345.03
#Sta/Elev= 30
  1870.7  266.01  1914.9  266.64  2311.6  268.14  2750.8  263.36  3240.5  265.41
  3410.7  261.02  3849.3  259.78  4106.9  247.79  4201.2  243.61  4327.9  244.02
  4366.5  240.53  4522.2  245.87  4785.7  246.41  4950.4  242.97  4952.4  232.76
  4953.9  231.16  5060.7  232.76  5079.8   245.2  5112.7  246.05  5181.9  248.16
  5336.3  256.05  5895.1  263.05  6006.8  263.57  6245.1  262.07  7359.6  268.25
  7798.1  276.81  7860.4  277.65  8042.8  282.44  8127.3  280.73  8265.8  280.27
#Mann= 17 ,-1 , 0
  1870.7     .07       0  1914.9     .12       0  3849.3     .05       0
  4106.9    .035       0  4366.5     .12       0  4522.2     .07       0
  4785.7      .1       0  4952.4     .05       0  5060.7      .1       0
  5112.7     .12       0  5181.9     .07       0  5336.3     .05       0
  5895.1    .035       0  6006.8     .12       0  7798.1     .07       0
  7860.4     .12       0  8127.3     .07       0
Bank Sta=4952.4,5060.7
XS Rating Curve= 0 ,0
Exp/Cntr=0.3,0.1