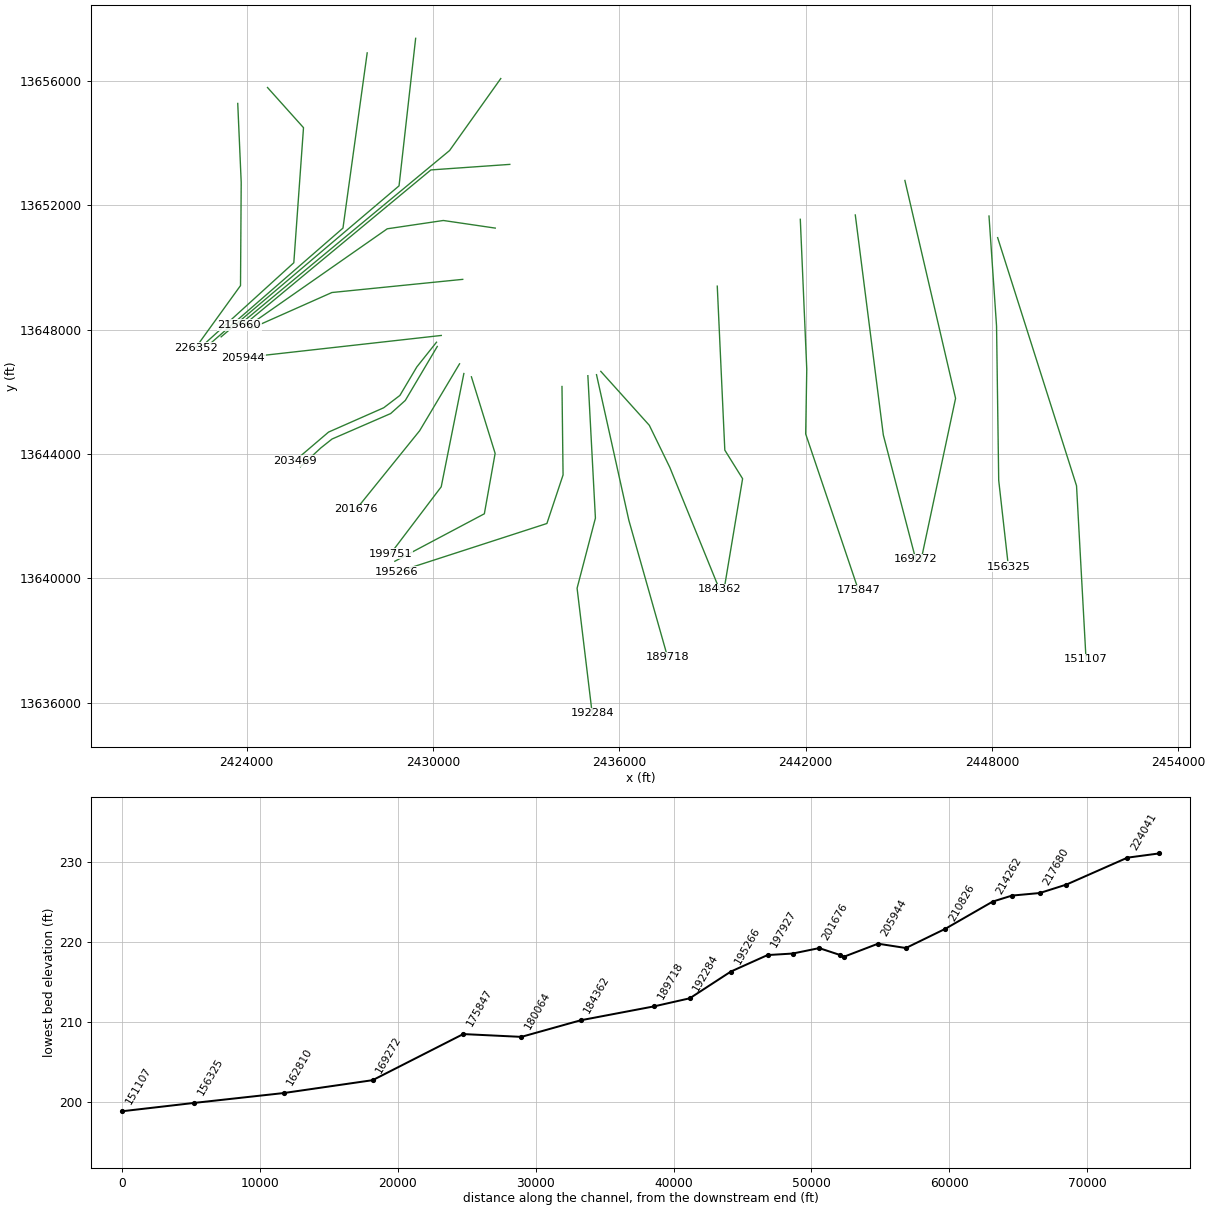
HEC-RAS study SANDIES CREEK.prj: SANDIES CREEK Base Level Engineering

--- SANDIES CREEK.g01 (geometry) --- (continued)

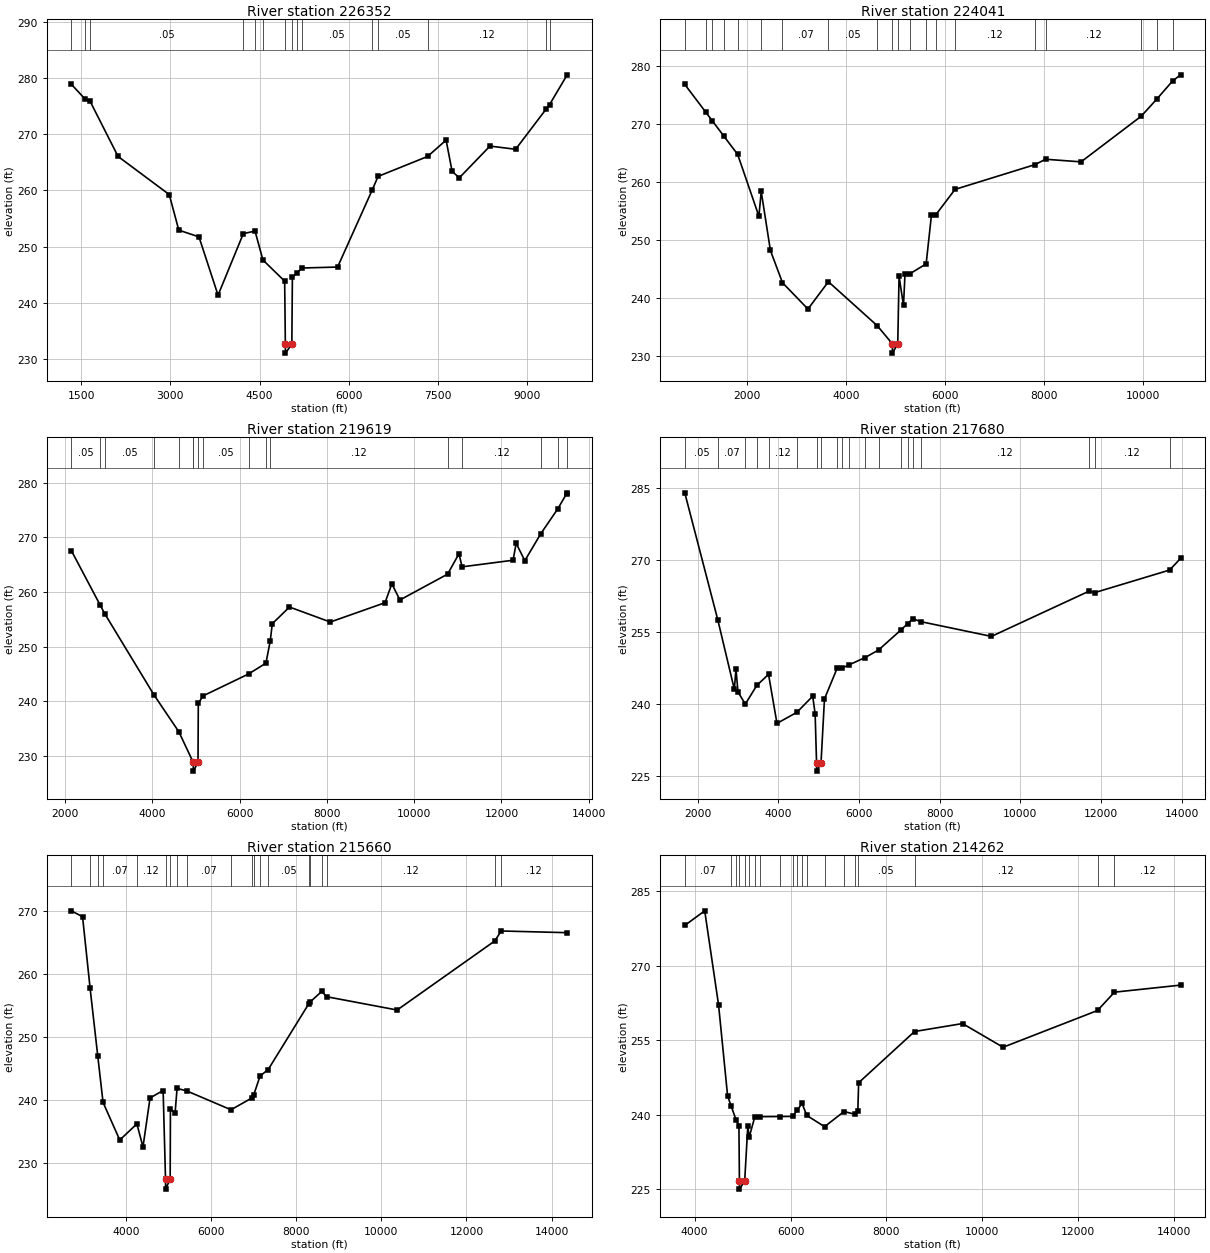
Type RM Length L Ch R = 1 ,226352  ,2311,2311,2311
BEGIN DESCRIPTION:
C20418
END DESCRIPTION:
XS GIS Cut Line= 4
      2423715.76     13655280.28       2423827.2     13652739.44
      2423804.91     13649418.11      2422355.98     13647411.91
#Sta/Elev= 30
  1334.1   278.9  1569.2  276.22  1648.7  275.89  2120.4  266.05    2981  259.27
  3141.1  252.94  3480.7  251.74  3801.7  241.36  4226.6  252.32  4423.7  252.77
  4556.6  247.62  4921.8  243.86  4933.7  232.65  4935.2  231.05  5042.7  232.65
  5051.8  244.56  5121.7  245.23  5211.9   246.2  5811.9  246.37  6394.1  260.08
  6492.7   262.5  7325.4  266.05  7637.3  268.96  7737.9   263.4  7859.4  262.25
  8374.6   267.9  8806.2  267.33  9315.6  274.43  9376.5  275.27  9673.5  280.58
#Mann= 15 ,-1 , 0
  1334.1     .05       0  1569.2    .035       0  1648.7     .05       0
  4226.6     .07       0  4423.7     .12       0  4556.6      .1       0
  4933.7     .05       0  5042.7      .1       0  5121.7     .12       0
  5211.9     .05       0  6394.1    .035       0  6492.7     .05       0
  7325.4     .12       0  9315.6     .07       0  9376.5     .12       0
Bank Sta=4933.7,5042.7
XS Rating Curve= 0 ,0
Exp/Cntr=0.3,0.1

Type RM Length L Ch R = 1 ,224041  ,4422,4422,4422
BEGIN DESCRIPTION:
C20417
END DESCRIPTION:
XS GIS Cut Line= 4
      2424674.24     13655793.29      2425833.37     13654500.41
       2425521.3     13650153.71      2422601.23     13647501.12
#Sta/Elev= 30
   732.1   276.8  1157.8  272.01  1286.8  270.56  1522.8   267.9  1802.6  264.75
    2233   254.1    2280  258.36    2466   248.2  2710.4  242.65  3225.9  238.11
  3639.9  242.82  4629.4  235.24  4935.1  232.12  4936.6  230.52  5044.1  232.12
  5070.6  243.75  5160.8  238.74  5190.9  244.15  5284.6  244.16    5619  245.89
  5727.3  254.37  5816.9  254.37  6204.1  258.72  7821.3  262.98  8037.3  263.91
  8755.3  263.46  9973.1  271.32   10288  274.26 10609.8   277.4 10771.4  278.45
#Mann= 20 ,-1 , 0
   732.1     .05       0  1157.8    .035       0  1286.8     .05       0
  1522.8    .035       0  1802.6     .05       0    2280     .05       0
  2710.4     .07       0  3639.9     .05       0  4629.4     .12       0
  4935.1     .05       0  5044.1     .12       0  5284.6     .12       0
    5619    .035       0  5816.9     .05       0  6204.1     .12       0
  7821.3     .07       0  8037.3     .12       0  9973.1     .07       0
   10288     .12       0 10609.8     .12       0
Bank Sta=4935.1,5044.1
XS Rating Curve= 0 ,0
Exp/Cntr=0.3,0.1

Type RM Length L Ch R = 1 ,219619  ,1939,1939,1939
BEGIN DESCRIPTION:
C20416
END DESCRIPTION:
XS GIS Cut Line= 3
      2427884.13     13656907.85      2427103.95     13651268.25
      2422824.09     13647545.66
#Sta/Elev= 30
  2140.6   267.6  2799.8  257.63  2907.3  256.01  4033.8  241.15  4605.5  234.37
  4929.1  228.86  4934.8  228.76  4936.3  227.16  5044.1  228.76  5050.9   239.6
  5160.9  240.96  6201.8  244.97  6601.2  246.96    6701  251.08  6746.9  254.19
  7140.6  257.25  8076.4   254.5  9330.7  258.04  9487.4  261.51  9671.5  258.54
   10765  263.28 11025.5  267.01 11097.3  264.62 12265.6  265.83 12336.8  268.93
 12535.2  265.75 12902.4  270.71 13291.5  275.26 13493.3  278.05 13506.2  278.19
#Mann= 17 ,-1 , 0
  2140.6     .05       0  2799.8    .035       0  2907.3     .05       0
  4033.8     .07       0  4605.5     .05       0  4929.1      .1       0
  4934.8     .05       0  5044.1      .1       0  5160.9     .05       0
  6201.8     .12       0  6601.2    .035       0    6701     .12       0
   10765     .07       0 11097.3     .12       0 12902.4     .07       0
 13291.5     .12       0 13493.3     .07       0
Bank Sta=4934.8,5044.1
XS Rating Curve= 0 ,0
Exp/Cntr=0.3,0.1

Type RM Length L Ch R = 1 ,217680  ,2020,2020,2020
BEGIN DESCRIPTION:
C20415
END DESCRIPTION:
XS GIS Cut Line= 3
      2429444.48     13657375.93       2428909.5     13652627.99
      2423180.78      13647768.6
#Sta/Elev= 30
  1683.4  283.98  2503.8   257.5  2912.1   243.1  2952.3  247.35  3002.6  242.55
    3184  240.05    3471  243.95  3759.5  246.22  3968.7  236.03  4462.6  238.33
  4854.3  241.69  4914.6  238.02  4950.2   227.7  4951.7   226.1  5059.5   227.7
  5146.1  241.12  5459.9   247.5  5586.2  247.55  5760.8  248.22  6155.7  249.73
  6486.4  251.29  7053.3  255.55  7208.1  256.78    7336   257.8  7526.9   257.2
  9283.7  254.12 11694.1  263.49 11854.4  263.25 13700.7  267.92 13973.5  270.35
#Mann= 20 ,-1 , 0
  1683.4     .05       0  2503.8     .07       0    3184     .05       0
    3471     .07       0  3759.5     .12       0  4462.6     .12       0
  4950.2     .05       0  5059.5      .1       0  5459.9     .05       0
  5586.2    .035       0  5760.8     .05       0  6155.7    .035       0
  6486.4     .05       0  7053.3     .05       0  7208.1     .05       0
    7336     .07       0  7526.9     .12       0 11694.1     .07       0
 11854.4     .12       0 13700.7     .07       0
Bank Sta=4950.2,5059.5
XS Rating Curve= 0 ,0
Exp/Cntr=0.3,0.1

Type RM Length L Ch R = 1 ,215660  ,1398,1398,1398
BEGIN DESCRIPTION:
C20414
END DESCRIPTION:
XS GIS Cut Line= 3
      2432185.15     13656081.52      2430536.73     13653764.82
      2423760.33     13648147.54
#Sta/Elev= 30
    2721  269.97  2984.6  269.03  3162.3  257.65  3342.4  246.87  3465.9  239.55
  3858.1  233.58  4260.6  236.14  4403.6  232.47  4569.7  240.26  4876.8  241.44
    4933  227.38  4934.5  225.78  5042.3  227.38  5048.6  238.57  5157.4  237.82
  5204.3  241.79  5443.7  241.34  6470.8  238.38  6970.2  240.29  7002.7  240.71
  7154.1  243.75  7344.7  244.77  8298.1  255.22  8332.4  255.52  8601.6  257.17
    8718  256.33 10372.8  254.22 12666.7  265.19 12815.7  266.77 14366.2   266.5
#Mann= 20 ,-1 , 0
    2721     .05       0  3162.3     .07       0  3342.4     .05       0
  3465.9     .07       0  4260.6     .12       0    4933     .05       0
  5042.3     .12       0  5204.3     .07       0  5443.7     .07       0
  6470.8     .12       0  6970.2     .07       0  7002.7     .12       0
  7154.1     .05       0  7344.7     .05       0  8298.1     .07       0
  8332.4     .05       0  8601.6     .07       0    8718     .12       0
 12666.7     .07       0 12815.7     .12       0
Bank Sta=4933,5042.3
XS Rating Curve= 0 ,0
Exp/Cntr=0.3,0.1

Type RM Length L Ch R = 1 ,214262  ,3436,3436,3436
BEGIN DESCRIPTION:
C20413
END DESCRIPTION:
XS GIS Cut Line= 3
      2432476.03       13653319.      2429934.88     13653140.67
      2423938.67     13648169.84
#Sta/Elev= 30
    3796  278.13  4211.7  281.07  4499.9  262.17  4689.2  243.77  4764.6  241.72
    4863  239.04  4924.7  237.82  4935.2  226.63  4936.7  225.03  5044.7  226.63
  5110.3  237.78  5137.8  235.46  5256.8  239.61  5355.2  239.62  5780.6  239.65
  6044.4  239.67  6142.8  240.98  6241.3  242.29  6339.7  239.86  6710.4  237.61
  7116.5  240.66  7337.5  240.11  7403.3  240.71  7420.2  246.45    8586  256.77
    9586  258.37 10431.2   253.6 12399.5     261   12753  264.69 14132.1  266.11
#Mann= 20 ,-1 , 0
    3796     .07       0  4764.6     .12       0    4863     .07       0
  4935.2     .05       0  5044.7     .07       0  5137.8     .12       0
  5256.8     .07       0  5355.2     .12       0  5780.6     .07       0
  6044.4     .07       0  6142.8     .12       0  6241.3     .07       0
  6339.7      .1       0  6710.4     .12       0  7116.5     .07       0
  7337.5     .12       0  7403.3     .05       0    8586     .12       0
 12399.5     .07       0   12753     .12       0
Bank Sta=4935.2,5044.7
XS Rating Curve= 0 ,0
Exp/Cntr=0.3,0.1

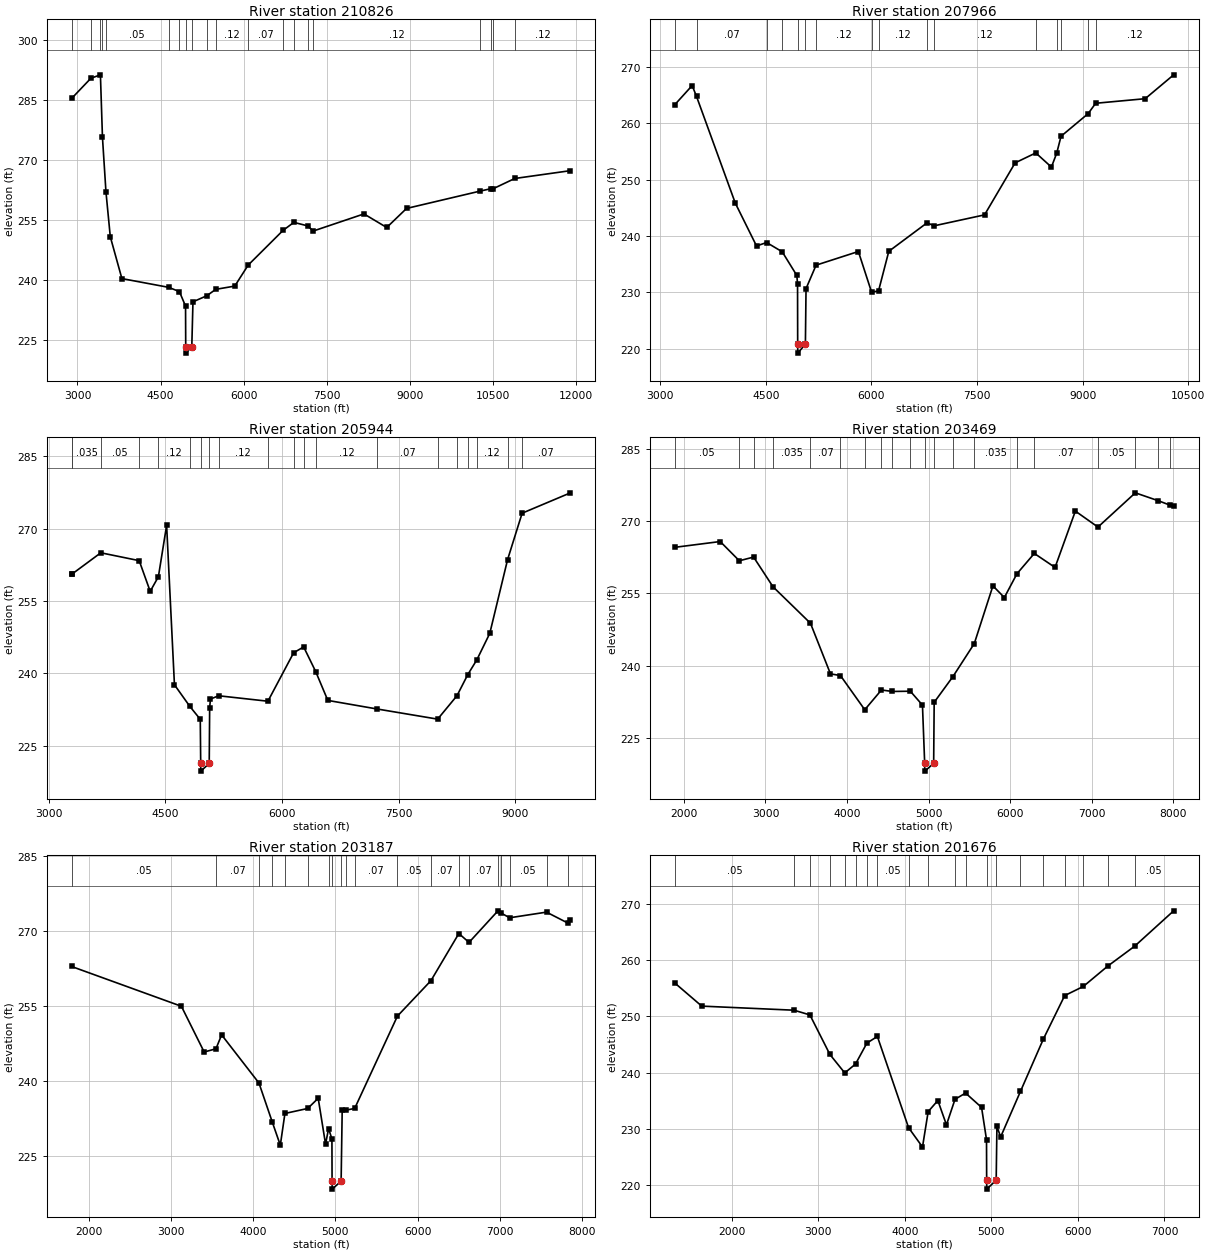
Type RM Length L Ch R = 1 ,210826  ,2860,2860,2860
BEGIN DESCRIPTION:
C20412
END DESCRIPTION:
XS GIS Cut Line= 4
      2432007.92     13651268.25      2430336.11     13651513.45
      2428530.56     13651245.96      2424027.77     13648102.92
#Sta/Elev= 30
  2894.9  285.38  3242.8  290.44    3415   291.3    3452  275.62    3515     262
  3593.1  250.78  3802.6  240.29    4647   238.1  4841.5  237.03    4952  233.38
  4955.1  223.23  4956.6  221.63  5064.7  223.23  5085.9  234.48    5334  235.98
  5497.8   237.6  5840.3  238.41  6082.8  243.67  6712.5  252.36  6907.3  254.36
  7159.5  253.48  7255.9  252.19  8173.1  256.48    8584  253.08  8941.6  257.85
 10265.7  262.18 10464.3  262.79 10507.4   262.8 10895.7  265.35 11901.1  267.31
#Mann= 20 ,-1 , 0
  2894.9     .05       0  3242.8     .07       0    3415     .05       0
    3452    .035       0    3515     .05       0    4647     .12       0
  4841.5      .1       0  4955.1     .05       0  5064.7      .1       0
    5334     .12       0  5497.8     .12       0  6082.8     .07       0
  6712.5     .07       0  6907.3     .12       0  7159.5     .07       0
  7255.9     .12       0 10265.7     .07       0 10464.3     .12       0
 10507.4     .07       0 10895.7     .12       0
Bank Sta=4955.1,5064.7
XS Rating Curve= 0 ,0
Exp/Cntr=0.3,0.1

Type RM Length L Ch R = 1 ,207966  ,2022,2022,2022
BEGIN DESCRIPTION:
C20411
END DESCRIPTION:
XS GIS Cut Line= 3
      2430960.17     13649618.72      2426747.29      13649195.2
      2424139.28     13648036.09
#Sta/Elev= 30
  3205.7  263.26  3452.1  266.65  3513.9  264.73  4065.2  245.81  4366.7  238.22
  4510.4  238.83  4731.7  237.19  4939.6  232.99  4949.6  231.46  4951.5  220.83
    4953  219.23  5061.2  220.83  5070.2  230.66  5212.9  234.82  5813.9  237.24
  6001.8  230.02  6100.4  230.26  6246.1  237.27  6790.7  242.33  6889.4  241.79
  7606.5  243.73  8041.1  252.95  8334.9  254.71  8556.8   252.2  8632.3  254.68
  8693.4  257.66  9079.1  261.68  9185.5  263.51  9889.2  264.32 10293.8  268.55
#Mann= 16 ,-1 , 0
  3205.7     .05       0  3513.9     .07       0  4510.4     .12       0
  4731.7      .1       0  4951.5     .05       0  5061.2      .1       0
  5212.9     .12       0  6001.8     .12       0  6100.4     .12       0
  6790.7    .035       0  6889.4     .12       0  8334.9     .07       0
  8632.3     .12       0  8693.4     .07       0  9079.1    .035       0
  9185.5     .12       0
Bank Sta=4951.5,5061.2
XS Rating Curve= 0 ,0
Exp/Cntr=0.3,0.1

Type RM Length L Ch R = 1 ,205944  ,2475,2475,2475
BEGIN DESCRIPTION:
C20410
END DESCRIPTION:
XS GIS Cut Line= 2
      2430269.19     13647813.17      2423894.07     13647099.87
#Sta/Elev= 30
  3295.2  260.66  3302.8  260.62  3670.8     265  4164.3  263.37  4305.7  257.01
  4411.2  260.04    4517   270.7  4617.6  237.66  4814.2  233.21  4949.7   230.5
  4955.2  221.37  4956.7  219.77  5064.9  221.37  5070.4  232.85  5080.5   234.7
  5186.3  235.38  5819.4  234.25  6150.3  244.29  6279.3   245.5  6434.4  240.38
  6589.8  234.42    7224  232.64  8002.3  230.54  8250.8  235.39  8389.6  239.76
    8507  242.85  8672.7  248.31  8901.8   263.6  9088.4   273.2  9710.1  277.42
#Mann= 20 ,-1 , 0
  3295.2     .05       0  3302.8    .035       0  3670.8     .05       0
  4164.3     .07       0  4411.2     .12       0  4814.2      .1       0
  4955.2     .05       0  5064.9      .1       0  5186.3     .12       0
  5819.4     .07       0  6150.3     .05       0  6279.3     .07       0
  6434.4     .12       0    7224     .07       0  8002.3     .12       0
  8250.8     .07       0  8389.6    .035       0    8507     .12       0
  8901.8    .035       0  9088.4     .07       0
Bank Sta=4955.2,5064.9
XS Rating Curve= 0 ,0
Exp/Cntr=0.3,0.1

Type RM Length L Ch R = 1 ,203469  ,282,282,282
BEGIN DESCRIPTION:
SAND21676
END DESCRIPTION:
XS GIS Cut Line= 6
      2430116.38      13647595.9      2429483.27     13646801.41
      2428937.05     13645882.77      2428415.66     13645485.52
      2426640.45     13644703.43      2425547.98     13643772.35
#Sta/Elev= 30
  1888.9  264.55  2445.5  265.75  2679.8  261.76  2854.6  262.53  3092.5  256.37
    3552   248.8    3797  238.31  3919.3  237.96  4217.4  230.87    4422  234.97
  4555.2  234.66  4776.2  234.71  4924.8  231.83    4952  219.74  4953.5  218.14
  5062.1  219.74  5068.4  232.41    5299  237.76  5560.4   244.6  5788.6  256.56
  5928.6  254.14  6083.2  259.07  6295.8  263.28  6550.1  260.38  6799.1  272.06
  7076.3  268.75  7534.2  275.85  7817.5   274.2  7965.2  273.26  8004.3  273.19
#Mann= 20 ,-1 , 0
  1888.9     .05       0  2679.8    .035       0  2854.6    .035       0
  3092.5    .035       0    3552     .07       0  3919.3    .035       0
  4217.4    .035       0    4422    .035       0  4555.2    .035       0
  4776.2    .035       0    4952    .035       0  5062.1    .035       0
    5299    .035       0  5560.4    .035       0  6083.2    .035       0
  6295.8     .07       0  7076.3     .05       0  7534.2     .05       0
  7817.5    .035       0  7965.2     .05       0
Bank Sta=4952,5062.1
XS Rating Curve= 0 ,0
Exp/Cntr=0.3,0.1

Type RM Length L Ch R = 1 ,203187  ,1511,1511,1511
BEGIN DESCRIPTION:
SAND21677
END DESCRIPTION:
XS GIS Cut Line= 6
      2430140.61     13647458.34      2429110.85     13645721.39
      2428639.12     13645299.31      2426752.18     13644479.98
      2426392.17     13644194.46      2425734.22     13643586.16
#Sta/Elev= 30
  1794.4  262.91  3129.2  254.95    3406   245.8  3549.3  246.44  3618.4  249.23
  4072.3  239.59  4234.1  231.79  4331.9  227.15  4387.9   233.5  4664.5   234.5
  4792.6  236.54  4881.9  227.36  4918.8  230.47  4959.5  228.39  4961.2  219.96
  4962.7  218.36  5071.3  219.96  5084.4  234.28  5129.7  234.16  5236.2  234.51
  5755.7  252.98  6163.9  260.09  6502.6  269.51  6626.5  267.73  6978.3  274.05
  7009.2  273.67  7120.5  272.66  7568.4  273.79  7829.7  271.59  7859.7  272.25
#Mann= 20 ,-1 , 0
  1794.4     .05       0  3549.3     .07       0  4072.3     .05       0
  4234.1     .12       0  4387.9     .05       0  4664.5     .12       0
  4918.8      .1       0  4961.2     .05       0  5071.3      .1       0
  5129.7     .12       0  5236.2     .07       0  5755.7     .05       0
  6163.9     .07       0  6502.6     .05       0  6626.5     .07       0
  6978.3     .05       0  7009.2     .07       0  7120.5     .05       0
  7568.4    .035       0  7829.7     .05       0
Bank Sta=4961.2,5071.3
XS Rating Curve= 0 ,0
Exp/Cntr=0.3,0.1

Type RM Length L Ch R = 1 ,201676  ,1925,1925,1925
BEGIN DESCRIPTION:
C20408
END DESCRIPTION:
XS GIS Cut Line= 3
      2430857.98     13646900.04       2429573.3     13644747.33
      2427524.68      13642212.6
#Sta/Elev= 30
  1340.7  255.97  1652.1  251.85    2719  251.12  2902.2  250.28  3133.3  243.23
  3304.9  239.94  3429.3  241.52    3561  245.26    3682  246.44  4042.8  230.17
  4203.5  226.73  4269.2  233.04    4381  235.02  4480.6  230.68  4579.2  235.23
  4701.3  236.35  4886.3  233.79  4943.5  228.03  4945.1  220.82  4946.6  219.22
  5055.3  220.82  5063.8   230.4  5106.9  228.53  5335.4  236.63  5600.6  245.98
  5847.2  253.73    6062  255.35  6344.4  258.98  6656.2  262.54  7106.7  268.84
#Mann= 20 ,-1 , 0
  1340.7     .05       0    2719    .035       0  2902.2     .05       0
  3133.3     .07       0  3304.9     .05       0  3429.3     .05       0
    3561    .035       0    3682     .05       0  4042.8    .033       0
  4269.2     .12       0  4579.2    .035       0  4701.3     .12       0
  4945.1     .05       0  5055.3      .1       0  5335.4     .05       0
  5600.6     .05       0  5847.2     .12       0    6062     .05       0
  6344.4     .07       0  6656.2     .05       0
Bank Sta=4945.1,5055.3
XS Rating Curve= 0 ,0
Exp/Cntr=0.3,0.1

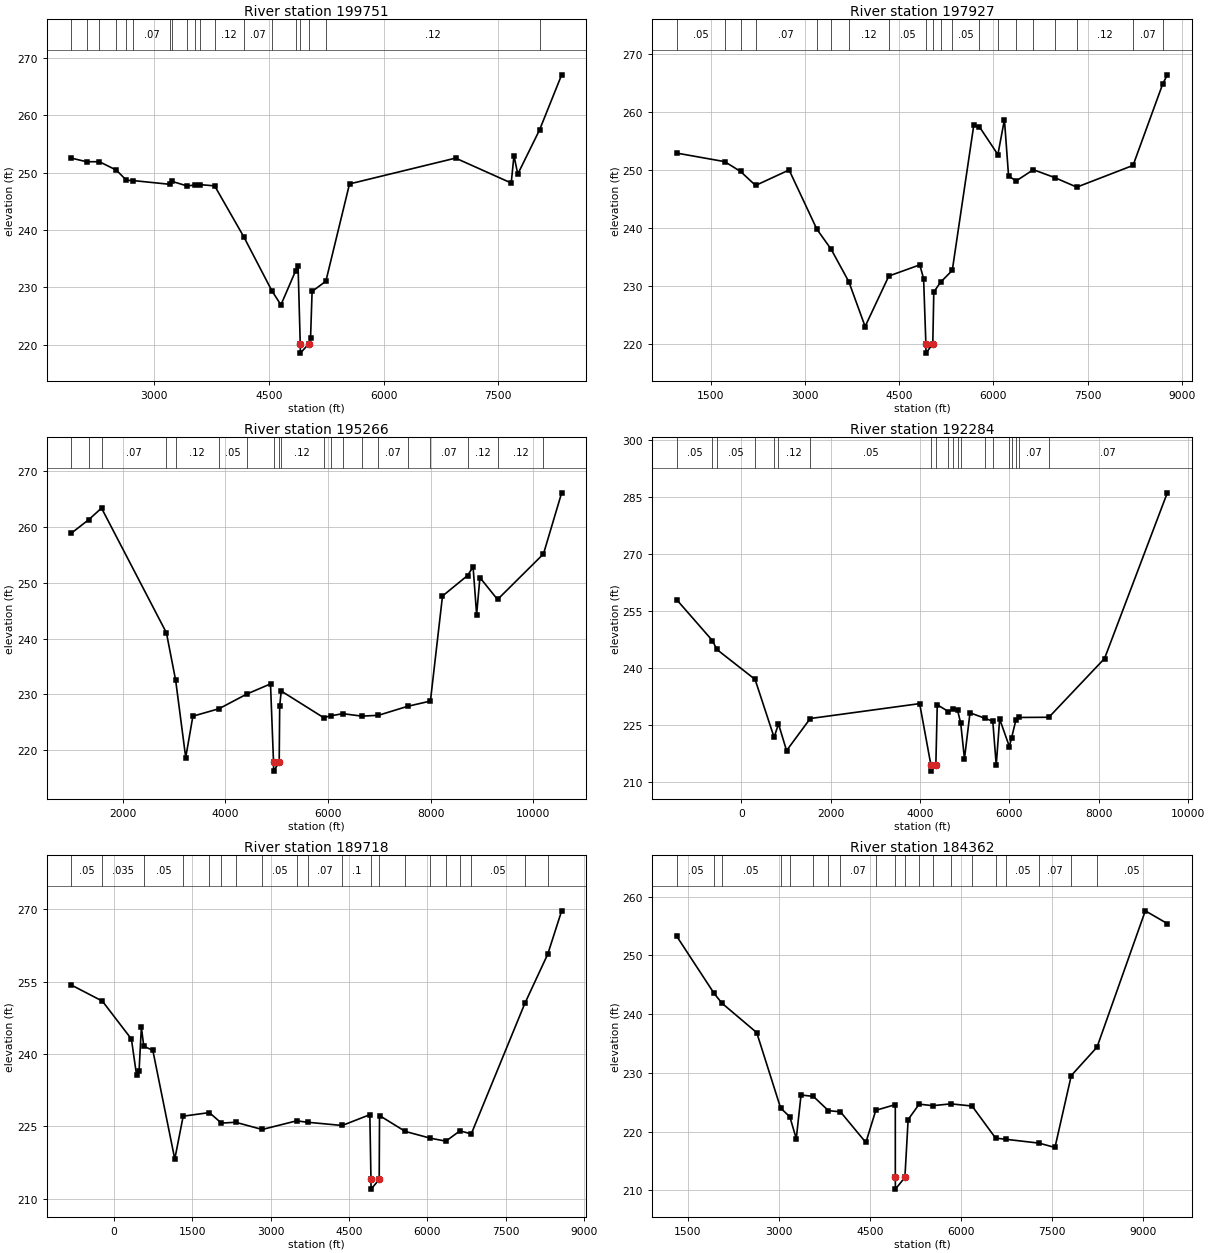
Type RM Length L Ch R = 1 ,199751  ,1824,1824,1824
BEGIN DESCRIPTION:
C20407
END DESCRIPTION:
XS GIS Cut Line= 3
      2430996.91     13646587.63      2430267.74     13642941.77
      2428635.79     13640788.98
#Sta/Elev= 30
  1911.4  252.53  2113.3  251.89  2281.6  251.89  2503.9  250.43  2636.2  248.65
  2719.4  248.61  3206.9  247.95  3233.2  248.46  3426.8  247.68  3527.8  247.81
    3598   247.9  3790.4  247.68  4173.7  238.75  4538.2  229.42  4657.4  226.94
  4851.3  232.93  4881.7   233.7  4910.2  220.14  4911.7  218.54  5020.4  220.14
  5044.9   221.1  5065.3  229.29  5245.4  231.07  5554.8  248.02    6943  252.52
  7670.8  248.18  7706.8  252.95  7756.7  249.73  8041.6  257.43  8330.9  267.03
#Mann= 19 ,-1 , 0
  1911.4     .05       0  2113.3     .07       0  2281.6     .05       0
  2503.9     .07       0  2636.2     .12       0  2719.4     .07       0
  3206.9     .12       0  3233.2     .07       0  3426.8     .05       0
  3527.8    .035       0    3598     .05       0  3790.4     .12       0
  4173.7     .07       0  4538.2     .12       0  4851.3      .1       0
  4910.2     .05       0  5020.4      .1       0  5245.4     .12       0
  8041.6     .07       0
Bank Sta=4910.2,5020.4
XS Rating Curve= 0 ,0
Exp/Cntr=0.3,0.1

Type RM Length L Ch R = 1 ,197927  ,2661,2661,2661
BEGIN DESCRIPTION:
C20406
END DESCRIPTION:
XS GIS Cut Line= 4
       2431240.5      13646481.7      2432003.85     13644018.16
      2431656.63     13642073.72      2428774.65     13640545.92
#Sta/Elev= 30
   954.9  252.85  1718.2  251.38  1971.1  249.69    2211  247.27  2745.4  249.94
  3188.5  239.71  3413.9  236.29  3696.9  230.67  3956.4  222.94  4334.5  231.65
  4827.3  233.57  4888.2  231.21  4924.6  219.95  4926.1  218.35  5034.8  219.95
  5050.8  228.89  5157.7  230.57  5345.1  232.62  5687.2  257.63  5778.5  257.37
  6071.8  252.59  6176.1  258.62  6242.1  248.89  6363.4  248.05  6636.4  249.99
  6976.2  248.63  7329.2  246.98  8225.4  250.73  8696.4  264.73  8771.1  266.35
#Mann= 20 ,-1 , 0
   954.9     .05       0  1718.2     .07       0  1971.1     .12       0
    2211     .07       0  3188.5     .05       0  3413.9     .05       0
  3696.9     .12       0  4334.5     .05       0  4924.6     .05       0
  5034.8      .1       0  5157.7     .12       0  5345.1     .05       0
  5778.5    .033       0  6071.8    .035       0  6363.4    .035       0
  6636.4    .035       0  6976.2     .07       0  7329.2     .12       0
  8225.4     .07       0  8696.4     .05       0
Bank Sta=4924.6,5034.8
XS Rating Curve= 0 ,0
Exp/Cntr=0.3,0.1

Type RM Length L Ch R = 1 ,195266  ,2982,2982,2982
BEGIN DESCRIPTION:
C20405
END DESCRIPTION:
XS GIS Cut Line= 4
      2434156.63     13646170.49      2434191.35     13643323.72
      2433670.52     13641761.22      2428844.15     13640198.72
#Sta/Elev= 30
   990.5  258.82    1333  261.25  1584.4  263.34    2850  241.03  3030.5  232.51
  3226.2  218.72  3366.2  226.12  3875.1  227.45  4423.2   230.1  4879.7  231.89
  4938.5  217.89    4940  216.29  5049.1  217.89  5058.9  227.92    5088  230.62
  5913.5  225.87  6059.2  226.18  6286.6  226.57  6657.9  226.13  6982.2  226.27
  7552.4  227.88  7998.1  228.82  8233.7  247.61  8721.3  251.27  8830.1  252.82
  8899.3   244.3  8963.3  250.91  9307.4  246.99 10202.8  255.14 10557.5  266.07
#Mann= 20 ,-1 , 0
   990.5     .07       0    1333     .05       0  1584.4     .07       0
    2850     .07       0  3030.5     .12       0  3875.1     .05       0
  4423.2    .035       0  4938.5     .05       0  5049.1     .12       0
    5088     .12       0  5913.5     .12       0  6059.2     .07       0
  6286.6     .07       0  6657.9     .12       0  6982.2     .07       0
  7552.4     .12       0  7998.1     .07       0  8721.3     .12       0
  9307.4     .12       0 10202.8     .05       0
Bank Sta=4938.5,5049.1
XS Rating Curve= 0 ,0
Exp/Cntr=0.3,0.1

Type RM Length L Ch R = 1 ,192284  ,2566,2566,2566
BEGIN DESCRIPTION:
SANDIES CREEK 256.0
END DESCRIPTION:
XS GIS Cut Line= 4
      2434989.98     13646517.84      2435233.02     13641934.83
      2434642.74     13639677.88      2435128.85     13635650.12
#Sta/Elev= 30
 -1447.4  258.04  -647.1  247.27  -548.6  244.95   306.1  237.08   731.8  221.84
   830.3  225.36  1010.9  218.35    1541  226.79  3989.5  230.71  4241.2  214.55
  4242.7  212.95  4351.9  214.55  4383.3  230.41  4632.6  228.63  4735.2  229.26
  4837.8  228.99  4908.9  225.51  4992.1   216.2  5116.1  228.29  5458.2  226.83
  5626.3  226.06  5703.4  214.55    5780  226.66    5997  219.41  6047.4  221.74
  6146.3  226.53  6208.9  227.07  6881.6  227.12  8127.3  242.58  9531.9  286.17
#Mann= 20 ,-1 , 0
 -1447.4     .05       0  -647.1    .035       0  -548.6     .05       0
   306.1    .035       0   731.8     .07       0   830.3     .12       0
    1541     .05       0  4241.2     .05       0  4351.9     .05       0
  4632.6      .1       0  4735.2     .07       0  4837.8     .12       0
  4908.9      .1       0  5458.2     .12       0  5626.3      .1       0
    5997     .07       0  6047.4      .1       0  6146.3     .12       0
  6208.9     .07       0  6881.6     .07       0
Bank Sta=4241.2,4351.9
XS Rating Curve= 0 ,0
Exp/Cntr=0.3,0.1

Type RM Length L Ch R = 1 ,189718  ,5356,5356,5356
BEGIN DESCRIPTION:
C20404
END DESCRIPTION:
XS GIS Cut Line= 3
      2435268.06     13646551.44      2436309.41     13641865.38
       2437559.4      13637455.7
#Sta/Elev= 30
  -817.2  254.31  -218.3  250.94   336.7  243.08   435.2  235.61   483.9  236.54
   527.4   245.5   573.8  241.58   746.5  240.74  1166.5  218.18  1327.1  227.08
    1827  227.82  2059.8  225.64  2329.8  225.82    2838  224.32  3495.4  226.11
  3707.5  225.82  4369.3  225.15  4897.5  227.39  4919.1  213.95  4920.6  211.95
  5076.6  213.95  5082.8  227.21  5574.7  223.92  6056.3  222.51  6352.8   221.9
  6621.2  224.04  6837.9   223.4  7861.6  250.45  8300.7  260.69  8566.6  269.67
#Mann= 20 ,-1 , 0
  -817.2     .05       0  -218.3    .035       0   573.8     .05       0
  1327.1     .05       0    1827    .035       0  2059.8     .05       0
  2329.8     .12       0    2838     .05       0  3495.4     .07       0
  3707.5     .07       0  4369.3      .1       0  4919.1     .05       0
  5076.6      .1       0  5574.7     .07       0  6056.3     .07       0
  6352.8     .12       0  6621.2     .07       0  6837.9     .05       0
  7861.6     .07       0  8300.7    .035       0
Bank Sta=4919.1,5076.6
XS Rating Curve= 0 ,0
Exp/Cntr=0.3,0.1

Type RM Length L Ch R = 1 ,184362  ,4298,4298,4298
BEGIN DESCRIPTION:
C20403
END DESCRIPTION:
XS GIS Cut Line= 4
      2435406.66     13646657.02      2436969.13     13644920.94
      2437628.85     13643566.77      2439226.06     13639643.19
#Sta/Elev= 30
  1316.1  253.26  1930.4  243.55  2059.8  241.87  2633.6  236.85  3027.3     224
  3178.6  222.52  3284.6  218.78    3363  226.23  3566.2  225.99  3813.3  223.57
  4012.4  223.36  4430.8  218.14  4594.3  223.62  4915.3  224.59  4915.8   212.2
  4917.3   210.2  5073.4   212.2  5126.7  222.05    5309  224.67  5530.7  224.41
  5830.7  224.72  6179.5  224.35  6566.6  218.89    6741  218.68  7284.9  218.03
  7544.4  217.29  7812.8  229.54  8237.1  234.38    9032  257.59  9394.3  255.42
#Mann= 20 ,-1 , 0
  1316.1     .05       0  1930.4    .035       0  2059.8     .05       0
  3027.3    .035       0  3178.6     .12       0  3566.2     .07       0
  3813.3     .05       0  4012.4     .07       0  4594.3     .07       0
  4915.8     .05       0  5073.4     .07       0    5309     .07       0
  5530.7     .05       0  5830.7      .1       0  6179.5     .07       0
  6566.6    .035       0    6741     .05       0  7284.9     .07       0
  7812.8    .035       0  8237.1     .05       0
Bank Sta=4915.8,5073.4
XS Rating Curve= 0 ,0
Exp/Cntr=0.3,0.1

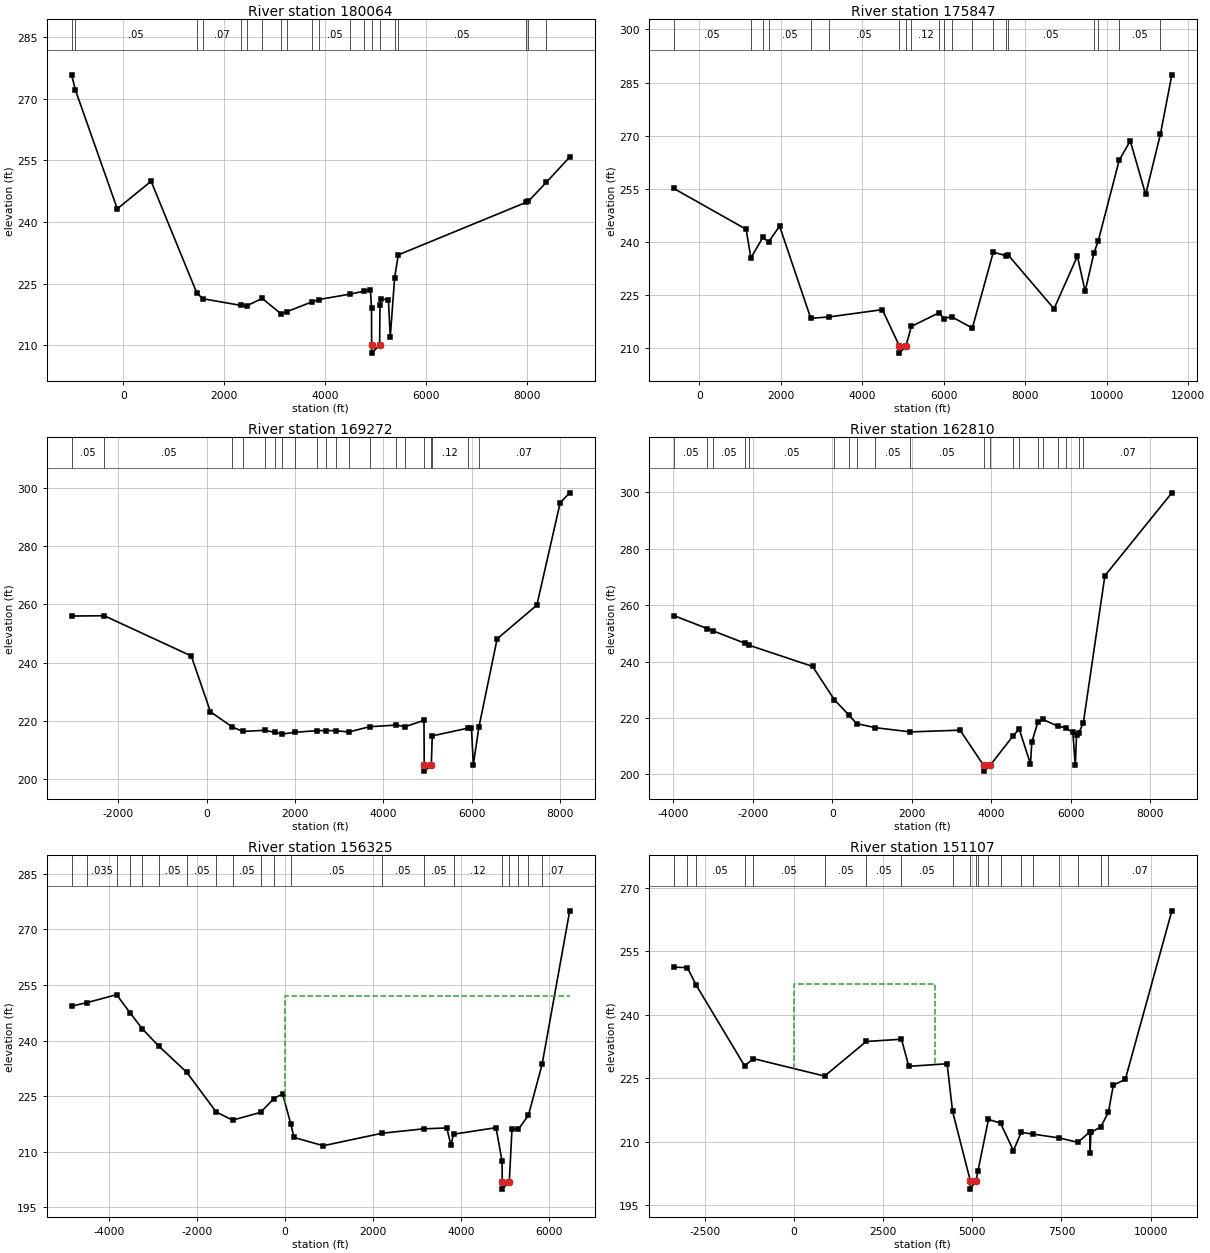
Type RM Length L Ch R = 1 ,180064  ,4217,4217,4217
BEGIN DESCRIPTION:
SANDIES CREEK 262.0
END DESCRIPTION:
XS GIS Cut Line= 4
      2439156.63       13649400.      2439399.68     13644122.33
      2439972.55     13643203.22      2439393.77     13639743.19
#Sta/Elev= 30
 -1025.9  275.81  -951.1  272.16  -119.9  243.22   550.8  249.93  1452.9  222.87
  1570.2  221.37  2324.7  219.75  2457.2  219.71  2753.2  221.44  3122.9  217.71
  3242.2  218.21  3747.1  220.63  3879.3  221.17  4492.6  222.48  4773.1  223.19
  4898.6  223.46  4919.8  219.08  4921.8  210.13  4923.3  208.13  5080.5  210.13
  5087.4  219.72  5102.6  221.33  5254.9  221.11  5291.2  212.01  5378.2  226.49
  5450.4  232.02  7984.3   244.8  8030.2  245.07  8388.3  249.71  8848.5  255.83
#Mann= 20 ,-1 , 0
 -1025.9     .07       0  -951.1     .05       0  1452.9    .035       0
  1570.2     .07       0  2324.7     .05       0  2457.2     .07       0
  2753.2     .05       0  3122.9     .12       0  3242.2     .07       0
  3747.1     .05       0  3879.3     .05       0  4492.6     .07       0
  4773.1     .07       0  4921.8     .05       0  5080.5     .07       0
  5378.2      .1       0  5450.4     .05       0  7984.3     .07       0
  8030.2     .05       0  8388.3     .05       0
Bank Sta=4921.8,5080.5
XS Rating Curve= 0 ,0
Exp/Cntr=0.3,0.1

Type RM Length L Ch R = 1 ,175847  ,6575,6575,6575
BEGIN DESCRIPTION:
C20402
END DESCRIPTION:
XS GIS Cut Line= 4
       2441830.3     13651551.43      2442038.57     13646726.49
      2442003.85     13644643.16      2443705.25     13639608.42
#Sta/Elev= 30
  -630.7  255.05  1147.4   243.5  1263.8  235.38  1558.8  241.24  1696.3  239.87
  1968.1  244.39  2733.5  218.32  3170.9   218.7  4490.3  220.77    4910  210.48
  4911.5  208.48  5069.3  210.48  5203.2  216.04  5893.2  219.95  5991.8  218.26
  6188.9  218.78  6699.6  215.57  7213.4  237.01  7523.4  236.06  7579.6  236.21
  8704.8  221.03  9278.2  235.89  9468.2  225.97  9686.1  236.84    9789  240.17
   10304  262.99 10576.1  268.49 10953.5  253.34 11315.2  270.35 11596.8  287.17
#Mann= 20 ,-1 , 0
  -630.7     .05       0  1263.8    .033       0  1558.8     .05       0
  1696.3     .05       0  2733.5     .07       0  3170.9     .05       0
    4910     .05       0  5069.3     .05       0  5203.2     .12       0
  5893.2     .07       0  5991.8      .1       0  6188.9     .05       0
  6699.6     .07       0  7213.4     .05       0  7523.4    .035       0
  7579.6     .05       0  9686.1    .035       0    9789     .05       0
   10304     .05       0 11315.2     .07       0
Bank Sta=4910,5069.3
XS Rating Curve= 0 ,0
Exp/Cntr=0.3,0.1

Type RM Length L Ch R = 1 ,169272  ,6462,6462,6462
BEGIN DESCRIPTION:
C20401
END DESCRIPTION:
XS GIS Cut Line= 3
      2443601.18      13651690.9      2444503.85     13644608.44
      2445545.51     13640615.43
#Sta/Elev= 30
 -3054.5  255.99 -2314.6  256.09  -346.9  242.27    86.6   223.1   583.9  217.86
   817.5  216.35  1312.2  216.74  1542.5  216.03  1707.9  215.47  2004.8  216.06
  2486.4  216.61  2697.3  216.67  2925.8  216.61  3215.7  216.16  3686.7  217.98
  4289.5  218.53  4486.6  217.98  4915.6  220.17    4922  204.72  4923.5  202.72
  5081.4  204.72    5103  214.83  5901.3  217.45  5990.4  217.53  6031.7  204.96
  6157.6  217.77  6570.1  248.15  7468.2  259.73  7996.2  294.89  8211.9  298.31
#Mann= 20 ,-1 , 0
 -3054.5     .05       0 -2314.6     .05       0   583.9     .05       0
   817.5     .05       0  1312.2    .035       0  1542.5     .07       0
  1707.9    .035       0  2004.8     .05       0  2486.4     .05       0
  2697.3    .035       0  2925.8     .05       0  3215.7     .05       0
  3686.7    .035       0  4289.5     .12       0  4486.6     .07       0
    4922     .05       0  5081.4      .1       0    5103     .12       0
  5901.3      .1       0  6157.6     .07       0
Bank Sta=4922,5081.4
XS Rating Curve= 0 ,0
Exp/Cntr=0.3,0.1

Type RM Length L Ch R = 1 ,162810  ,6485,6485,6485
BEGIN DESCRIPTION:
C20400
END DESCRIPTION:
XS GIS Cut Line= 3
      2445198.64     13652801.42      2446830.24     13645788.99
      2445719.12     13640580.64
#Sta/Elev= 30
 -3985.4  256.32 -3141.5  251.68 -3008.9  250.95 -2182.6  246.41 -2082.1  245.73
  -493.1  238.26    57.1  226.37   429.5  220.86   612.2  217.98  1088.2  216.52
  1967.2  215.03  3214.9  215.64  3807.9  203.11  3809.4  201.11  3967.8  203.11
  4546.2  213.59  4701.6  216.06  4985.6  203.63    5018  211.33  5168.2  218.38
  5293.8  219.46  5674.9  217.08  5875.7  216.42  6050.8  214.84  6112.1  203.11
  6143.6   213.8  6194.9  214.51  6314.5  218.25  6855.8  270.43  8539.9  299.85
#Mann= 20 ,-1 , 0
 -3985.4     .05       0 -3141.5    .035       0 -3008.9     .05       0
 -2182.6    .035       0 -2082.1     .05       0    57.1    .035       0
   429.5     .05       0   612.2     .12       0  1088.2     .05       0
  1967.2     .05       0  3807.9     .05       0  3967.8     .05       0
  4546.2     .07       0  4701.6      .1       0  5168.2     .07       0
  5293.8     .05       0  5674.9     .07       0  5875.7      .1       0
  6194.9     .12       0  6314.5     .07       0
Bank Sta=3807.9,3967.8
XS Rating Curve= 0 ,0
Exp/Cntr=0.3,0.1

Type RM Length L Ch R = 1 ,156325  ,5218,5218,5218
BEGIN DESCRIPTION:
C20399
END DESCRIPTION:
XS GIS Cut Line= 4
      2447906.63     13651657.03      2448149.68     13648115.38
      2448219.13     13643150.11      2448531.62     13640372.37
#Sta/Elev= 30
 -4849.1   249.3 -4500.3  250.23 -3826.8  252.38 -3514.9  247.38 -3244.2  243.17
 -2869.8  238.51 -2233.9  231.42   -1565  220.71 -1194.2  218.51  -559.2  220.59
  -253.4  224.34   -58.6  225.62   126.9  217.57   201.4  213.82   867.6   211.6
  2198.1  214.97  3146.6  216.16  3670.6   216.4  3765.6  211.72  3823.5  214.71
  4788.8  216.47  4925.7  207.42  4929.9  201.88  4931.4  199.88    5090  201.88
    5151  216.07  5293.3  215.99  5524.6  219.82  5834.6  233.55  6461.9  275.02
#Mann= 20 ,-1 , 0
 -4849.1     .05       0 -4500.3    .035       0 -3826.8    .035       0
 -3514.9     .05       0 -3244.2     .05       0 -2869.8     .05       0
 -2233.9     .05       0   -1565     .07       0 -1194.2     .05       0
  -559.2    .035       0  -253.4     .05       0   126.9     .05       0
  2198.1     .05       0  3146.6     .05       0  3823.5     .12       0
  4929.9     .05       0    5090      .1       0  5293.3     .07       0
  5524.6     .12       0  5834.6     .07       0
#XS Ineff= 2 , 0
       0   -53.1  252.07               0
Permanent Ineff=
       F       F
Bank Sta=4929.9,5090
XS Rating Curve= 0 ,0
Exp/Cntr=0.3,0.1

Type RM Length L Ch R = 1 ,151107  ,4340,4340,4340
BEGIN DESCRIPTION:
SANDIES CREEK 269.0
END DESCRIPTION:
XS GIS Cut Line= 3
      2448184.83     13650961.27        2450725.       13642975.
      2451031.63     13637386.21
#Sta/Elev= 30
 -3380.5  251.28 -2996.9  251.17 -2755.7  247.11 -1390.3  227.96 -1144.1  229.67
   852.6  225.55  2021.2  233.72  3010.9  234.26  3216.1  227.85  4291.2  228.46
    4445  217.18  4941.1  200.84  4942.6  198.84  5101.7  200.84  5155.8  203.08
  5451.3  215.31  5789.5  214.44  6151.7  207.94  6370.1  212.24  6695.2  211.84
  7421.3  210.96  7963.5   209.9    8295  212.36    8305  207.49    8325  212.22
  8603.3  213.55  8815.3  216.96  8955.9  223.42  9290.6  224.75 10597.2  264.59
#Mann= 20 ,-1 , 0
 -3380.5     .05       0 -2996.9     .07       0 -2755.7     .05       0
 -1390.3    .035       0 -1144.1     .05       0   852.6     .05       0
  2021.2     .05       0  3010.9     .05       0    4445      .1       0
  4941.1     .05       0  5101.7      .1       0  5155.8     .12       0
  5451.3     .05       0  5789.5     .07       0  6370.1     .12       0
  6695.2     .05       0  7421.3     .05       0  7963.5      .1       0
  8603.3     .12       0  8815.3     .07       0
#XS Ineff= 2 , 0
       0  3956.2  247.21               0
Permanent Ineff=
       F       F
Bank Sta=4941.1,5101.7
XS Rating Curve= 0 ,0
Exp/Cntr=0.3,0.1