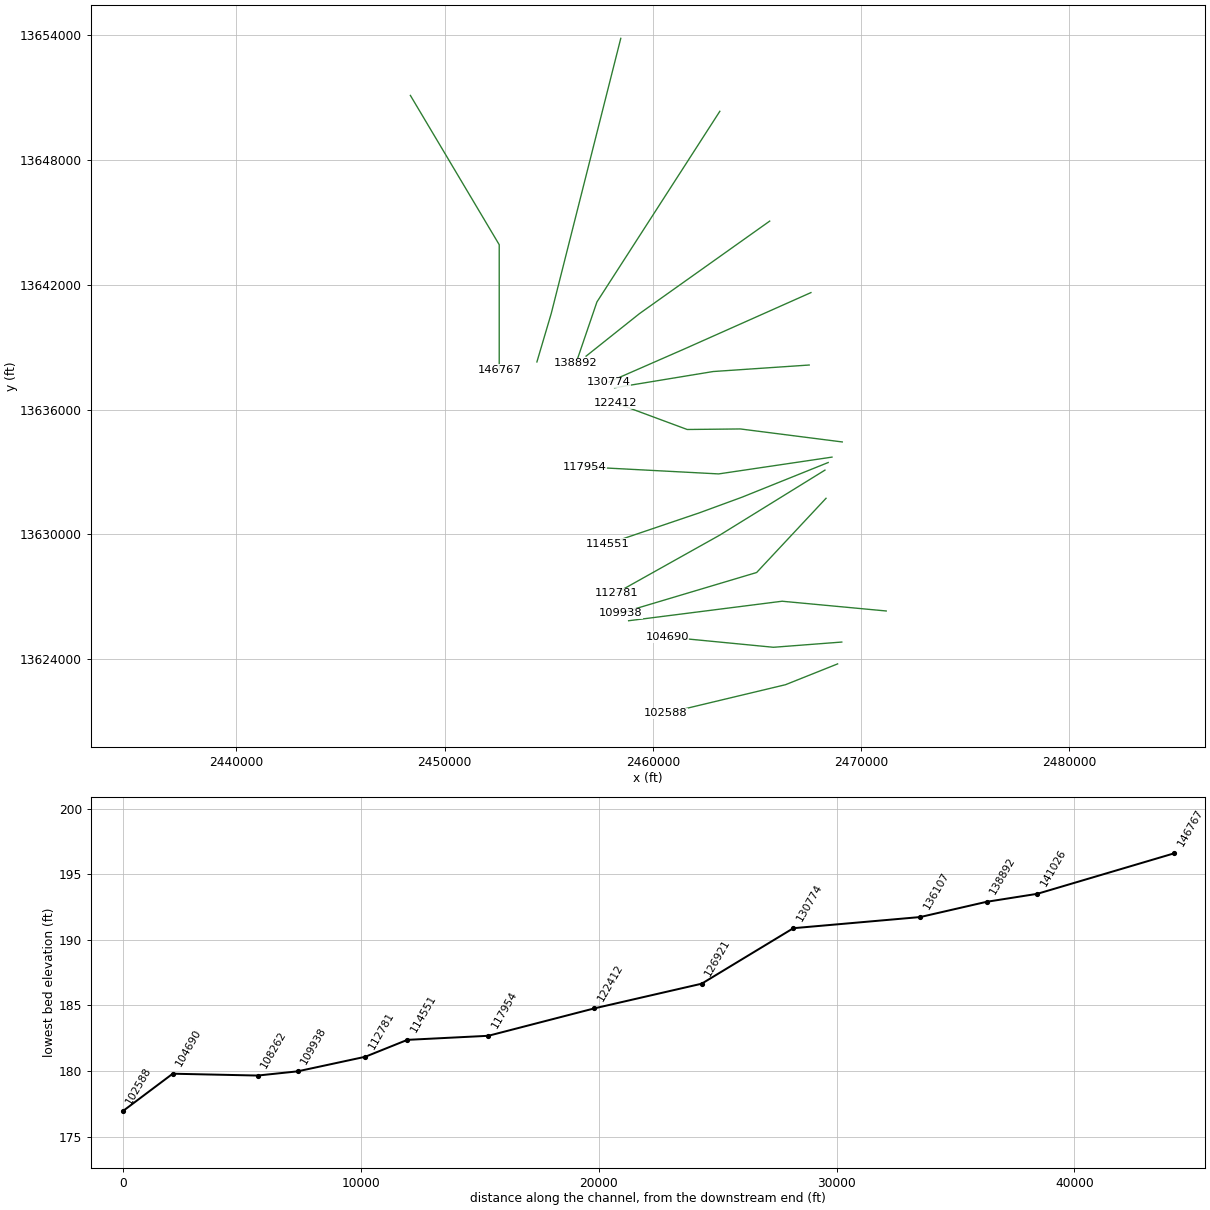
HEC-RAS study SANDIES CREEK.prj: SANDIES CREEK Base Level Engineering

--- SANDIES CREEK.g01 (geometry) --- (continued)

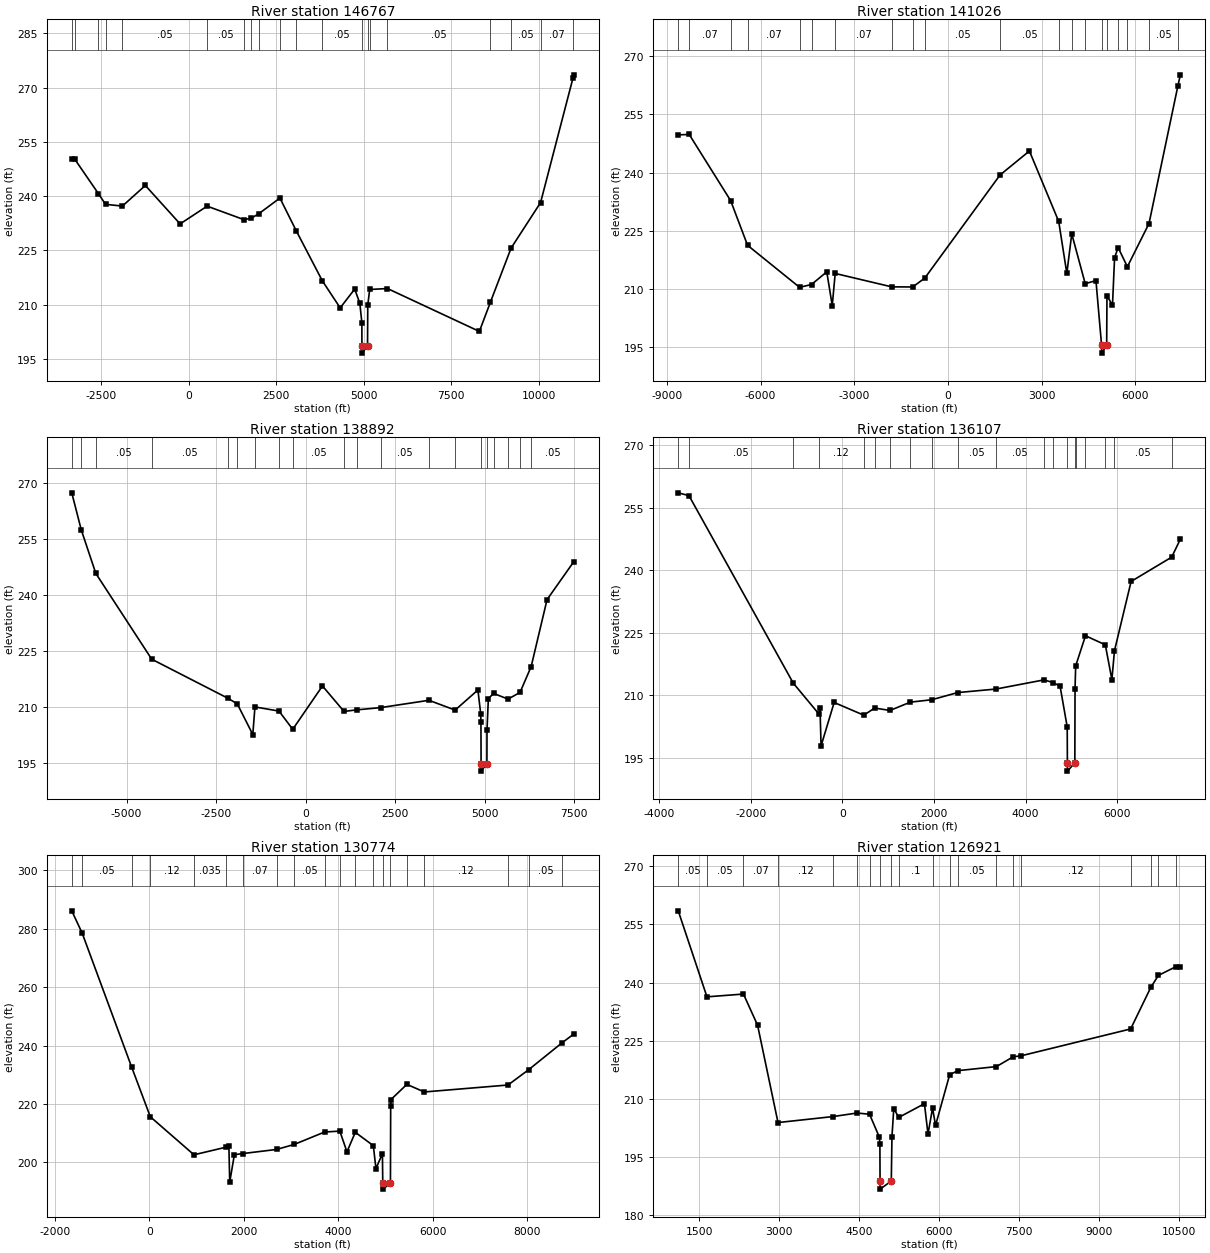
Type RM Length L Ch R = 1 ,146767  ,5741,5741,5741
BEGIN DESCRIPTION:
SANDIES CREEK 271.0
END DESCRIPTION:
XS GIS Cut Line= 3
      2448358.04     13651101.46        2452625.       13643925.
        2452625.     13637924.96
#Sta/Elev= 30
 -3349.2  250.21 -3266.1  250.24 -2586.5  240.66   -2384  237.72 -1901.6  237.24
 -1246.7  242.94  -253.3  232.31   519.3  237.22  1565.6  233.51  1775.6  233.85
  1995.9  235.12  2599.6  239.46  3064.4  230.44  3813.1  216.55  4322.1  209.09
    4737  214.29  4883.6  210.35  4941.8  204.96    4943  198.58  4944.5  196.58
  5103.7  198.58    5110  209.78  5164.9  214.18  5673.4  214.44    8300  202.58
  8612.6   210.6  9206.6  225.62 10049.1  238.21 10976.8  272.71   11000  273.53
#Mann= 20 ,-1 , 0
 -3349.2    .035       0 -3266.1     .05       0 -2586.5    .035       0
   -2384     .05       0 -1901.6     .05       0   519.3     .05       0
  1565.6     .07       0  1775.6     .05       0  1995.9     .07       0
  2599.6     .05       0  3064.4     .05       0  3813.1     .05       0
    4943     .05       0  5103.7     .12       0  5164.9     .05       0
  5673.4     .05       0  8612.6    .035       0  9206.6     .05       0
 10049.1     .07       0 10976.8     .07       0
Bank Sta=4943,5103.7
XS Rating Curve= 0 ,0
Exp/Cntr=0.3,0.1

Type RM Length L Ch R = 1 ,141026  ,2134,2134,2134
BEGIN DESCRIPTION:
SANDIES CREEK 273.0
END DESCRIPTION:
XS GIS Cut Line= 3
      2458462.19     13653844.56        2455125.       13640625.
      2454434.41     13638289.02
#Sta/Elev= 30
 -8634.3  249.72 -8283.1  249.82 -6956.4  232.77 -6415.4  221.27   -4751  210.45
 -4368.8  211.17 -3880.1  214.44 -3704.8  205.74 -3610.9  214.02 -1802.6  210.57
 -1130.3  210.54    -743  212.82  1665.9  239.38    2606  245.56  3544.1  227.41
  3803.6  214.04  3961.1  224.22  4392.4  211.38  4735.7  212.19  4916.3   195.5
  4917.8   193.5  5078.5   195.5  5088.4  208.27  5265.2  205.85  5331.8  218.09
  5446.5  220.68  5741.1  215.75  6433.7  226.88  7355.8  262.23  7435.9  265.18
#Mann= 20 ,-1 , 0
 -8634.3     .07       0 -8283.1     .07       0 -6956.4     .07       0
 -6415.4     .07       0   -4751    .033       0 -4368.8     .07       0
 -3610.9     .07       0 -1802.6     .05       0 -1130.3     .07       0
    -743     .05       0  1665.9     .05       0  3544.1     .07       0
  3961.1     .12       0  4392.4      .1       0  4916.3     .05       0
  5078.5      .1       0  5446.5     .07       0  5741.1     .05       0
  6433.7     .05       0  7355.8     .05       0
Bank Sta=4916.3,5078.5
XS Rating Curve= 0 ,0
Exp/Cntr=0.3,0.1

Type RM Length L Ch R = 1 ,138892  ,2785,2785,2785
BEGIN DESCRIPTION:
SANDIES CREEK 275.0
END DESCRIPTION:
XS GIS Cut Line= 3
      2463219.11     13650337.58      2457316.35     13641170.94
       2456309.4     13638219.53
#Sta/Elev= 30
 -6532.7  267.43 -6268.3  257.53   -5861  245.84 -4300.6  222.87 -2172.4  212.41
   -1911  210.91   -1477  202.69 -1417.3  210.09  -745.3  208.97  -361.9  204.09
     468   215.7  1070.3  208.88  1428.4   209.3  2089.4   209.9  3441.2  211.86
  4173.6  209.24  4809.5  214.62    4887  208.29  4894.1  205.92    4898  194.89
  4899.5  192.89  5060.4  194.89  5063.1   203.8    5101  212.33  5248.2   213.7
  5651.4  212.18    5986  213.98  6296.4  220.89  6740.6  238.84  7488.5  249.01
#Mann= 20 ,-1 , 0
 -6532.7     .07       0 -6268.3     .05       0   -5861     .05       0
 -4300.6     .05       0 -2172.4     .07       0   -1911      .1       0
 -1417.3     .07       0  -745.3    .035       0  -361.9     .05       0
  1070.3    .035       0  1428.4     .05       0  2089.4     .05       0
  3441.2    .033       0  4173.6     .12       0    4898     .05       0
  5060.4      .1       0  5248.2     .05       0  5651.4     .07       0
    5986    .035       0  6296.4     .05       0
Bank Sta=4898,5060.4
XS Rating Curve= 0 ,0
Exp/Cntr=0.3,0.1

Type RM Length L Ch R = 1 ,136107  ,5333,5333,5333
BEGIN DESCRIPTION:
SANDIES CREEK 276.0
END DESCRIPTION:
XS GIS Cut Line= 3
      2465614.92      13645059.8      2459364.96     13640615.38
      2456795.55      13638566.8
#Sta/Elev= 30
 -3580.1  258.59 -3346.1  257.92 -1070.2  212.87  -514.2   205.5  -486.8   206.9
  -463.5   197.8  -178.1  208.22   468.5  205.17   705.1  206.88    1041  206.31
  1483.7   208.3  1951.1  208.88  2516.6   210.6  3353.3  211.45  4400.4  213.65
  4600.4     213  4751.4  212.15  4907.5  202.32  4911.1  193.73  4912.6  191.73
  5073.6  193.73  5078.1  211.58  5092.1  217.01  5306.1  224.25  5738.5  222.08
    5882  213.72  5938.5  220.66  6301.6   237.3  7186.5  243.14  7375.1  247.43
#Mann= 20 ,-1 , 0
 -3580.1     .05       0 -3346.1     .05       0 -1070.2     .05       0
  -514.2     .12       0   468.5     .07       0   705.1     .05       0
    1041     .05       0  1483.7     .05       0  1951.1     .05       0
  2516.6     .05       0  3353.3     .05       0  4400.4     .05       0
  4600.4     .07       0  4911.1     .05       0  5073.6      .1       0
  5092.1     .05       0  5306.1     .07       0  5738.5     .12       0
  5938.5     .05       0  7186.5     .05       0
Bank Sta=4911.1,5073.6
XS Rating Curve= 0 ,0
Exp/Cntr=0.3,0.1

Type RM Length L Ch R = 1 ,130774  ,3853,3853,3853
BEGIN DESCRIPTION:
SANDIES CREEK 280.0
END DESCRIPTION:
XS GIS Cut Line= 3
      2467594.11     13641622.32      2461517.74     13638913.99
      2457871.88     13637316.76
#Sta/Elev= 30
 -1645.2  286.12 -1424.1  278.45  -375.3  232.58    18.2  215.64   942.9  202.63
  1621.4  205.23  1682.1  205.81  1699.8  193.27  1798.2  202.65  1975.7  203.05
  2692.2  204.46  3063.2  206.16  3708.7  210.42  4031.5  210.74  4182.9  203.65
  4359.3  210.32  4741.6  205.76  4796.5  197.88  4933.8  203.05  4941.2  192.88
  4942.7  190.88  5103.7  192.88  5108.7  219.36  5115.6  221.55  5451.5  226.73
  5820.5  224.13  7593.6  226.51  8033.3  231.78    8743  241.02  8987.8  243.97
#Mann= 20 ,-1 , 0
 -1645.2     .05       0 -1424.1     .05       0  -375.3     .05       0
    18.2     .12       0   942.9    .035       0  1621.4      .1       0
  1975.7     .07       0  2692.2     .05       0  3063.2     .05       0
  3708.7    .035       0  4031.5     .12       0  4359.3     .12       0
  4741.6      .1       0  4941.2     .05       0  5103.7      .1       0
  5451.5     .07       0  5820.5     .12       0  7593.6     .05       0
  8033.3     .05       0    8743     .05       0
Bank Sta=4941.2,5103.7
XS Rating Curve= 0 ,0
Exp/Cntr=0.3,0.1

Type RM Length L Ch R = 1 ,126921  ,4509,4509,4509
BEGIN DESCRIPTION:
SANDIES CREEK 282.0
END DESCRIPTION:
XS GIS Cut Line= 3
      2467510.81     13638141.37      2462902.29     13637828.92
      2458162.74     13637047.68
#Sta/Elev= 30
  1106.1  258.51  1645.1   236.3  2330.1  237.02  2595.3  228.97  2978.4  203.84
  4007.4  205.38  4461.8   206.3  4696.4  205.99  4880.6  200.07  4890.6  198.37
  4893.7  188.75  4895.3  186.65  5104.7  188.75    5117  200.18  5151.2  207.44
  5245.2  205.17  5726.4  208.71  5793.4  200.88  5878.9  207.56  5935.3  203.12
  6199.8  216.18  6354.3  217.24  7077.3  218.29  7390.5  220.81  7548.2   221.1
  9596.8  228.01  9973.9  238.72 10117.9  241.84 10444.6  244.08 10528.7  243.96
#Mann= 20 ,-1 , 0
  1106.1     .05       0  1645.1     .05       0  2330.1     .07       0
  2978.4     .12       0  4007.4     .07       0  4461.8     .07       0
  4696.4     .12       0  4893.7     .05       0  5104.7      .1       0
  5245.2      .1       0  5878.9     .05       0  6199.8    .035       0
  6354.3     .05       0  7077.3     .12       0  7390.5     .05       0
  7548.2     .12       0  9596.8     .07       0  9973.9     .12       0
 10117.9     .07       0 10444.6     .05       0
Bank Sta=4893.7,5104.7
XS Rating Curve= 0 ,0
Exp/Cntr=0.3,0.1

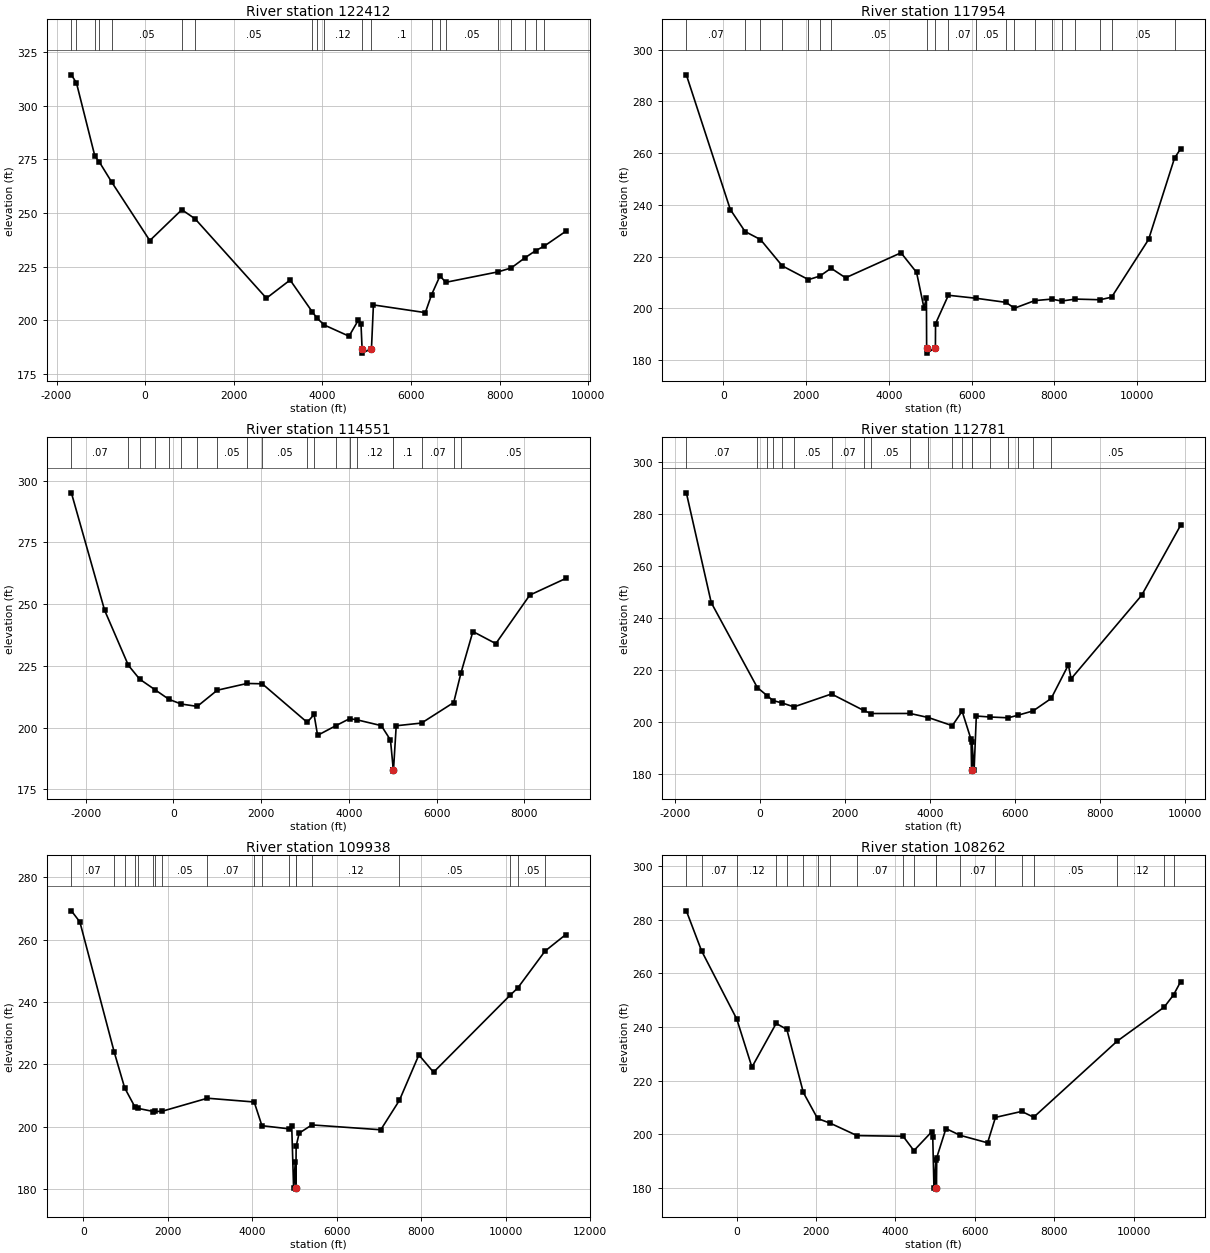
Type RM Length L Ch R = 1 ,122412  ,4458,4458,4458
BEGIN DESCRIPTION:
C20398
END DESCRIPTION:
XS GIS Cut Line= 4
      2469100.07     13634443.53      2464204.37     13635068.51
      2461652.29     13635042.47      2458214.83     13636318.49
#Sta/Elev= 30
   -1665  314.44 -1549.6   310.6 -1134.7  276.52 -1033.4  273.79  -754.2  264.42
   104.3  237.21     827  251.59  1126.2  247.35  2735.5  210.36  3270.4  218.83
  3766.3  204.13  3875.7  201.12  4040.1  197.88  4599.9  192.66  4809.9  200.14
  4869.9  198.29  4894.3  186.87  4895.9  184.77  5105.9  186.87  5149.9  207.23
  6321.1  203.64    6463  212.03  6652.6  220.77  6781.2  217.76  7961.1  222.63
  8258.8  224.45    8567  229.16    8808  232.48  9008.9   234.7  9489.3  241.52
#Mann= 20 ,-1 , 0
   -1665    .035       0 -1549.6     .07       0 -1134.7     .07       0
 -1033.4     .05       0  -754.2     .05       0     827    .035       0
  1126.2     .05       0  3766.3     .12       0  3875.7    .033       0
  4040.1     .12       0  4894.3     .05       0  5105.9      .1       0
    6463     .05       0  6652.6    .035       0  6781.2     .05       0
  7961.1     .12       0  8258.8     .05       0    8567     .05       0
    8808    .035       0  9008.9     .05       0
Bank Sta=4894.3,5105.9
XS Rating Curve= 0 ,0
Exp/Cntr=0.3,0.1

Type RM Length L Ch R = 1 ,117954  ,3403,3403,3403
BEGIN DESCRIPTION:
SANDIES CREEK 286.0
END DESCRIPTION:
XS GIS Cut Line= 3
      2468605.37     13633714.34      2463162.71     13632907.05
      2456730.42     13633245.59
#Sta/Elev= 30
  -890.8  290.27   171.1   238.2   527.5  229.69   900.2  226.59  1425.6  216.42
  2060.2  211.09  2334.7  212.47  2606.3   215.5  2955.9   211.8  4295.7  221.47
  4670.9   213.9  4849.4  200.26  4909.5  203.88  4914.5  184.78  4916.1  182.68
  5126.3  184.78  5129.8  194.08  5439.4  205.05    6118  203.87  6832.8   202.3
  7035.6  200.04  7524.3  202.98    7933  203.56    8173  202.82  8507.3  203.57
  9107.4  203.32  9383.7  204.32 10276.9  226.63 10903.9   258.1 11052.6   261.7
#Mann= 20 ,-1 , 0
  -890.8     .07       0   527.5     .05       0   900.2     .05       0
  1425.6     .05       0  2060.2     .05       0  2334.7    .035       0
  2606.3     .05       0  4914.5     .05       0  5126.3      .1       0
  5439.4     .07       0    6118     .05       0  6832.8     .12       0
  7035.6     .07       0  7524.3     .12       0    7933    .035       0
    8173     .12       0  8507.3     .12       0  9107.4     .07       0
  9383.7     .05       0 10903.9    .035       0
Bank Sta=4914.5,5126.3
XS Rating Curve= 0 ,0
Exp/Cntr=0.3,0.1

Type RM Length L Ch R = 1 ,114551  ,1770,1770,1770
BEGIN DESCRIPTION:
C20397
END DESCRIPTION:
XS GIS Cut Line= 4
      2468421.55     13633453.29       2464282.5     13631787.26
      2462225.21     13631032.05      2457850.17     13629547.66
#Sta/Elev= 30
 -2328.4   295.1 -1570.9  247.53 -1029.2  225.24  -770.9  219.62    -427  215.41
  -102.6  211.44   176.5  209.55   542.2  208.59   997.4  215.14  1677.2  217.88
  2023.9  217.75  3048.9  202.13  3205.4  205.31  3286.3  196.87  3707.8  200.82
  4017.8  203.63  4189.8  203.13  4739.1   200.8  4948.2  194.97    5013  182.87
  5013.3  182.37    5017  182.87  5079.2  200.75    5656  201.84  6389.9  210.15
  6557.7  222.26  6827.8  238.92  7350.4  234.02  8124.9  253.67  8944.9  260.41
#Mann= 20 ,-1 , 0
 -2328.4     .07       0 -1029.2     .07       0  -770.9     .05       0
    -427    .035       0  -102.6     .07       0   176.5     .05       0
   542.2     .07       0   997.4     .05       0  1677.2    .035       0
  2023.9     .05       0  3048.9     .05       0  3205.4     .07       0
  3707.8     .05       0  4017.8     .05       0  4189.8     .12       0
    5013     .05       0    5017      .1       0    5656     .07       0
  6389.9     .07       0  6557.7     .05       0
Bank Sta=5013,5017
XS Rating Curve= 0 ,0
Exp/Cntr=0.3,0.1

Type RM Length L Ch R = 1 ,112781  ,2843,2843,2843
BEGIN DESCRIPTION:
C20396
END DESCRIPTION:
XS GIS Cut Line= 3
      2468266.83     13633089.32      2463214.79     13629964.34
      2458240.83     13627177.89
#Sta/Elev= 30
 -1736.9  288.07 -1150.8  245.84   -65.9  213.22   161.5  210.14   304.1  208.21
   523.7  207.26   797.7  205.78  1681.4  210.74  2435.3  204.44  2610.2  203.23
  3532.5  203.25  3964.2  201.67  4525.9  198.55  4757.6  204.09  4967.5  193.26
  4980.9  181.58  4981.1  181.08  4984.9  181.58  4989.2  192.37    5040  181.66
  5091.9  202.26    5414  201.89  5843.2  201.58  6075.8  202.59  6429.4  204.23
  6854.6  209.01  7259.5  221.91  7324.6   216.6  8984.3  248.65  9904.8  275.65
#Mann= 20 ,-1 , 0
 -1736.9     .07       0   -65.9    .035       0   161.5      .1       0
   304.1    .035       0   523.7     .12       0   797.7     .05       0
  1681.4     .07       0  2435.3     .12       0  2610.2     .05       0
  3532.5    .035       0  3964.2     .07       0  4525.9     .07       0
  4757.6     .12       0  4980.9     .05       0  4984.9      .1       0
    5414     .12       0  5843.2     .07       0  6075.8     .12       0
  6429.4     .07       0  6854.6     .05       0
Bank Sta=4980.9,4984.9
XS Rating Curve= 0 ,0
Exp/Cntr=0.3,0.1

Type RM Length L Ch R = 1 ,109938  ,1676,1676,1676
BEGIN DESCRIPTION:
C20395
END DESCRIPTION:
XS GIS Cut Line= 3
      2468318.92     13631735.14      2464985.62     13628167.47
      2458449.13     13626214.33
#Sta/Elev= 30
  -286.8  269.24   -85.7  265.67   727.1  223.95   974.9  212.45  1220.1  206.27
  1299.2  205.85  1656.3  204.87  1687.2  204.88  1854.1  204.92    2934  209.13
  4041.4  207.92  4224.6  200.32  4859.7  199.32  4930.4  200.18  4974.2  180.47
  5013.9  188.53  5023.8  180.47    5024  179.97  5027.8  180.47  5034.7  193.74
  5106.7  197.93  5406.8  200.57  7038.6  199.01  7478.9  208.43  7940.7  223.02
  8287.6  217.47   10104  242.21 10279.5  244.46 10926.8  256.31 11417.8  261.62
#Mann= 19 ,-1 , 0
  -286.8     .07       0   727.1    .035       0   974.9     .07       0
  1220.1     .12       0  1299.2     .07       0  1656.3     .05       0
  1687.2      .1       0  1854.1     .05       0    2934     .07       0
  4041.4    .035       0  4224.6     .07       0  4859.7      .1       0
  5023.8     .05       0  5027.8      .1       0  5406.8     .12       0
  7478.9     .05       0   10104     .07       0 10279.5     .05       0
 10926.8    .035       0
Bank Sta=5023.8,5027.8
XS Rating Curve= 0 ,0
Exp/Cntr=0.3,0.1

Type RM Length L Ch R = 1 ,108262  ,3572,3572,3572
BEGIN DESCRIPTION:
C20394
END DESCRIPTION:
XS GIS Cut Line= 3
      2471209.58     13626318.51      2466209.58     13626787.26
      2458839.79     13625849.76
#Sta/Elev= 30
 -1266.5  283.31  -883.1   268.4     3.9  242.98   385.3  225.08   995.3  241.37
  1264.6  239.15  1679.3  215.67  2038.1  205.96  2362.5  204.18    3031  199.59
    4194  199.32  4464.9  193.99  4909.2  200.94  4939.5  199.18  4969.7  180.15
  5020.1  190.47  5028.3  180.15  5028.5  179.65  5032.3  180.15  5040.3  191.41
  5272.1  202.21  5629.6  199.69  6320.5   196.9    6519  206.37  7180.1   208.6
  7481.3  206.43  9582.5  234.75 10768.3  247.44 11004.5     252 11184.6  256.97
#Mann= 20 ,-1 , 0
 -1266.5     .07       0  -883.1     .07       0     3.9     .12       0
   995.3     .07       0  1264.6     .07       0  1679.3     .12       0
  2038.1     .07       0  2362.5     .12       0    3031     .07       0
    4194     .07       0  4464.9     .12       0  5028.3     .05       0
  5032.3      .1       0  5629.6     .07       0    6519    .045       0
  7180.1     .05       0  7481.3     .05       0  9582.5     .12       0
 10768.3     .05       0 11004.5     .07       0
Bank Sta=5028.3,5032.3
XS Rating Curve= 0 ,0
Exp/Cntr=0.3,0.1

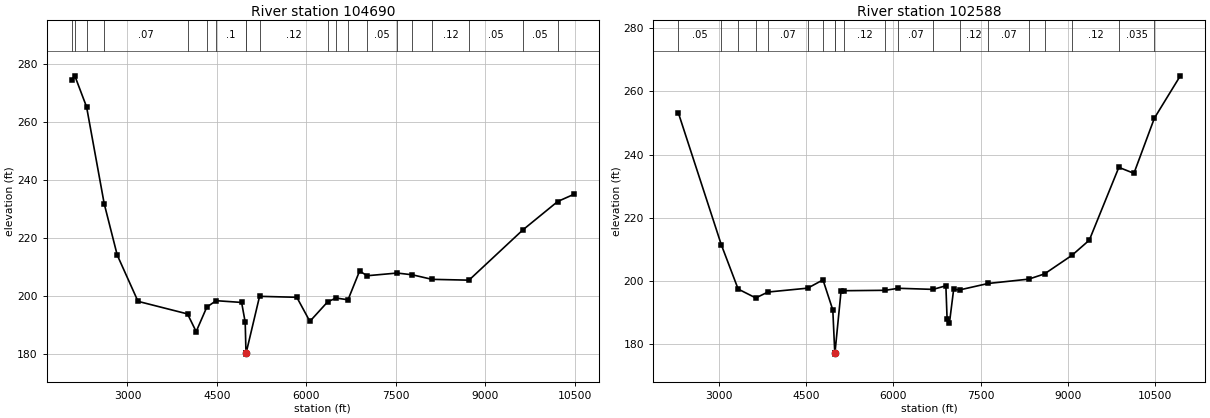
Type RM Length L Ch R = 1 ,104690  ,2102,2102,2102
BEGIN DESCRIPTION:
SANDIES CREEK 291.0
END DESCRIPTION:
XS GIS Cut Line= 3
      2469074.97       13624825.      2465792.91     13624573.72
       2460688.7     13625068.51
#Sta/Elev= 30
  2065.6   274.6  2116.7  275.96  2313.8  265.24  2609.2   231.8  2827.8  214.03
  3176.4  198.03  4006.6  193.68  4151.7  187.58  4330.2  196.04  4486.3  198.26
  4913.9  197.65  4974.1  190.81  4986.9  180.29  4987.2  179.79  4990.9  180.29
  5214.9  199.76  5839.7  199.43  6058.4  191.11  6357.3  197.87  6498.7  199.17
  6698.4  198.57  6892.3   208.5  7018.6  206.88  7523.1  207.81  7777.2   207.2
  8107.4  205.63  8726.7  205.35  9628.3  222.68 10214.3  232.53 10485.4  235.01
#Mann= 20 ,-1 , 0
  2065.6    .035       0  2116.7     .07       0  2313.8    .035       0
  2609.2     .07       0  4006.6      .1       0  4330.2     .12       0
  4486.3      .1       0  4986.9     .05       0  4990.9      .1       0
  5214.9     .12       0  6357.3    .035       0  6498.7     .12       0
  6698.4     .05       0  7018.6     .05       0  7523.1    .045       0
  7777.2     .12       0  8107.4     .12       0  8726.7     .05       0
  9628.3     .05       0 10214.3     .05       0
Bank Sta=4986.9,4990.9
XS Rating Curve= 0 ,0
Exp/Cntr=0.3,0.1

Type RM Length L Ch R = 1 ,102588  ,2423,2423,2423
BEGIN DESCRIPTION:
SANDIES CREEK 292.0
END DESCRIPTION:
XS GIS Cut Line= 3
      2468875.02     13623775.01        2466375.       13622775.
      2460610.61     13621396.63
#Sta/Elev= 30
  2307.8  253.29  3046.4  211.54  3336.1   197.5  3638.5  194.69    3848  196.55
  4529.9  197.78  4792.9  200.39  4961.4  190.89    4995  177.43  4995.3  176.93
    4999  177.43    5103  196.86  5157.3  196.97  5862.7   197.1  6085.9  197.74
    6682  197.39  6902.6  198.53  6923.1  188.17  6964.3  186.85  7036.2  197.41
  7138.4  197.22  7628.8  199.26  8324.9  200.63  8595.8  202.28  9068.1  208.17
    9365  212.95  9871.9  235.96 10131.1  234.07 10482.4  251.51 10927.3  264.88
#Mann= 20 ,-1 , 0
  2307.8     .05       0  3046.4     .12       0  3336.1     .07       0
  3638.5     .07       0    3848     .07       0  4529.9     .12       0
  4792.9      .1       0    4995     .05       0    4999      .1       0
  5157.3     .12       0  5862.7     .07       0  6085.9     .07       0
    6682      .1       0  7138.4     .12       0  7628.8     .07       0
  8324.9     .12       0  8595.8     .05       0  9068.1     .12       0
  9871.9    .035       0 10482.4     .07       0
Bank Sta=4995,4999
XS Rating Curve= 0 ,0
Exp/Cntr=0.3,0.1