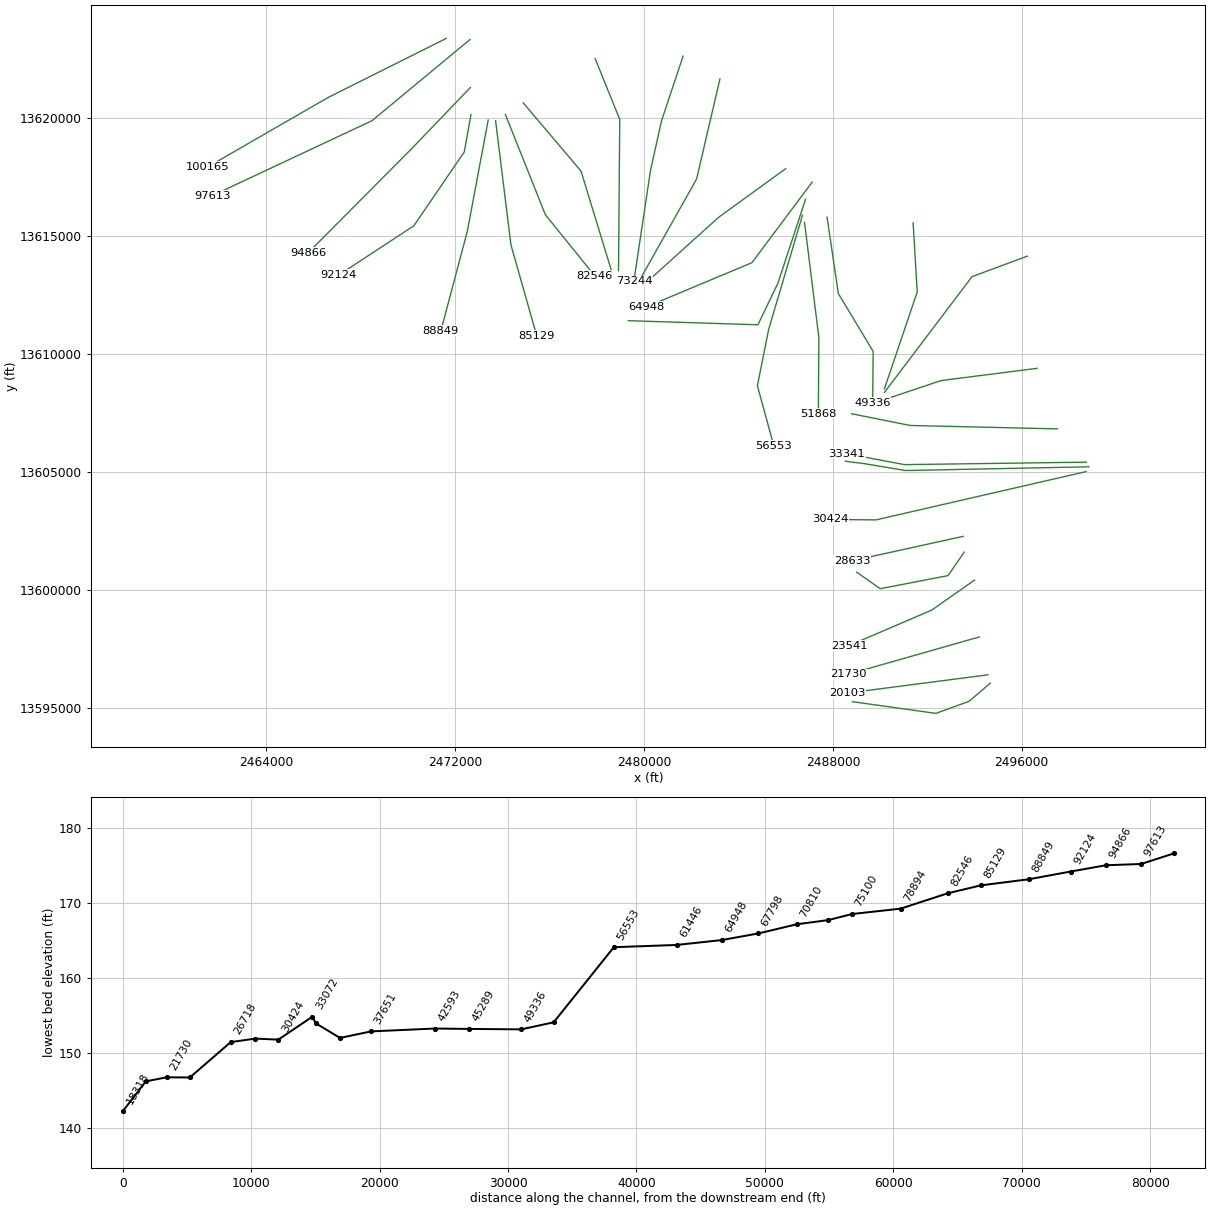
HEC-RAS study SANDIES CREEK.prj: SANDIES CREEK Base Level Engineering

--- SANDIES CREEK.g01 (geometry) --- (continued)

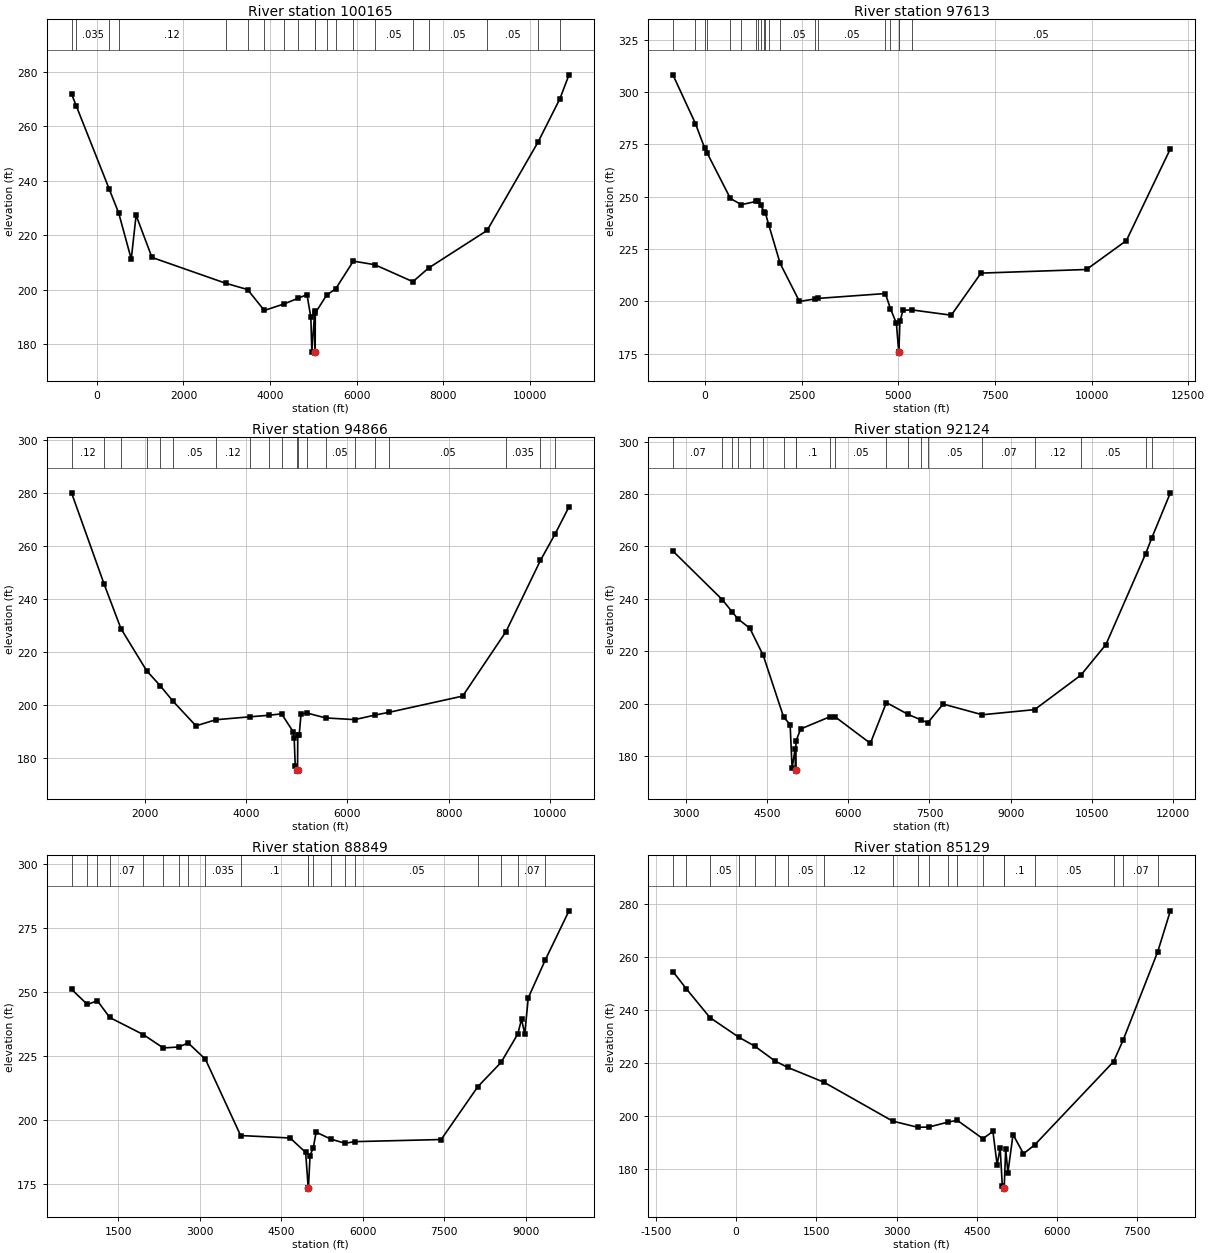
Type RM Length L Ch R = 1 ,100165  ,2552,2552,2552
BEGIN DESCRIPTION:
SANDIES CREEK 293.0
END DESCRIPTION:
XS GIS Cut Line= 3
      2471625.03     13623375.01        2466625.       13620875.
      2461522.09      13617933.1
#Sta/Elev= 30
  -583.2  271.94  -472.5  267.49   286.7  236.93   506.3  228.08   794.8   211.2
   906.6  227.32  1272.8  211.81  2972.4  202.32  3479.7  199.99  3865.6   192.3
  4327.9  194.74  4641.1  196.77  4850.5  198.13  4939.9  189.75  4962.3  177.11
  5030.1  191.98  5035.7  177.11    5036  176.61  5039.7  177.11  5042.2  191.34
  5301.1  197.89  5514.6  200.31  5920.6  210.45  6414.2  209.14  7294.7  202.89
  7655.3  207.89  9007.9  221.74 10186.3  254.32 10688.1  270.19 10897.2  278.97
#Mann= 20 ,-1 , 0
  -583.2     .07       0  -472.5    .035       0   286.7     .05       0
   506.3     .12       0  2972.4     .05       0  3479.7     .12       0
  3865.6     .12       0  4327.9     .07       0  4641.1     .12       0
  5035.7     .05       0  5039.7     .12       0  5301.1     .12       0
  5514.6     .05       0  5920.6     .12       0  6414.2     .05       0
  7294.7     .12       0  7655.3     .05       0  9007.9     .05       0
 10186.3     .07       0 10688.1     .05       0
Bank Sta=5035.7,5039.7
XS Rating Curve= 0 ,0
Exp/Cntr=0.3,0.1

Type RM Length L Ch R = 1 ,97613   ,2747,2747,2747
BEGIN DESCRIPTION:
SANDIES CREEK 294.0
END DESCRIPTION:
XS GIS Cut Line= 3
      2472624.99     13623324.99      2468475.21     13619886.22
      2461704.37     13616709.13
#Sta/Elev= 30
    -832  308.31  -249.5  285.01   -14.3  273.44    54.3  270.89   654.5  249.19
   936.8  246.21    1321  247.75  1369.5  247.95  1436.2  245.86  1529.4  242.93
    1561  242.14  1646.5  236.59  1942.1   218.1  2441.5  199.92  2837.9  201.11
  2926.4  201.38  4664.2   203.7  4793.9  196.49  4949.2   189.5  5009.6   175.7
  5009.8   175.2  5013.6   175.7  5040.5  190.41    5121  195.65  5344.3  195.89
  6369.2  193.34  7137.5  213.47  9867.1   215.2 10898.1  229.02 12036.6  272.94
#Mann= 20 ,-1 , 0
    -832    .035       0  -249.5     .07       0   -14.3    .035       0
    54.3     .07       0   654.5    .035       0   936.8     .05       0
    1321     .12       0  1369.5     .07       0  1436.2     .12       0
  1529.4     .07       0    1561     .12       0  1646.5    .035       0
  1942.1     .05       0  2837.9    .035       0  2926.4     .05       0
  4664.2     .12       0  4793.9      .1       0  5009.6     .05       0
  5013.6      .1       0  5344.3     .05       0
Bank Sta=5009.6,5013.6
XS Rating Curve= 0 ,0
Exp/Cntr=0.3,0.1

Type RM Length L Ch R = 1 ,94866   ,2742,2742,2742
BEGIN DESCRIPTION:
C20393
END DESCRIPTION:
XS GIS Cut Line= 3
      2472639.78     13621290.29      2470167.91     13618714.34
      2465766.84     13614287.23
#Sta/Elev= 30
   558.3     280  1203.7  245.43  1533.1  228.77  2039.3  212.92  2306.9  207.24
  2559.2  201.42  3012.5  192.11    3404  194.41  4083.3  195.53  4452.3   196.1
  4700.9  196.64  4933.9   189.8  4950.2  187.36  4971.5  176.79  5012.4  175.53
  5012.6  175.03  5016.4  175.53    5021  188.64  5049.2  188.75  5084.6  196.43
    5195  196.98  5573.1  195.09  6144.6  194.46  6547.7  196.19  6827.9  197.24
  8273.6  203.33  9129.1  227.68  9807.4   254.5 10097.5   264.5 10370.9  274.71
#Mann= 20 ,-1 , 0
   558.3     .12       0  1203.7     .12       0  1533.1     .07       0
  2039.3     .12       0  2306.9     .12       0  2559.2     .05       0
    3404     .12       0  4083.3     .05       0  4452.3     .12       0
  4700.9      .1       0  5012.4     .05       0  5016.4      .1       0
    5195     .12       0  5573.1     .05       0  6144.6     .12       0
  6547.7     .12       0  6827.9     .05       0  9129.1    .035       0
  9807.4     .07       0 10097.5     .05       0
Bank Sta=5012.4,5016.4
XS Rating Curve= 0 ,0
Exp/Cntr=0.3,0.1

Type RM Length L Ch R = 1 ,92124   ,3275,3275,3275
BEGIN DESCRIPTION:
C20392
END DESCRIPTION:
XS GIS Cut Line= 4
      2472667.92     13620146.65      2472381.46     13618558.09
      2470246.04     13615433.09      2467068.98     13613349.78
#Sta/Elev= 30
  2756.4  258.24  3668.5   239.7  3856.4   234.9  3954.8  232.42  4178.8  228.76
  4425.7  218.44  4802.2  194.92    4924  191.92  4959.9  175.22  5016.8   182.8
  5023.2  174.69  5023.4  174.19  5027.2  174.69  5031.7  185.65  5118.4  190.29
  5670.1  195.05  5762.3  194.83  6407.3  184.81  6703.8  200.38    7103  195.88
  7346.4  193.73  7468.1  192.65    7753   199.8  8477.9  195.72  9444.1  197.68
 10298.7  210.82 10763.3  222.55 11499.1   257.3 11613.2  263.37 11954.7  280.49
#Mann= 20 ,-1 , 0
  2756.4     .07       0  3668.5     .12       0  3856.4     .07       0
  3954.8     .12       0  4178.8     .05       0  4425.7     .12       0
  4802.2      .1       0  5023.2     .05       0  5027.2      .1       0
  5670.1     .07       0  5762.3     .05       0  6703.8     .05       0
    7103     .12       0  7346.4     .05       0  7468.1     .05       0
  8477.9     .07       0  9444.1     .12       0 10298.7     .05       0
 11499.1    .035       0 11613.2     .07       0
Bank Sta=5023.2,5027.2
XS Rating Curve= 0 ,0
Exp/Cntr=0.3,0.1

Type RM Length L Ch R = 1 ,88849   ,3720,3720,3720
BEGIN DESCRIPTION:
SANDIES CREEK 295.0
END DESCRIPTION:
XS GIS Cut Line= 3
      2473396.87     13619911.15      2472511.66     13615198.72
      2471391.87     13610979.96
#Sta/Elev= 30
   639.4  251.02     931  245.12  1115.4  246.58  1341.9  240.05  1962.7  233.36
  2328.5  228.18  2611.2  228.54  2786.7  230.12  3104.1  223.79  3752.9  194.05
  4664.7  193.08  4949.6  187.48  4997.5  173.66  4997.7  173.16  5001.5  173.66
    5031  186.23  5090.9  189.33    5143  195.36  5411.7  192.67  5672.3  191.04
  5862.7  191.67  7445.3  192.49  8122.3  213.13  8548.2  222.53  8856.4  233.63
  8924.8  239.31  8984.8  233.71    9049   247.7    9364  262.53  9799.1  281.61
#Mann= 20 ,-1 , 0
   639.4     .07       0     931     .07       0  1115.4    .035       0
  1341.9     .07       0  1962.7     .07       0  2328.5     .07       0
  2611.2     .07       0  2786.7    .035       0  3104.1    .035       0
  3752.9      .1       0  4997.5     .05       0  5001.5      .1       0
  5090.9     .12       0  5411.7      .1       0  5672.3     .07       0
  5862.7     .05       0  8122.3     .12       0  8548.2     .12       0
  8856.4     .07       0    9364     .07       0
Bank Sta=4997.5,5001.5
XS Rating Curve= 0 ,0
Exp/Cntr=0.3,0.1

Type RM Length L Ch R = 1 ,85129   ,2583,2583,2583
BEGIN DESCRIPTION:
C20391
END DESCRIPTION:
XS GIS Cut Line= 3
       2473709.8     13619884.48      2474360.62      13614625.8
      2475454.38     13610771.59
#Sta/Elev= 30
 -1183.3  254.47  -932.8  247.97  -490.5  237.09    45.8  229.73   347.9   226.3
   723.5  220.75   965.7  218.27  1639.2  212.72  2928.3  198.01  3396.5  195.69
  3606.4  195.78  3958.5  197.63  4135.1  198.32  4614.3  191.39  4802.4  194.11
  4881.4  181.53  4937.5  187.94  4979.1  173.36  5009.7  172.85  5009.9  172.35
  5013.7  172.85  5041.5  187.47  5083.1  178.58  5178.6  192.95  5374.1  185.72
  5585.2  189.07  7058.5  220.45  7236.6  228.49  7884.8  261.91  8121.9  277.38
#Mann= 20 ,-1 , 0
 -1183.3    .035       0  -932.8     .05       0  -490.5     .05       0
    45.8     .07       0   347.9     .05       0   723.5     .07       0
   965.7     .05       0  1639.2     .12       0  2928.3    .035       0
  3396.5     .07       0  3606.4     .12       0  3958.5     .07       0
  4135.1     .12       0  4614.3     .12       0  5009.7     .05       0
  5013.7      .1       0  5585.2     .05       0  7058.5     .12       0
  7236.6     .07       0  7884.8     .07       0
Bank Sta=5009.7,5013.7
XS Rating Curve= 0 ,0
Exp/Cntr=0.3,0.1

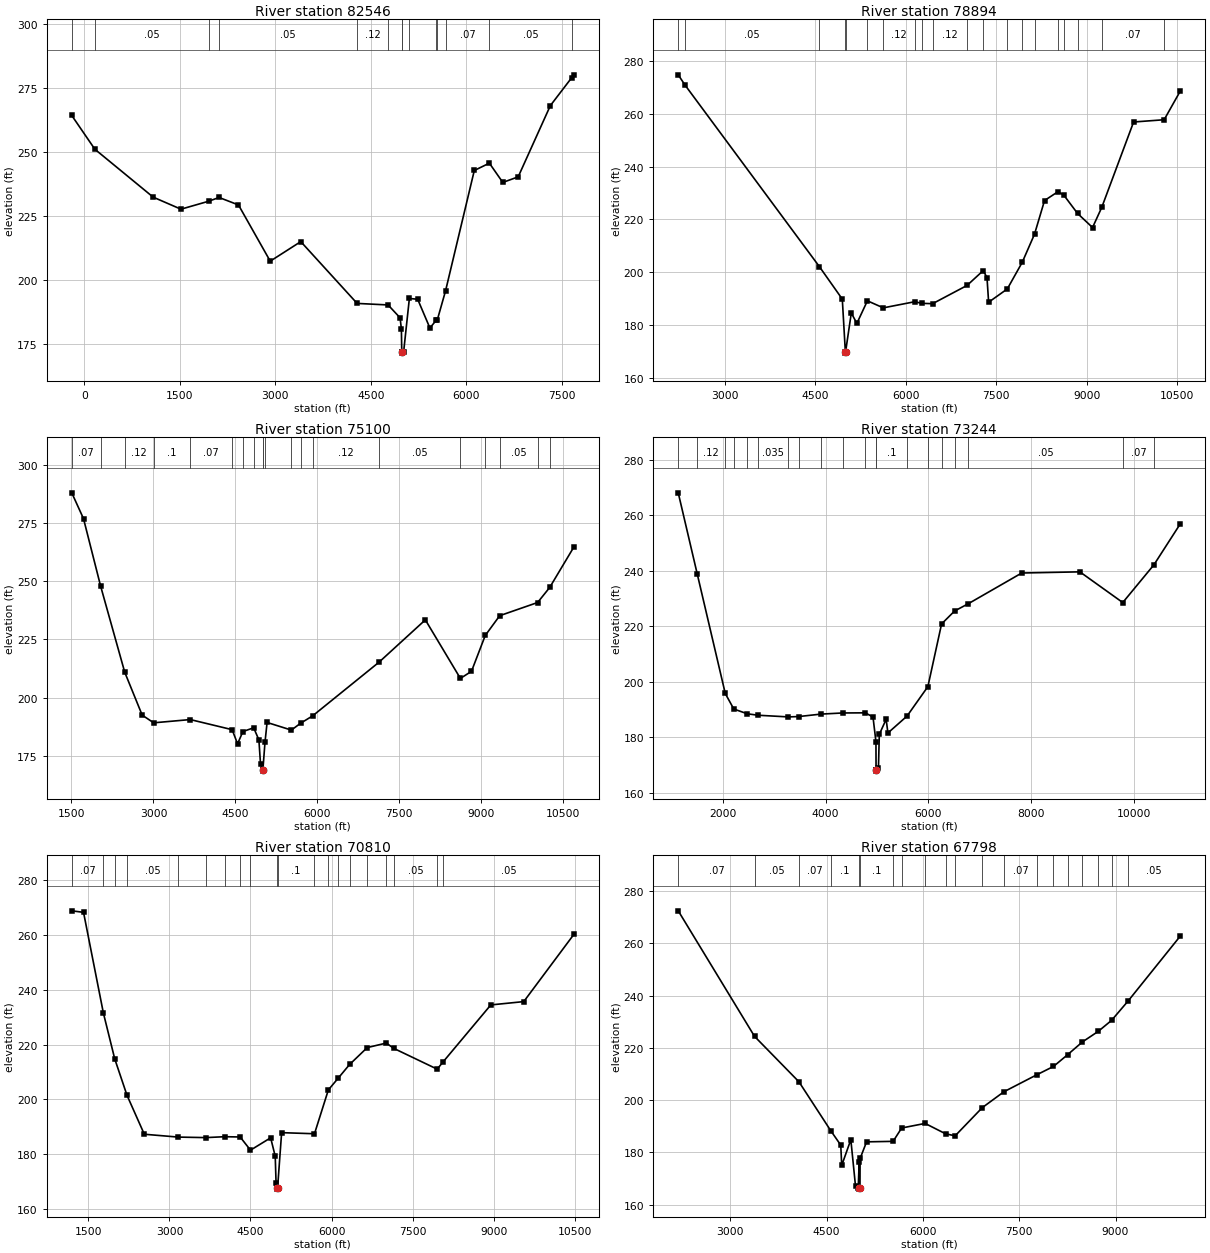
Type RM Length L Ch R = 1 ,82546   ,3652,3652,3652
BEGIN DESCRIPTION:
C20390
END DESCRIPTION:
XS GIS Cut Line= 3
      2474126.25     13620146.62      2475818.96     13615901.84
      2477902.29     13613323.71
#Sta/Elev= 30
  -197.8  264.27     165  251.06  1080.4  232.32  1517.1  227.61  1950.4  230.71
  2115.5  232.19    2420  229.27  2918.8  207.27  3398.6  214.92  4283.4  190.74
  4769.6  190.14  4957.7  185.12  4978.5  180.77  4984.3  171.79  4984.6  171.29
  4988.3  171.79  5013.7  171.79  5103.8  192.68  5234.3  192.37  5426.2  181.12
  5527.1   184.2  5543.1  184.33    5672  195.66  6123.4  242.75  6360.1  245.62
  6571.1  238.08  6812.6  240.26  7317.9  268.14  7654.4   279.1  7686.7  280.18
#Mann= 14 ,-1 , 0
  -197.8     .07       0     165     .05       0  1950.4    .035       0
  2115.5     .05       0  4283.4     .12       0  4769.6      .1       0
  4984.3     .05       0  4988.3      .1       0  5103.8     .12       0
  5527.1     .07       0  5543.1     .12       0    5672     .07       0
  6360.1     .05       0  7654.4     .07       0
Bank Sta=4984.3,4988.3
XS Rating Curve= 0 ,0
Exp/Cntr=0.3,0.1

Type RM Length L Ch R = 1 ,78894   ,3794,3794,3794
BEGIN DESCRIPTION:
C20389
END DESCRIPTION:
XS GIS Cut Line= 3
      2474882.05     13620640.72      2477329.37      13617750.8
       2478657.5     13613401.83
#Sta/Elev= 30
  2221.7  274.79  2331.3     271    4566  202.01  4945.1  189.73  4995.7  169.75
    4996  169.25  4999.7  169.75  5094.5  184.48  5186.8  180.52  5361.6  189.09
    5626  186.42  6144.9  188.73  6269.3  188.13  6443.9     188  7015.8  194.92
  7284.8  200.56    7347  197.87    7374  188.55  7683.8  193.59  7931.6  203.68
  8135.9  214.37    8302  227.12  8525.8  230.48    8624  229.11  8850.7  222.21
  9099.2  216.88  9252.6  224.56  9780.5   256.9 10287.7  257.76 10555.9  268.65
#Mann= 20 ,-1 , 0
  2221.7     .07       0  2331.3     .05       0    4566     .12       0
  4995.7     .05       0  4999.7      .1       0  5361.6     .12       0
    5626     .12       0  6144.9     .12       0  6269.3     .05       0
  6443.9     .12       0  7015.8     .12       0  7284.8     .12       0
  7683.8     .12       0  7931.6     .07       0  8135.9     .05       0
  8525.8    .035       0    8624     .05       0  8850.7     .07       0
  9252.6     .07       0 10287.7     .05       0
Bank Sta=4995.7,4999.7
XS Rating Curve= 0 ,0
Exp/Cntr=0.3,0.1

Type RM Length L Ch R = 1 ,75100   ,1856,1856,1856
BEGIN DESCRIPTION:
C20388
END DESCRIPTION:
XS GIS Cut Line= 3
      2477928.32     13622516.45        2478970.      13619938.3
      2478917.91     13613532.04
#Sta/Elev= 30
  1505.6  287.88  1720.6  276.79  2033.8  247.85  2474.7  210.95  2793.7  192.56
  3004.3  189.25  3674.3  190.64  4439.8  186.31  4539.5  180.24  4636.9   185.5
    4834  187.12  4929.6  181.93  4959.6  171.45  4998.4  169.03  4998.7  168.53
  5002.4  169.03  5041.3  180.93  5079.6   189.4  5523.9  186.13  5692.3  189.06
  5913.1  192.23  7128.4  215.26  7975.3   233.4  8616.5  208.29  8819.7  211.33
  9071.6  226.71  9336.1  235.19 10029.6  240.84 10250.9   247.3 10692.7  264.63
#Mann= 20 ,-1 , 0
  1505.6     .07       0  2033.8     .12       0  2474.7     .12       0
  3004.3      .1       0  3674.3     .07       0  4439.8     .07       0
  4636.9    .035       0    4834      .1       0  4998.4     .05       0
  5002.4      .1       0  5041.3     .12       0  5523.9     .07       0
  5692.3     .05       0  5913.1     .12       0  7128.4     .05       0
  8616.5     .12       0  9071.6     .05       0  9336.1     .05       0
 10029.6     .12       0 10250.9     .05       0
Bank Sta=4998.4,5002.4
XS Rating Curve= 0 ,0
Exp/Cntr=0.3,0.1

Type RM Length L Ch R = 1 ,73244   ,2434,2434,2434
BEGIN DESCRIPTION:
C20387
END DESCRIPTION:
XS GIS Cut Line= 4
      2481652.18     13622620.26      2480740.83     13619886.22
      2480272.08     13617776.84      2479568.96     13613089.35
#Sta/Elev= 30
  1128.2  268.17  1499.5   238.8  2044.4  195.75  2210.3  190.14  2474.9  188.41
  2685.2  187.89    3273  187.29  3476.6  187.42  3906.3   188.3  4332.7  188.71
  4773.8  188.76  4923.1  187.24  4980.7  178.33  4982.7  168.22    4983  167.72
  4986.7  168.22  5029.4  168.96    5046  180.98  5179.2  186.43  5213.8  181.49
  5586.3  187.59  5992.6  198.23  6259.1  220.84    6513  225.52  6778.4  228.13
  7821.1  239.23  8953.8  239.65  9789.6  228.57 10397.5  242.21 10910.9  256.99
#Mann= 20 ,-1 , 0
  1128.2     .07       0  1499.5     .12       0  2044.4     .05       0
  2210.3    .035       0  2474.9     .05       0  2685.2    .035       0
    3273     .07       0  3476.6     .12       0  3906.3     .07       0
  4332.7     .12       0  4773.8    .035       0  4982.7     .05       0
  4986.7      .1       0  5586.3     .07       0  5992.6     .05       0
  6259.1     .07       0    6513    .035       0  6778.4     .05       0
  9789.6     .07       0 10397.5     .05       0
Bank Sta=4982.7,4986.7
XS Rating Curve= 0 ,0
Exp/Cntr=0.3,0.1

Type RM Length L Ch R = 1 ,70810   ,3012,3012,3012
BEGIN DESCRIPTION:
C20386
END DESCRIPTION:
XS GIS Cut Line= 3
      2483214.78     13621657.01      2482225.21     13617412.26
      2479803.32     13613115.36
#Sta/Elev= 30
  1192.8  268.89  1410.5  268.34  1777.6  231.55  1987.2  214.82  2214.5  201.48
    2535  187.23  3163.2  186.19  3672.7     186  4022.3  186.33  4308.9  186.23
    4500  181.41  4872.8  185.92  4957.9  179.18  4973.5  169.25  4997.5  167.67
  4997.8  167.17  5001.5  167.67  5076.2  187.81  5684.5  187.41  5940.9  203.44
  6123.7  207.74  6334.7  212.74  6660.6  218.91  7013.1  220.55    7153   218.6
  7955.3  211.02    8061   213.6  8947.2   234.5  9556.9  235.71 10483.8  260.27
#Mann= 20 ,-1 , 0
  1192.8     .07       0  1777.6     .12       0  1987.2     .12       0
  2214.5     .05       0  3163.2     .07       0  3672.7     .07       0
  4022.3     .07       0  4308.9     .07       0    4500      .1       0
  4997.5     .05       0  5001.5      .1       0  5684.5     .12       0
  5940.9     .05       0  6123.7     .07       0  6334.7     .05       0
  6660.6     .07       0  7013.1     .07       0    7153     .05       0
  7955.3     .07       0    8061     .05       0
Bank Sta=4997.5,5001.5
XS Rating Curve= 0 ,0
Exp/Cntr=0.3,0.1

Type RM Length L Ch R = 1 ,67798   ,2850,2850,2850
BEGIN DESCRIPTION:
C20385
END DESCRIPTION:
XS GIS Cut Line= 3
      2486000.66     13617854.54      2483162.71     13615797.67
      2479959.62     13612907.08
#Sta/Elev= 30
  2189.4  272.42  3377.6  224.39  4069.2  207.01  4563.3  188.35  4720.6  182.77
  4735.3  175.01  4877.5  184.85  4950.5  167.06  4992.7  166.51  5007.4  176.23
  5011.4  166.44  5011.7  165.94  5015.4  166.44  5022.1  177.67  5122.6  184.03
    5536  184.22  5669.2  189.33  6034.3  191.08    6354   187.1  6502.3  186.34
  6925.2  197.13  7261.5  203.19  7775.3  209.71  8033.7  212.88  8255.1   217.4
  8484.1  222.26  8730.2  226.29  8938.2  230.51  9196.6  237.94 10008.9  262.77
#Mann= 20 ,-1 , 0
  2189.4     .07       0  3377.6     .05       0  4069.2     .07       0
  4563.3      .1       0  5011.4     .05       0  5015.4      .1       0
    5536     .12       0  5669.2     .07       0  6034.3     .05       0
    6354     .12       0  6502.3     .12       0  6925.2     .12       0
  7261.5     .07       0  7775.3     .12       0  8033.7     .05       0
  8255.1     .07       0  8484.1     .05       0  8730.2     .07       0
  8938.2     .07       0  9196.6     .05       0
Bank Sta=5011.4,5015.4
XS Rating Curve= 0 ,0
Exp/Cntr=0.3,0.1

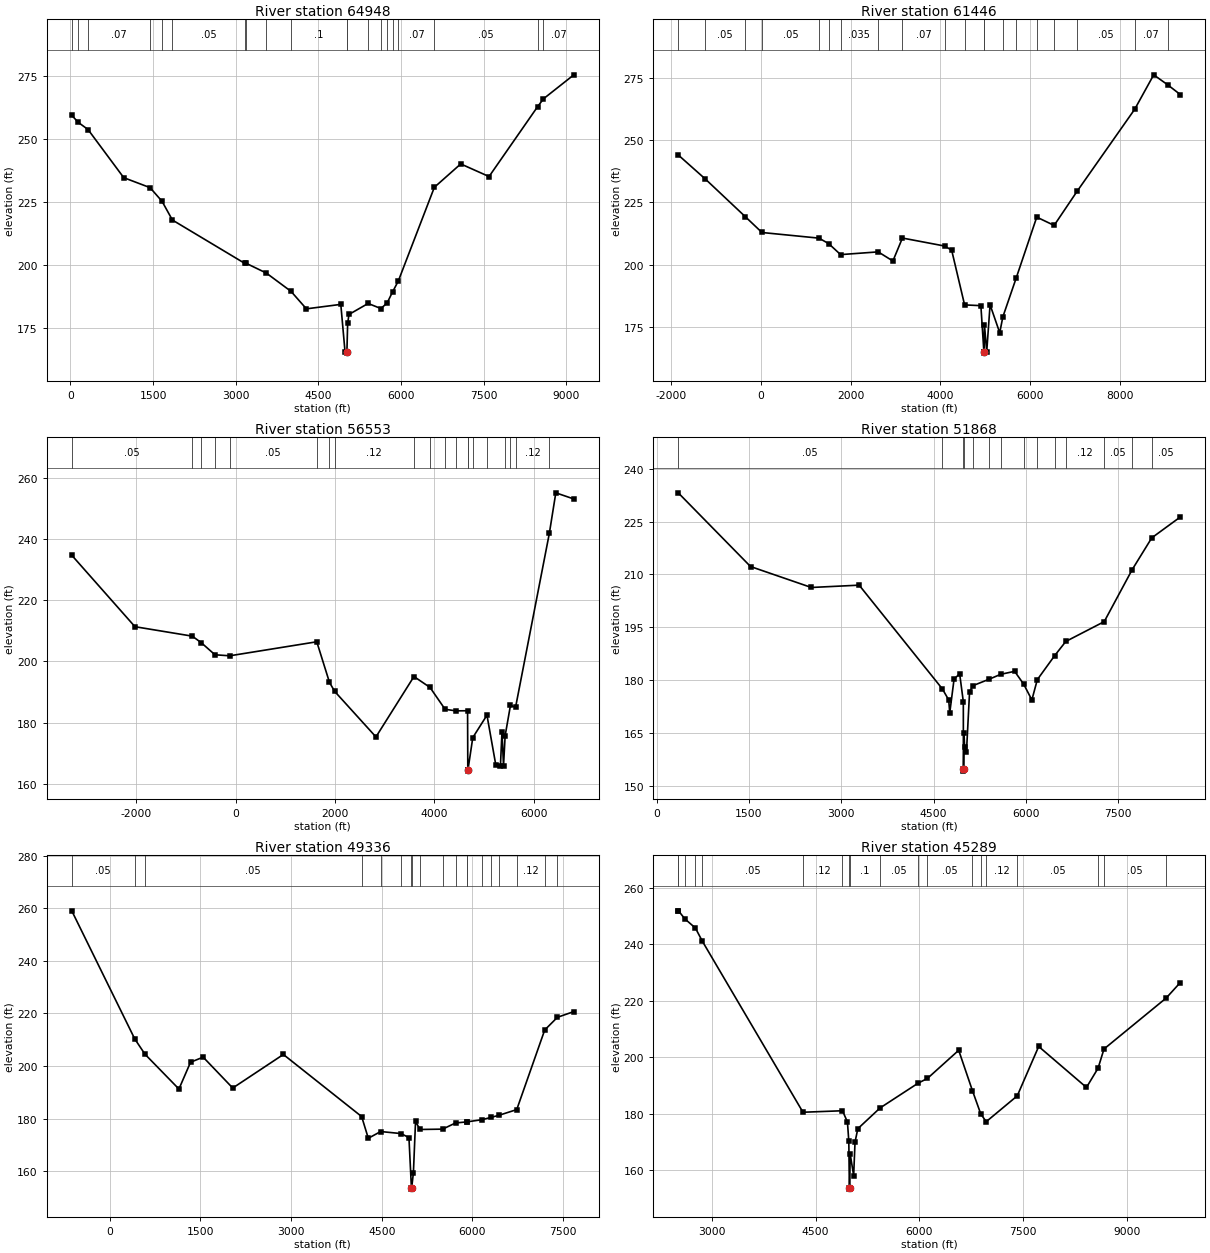
Type RM Length L Ch R = 1 ,64948   ,3502,3502,3502
BEGIN DESCRIPTION:
C20384
END DESCRIPTION:
XS GIS Cut Line= 3
      2487119.78     13617280.36      2484568.96     13613870.59
      2480089.78     13611995.59
#Sta/Elev= 30
    23.5  259.25   142.9  256.43   318.4  253.63   966.8  234.56  1444.3  230.61
  1661.7  225.21  1850.2  217.78  3161.4  200.64  3186.8  200.66  3554.9  196.78
  4003.2  189.53  4282.6   182.6  4907.2  184.37    4984  165.56    5014  165.56
  5014.3  165.06    5018  165.56  5031.5   176.8  5055.3  180.38    5403  184.73
  5635.5  182.72    5748  184.93  5846.3  189.28  5951.7  193.65  6605.4  230.74
  7084.4     240  7598.1     235  8481.3  262.72  8586.7   265.8  9137.6  275.29
#Mann= 20 ,-1 , 0
    23.5     .05       0   142.9    .035       0   318.4     .07       0
  1444.3     .05       0  1661.7     .07       0  1850.2     .05       0
  3161.4     .12       0  3186.8     .05       0  3554.9     .12       0
  4003.2      .1       0    5014     .05       0    5018      .1       0
    5403     .12       0  5635.5     .07       0    5748     .12       0
  5846.3     .05       0  5951.7     .07       0  6605.4     .05       0
  8481.3    .035       0  8586.7     .07       0
Bank Sta=5014,5018
XS Rating Curve= 0 ,0
Exp/Cntr=0.3,0.1

Type RM Length L Ch R = 1 ,61446   ,4893,4893,4893
BEGIN DESCRIPTION:
C20383
END DESCRIPTION:
XS GIS Cut Line= 4
      2486840.56      13616555.6      2485669.22      13612998.2
      2484822.86     13611240.38      2479332.45     13611413.99
#Sta/Elev= 30
 -1844.3  244.07 -1240.9   234.4  -351.6  219.29    21.5   212.9    1292  210.63
  1507.8  208.44  1774.1  204.01  2611.8  205.11  2939.4  201.44    3152  210.67
  4098.8  207.44    4250  205.75  4537.4   183.8  4900.3  183.49  4967.6  164.91
  4967.9  164.41  4971.6  164.91  4980.4  175.73  5030.4  164.91  5105.4  183.85
  5320.5   172.6    5390  178.97  5690.9  194.78  6145.6  219.08  6533.1  215.75
  7043.6  229.43  8329.4  262.46  8752.3  276.28  9062.1  272.29  9345.1  268.35
#Mann= 20 ,-1 , 0
 -1844.3     .07       0 -1240.9     .05       0  -351.6     .07       0
    21.5     .05       0    1292    .035       0  1507.8     .12       0
  1774.1    .035       0  2611.8     .05       0    3152     .07       0
  4098.8     .12       0  4537.4      .1       0  4967.6     .05       0
  4971.6      .1       0    5390     .12       0  5690.9    .035       0
  6145.6     .07       0  6533.1     .12       0  7043.6     .05       0
  8329.4     .07       0  9062.1     .05       0
Bank Sta=4967.6,4971.6
XS Rating Curve= 0 ,0
Exp/Cntr=0.3,0.1

Type RM Length L Ch R = 1 ,56553   ,4685,4685,4685
BEGIN DESCRIPTION:
C20382
END DESCRIPTION:
XS GIS Cut Line= 4
      2486710.43     13615882.96      2485278.59     13611045.07
      2484801.16     13608657.92      2485495.61     13606118.83
#Sta/Elev= 30
 -3300.8  234.68 -2028.1  211.32  -873.6  208.23  -693.3   206.1  -416.6  202.14
  -119.1  201.81  1633.8  206.39  1889.9   193.1  1994.5  190.17  2825.6  175.29
  3590.9  195.03  3914.4  191.47  4217.7  184.33  4434.5  183.81  4670.9  183.85
  4675.6  164.61  4675.9  164.11  4679.6  164.61  4775.9  175.07  5061.4   182.4
  5240.3  166.05  5332.8  165.83  5363.9  176.94    5395   165.9  5427.6   175.7
  5535.4  185.67  5636.7  184.92  6317.4   241.8  6448.1  255.08  6811.3  253.07
#Mann= 20 ,-1 , 0
 -3300.8     .05       0  -873.6    .035       0  -693.3    .035       0
  -416.6    .035       0  -119.1     .05       0  1633.8     .05       0
  1889.9    .035       0  1994.5     .12       0  3590.9     .12       0
  3914.4    .035       0  4217.7     .12       0  4434.5     .05       0
  4675.6     .05       0  4679.6     .05       0  4775.9     .05       0
  5061.4      .1       0  5427.6     .12       0  5535.4     .07       0
  5636.7     .12       0  6317.4     .05       0
Bank Sta=4675.6,4679.6
XS Rating Curve= 0 ,0
Exp/Cntr=0.3,0.1

Type RM Length L Ch R = 1 ,51868   ,2532,2532,2532
BEGIN DESCRIPTION:
C20381
END DESCRIPTION:
XS GIS Cut Line= 3
      2486797.73      13615580.3      2487405.33     13610697.85
      2487383.63     13607464.33
#Sta/Elev= 30
     353  233.19  1527.3  212.24  2514.8  206.29  3291.2  206.95  4642.7  177.46
  4745.5  174.33    4762  170.62  4832.6  180.27  4923.3  181.76  4982.9  173.82
    4984   154.6  4984.3   154.1    4988   154.6  4993.8  164.86  5003.9  160.98
  5034.1  159.58  5084.5  176.69  5143.2  178.42  5404.8  180.24    5589  181.61
    5816  182.46  5963.2  178.81    6096  174.33  6184.5   180.1  6466.5  186.93
  6647.1  190.95  7271.2  196.59  7725.3  211.37  8043.4   220.4  8506.7  226.32
#Mann= 14 ,-1 , 0
     353     .05       0  4642.7      .1       0    4984     .05       0
    4988      .1       0  5143.2     .12       0  5404.8    .035       0
    5589     .05       0  5963.2      .1       0  6184.5     .12       0
  6466.5     .07       0  6647.1     .12       0  7271.2     .05       0
  7725.3     .07       0  8043.4     .05       0
Bank Sta=4984,4988
XS Rating Curve= 0 ,0
Exp/Cntr=0.3,0.1

Type RM Length L Ch R = 1 ,49336   ,4047,4047,4047
BEGIN DESCRIPTION:
C20380
END DESCRIPTION:
XS GIS Cut Line= 4
      2487752.54     13615797.72      2488229.98     13612564.17
      2489705.67     13610111.91      2489683.97     13607941.76
#Sta/Elev= 30
  -625.2  258.98   416.1  210.27   584.9  204.47  1146.5  191.22  1338.2   201.4
    1547  203.35  2036.1   191.6  2873.1  204.36  4167.4  180.75  4277.4  172.49
    4482  175.06  4819.4  174.28  4949.4  172.74  4990.3  153.66  4990.6  153.16
  4994.3  153.66  5023.2   159.4  5058.3  178.88  5132.1  175.84  5506.2  175.97
  5719.8  178.32  5905.4  178.72    5910  178.73  6164.3  179.59  6309.2  180.46
  6434.6  181.21  6731.5   183.4  7193.9  213.66  7403.9  218.49  7675.7  220.67
#Mann= 19 ,-1 , 0
  -625.2     .05       0   416.1    .035       0   584.9     .05       0
  4167.4      .1       0    4482     .12       0  4819.4      .1       0
  4990.3     .05       0  4994.3      .1       0  5132.1     .12       0
  5506.2     .07       0  5719.8     .12       0  5905.4     .07       0
    5910     .12       0  6164.3     .07       0  6309.2     .12       0
  6434.6     .07       0  6731.5     .12       0  7193.9     .05       0
  7403.9     .07       0
Bank Sta=4990.3,4994.3
XS Rating Curve= 0 ,0
Exp/Cntr=0.3,0.1

Type RM Length L Ch R = 1 ,45289   ,2696,2696,2696
BEGIN DESCRIPTION:
C20379
END DESCRIPTION:
XS GIS Cut Line= 3
      2491398.38     13615558.97      2491571.99     13612629.27
       2490183.1     13608527.68
#Sta/Elev= 30
  2511.7  251.86  2515.5  251.86  2606.1  249.04  2760.5  245.75  2859.1  241.15
  4316.7  180.47  4888.6     181    4960  177.02    4980  170.18    4988  153.72
  4988.2  153.22    4992  153.72    5000  165.68  5050.1  158.01  5069.9  169.89
  5110.2  174.63  5432.1  181.99  5985.1  190.81  6117.3  192.45    6570  202.43
  6768.5  188.15  6889.6  179.85  6968.5  177.13  7417.5  186.28  7727.5  203.78
  8418.9  189.26    8587  196.09  8672.4  202.88  9573.3  220.97  9776.9  226.45
#Mann= 19 ,-1 , 0
  2511.7     .07       0  2515.5     .05       0  2606.1     .07       0
  2760.5    .035       0  2859.1     .05       0  4316.7     .12       0
  4888.6      .1       0    4988     .05       0    4992      .1       0
  5432.1     .05       0  5985.1     .07       0  6117.3     .05       0
  6768.5     .12       0  6889.6     .07       0  6968.5     .12       0
  7417.5     .05       0    8587     .07       0  8672.4     .05       0
  9573.3     .07       0
Bank Sta=4988,4992
XS Rating Curve= 0 ,0
Exp/Cntr=0.3,0.1

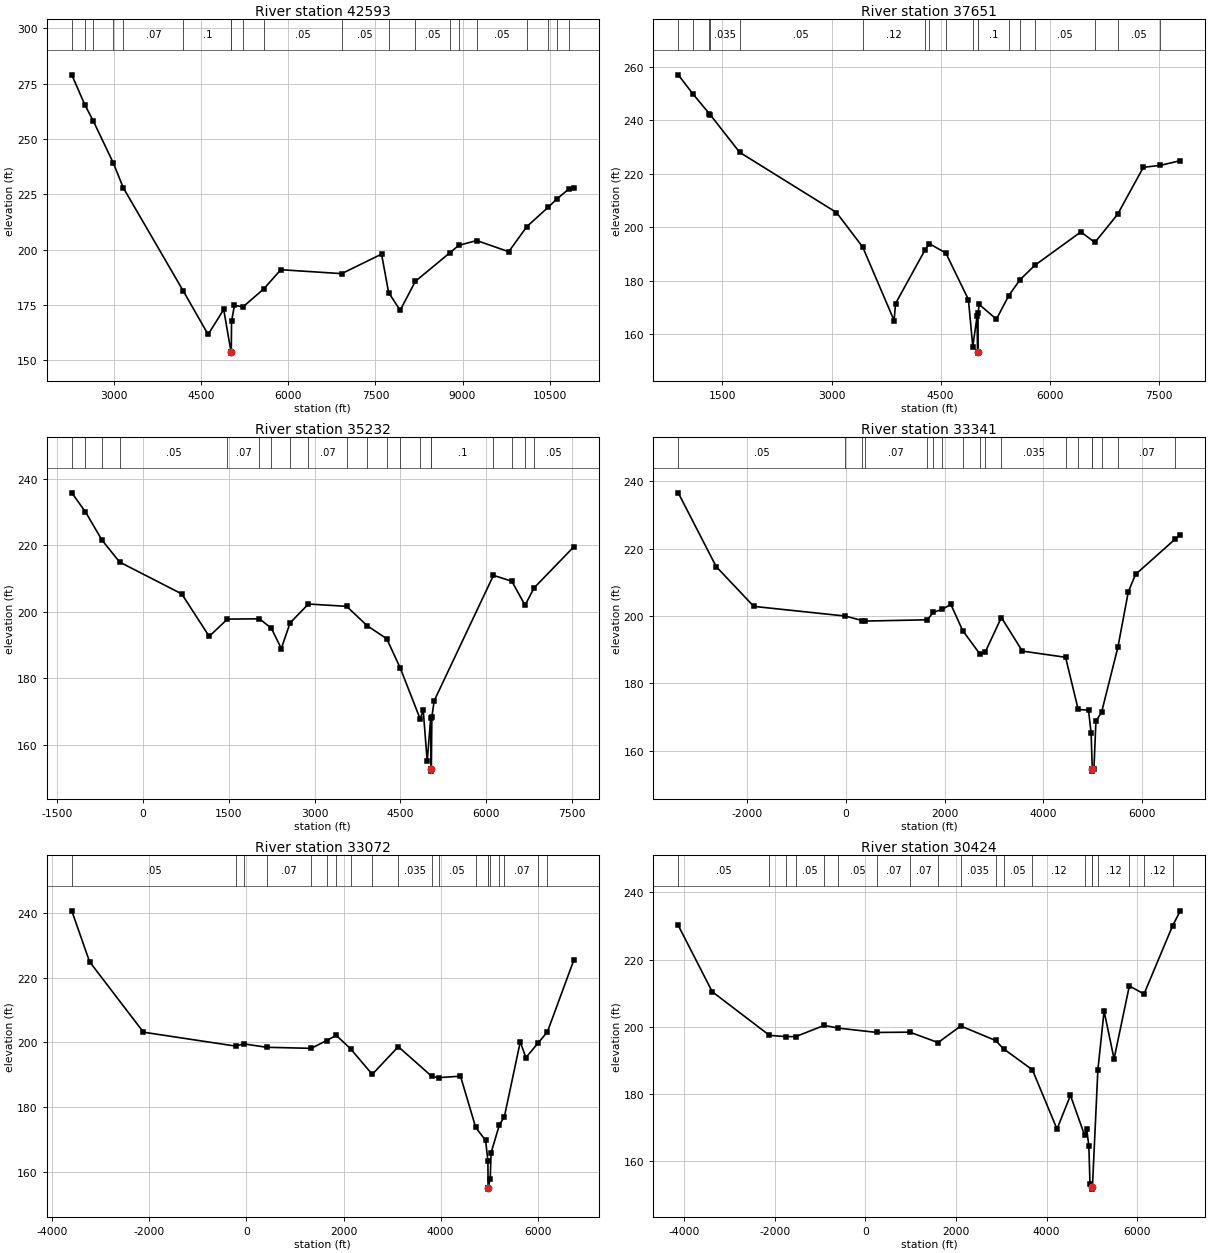
Type RM Length L Ch R = 1 ,42593   ,4942,4942,4942
BEGIN DESCRIPTION:
C20378
END DESCRIPTION:
XS GIS Cut Line= 3
       2496237.8     13614148.37      2493894.04     13613280.31
      2490183.09     13608375.78
#Sta/Elev= 30
  2268.4  279.02  2494.3  265.43  2642.4     258  2986.6  239.04  3154.5  228.05
  4192.7  181.19  4617.4   161.7  4885.7     173  5012.4  153.77  5012.6  153.27
  5016.4  153.77    5021  167.67  5070.9  174.85  5219.7   174.2  5572.8   182.2
    5870  190.96  6918.4  189.19  7605.3     198  7727.3  180.63  7925.8   172.6
  8187.7  185.72    8779  198.54  8936.6  201.99  9245.1  204.13  9796.4   199.1
 10107.9  210.43 10479.4  219.27 10624.9   222.9 10827.9  227.35   10918  227.72
#Mann= 20 ,-1 , 0
  2268.4     .05       0  2494.3     .05       0  2642.4     .07       0
  2986.6     .05       0  3154.5     .07       0  4192.7      .1       0
  5012.4     .05       0  5016.4      .1       0  5219.7     .12       0
  5572.8     .05       0  6918.4     .05       0  7727.3     .12       0
  8187.7     .05       0    8779     .07       0  8936.6     .07       0
  9245.1     .05       0 10107.9     .07       0 10479.4     .05       0
 10624.9     .07       0 10827.9     .05       0
Bank Sta=5012.4,5016.4
XS Rating Curve= 0 ,0
Exp/Cntr=0.3,0.1

Type RM Length L Ch R = 1 ,37651   ,2419,2419,2419
BEGIN DESCRIPTION:
SANDIES CREEK 319.0
END DESCRIPTION:
XS GIS Cut Line= 3
      2496650.06     13609395.76        2492575.       13608875.
      2489922.69     13607985.17
#Sta/Elev= 30
   891.8  256.97  1091.7  249.89  1321.3  242.38  1331.7  242.05  1736.8  227.99
  3068.3  205.48  3429.2  192.56    3861  165.09    3881  171.44  4287.1  191.51
  4346.9   193.8  4572.4  190.34  4882.9  172.94  4943.2  155.33  5002.6  166.78
  5008.1  153.39  5008.3  152.89  5012.1  153.39  5015.8  167.87  5031.6  171.11
  5268.1  165.57  5437.8  174.41  5594.7  180.38  5793.9  185.67  6429.9  198.22
  6622.6  194.28    6934  204.76  7288.9  222.37  7523.8  223.12  7797.6  224.87
#Mann= 18 ,-1 , 0
   891.8     .07       0  1091.7     .05       0  1321.3     .07       0
  1331.7    .035       0  1736.8     .05       0  3429.2     .12       0
  4287.1     .07       0  4346.9     .05       0  4572.4     .12       0
  4943.2      .1       0  5008.1     .05       0  5012.1      .1       0
  5437.8     .05       0  5594.7    .035       0  5793.9     .05       0
  6622.6     .07       0    6934     .05       0  7523.8     .07       0
Bank Sta=5008.1,5012.1
XS Rating Curve= 0 ,0
Exp/Cntr=0.3,0.1

Type RM Length L Ch R = 1 ,35232   ,1891,1891,1891
BEGIN DESCRIPTION:
SANDIES CREEK 320.0
END DESCRIPTION:
XS GIS Cut Line= 3
      2497516.43     13606829.74        2491275.       13606975.
       2488791.2     13607471.73
#Sta/Elev= 30
 -1243.1  235.72 -1004.1  229.99  -714.4  221.49  -407.7  214.91   678.8  205.32
    1159  192.55  1477.9  197.74  2037.1  197.83  2244.7  195.02  2419.3  188.88
  2572.8  196.59  2893.6  202.28  3561.5  201.58  3919.2  195.77  4261.7  191.84
  4498.6  183.05  4847.1  167.69    4900  170.37    4970  154.96  5030.6  167.93
    5038  152.52  5038.2  152.02    5042  152.52    5051  168.29  5091.8  173.18
    6128   210.9    6449  209.13    6680  201.91  6837.8  207.13    7533  219.49
#Mann= 20 ,-1 , 0
 -1243.1     .05       0 -1004.1     .07       0  -714.4     .07       0
  -407.7     .05       0  1477.9     .07       0  2037.1     .07       0
  2244.7     .12       0  2572.8     .07       0  2893.6     .07       0
  3561.5     .05       0  3919.2    .035       0  4261.7     .07       0
  4498.6    .035       0  4847.1      .1       0    5038     .05       0
    5042      .1       0    6128     .07       0    6449     .05       0
    6680    .035       0  6837.8     .05       0
Bank Sta=5038,5042
XS Rating Curve= 0 ,0
Exp/Cntr=0.3,0.1

Type RM Length L Ch R = 1 ,33341   ,269,269,269
BEGIN DESCRIPTION:
SAND21678
END DESCRIPTION:
XS GIS Cut Line= 3
      2498737.92     13605420.53      2491033.12     13605315.53
      2488591.78     13605774.92
#Sta/Elev= 30
 -3405.5  236.56 -2635.1  214.66 -1872.4  202.86   -17.2  199.99   332.6  198.64
   375.4   198.5  1653.3  198.88  1765.6  201.06  1948.3  201.97  2127.9  203.43
  2367.1  195.69  2712.3  188.82  2827.9   189.4  3152.5  199.56  3578.1  189.59
  4455.8  187.75  4711.3  172.28  4921.5  172.05  4973.9  165.23  4997.8  154.47
    4998  153.97  5001.8  154.47  5031.5  154.71  5071.4  168.82  5185.6  171.41
  5516.4  190.66    5729  207.19  5875.3  212.34  6682.8  222.87  6784.2  224.03
#Mann= 18 ,-1 , 0
 -3405.5     .05       0   -17.2    .035       0   332.6     .05       0
   375.4     .07       0  1653.3     .05       0  1765.6     .12       0
  1948.3     .07       0  2367.1     .12       0  2712.3     .07       0
  2827.9     .05       0  3152.5    .035       0  4455.8     .12       0
  4711.3      .1       0  4997.8     .05       0  5001.8      .1       0
  5185.6     .05       0  5516.4     .07       0  6682.8    .035       0
Bank Sta=4997.8,5001.8
XS Rating Curve= 0 ,0
Exp/Cntr=0.3,0.1

Type RM Length L Ch R = 1 ,33072   ,2648,2648,2648
BEGIN DESCRIPTION:
SAND21679
END DESCRIPTION:
XS GIS Cut Line= 4
      2498841.49     13605223.62      2491072.49     13605066.14
      2489353.03      13605354.9       2488526.1     13605459.91
#Sta/Elev= 30
   -3601  240.54 -3234.4  224.87 -2124.2  203.17    -224  198.88   -59.2  199.57
   415.6  198.52  1334.2  198.19  1649.5  200.59  1850.4  202.19  2145.4  198.05
  2591.6  190.19  3128.8   198.7  3817.1   189.6  3959.2  189.16  4410.4  189.63
  4724.4  173.82  4927.6  169.85  4975.5  163.59  4979.2  155.34  4979.4  154.84
  4983.2  155.34  5023.3  158.08  5041.2  166.02  5213.5  174.71  5313.8  177.07
  5642.2  200.18  5758.4  195.33  6014.6  199.91  6202.7  203.31  6746.7  225.39
#Mann= 20 ,-1 , 0
   -3601     .05       0    -224    .035       0   -59.2     .05       0
   415.6     .07       0  1334.2     .07       0  1649.5     .05       0
  1850.4     .07       0  2145.4     .12       0  2591.6     .07       0
  3128.8    .035       0  3817.1     .07       0  3959.2     .05       0
  4724.4     .12       0  4979.2     .05       0  4983.2      .1       0
  5023.3     .07       0  5213.5     .05       0  5313.8     .07       0
  6014.6     .12       0  6202.7     .05       0
Bank Sta=4979.2,4983.2
XS Rating Curve= 0 ,0
Exp/Cntr=0.3,0.1

Type RM Length L Ch R = 1 ,30424   ,1791,1791,1791
BEGIN DESCRIPTION:
SANDIES CREEK 322.0
END DESCRIPTION:
XS GIS Cut Line= 3
      2498726.35     13605020.24        2489825.       13602975.
      2487872.07     13602992.39
#Sta/Elev= 30
 -4133.3  230.16 -3382.9  210.45 -2118.6  197.48 -1761.6  197.11 -1538.6  197.11
  -912.1  200.44  -600.4  199.63   256.1  198.34   981.2  198.43  1603.6  195.33
    2105  200.26  2873.5  195.96  3049.2  193.49  3686.8  187.24  4230.4  169.64
    4527  179.66  4841.7  167.73  4885.2  169.65  4933.2  164.69  4958.9  153.24
  5008.3  152.29  5008.5  151.79  5012.3  152.29  5132.3  187.18    5270  204.69
    5490  190.49  5827.7  212.16  6151.4  209.76  6784.2  230.09    6953  234.48
#Mann= 20 ,-1 , 0
 -4133.3     .05       0 -2118.6    .035       0 -1761.6    .035       0
 -1538.6     .05       0  -912.1    .035       0  -600.4     .05       0
   256.1     .07       0   981.2     .07       0  1603.6     .12       0
    2105    .035       0  2873.5    .035       0  3049.2     .05       0
  3686.8     .12       0  4841.7      .1       0  5008.3     .05       0
  5012.3      .1       0  5132.3     .12       0  5827.7     .07       0
  6151.4     .12       0  6784.2     .05       0
Bank Sta=5008.3,5012.3
XS Rating Curve= 0 ,0
Exp/Cntr=0.3,0.1

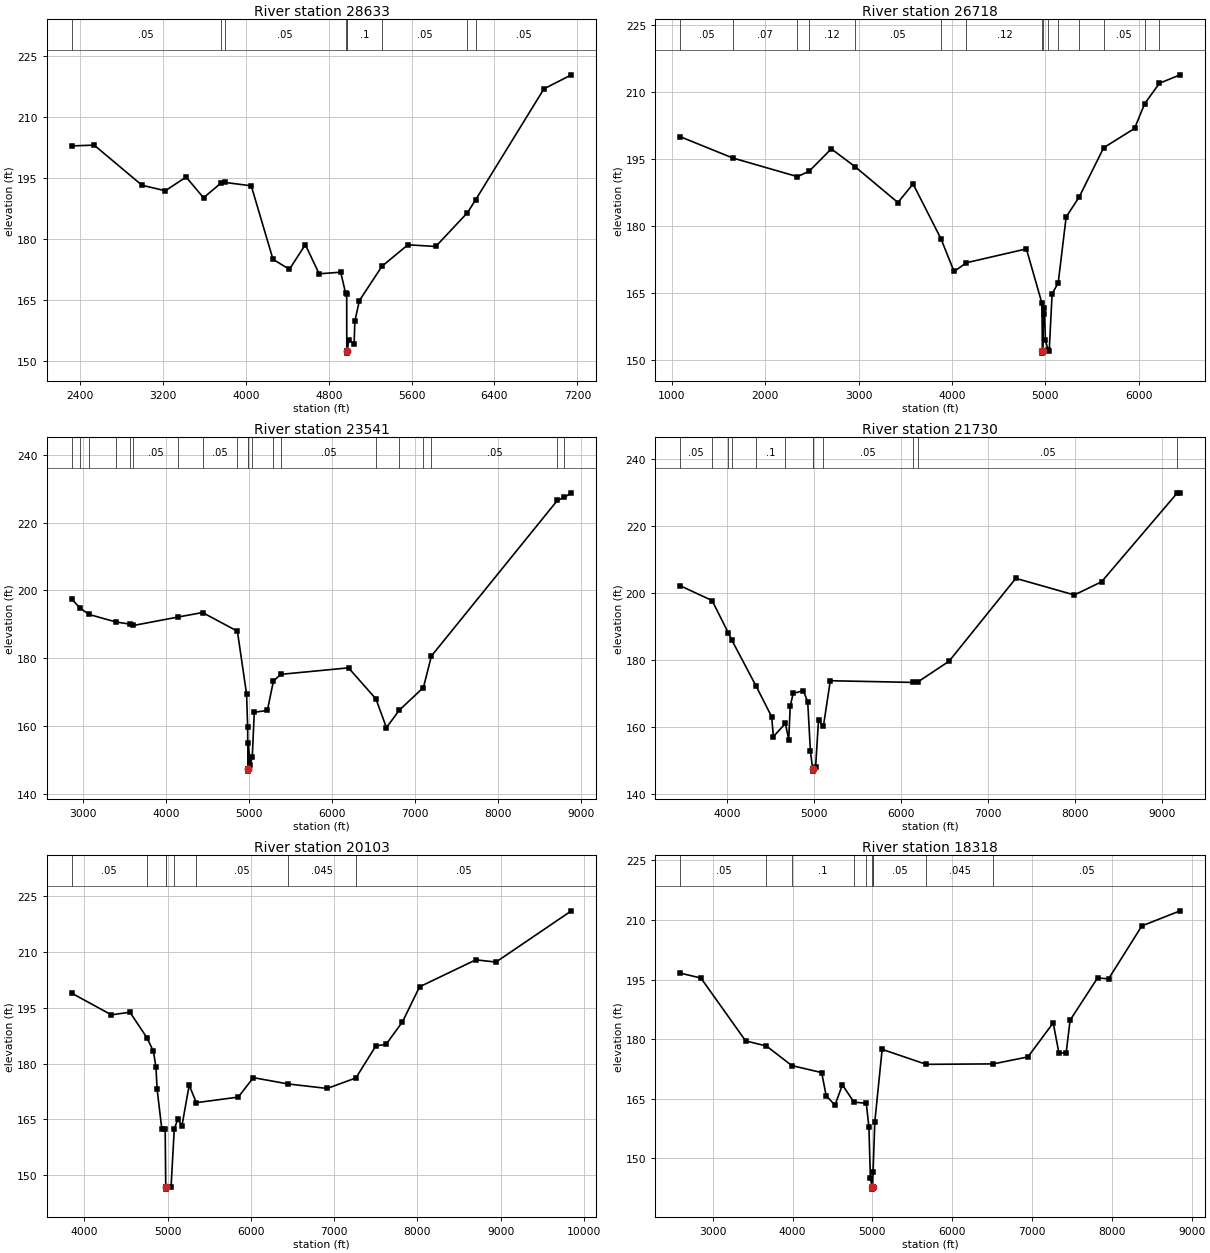
Type RM Length L Ch R = 1 ,28633   ,1915,1915,1915
BEGIN DESCRIPTION:
C20377
END DESCRIPTION:
XS GIS Cut Line= 2
      2493518.61     13602277.45      2488805.83     13601241.52
#Sta/Elev= 30
  2317.5  202.88  2534.8  203.08    2997   193.2  3222.2  191.86  3422.7  195.23
  3590.8  190.13  3754.8  193.65  3795.4  193.91  4051.5  193.07  4261.7  174.98
  4420.1  172.54  4573.7   178.6  4706.8  171.44  4915.4  171.83  4962.1  166.71
    4973  166.36  4973.8  152.43    4974  151.93  4977.8  152.43  4993.5  155.26
  5044.7  154.15  5051.8  159.79  5095.6  164.84  5313.7  173.29    5564  178.57
  5833.1  178.15  6138.2  186.44  6217.6  189.62  6877.4  216.91  7142.8  220.36
#Mann= 9 ,-1 , 0
  2317.5     .05       0  3754.8    .035       0  3795.4     .05       0
  4962.1      .1       0  4973.8     .05       0  4977.8      .1       0
  5313.7     .05       0  6138.2    .035       0  6217.6     .05       0
Bank Sta=4973.8,4977.8
XS Rating Curve= 0 ,0
Exp/Cntr=0.3,0.1

Type RM Length L Ch R = 1 ,26718   ,3177,3177,3177
BEGIN DESCRIPTION:
C20376
END DESCRIPTION:
XS GIS Cut Line= 4
      2493562.36     13601606.25      2492876.62     13600614.12
      2490002.26     13600059.67      2489010.13       13600760.
#Sta/Elev= 30
  1093.4  199.95  1654.6  195.19  2346.7  191.01  2472.6  192.24  2708.5  197.24
    2961  193.28  3421.4  185.21  3583.8  189.38  3882.6  177.07  4022.3  169.76
  4155.2  171.72  4796.3  174.82  4962.7  162.64  4967.5  151.96  4967.7  151.46
  4971.5  151.96  4979.6  160.21  4989.8  161.52    5000  154.32  5028.1  152.19
  5040.7  152.01  5071.5  164.75  5136.6  167.19    5222  181.99  5359.7  186.39
  5623.7   197.5  5953.7  201.81  6061.8  207.35  6219.5  211.93  6441.2  213.83
#Mann= 15 ,-1 , 0
  1093.4     .05       0  1654.6     .07       0  2346.7     .05       0
  2472.6     .12       0    2961     .05       0  3882.6      .1       0
  4155.2     .12       0  4967.5     .05       0  4971.5     .12       0
  5028.1      .1       0  5136.6     .05       0  5359.7    .035       0
  5623.7     .05       0  6061.8    .035       0  6219.5     .05       0
Bank Sta=4967.5,4971.5
XS Rating Curve= 0 ,0
Exp/Cntr=0.3,0.1

Type RM Length L Ch R = 1 ,23541   ,1811,1811,1811
BEGIN DESCRIPTION:
C20375
END DESCRIPTION:
XS GIS Cut Line= 3
      2494000.06     13600424.41      2492190.86     13599155.05
      2488689.11     13597652.22
#Sta/Elev= 30
    2865  197.48  2963.9  194.83    3074  192.92  3394.6  190.72  3562.8  190.07
  3608.2  189.66  4144.3  192.14  4441.6  193.48  4861.8  187.97  4972.3   169.4
    4985  159.87  4989.5  147.25  4989.7  146.75  4993.5  147.25  4993.7  155.03
  5014.7  148.55  5040.6  150.87  5065.2  164.09  5222.9  164.63  5296.1  173.33
  5386.4  175.27  6200.2  177.18  6530.6  168.03    6657  159.56    6812   164.7
  7102.7  171.39    7199  180.67    8717  226.53  8801.4  227.43  8885.7  228.75
#Mann= 20 ,-1 , 0
    2865     .05       0  2963.9     .12       0    3074     .05       0
  3394.6     .05       0  3562.8     .07       0  3608.2     .05       0
  4144.3     .07       0  4441.6     .05       0  4861.8     .07       0
  4989.5     .05       0  4993.5     .07       0  5040.6     .12       0
  5296.1     .12       0  5386.4     .05       0  6530.6      .1       0
    6812     .12       0  7102.7     .07       0    7199     .05       0
    8717    .035       0  8801.4     .05       0
Bank Sta=4989.5,4993.5
XS Rating Curve= 0 ,0
Exp/Cntr=0.3,0.1

Type RM Length L Ch R = 1 ,21730   ,1627,1627,1627
BEGIN DESCRIPTION:
C20374
END DESCRIPTION:
XS GIS Cut Line= 2
      2494204.37     13598016.98      2488674.51     13596441.19
#Sta/Elev= 30
  3461.7  202.19  3827.7  197.77  4013.6  188.09    4055   185.9  4335.6  172.09
  4512.7  163.01    4532  157.08  4670.8  161.04  4708.8  156.16  4726.1  166.29
    4760  169.99  4877.1  170.86  4927.2  167.44  4958.4  152.67  4985.1  147.25
  4987.6  147.27  4987.9  146.77  4991.6  147.27  5017.6  147.91  5051.5  161.94
  5107.9  160.23  5187.1   173.8    6135   173.3  6195.4  173.46  6553.4  179.63
  7321.3  204.42  7994.6  199.45  8307.8  203.38  9175.2  229.83  9211.7  229.99
#Mann= 13 ,-1 , 0
  3461.7     .05       0  3827.7     .07       0  4013.6    .035       0
    4055     .07       0  4335.6      .1       0  4670.8     .12       0
  4985.1      .1       0  4987.6     .05       0  4991.6      .1       0
  5107.9     .05       0    6135    .035       0  6195.4     .05       0
  9175.2    .035       0
Bank Sta=4987.6,4991.6
XS Rating Curve= 0 ,0
Exp/Cntr=0.3,0.1

Type RM Length L Ch R = 1 ,20103   ,1785,1785,1785
BEGIN DESCRIPTION:
C20373
END DESCRIPTION:
XS GIS Cut Line= 2
      2494569.16     13596412.01      2488616.18     13595638.71
#Sta/Elev= 30
    3847  198.98  4324.3  193.14    4547  193.85    4751  186.98  4829.4  183.32
  4859.6  179.02  4873.3  173.14  4930.2  162.37  4970.5  162.41  4977.1  146.73
  4977.3  146.23  4981.1  146.73  5041.1  146.82  5079.5  162.44  5121.8  164.98
  5172.2  163.34  5258.9  174.21  5344.7   169.5  5847.8     171  6029.3  176.24
    6446  174.54  6916.7  173.33  7261.2  176.16  7501.6   184.8  7622.6  185.18
  7820.5  191.25    8026  200.69  8701.6  207.95  8943.6  207.35    9850  221.14
#Mann= 8 ,-1 , 0
    3847     .05       0    4751     .12       0  4977.1     .05       0
  4981.1     .12       0  5079.5     .07       0  5344.7     .05       0
    6446    .045       0  7261.2     .05       0
Bank Sta=4977.1,4981.1
XS Rating Curve= 0 ,0
Exp/Cntr=0.3,0.1

Type RM Length L Ch R = 1 ,18318   ,1812,1812,1812
BEGIN DESCRIPTION:
C20372
END DESCRIPTION:
XS GIS Cut Line= 4
      2494671.24      13596061.8      2493766.65     13595288.53
      2492365.95     13594777.86      2488820.43     13595273.94
#Sta/Elev= 30
  2594.3  196.62  2852.3  195.38  3412.2  179.56  3673.1  178.27  3990.5  173.35
  4365.1  171.58  4420.9  165.79  4531.2  163.38  4624.2  168.49  4769.8  164.14
  4923.2  163.86  4956.9   157.9    4975  144.98  4998.5  142.75  4998.7  142.25
  5002.5  142.75  5008.6  146.55  5030.8  159.24  5122.5  177.43  5674.6  173.66
  6514.5  173.77  6948.9  175.53  7265.4  184.09  7336.1  176.62  7426.9  176.46
  7477.4  184.78  7821.2  195.41    7959  195.18  8376.1   208.5  8855.3   212.3
#Mann= 10 ,-1 , 0
  2594.3     .05       0  3673.1     .12       0  3990.5      .1       0
  4769.8     .12       0  4923.2      .1       0  4998.5     .05       0
  5002.5      .1       0  5008.6     .05       0  5674.6    .045       0
  6514.5     .05       0
Bank Sta=4998.5,5002.5
XS Rating Curve= 0 ,0
Exp/Cntr=0.3,0.1