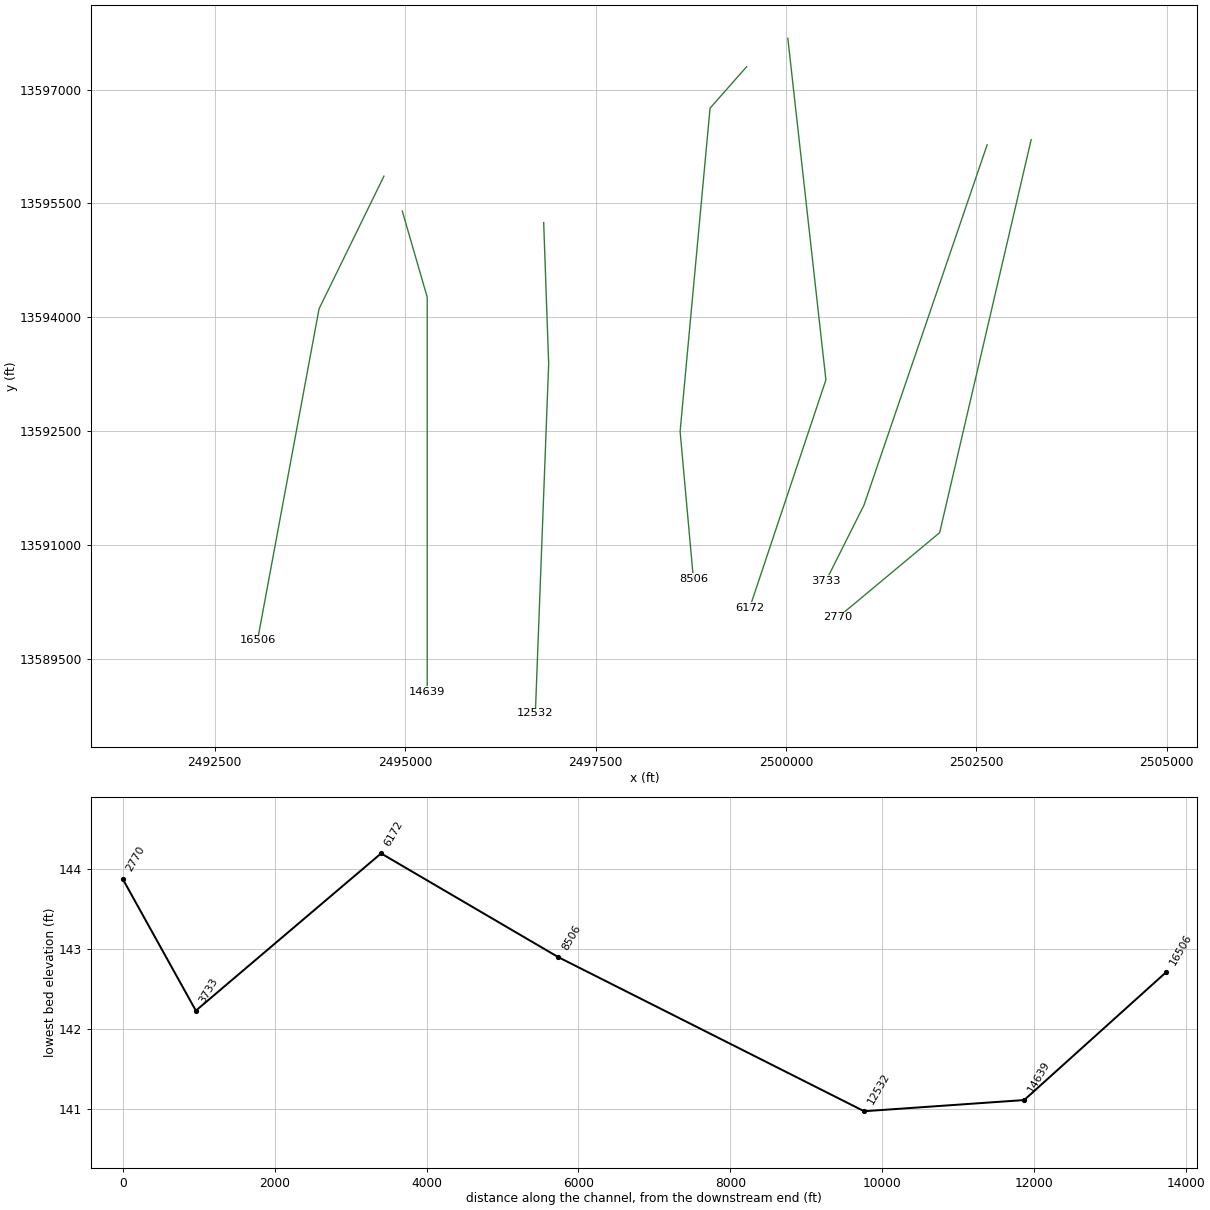
HEC-RAS study SANDIES CREEK.prj: SANDIES CREEK Base Level Engineering

--- SANDIES CREEK.g01 (geometry) --- (continued)

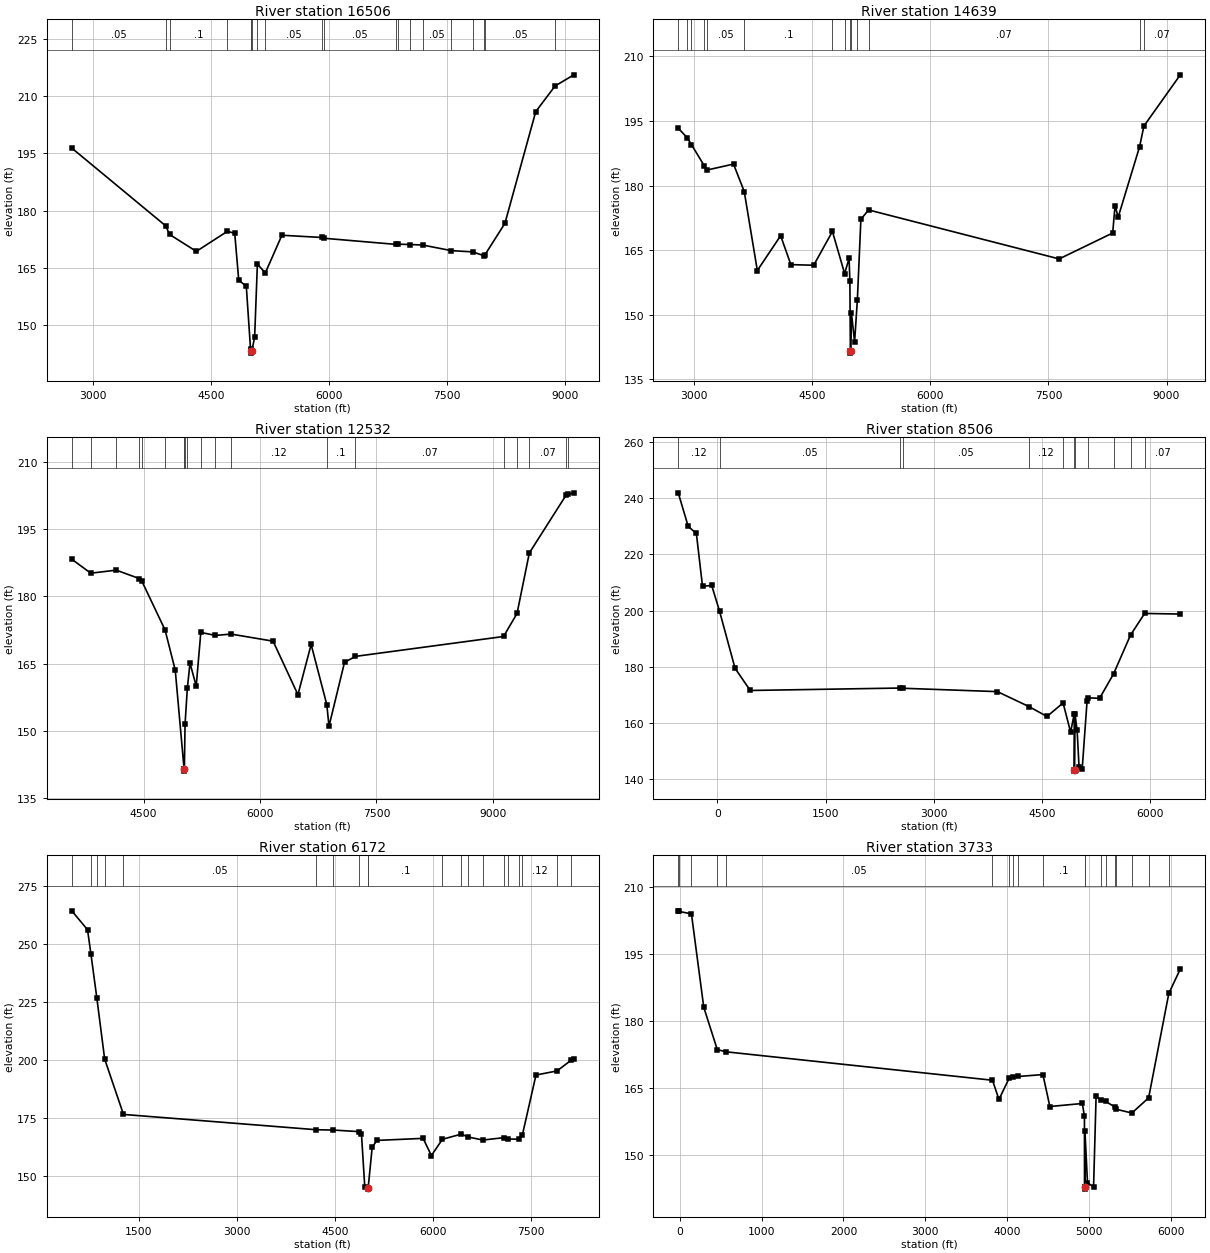
Type RM Length L Ch R = 1 ,16506   ,1867,1867,1867
BEGIN DESCRIPTION:
C20371
END DESCRIPTION:
XS GIS Cut Line= 3
       2494722.2     13595859.45      2493870.23     13594111.81
      2493061.94     13589742.69
#Sta/Elev= 30
  2728.1  196.38    3923  176.02  3972.9  173.76    4313  169.34  4708.8   174.6
  4801.3  174.05  4852.2  161.82  4948.6  160.18  5002.2  143.83  5013.6  143.21
  5013.9  142.71  5017.6  143.21  5054.4  146.81  5089.5  166.01  5190.3   163.7
  5401.3  173.56  5909.8  172.98  5934.6  172.78  6851.9  171.17  6874.3  171.23
  7032.5  171.14  7192.2     171  7555.6  169.54  7826.3  169.21  7971.7  168.23
  7984.8  168.45  8238.7  176.68  8630.9  205.92  8876.4  212.62  9115.6  215.55
#Mann= 20 ,-1 , 0
  2728.1     .05       0    3923     .12       0  3972.9      .1       0
  4708.8     .12       0  5002.2      .1       0  5013.6     .05       0
  5017.6      .1       0  5089.5     .12       0  5190.3     .05       0
  5909.8     .12       0  5934.6     .05       0  6851.9    .035       0
  6874.3     .05       0  7032.5    .035       0  7192.2     .05       0
  7555.6    .035       0  7826.3     .05       0  7971.7     .07       0
  7984.8     .05       0  8876.4    .035       0
Bank Sta=5013.6,5017.6
XS Rating Curve= 0 ,0
Exp/Cntr=0.3,0.1

Type RM Length L Ch R = 1 ,14639   ,2107,2107,2107
BEGIN DESCRIPTION:
C20370
END DESCRIPTION:
XS GIS Cut Line= 3
      2494962.69     13595400.05      2495290.19     13594264.73
      2495290.19     13589065.54
#Sta/Elev= 30
  2794.5  193.32  2908.2  191.12  2962.9  189.51  3128.2  184.52  3155.5   183.6
  3497.1     185  3633.5  178.62  3799.6  160.29  4095.8  168.37  4225.8  161.66
  4515.8  161.51    4754  169.35  4909.1  159.59  4965.8  163.11  4975.8  157.86
  4982.2  141.61  4982.4  141.11  4986.2  141.61  4995.8  150.39  5035.8  143.72
    5071  153.46  5115.8  172.18  5213.8  174.35  7635.8  162.98  8315.8     169
  8345.8  175.34  8385.8  172.69  8658.2  189.06  8712.6  193.83  9175.3  205.72
#Mann= 14 ,-1 , 0
  2794.5     .05       0  2908.2     .07       0  2962.9     .05       0
  3128.2     .07       0  3155.5     .05       0  3633.5      .1       0
    4754     .12       0  4909.1      .1       0  4982.2     .05       0
  4986.2      .1       0    5071     .12       0  5213.8     .07       0
  8658.2     .12       0  8712.6     .07       0
Bank Sta=4982.2,4986.2
XS Rating Curve= 0 ,0
Exp/Cntr=0.3,0.1

Type RM Length L Ch R = 1 ,12532   ,4026,4026,4026
BEGIN DESCRIPTION:
C20369
END DESCRIPTION:
XS GIS Cut Line= 3
      2496819.37     13595247.83      2496884.91     13593390.91
      2496710.15      13588781.5
#Sta/Elev= 30
  3573.5   188.3  3818.2  185.18    4147  185.86  4442.5  183.99  4476.9   183.4
  4775.9   172.5  4907.2  163.51  5020.8  141.47    5021  140.97  5024.8  141.47
  5033.5  151.46    5063  159.51  5097.3  165.09  5177.3  159.96  5236.6  171.95
  5425.7  171.28    5626  171.58    6168     170  6488.2  158.05  6658.4  169.26
  6860.6  155.81  6888.5     151  7088.7  165.27  7230.1   166.6  9138.3  171.04
  9312.1  176.19  9470.7   189.7  9947.6   202.7  9968.3   202.8 10044.3  203.13
#Mann= 20 ,-1 , 0
  3573.5     .05       0  3818.2     .07       0    4147     .07       0
  4442.5     .05       0  4476.9    .035       0  4775.9     .12       0
  5020.8     .05       0  5024.8      .1       0  5033.5     .12       0
    5063      .1       0  5236.6     .12       0  5425.7      .1       0
    5626     .12       0  6860.6      .1       0  7230.1     .07       0
  9138.3    .035       0  9312.1     .12       0  9470.7     .07       0
  9947.6    .035       0  9968.3     .05       0
Bank Sta=5020.8,5024.8
XS Rating Curve= 0 ,0
Exp/Cntr=0.3,0.1

Type RM Length L Ch R = 1 ,8506    ,2334,2334,2334
BEGIN DESCRIPTION:
C20368
END DESCRIPTION:
XS GIS Cut Line= 4
      2499483.97     13597300.62      2499003.93     13596755.12
      2498610.71     13592495.24      2498785.47     13590551.01
#Sta/Elev= 30
  -543.2   241.9  -405.1  229.94  -292.1  227.47  -206.8  208.65   -79.6  208.96
    28.8  199.84   243.8  179.49   454.7  171.59  2534.8  172.46  2569.5  172.38
  3879.2  171.18  4319.9  165.82  4566.2  162.34  4789.2  167.16  4893.4  156.77
  4943.6  163.28  4943.9   143.4  4944.2   142.9  4947.9   143.4  4953.7  163.34
  4983.8  157.38  5010.5  144.34  5054.1  143.72  5121.5  167.81    5140  168.97
    5295   168.8    5489  177.52  5723.6   191.3  5919.2  198.99  6413.5  198.78
#Mann= 12 ,-1 , 0
  -543.2     .12       0    28.8     .05       0  2534.8    .035       0
  2569.5     .05       0  4319.9     .12       0  4789.2      .1       0
  4943.9     .05       0  4947.9      .1       0    5140     .12       0
    5489     .07       0  5723.6     .12       0  5919.2     .07       0
Bank Sta=4943.9,4947.9
XS Rating Curve= 0 ,0
Exp/Cntr=0.3,0.1

Type RM Length L Ch R = 1 ,6172    ,2439,2439,2439
BEGIN DESCRIPTION:
SANDIES CREEK 331.0
END DESCRIPTION:
XS GIS Cut Line= 3
        2500025.     13597675.03        2500525.       13593175.
        2499525.       13590175.
#Sta/Elev= 30
   472.3  264.09   713.8  255.95     766  245.44   856.5  226.46   976.1  200.23
  1264.3  176.38  4220.4  169.78  4478.2  169.65  4873.6  168.97  4909.5  167.87
  4959.8  145.22    5008   144.7  5008.3   144.2    5012   144.7  5073.8  162.31
  5147.6  165.19  5853.8  166.07  5980.3  158.66  6149.3  165.67  6438.7   167.9
  6543.6  166.65  6769.8  165.35  7099.2   166.4  7148.4   165.8  7318.8   165.7
  7374.5  167.61  7582.5  193.36  7904.9  195.12  8116.5  199.64  8162.3  200.23
#Mann= 20 ,-1 , 0
   472.3     .07       0     766     .12       0   856.5     .07       0
   976.1     .12       0  1264.3     .05       0  4220.4    .035       0
  4478.2     .07       0  4873.6     .12       0    5008     .05       0
    5012      .1       0  6149.3     .12       0  6438.7     .07       0
  6543.6     .12       0  6769.8     .07       0  7099.2      .1       0
  7148.4     .07       0  7318.8     .07       0  7374.5     .12       0
  7904.9     .12       0  8116.5     .07       0
Bank Sta=5008,5012
XS Rating Curve= 0 ,0
Exp/Cntr=0.3,0.1

Type RM Length L Ch R = 1 ,3733    ,963,963,963
BEGIN DESCRIPTION:
SANDIES CREEK 332.0
END DESCRIPTION:
XS GIS Cut Line= 3
      2502641.79     13596271.23        2501025.       13591525.
      2500524.99     13590524.99
#Sta/Elev= 30
   -18.4  204.72    -4.4  204.57   142.9  204.04   293.3  183.06   458.3  173.57
   561.4  173.07  3819.8  166.68  3898.5  162.36  4023.1  167.12  4064.8  167.34
  4137.1  167.53  4435.6  167.95  4520.3  160.78  4917.3  161.46  4942.8  158.54
  4943.7  142.73  4943.9  142.23  4947.7  142.73  4948.6  155.36    4980  143.65
  5054.3  142.73  5085.1  163.07  5140.5  162.25  5200.4  161.93  5312.1  160.71
  5328.8  160.18  5521.8  159.32  5726.6  162.72  5973.2  186.16  6113.7  191.66
#Mann= 19 ,-1 , 0
   -18.4     .05       0    -4.4     .07       0   142.9     .12       0
   458.3    .035       0   561.4     .05       0  3819.8     .12       0
  4023.1     .05       0  4064.8      .1       0  4137.1     .05       0
  4435.6      .1       0  4943.7     .05       0  4947.7      .1       0
  5140.5     .12       0  5200.4      .1       0  5312.1     .12       0
  5328.8      .1       0  5521.8     .12       0  5726.6      .1       0
  5973.2     .12       0
Bank Sta=4943.7,4947.7
XS Rating Curve= 0 ,0
Exp/Cntr=0.3,0.1

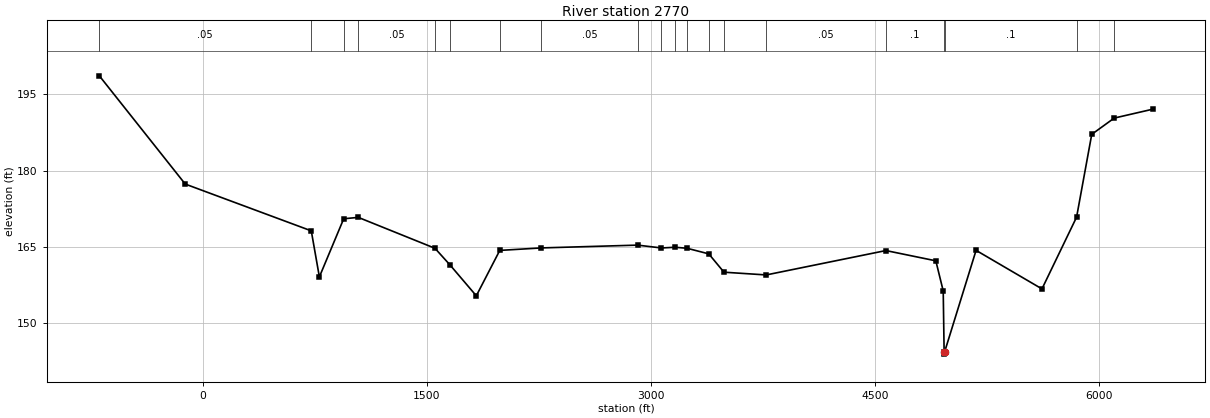
Type RM Length L Ch R = 1 ,2770    ,0,0,0
BEGIN DESCRIPTION:
C20367
END DESCRIPTION:
XS GIS Cut Line= 3
      2503220.06     13596339.83      2502018.61     13591162.67
      2500686.03     13590048.55
#Sta/Elev= 30
  -692.1  198.67  -117.1  177.36   726.7  168.15   780.9  159.08   943.7  170.53
  1041.6   170.8  1554.6  164.72  1656.4   161.4  1831.4  155.36  1988.5   164.3
  2267.4  164.79  2911.1  165.34    3071  164.78  3163.4  164.92  3242.2  164.72
  3387.5  163.62  3489.3  160.01    3772  159.47  4573.2  164.27  4907.5  162.25
    4957  156.32    4963  144.38  4963.2  143.88    4967  144.38  5176.9  164.31
    5618  156.72  5849.8  170.85  5951.2  187.15  6101.6  190.35  6359.6   192.1
#Mann= 20 ,-1 , 0
  -692.1     .05       0   726.7     .12       0   943.7     .12       0
  1041.6     .05       0  1554.6     .12       0  1656.4     .12       0
  1988.5      .1       0  2267.4     .05       0  2911.1     .07       0
    3071     .05       0  3163.4     .07       0  3242.2     .05       0
  3387.5     .07       0  3489.3     .12       0    3772     .05       0
  4573.2      .1       0    4963     .05       0    4967      .1       0
  5849.8     .12       0  6101.6     .07       0
Bank Sta=4963,4967
XS Rating Curve= 0 ,0
Exp/Cntr=0.3,0.1

Chan Stop Cuts=-1
Use User Specified Reach Order=0
Composite Channel Slope=5