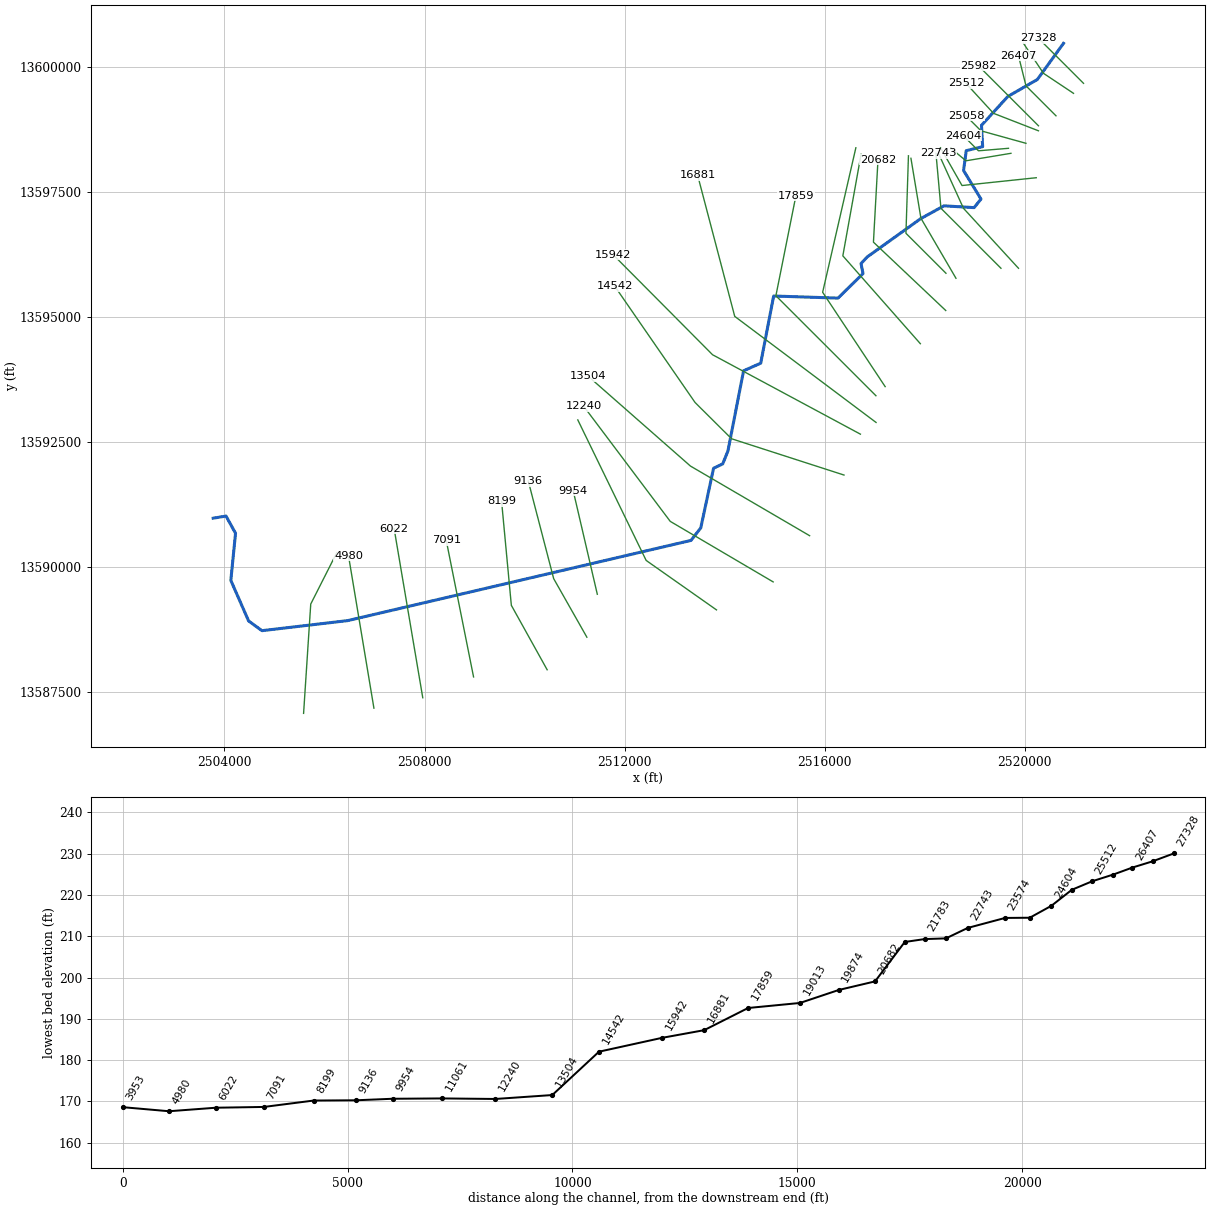
--- SCS CHANNEL.prj (project) ---

Proj Title=SCS CHANNEL Base Level Engineering
Current Plan=p01
Default Exp/Contr=0.3,0.1
English Units
Geom File=g01
Flow File=f01
Plan File=p01
Y Axis Title=Elevation
X Axis Title(PF)=Main Channel Distance
X Axis Title(XS)=Station
BEGIN DESCRIPTION:
SCS CHANNEL
END DESCRIPTION:
DSS Export Rating Curves= 0
DSS Export Rating Curve Sorted= 0
DSS Export Volume Flow Curves= 0
DXF OffsetX= 0
DXF OffsetY= 0
DXF ScaleX= 1
DXF ScaleY= 10

--- SCS CHANNEL.p01 (plan) ---

Plan Title=Multiple Run
Short Identifier=Multiple
Geom File=g01
Flow File=f01
Subcritical Flow
K Sum by GR= 0
Std Step Tol= 0.01
Critical Tol= 0.01
Num of Std Step Trials= 20
Max Error Tol= 0.3
Flow Tol Ratio= 0.001
Split Flow NTrial= 30
Split Flow Tol= 0.02
Split Flow Ratio= 0.02
Log Output Level= 0
Friction Slope Method= 1
Unsteady Friction Slope Method= 2
Unsteady Bridges Friction Slope Method= 1
Parabolic Critical Depth
Global Vel Dist=  1 , 1 , 1
Global Log Level= 0
CheckData=True
Encroach Param= -1, 0, 0, 0
BEGIN DESCRIPTION:
Multiple Run
END DESCRIPTION:

--- SCS CHANNEL.f01 (steady flow) ---

Flow Title=Multiple
Number of Profiles=7
Profile Names=10-year,25-year,50-year,1pct_min,100-year,1pct_plu,500-year
River Rch & RM= SCS CHANNEL,Reach-1,27328
     570     912    1219     790    1576    3144    2604
River Rch & RM= SCS CHANNEL,Reach-1,22743
     953    1560    2116    1387    2768    5523    4695
River Rch & RM= SCS CHANNEL,Reach-1,15942
    1196    1979    2702    1782    3555    7094    6103
River Rch & RM= SCS CHANNEL,Reach-1,13504
    1408    2325    3171    2085    4160    8300    7100
River Rch & RM= SCS CHANNEL,Reach-1,2162
    1376    2265    3081    2020    4031    8043    6843
Boundary for River Rch & Prof#=SCS CHANNEL,Reach-1,1
Up Type=0
Dn Type=3
Dn Slope=0.005
Boundary for River Rch & Prof#=SCS CHANNEL,Reach-1,2
Up Type=0
Dn Type=3
Dn Slope=0.005
Boundary for River Rch & Prof#=SCS CHANNEL,Reach-1,3
Up Type=0
Dn Type=3
Dn Slope=0.005
Boundary for River Rch & Prof#=SCS CHANNEL,Reach-1,4
Up Type=0
Dn Type=3
Dn Slope=0.005
Boundary for River Rch & Prof#=SCS CHANNEL,Reach-1,5
Up Type=0
Dn Type=3
Dn Slope=0.005
Boundary for River Rch & Prof#=SCS CHANNEL,Reach-1,6
Up Type=0
Dn Type=3
Dn Slope=0.005
Boundary for River Rch & Prof#=SCS CHANNEL,Reach-1,7
Up Type=0
Dn Type=3
Dn Slope=0.005

--- SCS CHANNEL.g01 (geometry) ---

Geom Title=Existing Conditions
Program Version=4.10

River Reach=SCS CHANNEL     ,Reach-1
Reach XY= 30
        2520775.       13600475.      2520251.87     13599751.18
      2519661.76     13599411.38      2519135.43     13598834.79
      2519158.59      13598408.2      2518830.36     13598327.78
      2518776.97     13597930.89      2519125.11     13597359.64
      2518988.32     13597188.37      2518385.44     13597223.96
      2517918.81     13596967.14      2516851.53     13596201.99
      2516726.62     13596068.97      2516767.24     13595868.83
      2516266.66     13595378.16      2514980.08     13595419.96
      2514721.57     13594076.22      2514378.53     13593923.55
      2514066.76     13592321.77      2513961.77     13592061.28
      2513778.44     13591973.77      2513522.75     13590780.93
      2513327.43     13590530.52      2506464.49     13588926.22
      2504749.91     13588724.79      2504483.14     13588918.94
      2504127.26     13589730.94      2504221.46     13590673.54
      2504031.39     13591017.66        2503775.       13590975.

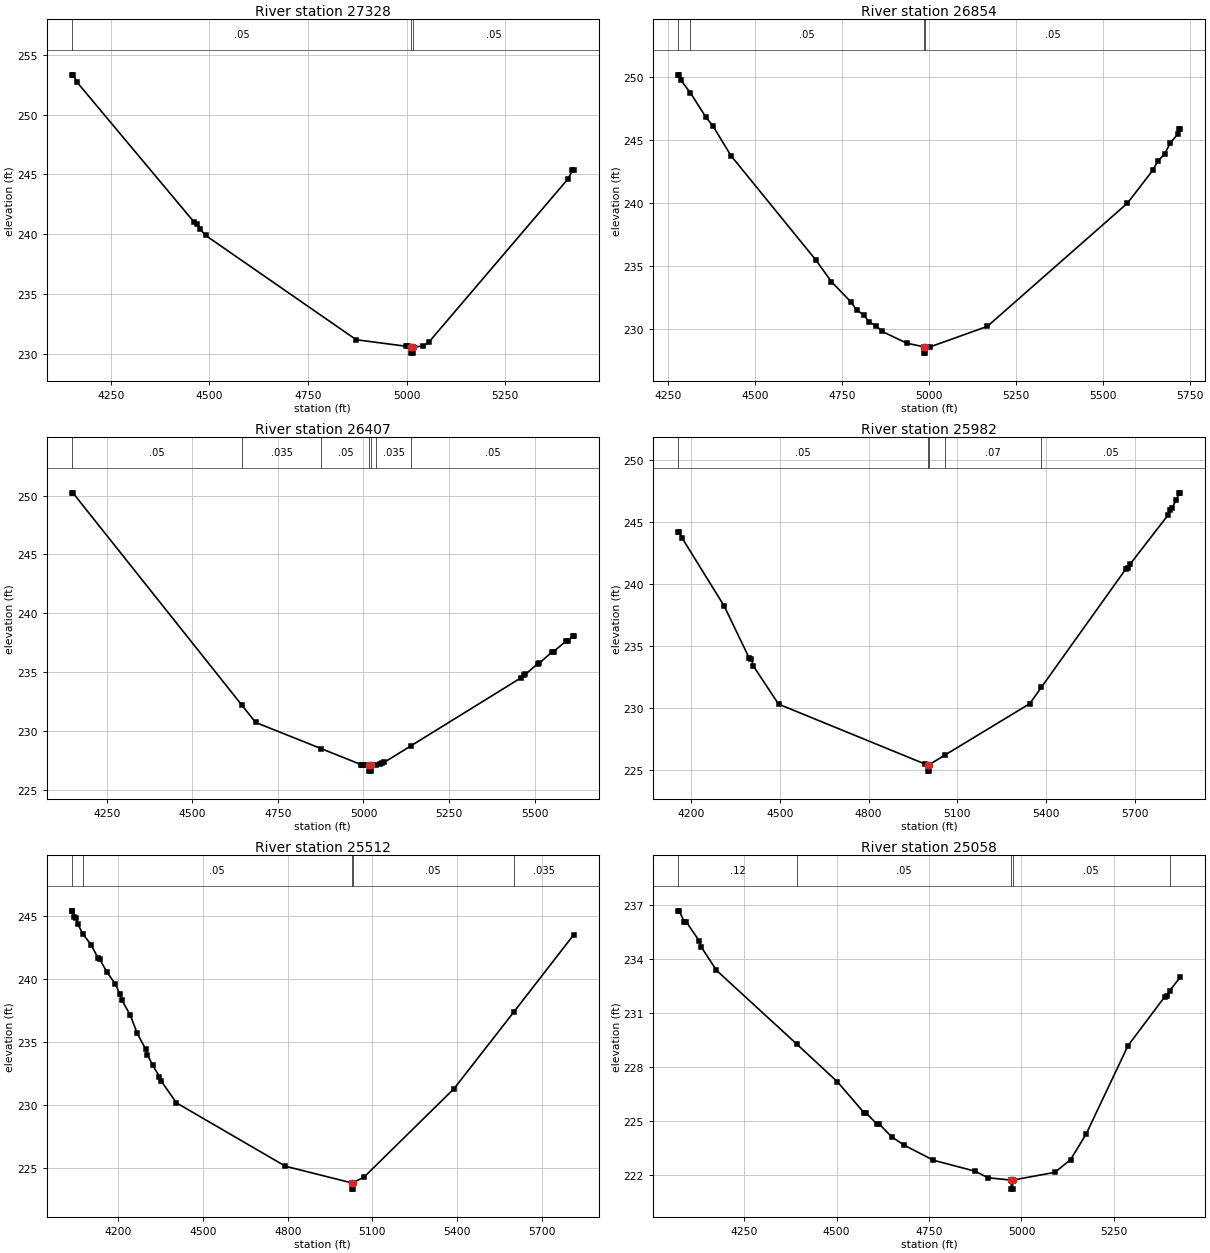
Type RM Length L Ch R = 1 ,27328   ,474,474,474
BEGIN DESCRIPTION:
SCS CHANNEL 51.0
END DESCRIPTION:
XS GIS Cut Line= 3
      2521175.01     13599674.99        2520575.       13600275.
      2520275.01     13600574.99
#Sta/Elev= 19
  4151.2  253.32  4154.8  253.32  4165.4  252.68  4462.3  240.97  4469.4  240.88
  4476.5  240.43  4490.6  239.89  4872.5  231.16  4999.7  230.61  5003.3  230.61
  5011.9  230.54  5012.1  230.04  5015.6  230.04  5015.9  230.54  5042.2  230.64
  5056.3  230.95  5409.9  244.64  5420.5  245.35    5424  245.35
#Mann= 3 ,-1 , 0
  4151.2     .05       0  5011.9     .05       0  5015.9     .05       0
Bank Sta=5011.9,5015.9
XS Rating Curve= 0 ,0
Exp/Cntr=0.3,0.1

Type RM Length L Ch R = 1 ,26854   ,447,447,447
BEGIN DESCRIPTION:
SCS CHANNEL 50.0
END DESCRIPTION:
XS GIS Cut Line= 3
        2520975.       13599475.        2520375.       13599875.
      2519975.01     13600474.98
#Sta/Elev= 30
  4279.1   250.2  4282.1   250.2  4286.6   249.8  4314.1  248.78  4358.7  246.85
  4379.8  246.11  4430.8  243.79  4675.7  235.47  4719.3  233.79  4776.4  232.15
  4791.4  231.55  4812.4  231.14  4827.4  230.59  4848.5  230.28  4863.5  229.86
  4935.6  228.91  4984.7  228.62  4984.9  228.12  4988.4  228.12  4988.7  228.62
  5003.2  228.62    5167  230.24  5569.6  240.02  5641.7  242.61  5656.7  243.35
  5676.3  243.92  5692.8  244.81  5713.8  245.49  5718.3  245.94  5721.3  245.94
#Mann= 4 ,-1 , 0
  4279.1    .035       0  4314.1     .05       0  4984.7     .05       0
  4988.7     .05       0
Bank Sta=4984.7,4988.7
XS Rating Curve= 0 ,0
Exp/Cntr=0.3,0.1

Type RM Length L Ch R = 1 ,26407   ,425,425,425
BEGIN DESCRIPTION:
SCS CHANNEL 49.0
END DESCRIPTION:
XS GIS Cut Line= 3
      2520624.98     13599025.02        2520025.       13599625.
      2519874.99     13600225.04
#Sta/Elev= 29
  4147.5  250.23    4151  250.23  4645.2   232.2  4684.9  230.75  4877.3  228.52
  4992.5  227.18    4996  227.18  4998.6  227.18  5006.3  227.15  5017.2  227.12
  5017.4  226.62  5020.9  226.62  5021.2  227.12  5037.5  227.17  5047.5   227.2
  5055.3  227.34  5060.4  227.36  5138.3  228.76  5459.8  234.53  5467.6  234.76
  5472.7  234.82  5508.8  235.73    5514  235.79    5550  236.71  5555.2  236.76
  5591.3  237.64  5596.4  237.67  5611.9   238.1  5614.5   238.1
#Mann= 7 ,-1 , 0
  4147.5     .05       0  4645.2    .035       0  4877.3     .05       0
  5017.2     .05       0  5021.2     .05       0  5037.5    .035       0
  5138.3     .05       0
Bank Sta=5017.2,5021.2
XS Rating Curve= 0 ,0
Exp/Cntr=0.3,0.1

Type RM Length L Ch R = 1 ,25982   ,470,470,470
BEGIN DESCRIPTION:
SCS CHANNEL 48.0
END DESCRIPTION:
XS GIS Cut Line= 3
      2520274.98     13598825.02        2519675.       13599425.
      2519075.02     13600024.98
#Sta/Elev= 25
  4156.3  244.18  4159.8  244.18  4170.4  243.66  4311.8  238.22  4396.7  234.02
  4403.8  233.92  4410.8  233.38  4495.7  230.32  4990.7   225.5  4999.3  225.43
  4999.5  224.93    5003  224.93  5003.3  225.43  5058.5  226.23  5344.2  230.35
    5384  231.68  5669.5   241.2  5676.6  241.27  5683.6  241.58  5810.9   245.5
    5818  245.94    5825  246.11  5839.2  246.72  5849.8  247.32  5853.3  247.32
#Mann= 5 ,-1 , 0
  4156.3     .05       0  4999.3     .05       0  5003.3     .05       0
  5058.5     .07       0    5384     .05       0
Bank Sta=4999.3,5003.3
XS Rating Curve= 0 ,0
Exp/Cntr=0.3,0.1

Type RM Length L Ch R = 1 ,25512   ,454,454,454
BEGIN DESCRIPTION:
SCS CHANNEL 47.0
END DESCRIPTION:
XS GIS Cut Line= 3
      2520275.04     13598724.98        2519375.       13599075.
      2518825.03     13599674.97
#Sta/Elev= 30
  4034.3  245.43    4037  245.43  4043.9  244.95  4049.3  244.87  4055.8   244.4
  4073.9  243.59  4103.7  242.72  4128.2  241.67  4133.6  241.59  4158.1   240.6
    4188  239.64    4206  238.78  4212.5  238.33  4242.4  237.11  4266.9  235.68
  4296.8  234.42  4302.6  233.99  4321.4  233.15  4345.5  232.25  4351.2  231.91
  4405.7  230.16  4791.9  225.12  5026.1   223.8  5026.3   223.3  5029.8   223.3
  5030.1   223.8  5070.6  224.26  5389.4  231.29  5601.3  237.39  5813.9  243.54
#Mann= 5 ,-1 , 0
  4034.3     .12       0  4073.9     .05       0  5026.1     .05       0
  5030.1     .05       0  5601.3    .035       0
Bank Sta=5026.1,5030.1
XS Rating Curve= 0 ,0
Exp/Cntr=0.3,0.1

Type RM Length L Ch R = 1 ,25058   ,454,454,454
BEGIN DESCRIPTION:
SCS CHANNEL 46.0
END DESCRIPTION:
XS GIS Cut Line= 3
      2520024.97     13598475.01        2519125.       13598725.
      2518825.01     13599024.99
#Sta/Elev= 30
  4071.4  236.65    4074  236.65  4088.5  236.03  4093.7  236.03  4127.9     235
  4133.6  234.66  4175.2  233.35  4392.1  229.27  4501.6  227.19  4575.3  225.44
  4580.4  225.44  4609.5  224.83  4614.7  224.85  4648.9  224.13  4683.2  223.66
  4762.1  222.83  4875.2  222.22  4909.4  221.86  4972.3  221.73  4972.6  221.23
  4976.1  221.23  4976.3  221.73  5090.3  222.16  5132.7  222.86  5175.2  224.29
  5288.3  229.18  5387.3  231.88  5394.4  231.95  5401.1  232.23  5429.7  232.97
#Mann= 5 ,-1 , 0
  4071.4     .12       0  4392.1     .05       0  4972.3     .05       0
  4976.3     .05       0  5401.1    .063       0
Bank Sta=4972.3,4976.3
XS Rating Curve= 0 ,0
Exp/Cntr=0.3,0.1

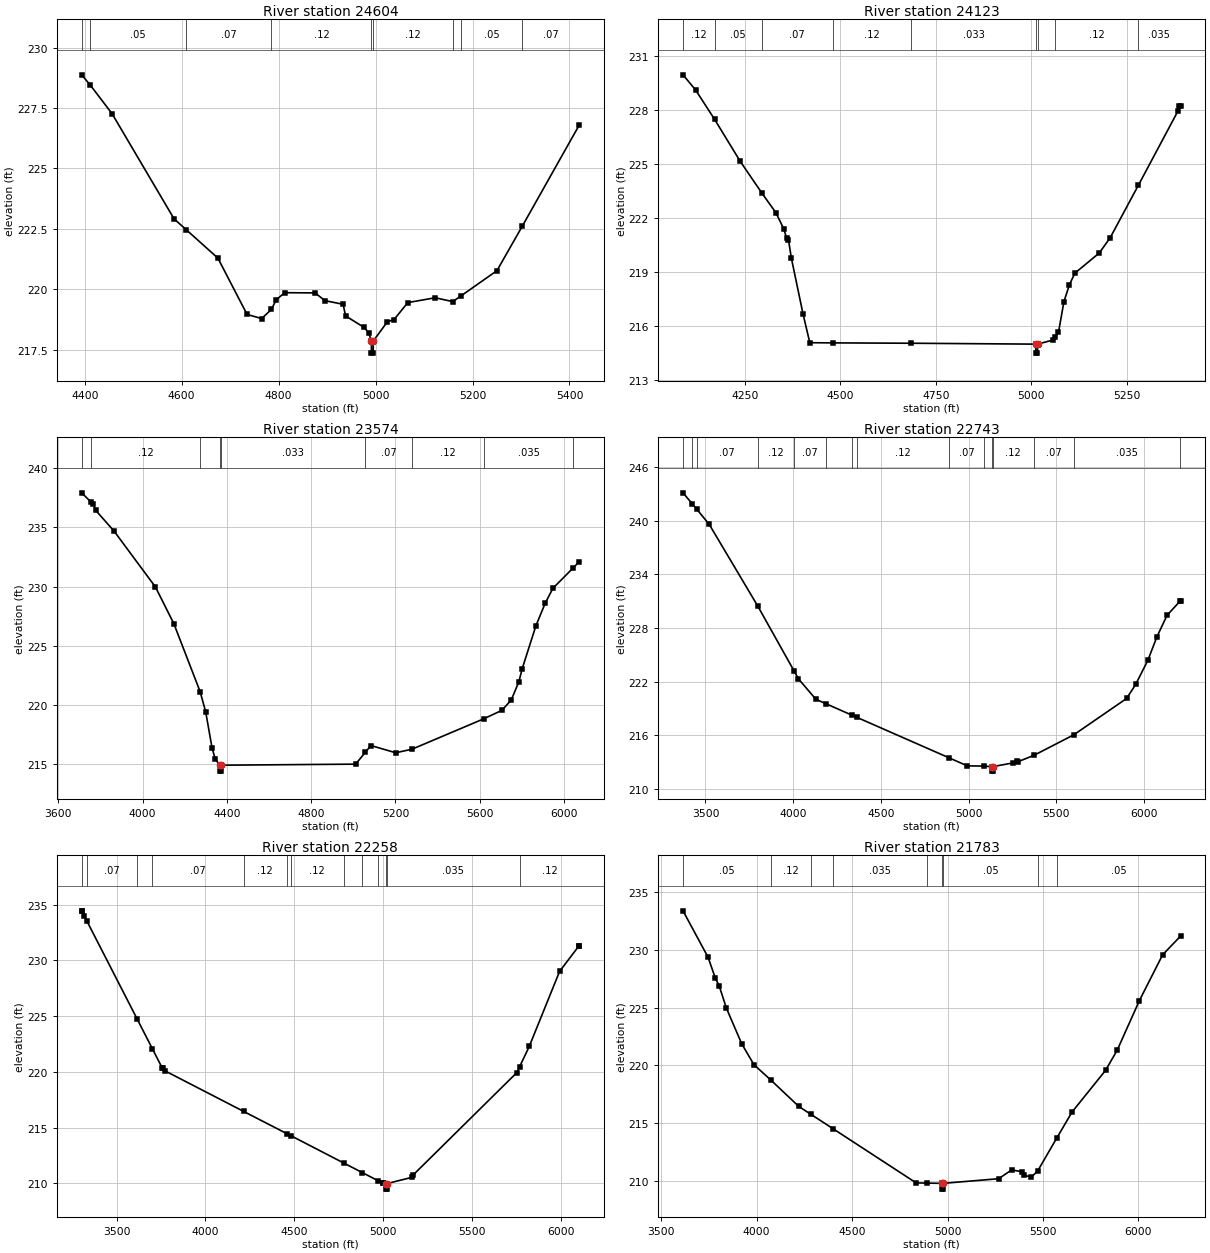
Type RM Length L Ch R = 1 ,24604   ,481,481,481
BEGIN DESCRIPTION:
SCS CHANNEL 45.0
END DESCRIPTION:
XS GIS Cut Line= 3
      2519675.04       13598375.        2519075.       13598325.
      2518774.99     13598625.01
#Sta/Elev= 30
  4393.7  228.87  4411.3  228.45  4456.5  227.26  4584.4  222.91  4609.1  222.47
  4674.7  221.29  4734.9  218.96    4765  218.79  4785.3  219.17  4795.1  219.57
  4812.7  219.86  4875.4  219.85  4895.5  219.53  4933.1  219.38  4938.1   218.9
  4975.8  218.43  4985.8  218.21  4991.3  217.86  4991.6  217.36  4995.1  217.36
  4995.3  217.86  5024.1  218.65  5038.2  218.75  5066.5  219.45  5123.1  219.65
  5159.2  219.49  5176.5  219.73  5250.4  220.77  5302.4   222.6  5420.1  226.79
#Mann= 9 ,-1 , 0
  4393.7     .12       0  4411.3     .05       0  4609.1     .07       0
  4785.3     .12       0  4991.3     .05       0  4995.3     .12       0
  5159.2     .07       0  5176.5     .05       0  5302.4     .07       0
Bank Sta=4991.3,4995.3
XS Rating Curve= 0 ,0
Exp/Cntr=0.3,0.1

Type RM Length L Ch R = 1 ,24123   ,549,549,549
BEGIN DESCRIPTION:
SCS CHANNEL 44.0
END DESCRIPTION:
XS GIS Cut Line= 3
      2519724.97       13598275.        2518825.       13598125.
        2518525.       13598375.
#Sta/Elev= 30
    4088  229.95  4120.9  229.11  4170.8  227.47  4237.5  225.15  4294.6  223.37
  4331.3  222.28  4351.6  221.39  4359.2  220.88  4364.2  220.77  4371.8  219.75
  4402.2  216.66    4420  215.05  4479.9  215.04  4685.7  215.02  5011.6  214.97
    5012  214.47  5016.2  214.47  5016.5  214.97    5057   215.2  5063.4  215.39
  5071.3  215.63  5085.6  217.34    5100  218.28  5114.3  218.92  5178.1  220.04
  5206.7  220.89  5280.3   223.8  5383.7  227.92  5387.6  228.21  5390.9  228.21
#Mann= 9 ,-1 , 0
    4088     .12       0  4170.8     .05       0  4294.6     .07       0
  4479.9     .12       0  4685.7    .033       0  5011.6    .033       0
  5016.5    .033       0  5063.4     .12       0  5280.3    .035       0
Bank Sta=5011.6,5016.5
XS Rating Curve= 0 ,0
Exp/Cntr=0.3,0.1

Type RM Length L Ch R = 1 ,23574   ,831,831,831
BEGIN DESCRIPTION:
E20801
END DESCRIPTION:
XS GIS Cut Line= 3
       2520230.5     13597786.44      2518746.09     13597630.19
       2518316.4      13598385.4
#Sta/Elev= 30
  3710.6  237.91    3755  237.13  3766.4  236.94  3776.8  236.44  3864.8  234.67
  4060.9  229.96  4148.5  226.85  4272.8  221.13  4299.3  219.42  4329.5  216.38
  4344.9  215.42  4367.3  214.92  4367.6  214.42  4371.8  214.42  4372.2  214.92
  5011.1  215.01  5056.4     216  5083.6  216.58  5201.2  215.97  5278.4  216.27
  5620.9  218.85    5705  219.55  5749.5  220.42  5785.7  221.96  5801.6  223.07
  5866.5  226.68  5910.6  228.59  5947.2  229.85  6042.3  231.55  6072.1   232.1
#Mann= 9 ,-1 , 0
  3710.6     .07       0    3755     .12       0  4272.8    .033       0
  4367.3    .033       0  4372.2    .033       0  5056.4     .07       0
  5278.4     .12       0  5620.9    .035       0  6042.3     .12       0
Bank Sta=4367.3,4372.2
XS Rating Curve= 0 ,0
Exp/Cntr=0.3,0.1

Type RM Length L Ch R = 1 ,22743   ,485,485,485
BEGIN DESCRIPTION:
SCS CHANNEL 43.0
END DESCRIPTION:
XS GIS Cut Line= 3
      2519874.97     13595975.03        2518775.       13597175.
      2518275.02     13598274.96
#Sta/Elev= 30
  3372.2  243.11  3425.8  241.86  3449.1  241.31  3521.1   239.6  3798.6  230.44
  4004.4  223.23  4030.4  222.31  4129.7  220.03  4187.5  219.53  4337.9  218.23
  4363.6  218.01  4888.4  213.49  4992.9  212.59  5087.7  212.56  5132.6   212.5
    5133     212  5137.2     212  5137.6   212.5    5256  212.93  5273.6  213.16
    5279  213.03  5373.2  213.77  5599.8  216.06  5900.8  220.12  5952.4  221.69
  6021.6  224.37  6073.2  226.99  6131.4  229.42  6206.9  231.03  6208.3  231.03
#Mann= 15 ,-1 , 0
  3372.2     .05       0  3425.8     .12       0  3449.1     .07       0
  3798.6     .12       0  4004.4     .07       0  4187.5     .12       0
  4337.9     .07       0  4363.6     .12       0  4888.4     .07       0
  5087.7     .12       0  5132.6     .05       0  5137.6     .12       0
  5373.2     .07       0  5599.8    .035       0  6206.9     .12       0
Bank Sta=5132.6,5137.6
XS Rating Curve= 0 ,0
Exp/Cntr=0.3,0.1

Type RM Length L Ch R = 1 ,22258   ,475,475,475
BEGIN DESCRIPTION:
SCS CHANNEL 42.0
END DESCRIPTION:
XS GIS Cut Line= 3
      2519525.02     13595974.98        2518325.       13597175.
        2518225.     13598274.98
#Sta/Elev= 29
  3302.9  234.46  3306.5  234.46  3317.1  234.01  3331.7  233.56  3616.1  224.72
  3700.6  222.09  3755.5  220.38  3762.5  220.35  3769.6  220.11  4214.7  216.45
  4457.2  214.46  4480.8  214.27  4777.9  211.82  4883.7  210.95  4971.5  210.23
    5000  209.99  5002.5  209.99  5017.5  209.97  5017.9  209.47  5022.2  209.47
  5022.6  209.97  5160.6  210.52  5170.7  210.76  5753.1  219.93  5768.7  220.45
  5823.4  222.29  5994.1  229.02    6102  231.29  6104.5  231.29
#Mann= 13 ,-1 , 0
  3302.9     .12       0  3331.7     .07       0  3616.1     .12       0
  3700.6     .07       0  4214.7     .12       0  4457.2     .07       0
  4480.8     .12       0  4777.9     .07       0  4883.7      .1       0
  4971.5    .035       0  5017.5    .035       0  5022.6    .035       0
  5768.7     .12       0
Bank Sta=5017.5,5022.6
XS Rating Curve= 0 ,0
Exp/Cntr=0.3,0.1

Type RM Length L Ch R = 1 ,21783   ,440,440,440
BEGIN DESCRIPTION:
SCS CHANNEL 41.0
END DESCRIPTION:
XS GIS Cut Line= 3
      2518625.02     13595774.97        2517925.       13596975.
      2517725.01     13598174.97
#Sta/Elev= 30
  3614.7  233.37  3745.8  229.36    3783  227.59  3804.5  226.87  3841.7  224.96
  3921.9  221.88  3986.4  220.06    4073  218.76  4221.3  216.45  4284.5  215.77
  4401.8  214.51  4835.7  209.84  4892.7  209.82  4972.1   209.8  4972.5   209.3
  4976.8   209.3  4977.2   209.8  5267.6   210.2    5336  210.96  5389.2  210.81
  5401.9  210.48  5439.9  210.36  5471.8  210.86  5571.2  213.69  5652.8  215.98
  5827.7  219.57  5888.5  221.31  6005.1  225.61  6126.8  229.57  6220.5  231.18
#Mann= 9 ,-1 , 0
  3614.7     .05       0    4073     .12       0  4284.5     .07       0
  4401.8    .035       0  4892.7     .05       0  4972.1     .05       0
  4977.2     .05       0  5471.8    .035       0  5571.2     .05       0
Bank Sta=4972.1,4977.2
XS Rating Curve= 0 ,0
Exp/Cntr=0.3,0.1

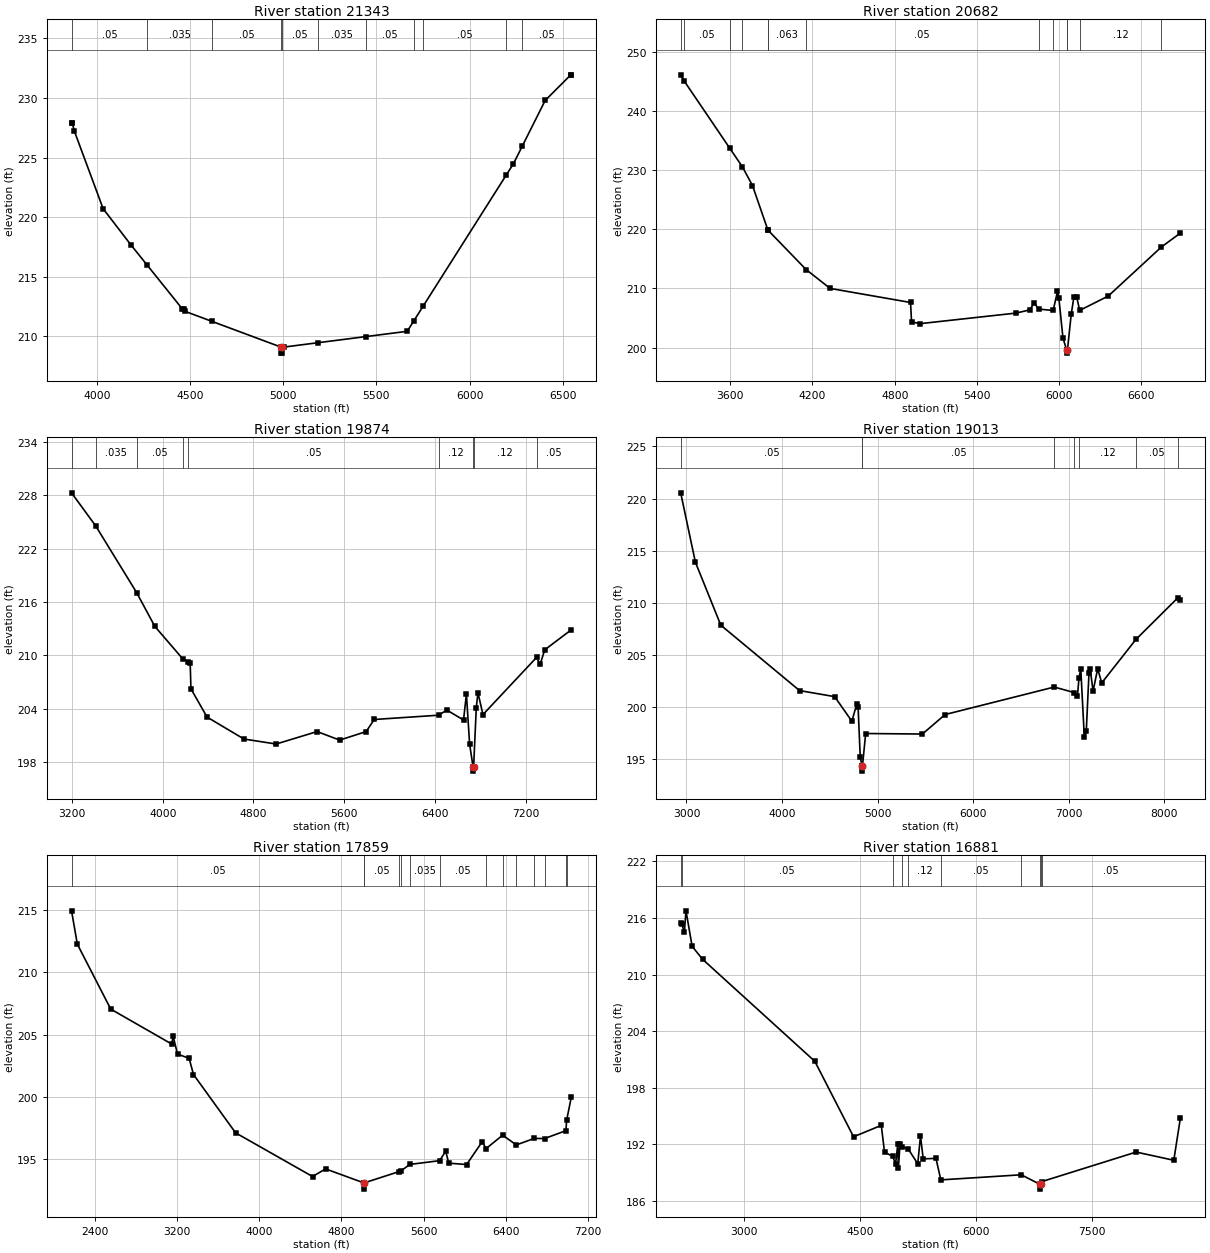
Type RM Length L Ch R = 1 ,21343   ,661,661,661
BEGIN DESCRIPTION:
SCS CHANNEL 40.0
END DESCRIPTION:
XS GIS Cut Line= 3
      2518425.01     13595874.99        2517625.       13596675.
        2517675.     13598225.01
#Sta/Elev= 28
    3864  227.94  3867.6  227.94  3878.2  227.26  4033.7  220.71  4182.2  217.69
    4270  215.98    4458  212.32  4465.1  212.27  4472.1  212.11  4616.4  211.27
  4989.3   209.1  4989.7   208.6  4994.1   208.6  4994.5   209.1  4995.4   209.1
  4997.9   209.1  5005.4  209.11  5185.1  209.47  5445.3  209.99  5665.7  210.43
  5701.7  211.32  5751.6  212.55  6195.7   223.5    6236  224.49  6282.5  225.94
  6406.1  229.79  6543.7  231.94  6546.2  231.94
#Mann= 11 ,-1 , 0
    3864     .05       0    4270    .035       0  4616.4     .05       0
  4989.3     .05       0  4994.5     .05       0  5185.1    .035       0
  5445.3     .05       0  5701.7    .035       0  5751.6     .05       0
  6195.7     .12       0  6282.5     .05       0
Bank Sta=4989.3,4994.5
XS Rating Curve= 0 ,0
Exp/Cntr=0.3,0.1

Type RM Length L Ch R = 1 ,20682   ,808,808,808
BEGIN DESCRIPTION:
E20800
END DESCRIPTION:
XS GIS Cut Line= 3
      2518420.56     13595130.19      2516975.26     13596497.38
      2517066.37     13598150.47
#Sta/Elev= 30
  3238.9  246.15  3263.9  245.13    3597  233.73  3689.5  230.57  3762.6  227.42
  3875.1  219.88  3875.2  219.88  4153.4  213.21  4328.6  210.01  4915.6  207.63
  4922.8  204.34  4986.3  204.05  5686.7  205.84  5786.9  206.39  5816.9   207.6
  5849.1  206.51  5955.9  206.28  5987.2  209.49  5997.2  208.42  6027.2  201.61
  6054.7  199.56  6055.1  199.06  6059.9  199.56  6087.3  205.61  6107.4  208.61
  6127.4  208.55  6149.2  206.29  6357.7  208.72  6745.3  217.02    6884  219.38
#Mann= 13 ,-1 , 0
  3238.9    .035       0  3263.9     .05       0    3597    .035       0
  3689.5     .05       0  3875.1    .035       0  3875.2    .063       0
  4153.4     .05       0  5849.1     .12       0  5955.9     .05       0
  6054.7     .05       0  6059.9     .05       0  6149.2     .12       0
  6745.3     .05       0
Bank Sta=6054.7,6059.9
XS Rating Curve= 0 ,0
Exp/Cntr=0.3,0.1

Type RM Length L Ch R = 1 ,19874   ,861,861,861
BEGIN DESCRIPTION:
E20799
END DESCRIPTION:
XS GIS Cut Line= 3
      2517912.76     13594466.13      2516363.28     13596223.94
      2516727.87     13598255.24
#Sta/Elev= 30
  3195.9  228.29  3409.9  224.55  3769.8  217.07  3930.1  213.27  4174.7  209.64
    4225  209.26  4242.2  209.13  4248.9  206.24  4391.1  203.06  4716.5  200.59
  5000.2  200.03  5361.6  201.43  5560.5  200.47  5794.2  201.43  5865.3  202.79
  6432.6  203.27  6505.4  203.85  6652.7  202.73  6678.1  205.64  6706.4  200.01
  6736.5  197.48  6736.9  196.98  6741.7  197.48  6765.2  204.11  6779.7  205.82
    6824  203.34  7297.3  209.78  7327.6  208.98    7369  210.63  7602.9  212.88
#Mann= 9 ,-1 , 0
  3195.9     .05       0  3409.9    .035       0  3769.8     .05       0
  4174.7    .035       0    4225     .05       0  6432.6     .12       0
  6736.5     .05       0  6741.7     .12       0  7297.3     .05       0
Bank Sta=6736.5,6741.7
XS Rating Curve= 0 ,0
Exp/Cntr=0.3,0.1

Type RM Length L Ch R = 1 ,19013   ,1154,1154,1154
BEGIN DESCRIPTION:
E20798
END DESCRIPTION:
XS GIS Cut Line= 3
      2517209.65     13593606.73      2515959.63     13595494.77
       2516623.7     13598385.43
#Sta/Elev= 30
  2939.7  220.55  3093.5   213.9  3359.5  207.85  4183.9  201.57    4551  200.99
  4731.5  198.63  4782.7  200.28  4796.6  199.97  4818.8  195.24  4837.2  194.34
  4837.6  193.84  4842.4  194.34  4875.9  197.45  5469.8   197.4    5707  199.27
    6849  201.91  7058.7  201.38  7092.2  201.05  7108.4  202.78  7127.2  203.64
    7164  197.14  7184.6  197.67  7212.9  203.23  7225.6  203.65  7255.7  201.51
  7303.7  203.66  7346.6  202.31  7704.2  206.48  8143.5  210.48    8170  210.22
#Mann= 8 ,-1 , 0
  2939.7     .05       0  4837.2     .05       0  4842.4     .05       0
    6849     .12       0  7058.7     .05       0  7108.4     .12       0
  7704.2     .05       0  8143.5     .12       0
Bank Sta=4837.2,4842.4
XS Rating Curve= 0 ,0
Exp/Cntr=0.3,0.1

Type RM Length L Ch R = 1 ,17859   ,978,978,978
BEGIN DESCRIPTION:
SCS CHANNEL 38.0
END DESCRIPTION:
XS GIS Cut Line= 3
      2517024.98     13593425.02        2515025.       13595425.
        2515425.     13597424.99
#Sta/Elev= 30
  2171.1  214.91  2227.6  212.24  2552.9  207.04  3146.9  204.24    3161  204.87
  3203.4  203.43  3316.6   203.1    3359   201.8  3769.1  197.13  4518.7  193.63
  4645.9  194.24  5017.9  193.12  5018.1  192.62  5021.9  193.12  5363.8  194.03
  5377.9  194.07  5467.4   194.6  5757.1   194.9  5815.3  195.66  5845.9   194.7
  6019.3  194.59  6172.3  196.43  6208.4  195.86    6370  196.94  6504.1  196.16
  6677.5  196.68  6778.6  196.67  6986.2   197.3  6994.7  198.17  7039.1  199.98
#Mann= 14 ,-1 , 0
  2171.1     .05       0  5017.9     .05       0  5021.9     .05       0
  5363.8    .035       0  5377.9     .05       0  5467.4    .035       0
  5757.1     .05       0  6208.4     .07       0    6370     .05       0
  6504.1     .12       0  6677.5     .07       0  6778.6     .12       0
  6986.2     .05       0  6994.7     .12       0
Bank Sta=5017.9,5021.9
XS Rating Curve= 0 ,0
Exp/Cntr=0.3,0.1

Type RM Length L Ch R = 1 ,16881   ,939,939,939
BEGIN DESCRIPTION:
E20797
END DESCRIPTION:
XS GIS Cut Line= 3
      2517027.35      13592890.6      2514201.82       13595013.
      2513459.82     13597837.81
#Sta/Elev= 30
  2183.3  215.52  2196.3  215.33  2231.1  214.53    2252  216.76  2331.1     213
  2466.5  211.62  3916.2   200.8  4416.1   192.8  4774.3  194.01    4816  191.18
  4919.4  190.73  4959.7  189.96  4987.8  192.07  4995.1  189.45    5016  192.05
  5045.1  191.76  5122.4   191.5  5245.1  189.94  5280.5  192.86  5315.9  190.46
  5480.4  190.51  5543.3  188.23  6581.8  188.77  6826.6  187.75  6826.8  187.25
  6830.6  187.75  6847.9  188.05  8066.2  191.18  8552.2  190.31  8637.8  194.82
#Mann= 10 ,-1 , 0
  2183.3    .035       0  2196.3     .05       0  4919.4    .035       0
  5045.1     .05       0  5122.4     .12       0  5543.3     .05       0
  6581.8     .07       0  6826.6    .035       0  6830.6     .07       0
  6847.9     .05       0
Bank Sta=6826.6,6830.6
XS Rating Curve= 0 ,0
Exp/Cntr=0.3,0.1

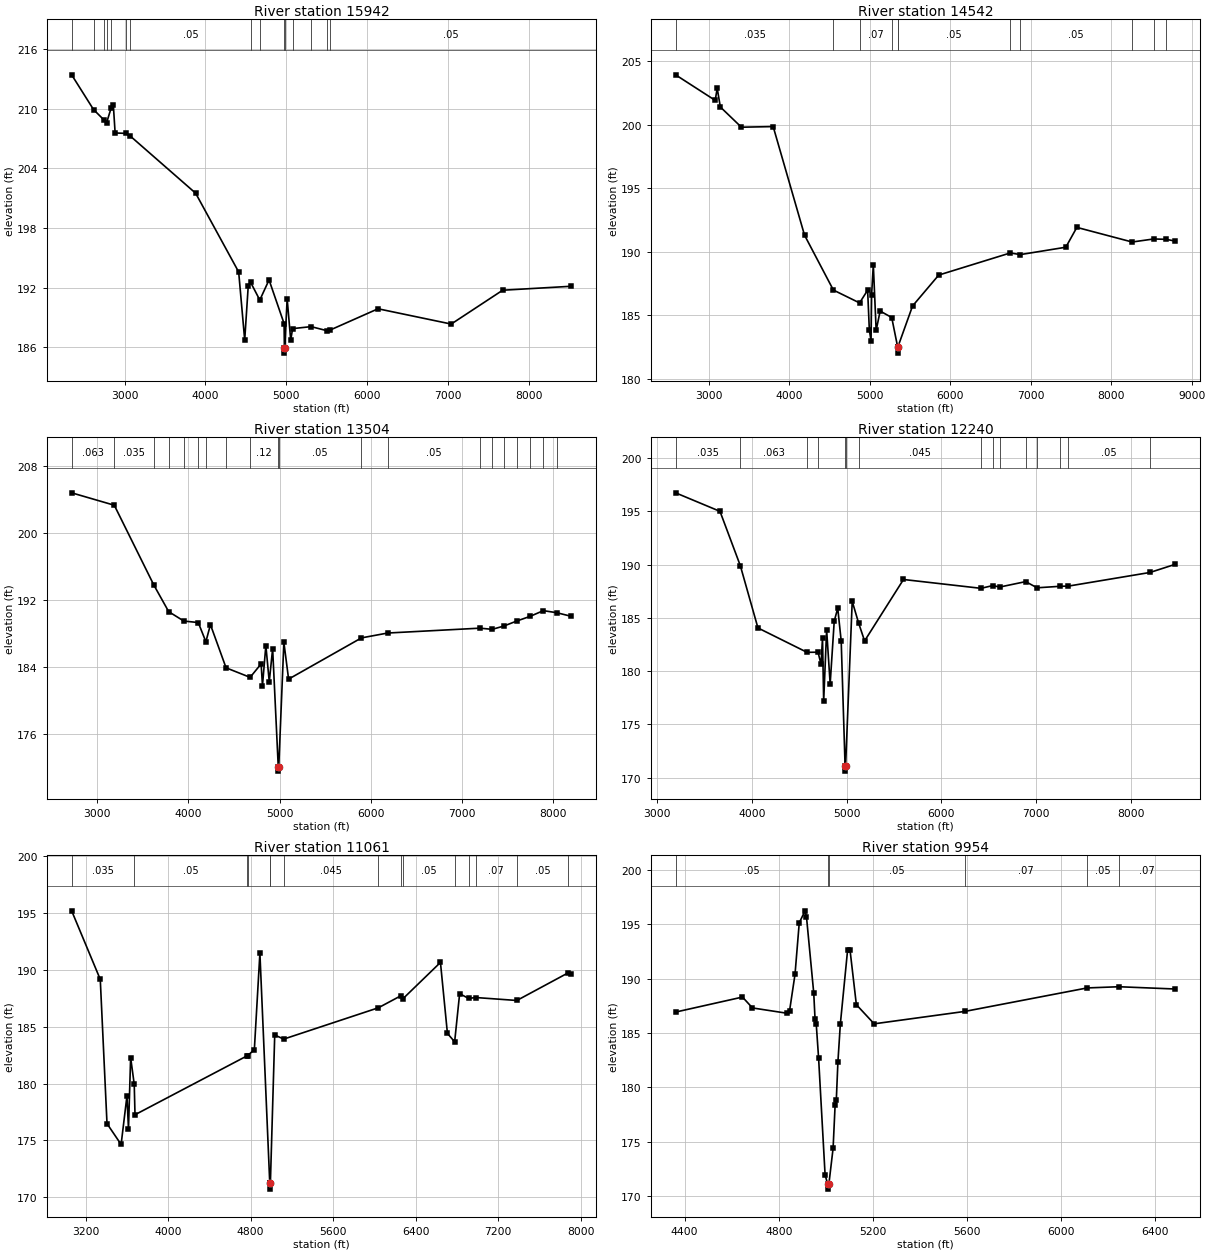
Type RM Length L Ch R = 1 ,15942   ,1400,1400,1400
BEGIN DESCRIPTION:
E20796
END DESCRIPTION:
XS GIS Cut Line= 3
      2516714.86     13592656.22      2513759.11     13594244.77
      2511766.91     13596249.99
#Sta/Elev= 30
  2344.6  213.44  2615.2  209.94  2744.4  208.89  2777.3  208.62  2833.1   210.1
  2860.3  210.39  2882.2  207.58    3011  207.54  3069.4  207.27  3878.1  201.51
  4410.6  193.57  4485.2  186.71  4529.1  192.18  4558.6  192.52    4672  190.74
  4786.4  192.77  4972.3  188.37  4976.3  185.89  4976.5  185.39  4980.3  185.89
  5010.4  190.87  5054.2  186.71    5078  187.86  5306.9  188.06  5508.2  187.64
  5534.3  187.69  6134.6  189.86  7039.7  188.32  7676.1  191.73  8526.8  192.13
#Mann= 15 ,-1 , 0
  2344.6     .05       0  2615.2    .035       0  2744.4     .05       0
  2777.3    .035       0  2833.1     .05       0    3011    .035       0
  3069.4     .05       0  4558.6    .035       0    4672     .12       0
  4976.3     .05       0  4980.3     .12       0    5078     .07       0
  5306.9     .05       0  5508.2      .1       0  5534.3     .05       0
Bank Sta=4976.3,4980.3
XS Rating Curve= 0 ,0
Exp/Cntr=0.3,0.1

Type RM Length L Ch R = 1 ,14542   ,1038,1038,1038
BEGIN DESCRIPTION:
E20795
END DESCRIPTION:
XS GIS Cut Line= 4
      2516387.07     13591838.18      2514138.84     13592564.13
      2513408.25     13593290.59      2511806.65       13595611.
#Sta/Elev= 30
  2584.6  203.93  3077.1  201.92  3101.7  202.87  3141.1   201.4  3402.7  199.81
  3797.6  199.86  4187.2  191.32    4546     187  4871.6  185.99  4971.7  186.99
  4992.9  183.87  5014.1     183  5021.2  186.64  5042.4  188.99  5077.8  183.83
  5127.2  185.35  5271.2  184.84  5344.4  182.54  5344.6  182.04  5348.6  182.54
  5530.3  185.75  5855.5  188.18  6745.3  189.92  6869.7  189.79  7435.1  190.37
  7572.4  191.93  8259.5  190.78  8528.4  191.02  8681.9  190.99  8796.9  190.85
#Mann= 11 ,-1 , 0
  2584.6    .035       0    4546     .05       0  4871.6     .07       0
  5271.2     .05       0  5344.4     .05       0  5348.6     .05       0
  6745.3    .035       0  6869.7     .05       0  8259.5    .035       0
  8528.4     .05       0  8681.9    .035       0
Bank Sta=5344.4,5348.6
XS Rating Curve= 0 ,0
Exp/Cntr=0.3,0.1

Type RM Length L Ch R = 1 ,13504   ,1264,1264,1264
BEGIN DESCRIPTION:
E20794
END DESCRIPTION:
XS GIS Cut Line= 3
      2515699.23     13590624.97       2513316.4     13592018.21
      2511272.12      13593815.1
#Sta/Elev= 30
  2719.1  204.76  3186.7  203.28  3621.3  193.74  3783.6  190.58  3949.3  189.46
  4107.9  189.28  4191.3  186.99  4241.5  189.03  4412.7  183.88  4676.6  182.74
  4797.5  184.35  4812.1  181.75  4849.3  186.54  4886.5  182.21  4923.7  186.16
  4985.4  172.05  4985.8  171.55  4990.8  172.05  5046.8  186.93  5098.7  182.53
    5898  187.45  6185.8  188.03  7197.4  188.61  7331.7  188.47  7458.9  188.86
  7603.6  189.47  7748.2  190.02  7892.8   190.7  8037.4  190.46  8201.1  190.02
#Mann= 20 ,-1 , 0
  2719.1    .063       0  3186.7    .035       0  3621.3    .035       0
  3783.6    .094       0  3949.3    .035       0  4107.9    .094       0
  4191.3    .035       0  4412.7    .035       0  4676.6     .12       0
  4985.4     .05       0  4990.8     .05       0    5898     .12       0
  6185.8     .05       0  7197.4    .035       0  7331.7     .07       0
  7458.9     .12       0  7603.6     .07       0  7748.2     .07       0
  7892.8    .035       0  8037.4     .05       0
Bank Sta=4985.4,4990.8
XS Rating Curve= 0 ,0
Exp/Cntr=0.3,0.1

Type RM Length L Ch R = 1 ,12240   ,1179,1179,1179
BEGIN DESCRIPTION:
E20793
END DESCRIPTION:
XS GIS Cut Line= 3
      2514970.07     13589700.49      2512912.76     13590911.44
      2511180.96     13593216.16
#Sta/Elev= 30
  3196.3  196.74  3664.5     195  3879.2  189.89  4064.7  184.05  4582.2  181.76
  4698.3  181.77  4730.5  180.62  4745.5  183.14  4757.8  177.16  4789.1  183.86
  4826.2  178.79  4869.2  184.69  4906.3   185.9  4942.7  182.82  4983.6   171.1
    4984   170.6  4989.1   171.1  5058.8  186.55    5127  184.49  5189.3  182.83
  5599.5   188.6  6416.8  187.77  6541.4  188.03  6614.3  187.89  6887.7   188.4
  7008.4  187.82  7249.8  187.96  7339.1  187.98  8198.9  189.26  8466.4  190.03
#Mann= 15 ,-1 , 0
  3196.3    .035       0  3879.2    .063       0  4582.2    .035       0
  4698.3     .05       0  4983.6     .05       0  4989.1     .05       0
    5127    .045       0  6416.8     .05       0  6541.4    .035       0
  6614.3     .05       0  6887.7    .035       0  7008.4     .07       0
  7249.8    .035       0  7339.1     .05       0  8198.9     .07       0
Bank Sta=4983.6,4989.1
XS Rating Curve= 0 ,0
Exp/Cntr=0.3,0.1

Type RM Length L Ch R = 1 ,11061   ,1107,1107,1107
BEGIN DESCRIPTION:
E20792
END DESCRIPTION:
XS GIS Cut Line= 3
      2513837.23     13589140.61      2512430.99     13590130.19
      2511064.47     13592941.31
#Sta/Elev= 30
    3065  195.16  3342.4  189.14  3407.7  176.48  3544.5  174.65  3601.1  178.91
  3615.9     176  3636.8  182.28  3671.7  179.93  3679.1  177.26  4767.8  182.44
  4772.7  182.46  4836.2  182.98    4890  191.44  4985.7  171.23  4986.2  170.73
  4991.5  171.23  5033.7  184.26    5121   183.9  6038.7  186.65    6254  187.69
  6277.6  187.45  6640.4  190.63    6708   184.4    6778  183.66  6826.4  187.89
  6913.2  187.47  6981.8  187.55  7380.9  187.29  7875.2   189.7  7910.2  189.65
#Mann= 15 ,-1 , 0
    3065    .035       0  3671.7     .05       0  4767.8     .12       0
  4772.7     .05       0  4985.7     .05       0  4991.5     .05       0
    5121    .045       0  6038.7     .05       0    6254    .035       0
  6277.6     .05       0    6778     .07       0  6913.2     .05       0
  6981.8     .07       0  7380.9     .05       0  7875.2     .07       0
Bank Sta=4985.7,4991.5
XS Rating Curve= 0 ,0
Exp/Cntr=0.3,0.1

Type RM Length L Ch R = 1 ,9954    ,818,818,818
BEGIN DESCRIPTION:
E20791
END DESCRIPTION:
XS GIS Cut Line= 2
      2511454.42     13589453.14      2510973.06     13591521.67
#Sta/Elev= 30
  4361.8  186.93    4646  188.31  4688.6  187.31    4836  186.82  4846.3  187.07
  4869.3   190.4  4887.3  195.14  4911.9  196.24  4918.1  195.67  4948.9  188.68
  4954.5  186.25  4959.6   185.8  4969.5  182.71  4997.1  171.96  5007.6  171.15
  5008.1  170.65  5013.4  171.15  5031.1   174.4  5039.7  178.38  5044.8  178.85
  5051.6  182.35  5061.9  185.83  5092.7  192.62    5103  192.65    5130  187.61
  5205.6  185.85  5590.7  186.99  6110.8  189.15  6245.7  189.26  6485.6  189.05
#Mann= 6 ,-1 , 0
  4361.8     .05       0  5007.6     .05       0  5013.4     .05       0
  5590.7     .07       0  6110.8     .05       0  6245.7     .07       0
Bank Sta=5007.6,5013.4
XS Rating Curve= 0 ,0
Exp/Cntr=0.3,0.1

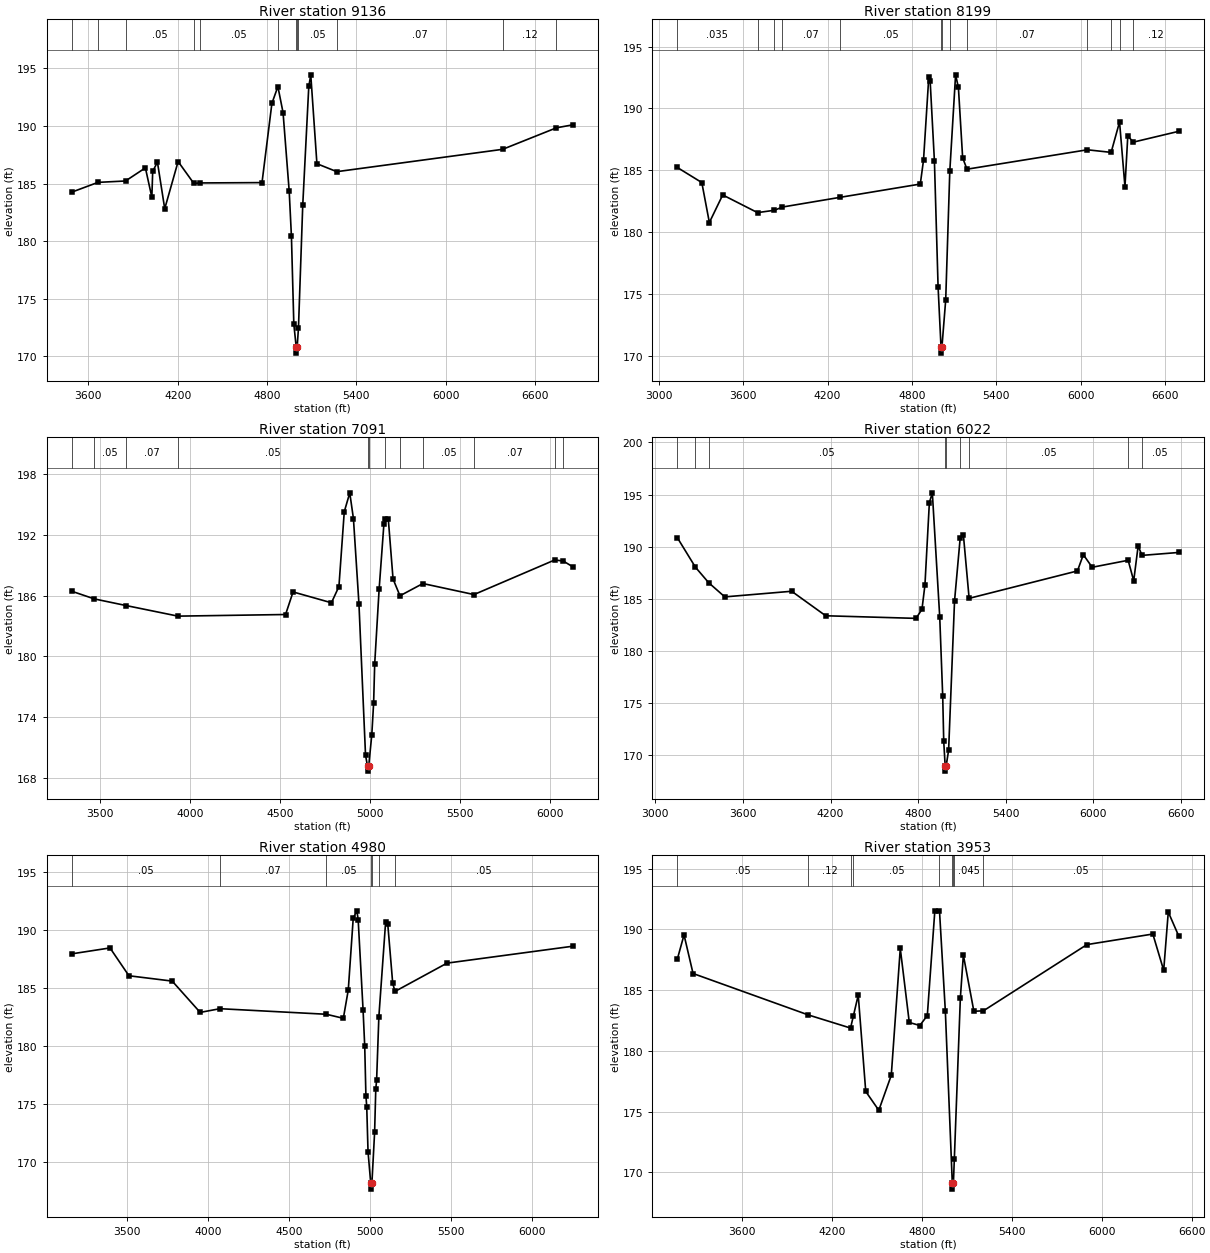
Type RM Length L Ch R = 1 ,9136    ,937,937,937
BEGIN DESCRIPTION:
E20790
END DESCRIPTION:
XS GIS Cut Line= 3
      2511246.07     13588593.76      2510582.03     13589765.61
      2510074.21     13591718.75
#Sta/Elev= 30
  3488.9  184.26  3665.2  185.11  3849.9  185.23  3983.4  186.37  4026.7  183.82
  4032.4  186.06  4064.2  186.87  4113.2  182.82    4203  186.92  4308.5  185.02
  4352.8  185.06  4766.2  185.09  4832.6  191.97  4872.8  193.43  4907.5  191.17
  4948.8  184.33  4963.7  180.42  4979.8  172.78  4996.1  170.78  4996.6  170.28
    5002  170.78  5010.9  172.46  5039.6  183.11  5080.2  193.44  5093.5  194.45
  5134.8  186.73  5268.4  186.04  6381.4  187.98    6743  189.85  6853.9  190.11
#Mann= 12 ,-1 , 0
  3488.9     .05       0  3665.2    .035       0  3849.9     .05       0
  4308.5     .07       0  4352.8     .05       0  4872.8     .07       0
  4996.1     .05       0    5002     .07       0  5010.9     .05       0
  5268.4     .07       0  6381.4     .12       0    6743     .07       0
Bank Sta=4996.1,5002
XS Rating Curve= 0 ,0
Exp/Cntr=0.3,0.1

Type RM Length L Ch R = 1 ,8199    ,1108,1108,1108
BEGIN DESCRIPTION:
E20789
END DESCRIPTION:
XS GIS Cut Line= 3
      2510451.84     13587942.66      2509735.67     13589231.75
      2509540.36     13591315.05
#Sta/Elev= 30
  3130.6  185.23  3304.9  184.01  3358.6  180.78  3453.6  183.01  3701.3  181.58
  3821.8  181.77  3878.1  182.03    4286  182.81  4859.6  183.89  4882.5  185.82
  4919.9  192.52  4929.9  192.19  4960.1  185.75  4986.3  175.55    5007  170.72
  5007.5  170.22  5013.6  170.72  5040.4  174.52  5069.6  184.94  5110.7  192.72
  5130.8   191.7  5160.9  186.02  5191.7  185.09  6048.4  186.66  6217.6  186.45
  6277.5  188.91    6316  183.67  6336.1  187.77  6376.2  187.28  6697.7  188.15
#Mann= 13 ,-1 , 0
  3130.6    .035       0  3701.3     .07       0  3821.8    .035       0
  3878.1     .07       0    4286     .05       0    5007     .05       0
  5013.6     .05       0  5069.6    .035       0  5191.7     .07       0
  6048.4     .05       0  6217.6     .07       0  6277.5     .05       0
  6376.2     .12       0
Bank Sta=5007,5013.6
XS Rating Curve= 0 ,0
Exp/Cntr=0.3,0.1

Type RM Length L Ch R = 1 ,7091    ,1069,1069,1069
BEGIN DESCRIPTION:
E20788
END DESCRIPTION:
XS GIS Cut Line= 2
      2508980.47     13587799.43      2508433.97     13590531.91
#Sta/Elev= 30
  3341.9  186.44  3467.8  185.68  3642.8  185.03  3932.4  183.98  4530.6  184.14
  4572.3  186.37  4785.5   185.3  4827.2   186.9  4856.9  194.29  4887.5  196.16
  4907.9  193.61  4938.5  185.21  4975.1  170.25  4986.1  169.17  4986.6  168.67
  4992.8  169.17  5009.9  172.25  5020.1  175.38  5026.1  179.27  5050.7  186.64
  5077.1  193.04  5086.1  193.61  5101.6  193.59  5128.1  187.65  5166.5  185.99
    5294   187.2    5578  186.11  6027.2  189.53  6074.6  189.42  6128.5  188.84
#Mann= 12 ,-1 , 0
  3341.9    .035       0  3467.8     .05       0  3642.8     .07       0
  3932.4     .05       0  4986.1     .05       0  4992.8     .05       0
  5086.1    .035       0  5166.5     .07       0    5294     .05       0
    5578     .07       0  6027.2     .05       0  6074.6     .12       0
Bank Sta=4986.1,4992.8
XS Rating Curve= 0 ,0
Exp/Cntr=0.3,0.1

Type RM Length L Ch R = 1 ,6022    ,1042,1042,1042
BEGIN DESCRIPTION:
E20787
END DESCRIPTION:
XS GIS Cut Line= 2
      2507964.84      13587382.8      2507391.93     13590768.17
#Sta/Elev= 30
  3150.8  190.87  3274.7  188.04  3365.6  186.55    3476  185.19    3934  185.73
  4167.2  183.38  4785.9  183.13  4826.5     184  4846.8  186.32  4877.2  194.24
  4897.5  195.17  4948.2  183.26  4968.5   175.7  4975.6  171.33  4985.4  168.98
  4985.9  168.48  4992.1  168.98    5009  170.48  5049.6   184.8  5088.1  190.81
  5110.5  191.09  5149.5  185.05  5891.4  187.68  5931.8  189.24  5992.2  188.03
  6238.8   188.7  6276.8  186.73  6307.2  190.08  6333.6  189.17  6584.3  189.45
#Mann= 9 ,-1 , 0
  3150.8    .035       0  3274.7     .12       0  3365.6     .05       0
  4985.4     .05       0  4992.1     .05       0  5088.1    .035       0
  5149.5     .05       0  6238.8     .07       0  6333.6     .05       0
Bank Sta=4985.4,4992.1
XS Rating Curve= 0 ,0
Exp/Cntr=0.3,0.1

Type RM Length L Ch R = 1 ,4980    ,1027,1027,1027
BEGIN DESCRIPTION:
E20786
END DESCRIPTION:
XS GIS Cut Line= 2
      2506988.28     13587174.44      2506480.58     13590220.62
#Sta/Elev= 30
  3162.3  187.92  3398.1  188.43  3514.7  186.03  3781.3  185.57  3953.6  182.87
  4075.3  183.19  4730.9  182.71  4835.6  182.36    4866  184.81  4896.5     191
  4918.8  191.63  4926.9  190.88  4957.3  183.04  4967.4  179.93  4974.6   175.7
  4979.7  174.74  4987.7  170.86  5004.4  168.13  5004.9  167.63  5011.5  168.13
  5028.2  172.52  5035.4  176.26  5040.5  177.01  5054.5  182.51  5096.2  190.69
  5109.4  190.47  5139.8  185.37    5154  184.68  5474.3  187.12  6250.5  188.58
#Mann= 7 ,-1 , 0
  3162.3     .05       0  4075.3     .07       0  4730.9     .05       0
  5004.4     .05       0  5011.5     .05       0  5054.5    .035       0
    5154     .05       0
Bank Sta=5004.4,5011.5
XS Rating Curve= 0 ,0
Exp/Cntr=0.3,0.1

Type RM Length L Ch R = 1 ,3953    ,977,977,977
BEGIN DESCRIPTION:
E20785
END DESCRIPTION:
XS GIS Cut Line= 3
      2505582.03     13587070.27      2505725.26     13589257.79
      2506246.09     13590286.44
#Sta/Elev= 30
  3167.8  187.54  3212.6  189.54  3272.8  186.36  4041.8  182.95  4323.8  181.87
  4342.9  182.88  4375.1  184.58  4425.2  176.65  4512.3   175.1  4595.6  177.98
  4655.7  188.42  4715.8  182.33    4786  182.08  4836.1   182.9  4886.2  191.52
  4917.4  191.51  4956.4  183.27  5002.8  169.11  5003.3  168.61  5010.2  169.11
  5016.3  171.07  5056.6  184.34  5076.6  187.88  5146.8  183.25  5210.6  183.29
  5901.2  188.74  6341.1  189.61  6413.5  186.62  6444.1  191.42    6513  189.47
#Mann= 9 ,-1 , 0
  3167.8     .05       0  4041.8     .12       0  4323.8     .07       0
  4342.9     .05       0  4917.4    .035       0  5002.8    .035       0
  5010.2    .035       0  5016.3    .045       0  5210.6     .05       0
Bank Sta=5002.8,5010.2
XS Rating Curve= 0 ,0
Exp/Cntr=0.3,0.1