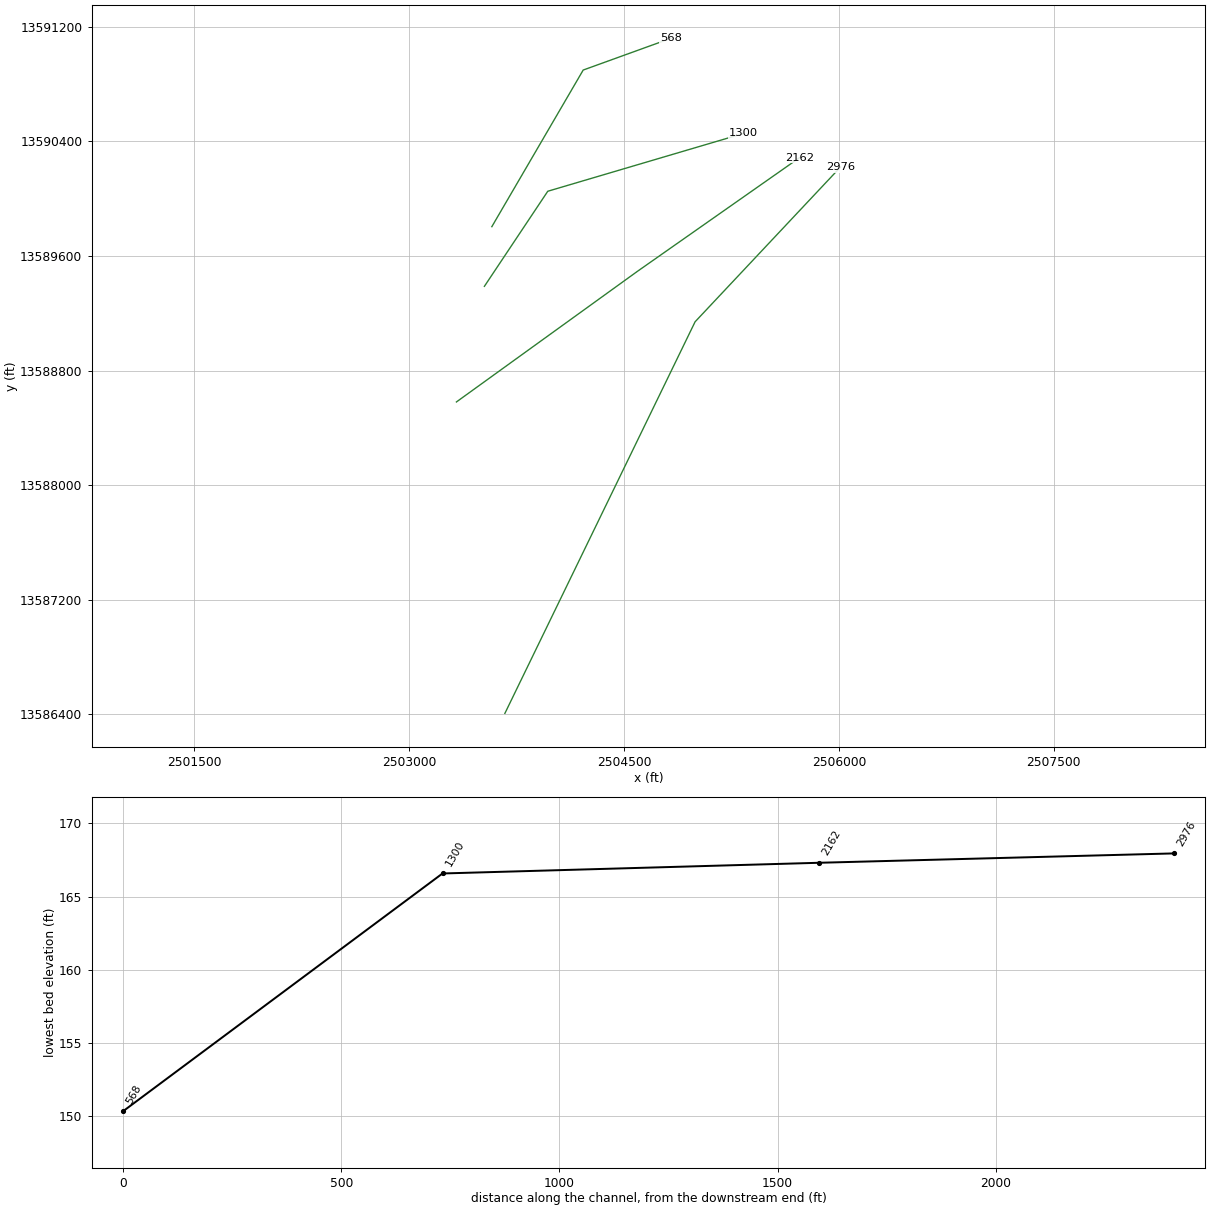
HEC-RAS study SCS CHANNEL.prj: SCS CHANNEL Base Level Engineering

--- SCS CHANNEL.g01 (geometry) --- (continued)

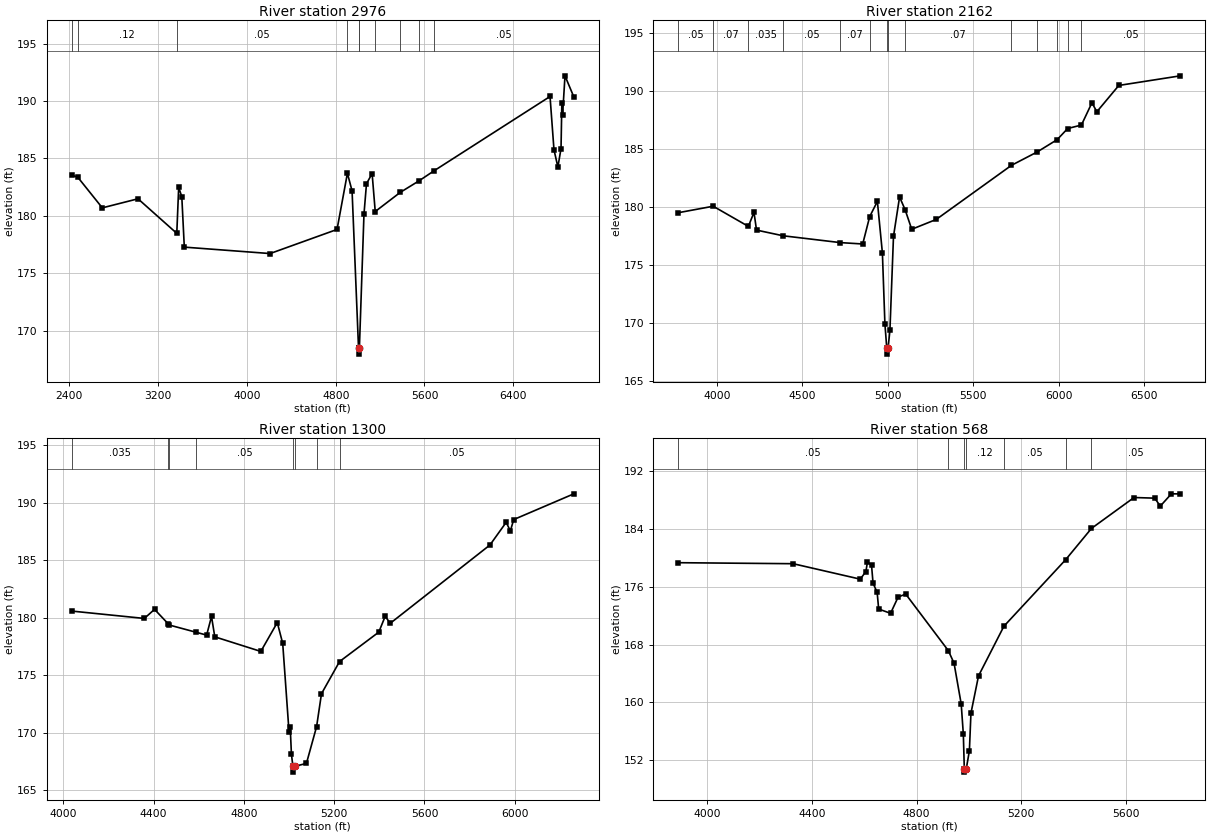
Type RM Length L Ch R = 1 ,2976    ,814,814,814
BEGIN DESCRIPTION:
E20784
END DESCRIPTION:
XS GIS Cut Line= 3
      2503667.97     13586406.25      2504996.09     13589140.61
      2506011.72     13590221.34
#Sta/Elev= 30
  2422.5  183.53  2475.7  183.37  2697.6  180.69  3019.1  181.48  3368.5  178.47
  3385.6  182.47  3413.7  181.66  3436.3  177.27  4208.9  176.71  4812.2  178.81
  4905.5   183.7  4947.6  182.17  5005.9  168.45  5006.4  167.95  5013.4  168.45
  5054.8  180.14  5077.4  182.79  5128.1  183.68  5156.2  180.37  5381.8  182.04
  5548.5  183.03    5688  183.93  6730.9  190.39  6766.4  185.75  6801.6  184.25
  6829.9  185.85  6837.2  189.82  6844.1  188.81  6865.6  192.19  6945.4  190.35
#Mann= 10 ,-1 , 0
  2422.5     .05       0  2475.7     .12       0  3368.5     .05       0
  4905.5    .045       0  5005.9    .045       0  5013.4    .045       0
  5156.2     .07       0  5381.8     .05       0  5548.5    .035       0
    5688     .05       0
Bank Sta=5005.9,5013.4
XS Rating Curve= 0 ,0
Exp/Cntr=0.3,0.1

Type RM Length L Ch R = 1 ,2162    ,862,862,862
BEGIN DESCRIPTION:
E20783
END DESCRIPTION:
XS GIS Cut Line= 3
      2503329.45     13588580.73      2504592.44     13589492.17
      2505725.23     13590286.42
#Sta/Elev= 30
  3772.2  179.52    3977  180.08  4182.9  178.34    4216  179.55  4230.7  178.02
    4386  177.53  4721.3  176.94  4852.8  176.82  4893.6  179.18  4938.7   180.5
  4968.1  176.05  4982.8  169.93  4993.8  167.81  4994.3  167.31  5001.3  167.81
  5012.2  169.37  5033.1  177.48  5068.7  180.88  5100.9  179.79  5139.9  178.09
  5283.5  178.94  5723.9  183.61  5874.1  184.76  5991.9  185.83  6053.3  186.79
  6133.9  187.09  6195.4  189.01  6224.4  188.24  6353.1  190.51  6713.2  191.34
#Mann= 14 ,-1 , 0
  3772.2     .05       0    3977     .07       0  4182.9    .035       0
    4386     .05       0  4721.3     .07       0  4893.6    .045       0
  4993.8    .045       0  5001.3    .045       0  5100.9     .07       0
  5723.9     .05       0  5874.1    .035       0  5991.9     .05       0
  6053.3    .035       0  6133.9     .05       0
Bank Sta=4993.8,5001.3
XS Rating Curve= 0 ,0
Exp/Cntr=0.3,0.1

Type RM Length L Ch R = 1 ,1300    ,732,732,732
BEGIN DESCRIPTION:
E20782
END DESCRIPTION:
XS GIS Cut Line= 3
      2503524.75     13589388.02      2503967.44     13590052.06
      2505334.62     13590455.71
#Sta/Elev= 30
  4037.9  180.59  4359.3  179.95  4404.4  180.74  4464.1   179.5  4469.1  179.38
  4589.9  178.74  4635.2   178.5  4656.8  180.12  4671.3  178.35  4875.1  177.08
  4948.1  179.59  4972.1  177.78  5000.2  170.05  5005.4  170.48  5010.7  168.14
  5017.3  167.08  5017.8  166.58    5025  167.08  5077.2  167.34  5122.2  170.54
  5143.8   173.4  5223.9   176.2  5397.7  178.76  5425.8  180.13  5448.6  179.53
    5890  186.34  5961.8  188.31  5980.4  187.56  5995.1  188.55  6261.5  190.79
#Mann= 8 ,-1 , 0
  4037.9    .035       0  4464.1     .05       0  4469.1    .035       0
  4589.9     .05       0  5017.3     .05       0    5025     .05       0
  5122.2    .035       0  5223.9     .05       0
Bank Sta=5017.3,5025
XS Rating Curve= 0 ,0
Exp/Cntr=0.3,0.1

Type RM Length L Ch R = 1 ,568     ,0,0,0
BEGIN DESCRIPTION:
E20781
END DESCRIPTION:
XS GIS Cut Line= 3
      2503576.84     13589804.71      2504214.84     13590898.42
      2504826.85     13591119.78
#Sta/Elev= 30
  3889.9  179.36  4328.6  179.22  4584.9  177.08  4606.4  178.14  4612.2  179.42
  4627.9  179.03  4633.7  176.53  4649.4  175.24  4655.2  172.94  4700.6  172.35
  4729.6  174.61  4758.5  175.01  4921.1  167.18    4943  165.44  4970.3  159.79
  4978.5  155.58  4982.1  150.85  4982.6  150.35  4989.9  150.85  5001.6  153.33
  5007.5  158.51  5036.4  163.68  5133.4  170.56    5369  179.77  5467.7  184.11
  5630.3  188.39  5709.2   188.3  5730.5   187.2  5772.9   188.9  5806.9  188.89
#Mann= 7 ,-1 , 0
  3889.9     .05       0  4921.1     .12       0  4982.1     .05       0
  4989.9     .12       0  5133.4     .05       0    5369    .035       0
  5467.7     .05       0
Bank Sta=4982.1,4989.9
XS Rating Curve= 0 ,0
Exp/Cntr=0.3,0.1

Chan Stop Cuts=-1
Use User Specified Reach Order=0
Composite Channel Slope=5