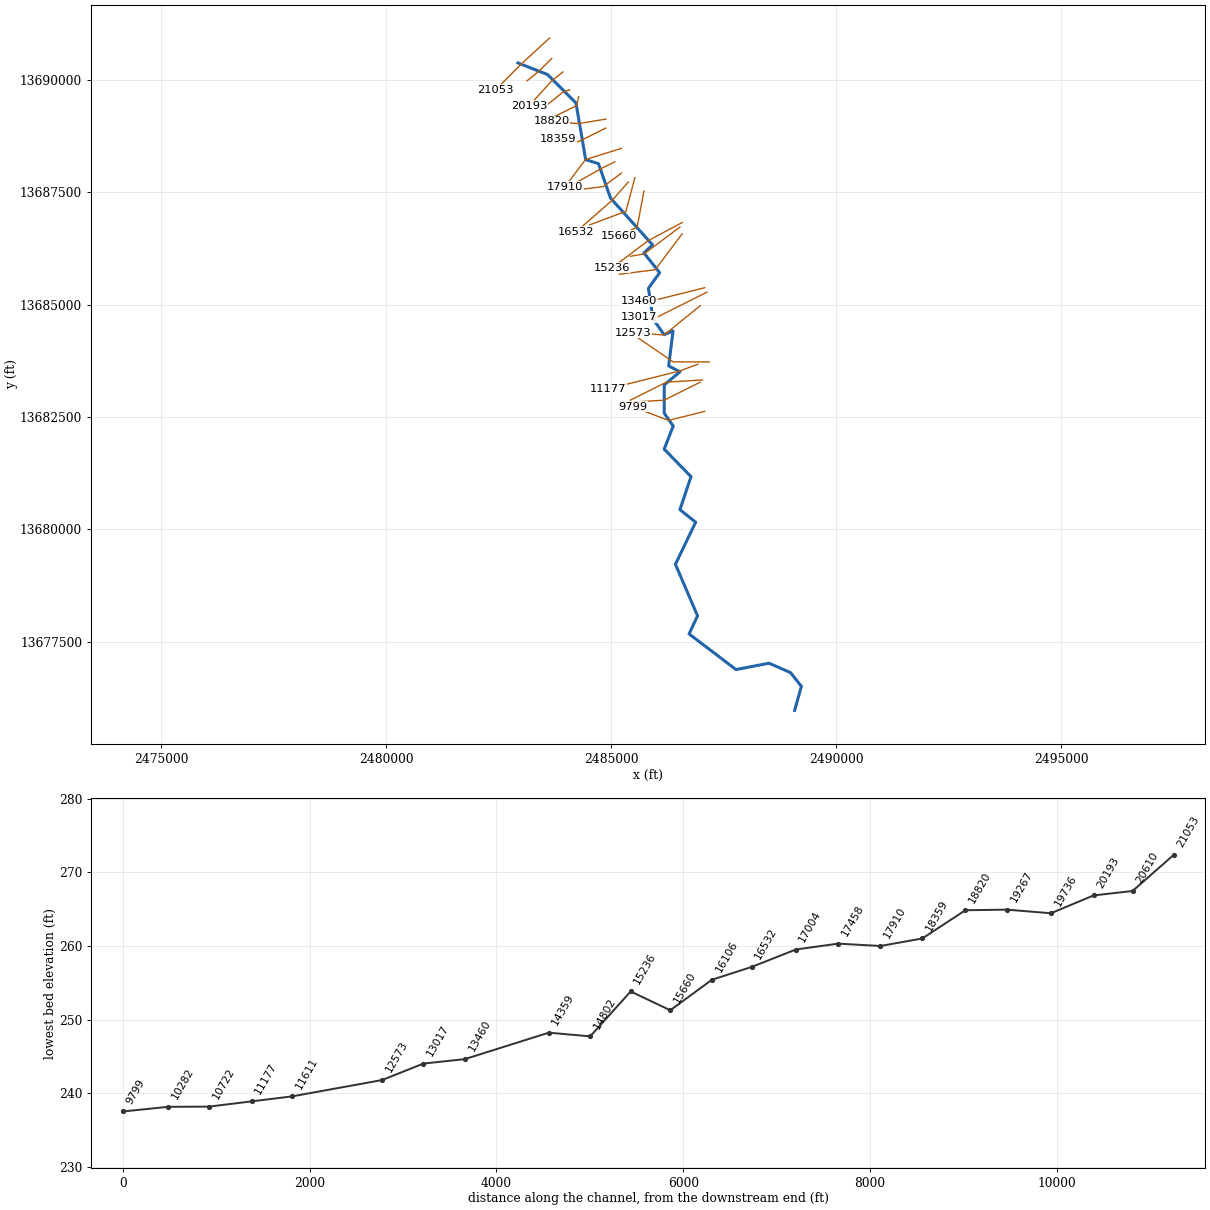
--- SOUTH DENTON CREEK.prj (project) ---

Proj Title=SOUTH DENTON CREEK Base Level Engineering
Current Plan=p01
Default Exp/Contr=0.3,0.1
English Units
Geom File=g01
Flow File=f01
Plan File=p01
Y Axis Title=Elevation
X Axis Title(PF)=Main Channel Distance
X Axis Title(XS)=Station
BEGIN DESCRIPTION:
SOUTH DENTON CREEK
END DESCRIPTION:
DSS Export Rating Curves= 0
DSS Export Rating Curve Sorted= 0
DSS Export Volume Flow Curves= 0
DXF OffsetX= 0
DXF OffsetY= 0
DXF ScaleX= 1
DXF ScaleY= 10

--- SOUTH DENTON CREEK.p01 (plan) ---

Plan Title=Multiple Run
Program Version=4.10
Short Identifier=Multiple
Geom File=g01
Flow File=f01
Subcritical Flow
K Sum by GR= 0
Std Step Tol= 0.01
Critical Tol= 0.01
Num of Std Step Trials= 20
Max Error Tol= 0.3
Flow Tol Ratio= 0.001
Split Flow NTrial= 30
Split Flow Tol= 0.02
Split Flow Ratio= 0.02
Log Output Level= 0
Friction Slope Method= 1
Unsteady Friction Slope Method= 2
Unsteady Bridges Friction Slope Method= 1
Parabolic Critical Depth
Global Vel Dist= 1 , 1 , 1
Global Log Level= 0
CheckData=True
Encroach Param=-1 ,0,0, 0
BEGIN DESCRIPTION:
Multiple Run
END DESCRIPTION:
Computation Interval=1HOUR
Output Interval=1HOUR
Run HTab= 0
Run UNet= 0
Run PostProcess= 0
Run WQNet= 0
UNET Theta= 1
UNET Theta Warmup= 1
UNET ZTol= 0.02
UNET ZSATol= 0.05
UNET MxIter= 20
UNET MaxInSteps= 0
UNET DtIC= 0
UNET DtMin= 0
UNET MaxCRTS= 20
UNET WFStab= 2
UNET SFStab= 1
UNET WFX= 1
UNET SFX= 1
UNET DSS MLevel= 4
UNET DZMax Abort= 100
UNET Convert EG Bridges= 0
UNET Use Existing IB Tables=-1
UNET Froude Reduction=False
UNET Froude Limit= 1
UNET Froude Power= 10
UNET Time Slicing=0,0, 5
UNET Junction Losses=0
Instantaneous Interval=1HOUR
Write IC File= 0
Write IC File at Sim End=0
Echo Input=False
Echo Parameters=False
Echo Output=False
Write Detailed= 0
WQ AD Non Conservative
WQ ULTIMATE=-1
WQ Max Comp Step=1HOUR
WQ Output Interval=15MIN
WQ Output Selected Increments= 0
WQ Output face flow=0
WQ Output face velocity=0
WQ Output face area=0
WQ Output face dispersion=0
WQ Output cell volume=0
WQ Output cell surface area=0
WQ Output cell continuity=0
WQ Output cumulative cell continuity=0
WQ Output face conc=0
WQ Output face dconc_dx=0
WQ Output face courant=0
WQ Output face peclet=0
WQ Output face adv mass=0
WQ Output face disp mass=0
WQ Output cell mass=0
WQ Output cell source sink temp=0
WQ Output cell source sink nsm=0
WQ Output MaxMinRange=-1
WQ Daily Max Min Mean=-1
WQ Daily Range=0
WQ Daily Time=0
WQ Create Restart=0
WQ Fixed Restart=0
WQ System Summary=0
WQ Use Fixed Temperature=0
Sorting and Armoring Iterations= 10
XS Update Threshold= 0.02
Hydraulics Update Threshold= 0.02
Energy Slope Method= 1
Volume Change Method= 0
XS Weighting Method= 0
Number of US Weighted Cross Sections= 1
Number of DS Weighted Cross Sections= 1
Upstream XS Weight=0.25
Main XS Weight=0.5
Downstream XS Weight=0.25
Number of DS XS's Weighted with US Boundary= 1
Upstream Boundary Weight= 1
Weight of XSs Associated with US Boundary= 0
Number of US XS's Weighted with DS Boundary= 1
Downstream Boundary Weight= 0.5
Weight of XSs Associated with DS Boundary= 0.5
Sediment Output Level= 4
Mass or Volume Output= 0
Output Increment Type= 1
Profile and TS Output Increment= 10
XS Output Flag= 0
XS Output Increment= 10
Disregard all LS=0
Disregard all Conn=0
Disregard all Breaches=0
Disregard all Pumps=0

--- SOUTH DENTON CREEK.f01 (steady flow) ---

Flow Title=Multiple
Number of Profiles=7
Profile Names=10-year,25-year,50-year,1pct_min,100-year,1pct_plu,500-year
River Rch & RM= SOUTH DENTON CRE,Reach-1,21053
     607     966    1286     829    1653    3299    2707
River Rch & RM= SOUTH DENTON CRE,Reach-1,17458
     797    1285    1725    1120    2234    4457    3710
River Rch & RM= SOUTH DENTON CRE,Reach-1,13460
    1089    1781    2415    1581    3155    6295    5337
River Rch & RM= SOUTH DENTON CRE,Reach-1,11611
    1182    1941    2636    1729    3450    6884    5856
River Rch & RM= SOUTH DENTON CRE,Reach-1,10282
    1392    2297    3131    2059    4109    8198    7013
River Rch & RM= SOUTH DENTON CRE,Reach-1,5326
    1755    2909    3976    2619    5225   10425    8944
Boundary for River Rch & Prof#=SOUTH DENTON CRE,Reach-1,1
Up Type=0
Dn Type=3
Dn Slope=0.005
Boundary for River Rch & Prof#=SOUTH DENTON CRE,Reach-1,2
Up Type=0
Dn Type=3
Dn Slope=0.005
Boundary for River Rch & Prof#=SOUTH DENTON CRE,Reach-1,3
Up Type=0
Dn Type=3
Dn Slope=0.005
Boundary for River Rch & Prof#=SOUTH DENTON CRE,Reach-1,4
Up Type=0
Dn Type=3
Dn Slope=0.005
Boundary for River Rch & Prof#=SOUTH DENTON CRE,Reach-1,5
Up Type=0
Dn Type=3
Dn Slope=0.005
Boundary for River Rch & Prof#=SOUTH DENTON CRE,Reach-1,6
Up Type=0
Dn Type=3
Dn Slope=0.005
Boundary for River Rch & Prof#=SOUTH DENTON CRE,Reach-1,7
Up Type=0
Dn Type=3
Dn Slope=0.005

--- SOUTH DENTON CREEK.g01 (geometry) ---

Geom Title=Existing Conditions
Program Version=4.10

River Reach=SOUTH DENTON CRE,Reach-1
Reach XY= 30
        2482925.       13690375.      2483581.38     13690116.99
      2484214.49     13689484.81       2484430.4     13688222.29
      2484714.38     13688135.05      2484982.48     13687368.94
      2485917.41     13686328.33      2485724.37     13686150.08
      2486075.25     13685709.88      2485825.54     13685364.53
      2485925.65     13684685.64      2486172.46     13684329.96
      2486371.93     13684417.48      2486275.33     13683635.87
      2486525.51     13683504.77      2486176.09     13683214.45
       2486176.2      13682585.5      2486375.41       13682300.
      2486175.93     13681785.48       2486771.9     13681173.35
      2486524.95     13680440.33      2486875.11     13680159.64
        2486425.       13679225.      2486916.95     13678078.29
      2486728.44     13677676.25      2487771.77     13676882.84
      2488504.97     13677024.94       2488984.7     13676814.23
      2489224.64     13676509.84        2489075.       13675975.

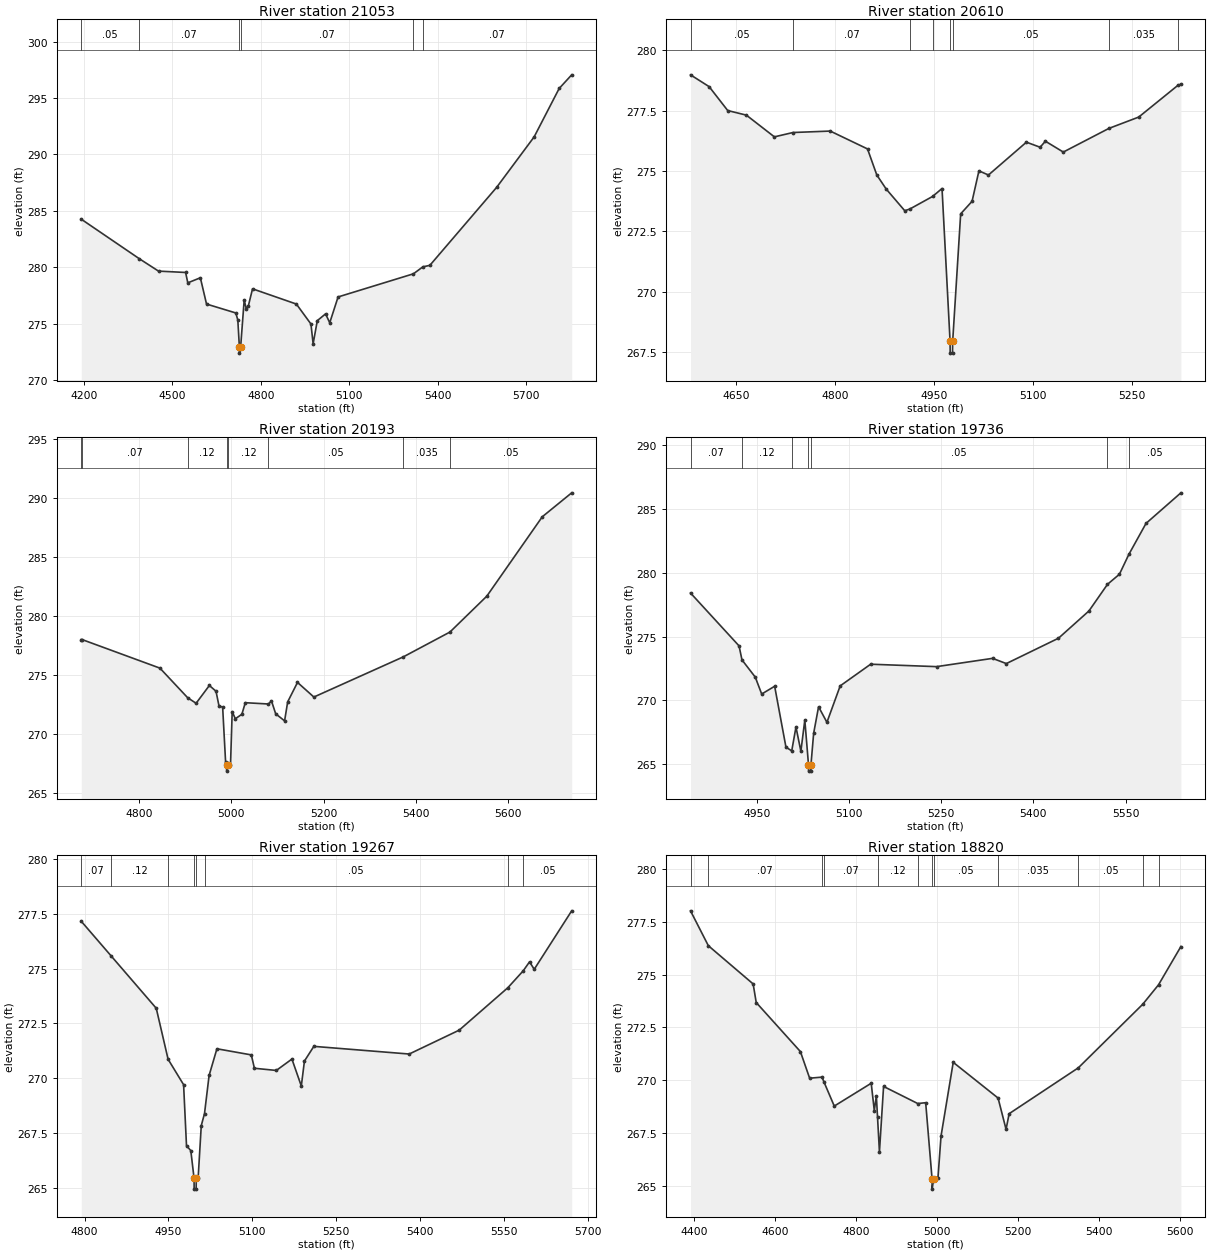
Type RM Length L Ch R = 1 ,21053   ,443,443,443
BEGIN DESCRIPTION:
SOUTH DENTON CREEK 31.0
END DESCRIPTION:
XS GIS Cut Line= 3
      2483624.99     13690924.99        2483025.       13690375.
      2482424.97     13689774.97
#Sta/Elev= 30
  4191.7  284.25  4387.7  280.76  4453.4  279.65  4545.3  279.53  4552.7  278.61
  4595.3  279.06  4616.2  276.73  4715.5  275.94  4722.3  275.31  4727.7  272.88
  4727.9  272.38  4731.7  272.88  4743.9   277.1  4750.7  276.33  4758.1  276.58
  4772.2  278.08  4920.8  276.73  4970.2  274.96  4977.6  273.21  4991.8  275.26
  5019.8  275.86  5033.9  275.07  5062.2  277.36  5317.5  279.41  5349.7  280.03
  5373.3  280.16  5599.6  287.07  5726.9  291.55  5811.7  295.84  5854.2  297.05
#Mann= 6 ,-1 , 0
  4191.7     .05       0  4387.7     .07       0  4727.7     .05       0
  4731.7     .07       0  5317.5     .12       0  5349.7     .07       0
Bank Sta=4727.7,4731.7
XS Rating Curve= 0 ,0
Exp/Cntr=0.3,0.1

Type RM Length L Ch R = 1 ,20610   ,417,417,417
BEGIN DESCRIPTION:
SOUTH DENTON CREEK 30.0
END DESCRIPTION:
XS GIS Cut Line= 3
      2483674.98     13690474.98        2483375.       13690175.
        2483125.       13689975.
#Sta/Elev= 30
  4580.4  278.99  4608.7   278.5  4636.9  277.51  4665.2  277.32  4707.7  276.42
    4736   276.6  4792.5  276.66  4849.1  275.92  4863.2  274.84  4877.4  274.26
  4905.6  273.36  4913.3  273.43  4947.8  273.95  4962.2  274.28  4974.4  267.96
  4974.6  267.46  4978.1  267.46  4978.4  267.96  4990.5  273.23  5007.8  273.75
  5018.2  275.01  5032.7  274.84  5090.3   276.2  5111.1  275.99  5119.1  276.24
  5146.3  275.79  5215.5  276.77  5260.8  277.24  5320.5  278.56  5324.8   278.6
#Mann= 8 ,-1 , 0
  4580.4     .05       0    4736     .07       0  4913.3     .12       0
  4947.8     .05       0  4974.4     .05       0  4978.4     .05       0
  5215.5    .035       0  5320.5     .05       0
Bank Sta=4974.4,4978.4
XS Rating Curve= 0 ,0
Exp/Cntr=0.3,0.1

Type RM Length L Ch R = 1 ,20193   ,457,457,457
BEGIN DESCRIPTION:
SOUTH DENTON CREEK 29.0
END DESCRIPTION:
XS GIS Cut Line= 3
      2483924.98     13690174.99        2483675.       13689975.
      2483175.02     13689425.03
#Sta/Elev= 30
  4674.8  278.01  4676.6  278.01  4845.3  275.59  4905.2  273.09  4923.7  272.61
  4952.5  274.12  4966.9  273.63  4973.3   272.4  4981.3  272.28  4987.7  267.62
  4989.7  267.36    4990  266.86  4993.7  267.36  4998.3  267.36    5002   271.9
  5008.8   271.3    5023  271.68  5030.4  272.66  5080.7  272.55  5087.2  272.81
  5096.3  271.72  5115.6  271.12  5122.3  272.73  5143.6  274.38  5179.1  273.14
  5373.3  276.55  5474.2  278.65  5554.1  281.69  5674.4  288.42  5738.2  290.45
#Mann= 8 ,-1 , 0
  4674.8     .05       0  4676.6     .07       0  4905.2     .12       0
  4989.7     .05       0  4993.7     .12       0  5080.7     .05       0
  5373.3    .035       0  5474.2     .05       0
Bank Sta=4989.7,4993.7
XS Rating Curve= 0 ,0
Exp/Cntr=0.3,0.1

Type RM Length L Ch R = 1 ,19736   ,469,469,469
BEGIN DESCRIPTION:
SOUTH DENTON CREEK 28.0
END DESCRIPTION:
XS GIS Cut Line= 3
      2484074.96     13689774.99        2483925.       13689725.
      2483424.98     13689324.99
#Sta/Elev= 30
  4841.7  278.42  4920.7  274.27  4925.5  273.17  4947.1  271.82  4957.6  270.49
  4978.7   271.1  4997.1  266.32  5006.5  266.03  5013.4   267.9  5021.4     266
  5027.8  268.45  5033.8  264.94    5034  264.44  5037.5  264.44  5037.8  264.94
  5042.2  267.41  5050.2  269.49  5063.8  268.27  5085.4  271.13    5135  272.83
  5242.3  272.64  5333.5  273.29  5355.9  272.88  5440.8  274.87  5490.4  277.01
  5520.6   279.1    5540  279.89  5555.5  281.46  5583.3  283.88  5640.1  286.28
#Mann= 7 ,-1 , 0
  4841.7     .07       0  4925.5     .12       0  5006.5     .05       0
  5033.8     .05       0  5037.8     .05       0  5520.6    .035       0
  5555.5     .05       0
Bank Sta=5033.8,5037.8
XS Rating Curve= 0 ,0
Exp/Cntr=0.3,0.1

Type RM Length L Ch R = 1 ,19267   ,447,447,447
BEGIN DESCRIPTION:
SOUTH DENTON CREEK 27.0
END DESCRIPTION:
XS GIS Cut Line= 3
      2484274.99     13689624.97        2484225.       13689425.
      2483625.04     13689125.02
#Sta/Elev= 30
  4794.1  277.16  4847.1  275.59  4928.1  273.19  4949.3  270.86    4977   269.7
  4982.2  266.91  4989.9  266.69  4995.7  265.43  4995.9  264.93  4999.4  264.93
  4999.7  265.43    5003  265.43  5008.6  267.83  5014.4  268.38  5022.6  270.12
  5036.6  271.34  5098.1  271.06  5103.6  270.45  5142.8  270.35  5170.7  270.87
  5187.5  269.64  5193.1  270.78  5209.9  271.45  5380.4   271.1  5469.8  272.19
  5556.9  274.13  5584.3   274.9  5595.6  275.31    5604  274.97    5671  277.64
#Mann= 8 ,-1 , 0
  4794.1     .07       0  4847.1     .12       0  4949.3     .07       0
  4995.7     .05       0  4999.7     .07       0  5014.4     .05       0
  5556.9    .035       0  5584.3     .05       0
Bank Sta=4995.7,4999.7
XS Rating Curve= 0 ,0
Exp/Cntr=0.3,0.1

Type RM Length L Ch R = 1 ,18820   ,461,461,461
BEGIN DESCRIPTION:
SOUTH DENTON CREEK 26.0
END DESCRIPTION:
XS GIS Cut Line= 3
      2484874.97       13689125.        2484275.       13689025.
      2483675.03       13689075.
#Sta/Elev= 30
  4391.6  278.02  4435.6  276.37  4546.2  274.56  4553.8  273.68  4662.8  271.36
  4685.6   270.1  4716.2  270.15  4720.8  269.93  4746.4  268.78  4837.6  269.86
  4845.2  268.57  4850.3  269.26  4853.2  268.25  4857.9  266.61  4868.1  269.71
  4952.5   268.9    4972  268.94  4987.7  265.35    4988  264.85  4991.7  265.35
  5002.4   265.4  5009.9  267.36    5040  270.85  5150.7  269.16  5170.4  267.68
    5178  268.42  5348.7  270.59  5507.8   273.6  5546.7  274.52  5601.9  276.33
#Mann= 12 ,-1 , 0
  4391.6     .05       0  4435.6     .07       0  4716.2     .12       0
  4720.8     .07       0  4853.2     .12       0  4952.5     .05       0
  4987.7     .05       0  4991.7     .05       0  5150.7    .035       0
  5348.7     .05       0  5507.8    .035       0  5546.7     .05       0
Bank Sta=4987.7,4991.7
XS Rating Curve= 0 ,0
Exp/Cntr=0.3,0.1

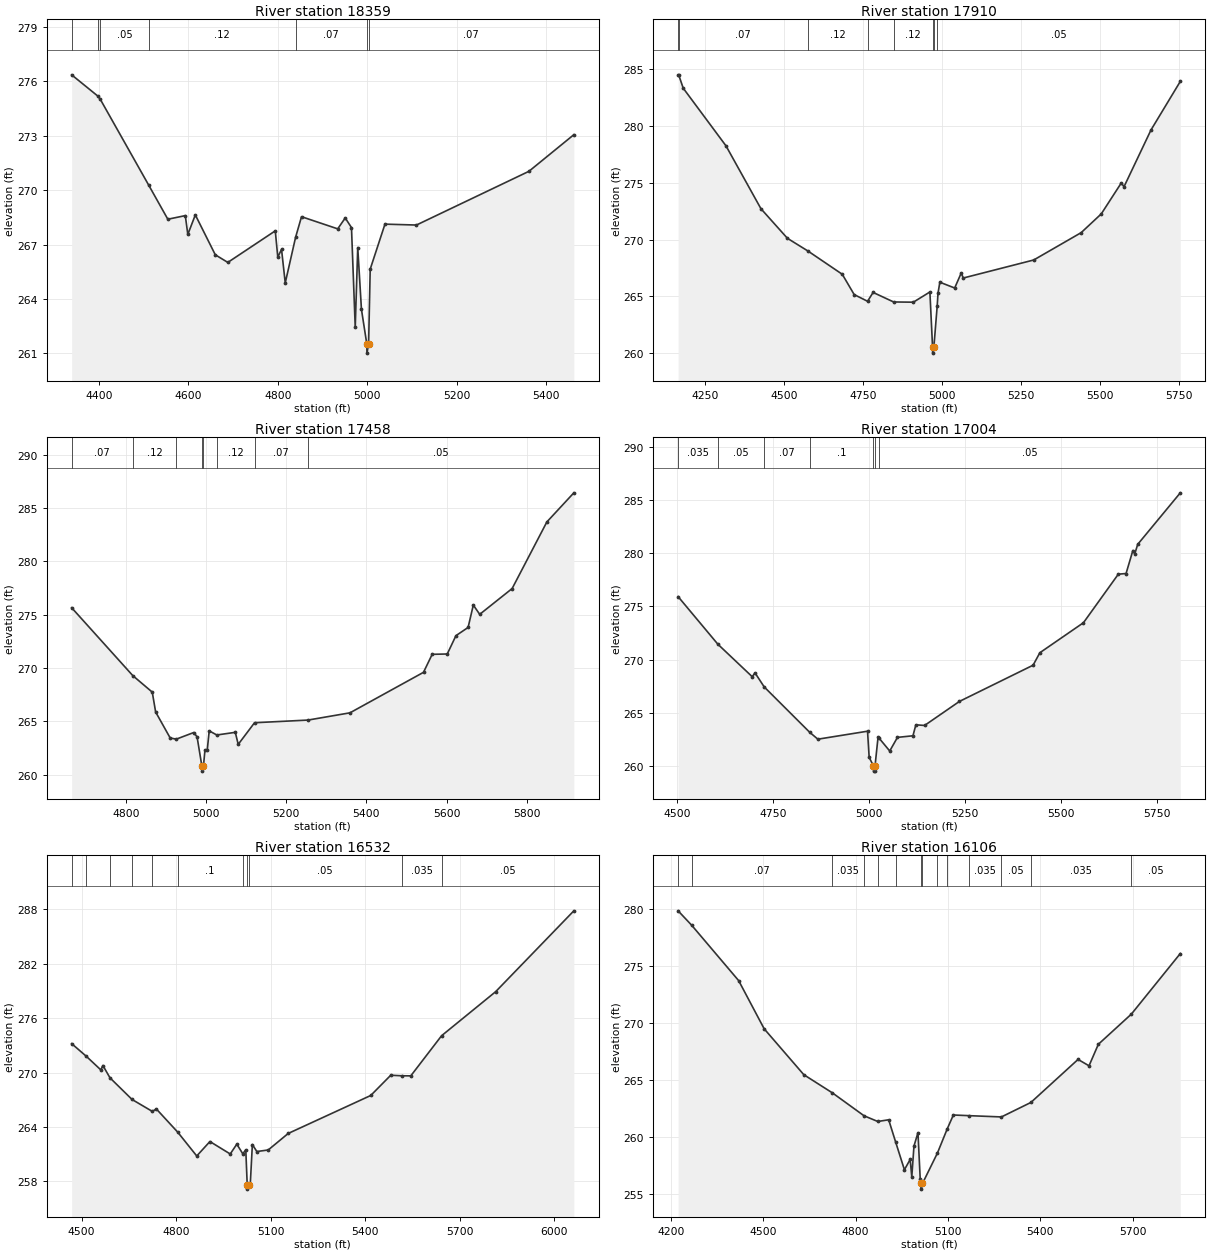
Type RM Length L Ch R = 1 ,18359   ,449,449,449
BEGIN DESCRIPTION:
SOUTH DENTON CREEK 25.0
END DESCRIPTION:
XS GIS Cut Line= 3
      2484874.98     13688924.99        2484275.       13688625.
      2483824.97       13688675.
#Sta/Elev= 30
  4338.6  276.36  4397.1  275.19  4402.7  275.01  4511.2  270.27  4553.8   268.4
  4592.9   268.6  4598.5  267.56  4615.3  268.64    4660  266.44    4688  266.02
  4794.2  267.76  4799.8  266.31  4808.2  266.74  4816.5  264.89  4839.6   267.4
  4852.9  268.54  4933.9  267.87  4950.7  268.47  4964.7  267.94  4973.1  262.44
  4978.7  266.84    4987  263.43    4999  261.52  4999.3  261.02    5003  261.52
  5006.6  265.65  5039.6  268.13    5110  268.08  5361.6  271.04  5462.2  273.06
#Mann= 7 ,-1 , 0
  4338.6     .05       0  4397.1    .035       0  4402.7     .05       0
  4511.2     .12       0  4839.6     .07       0    4999     .05       0
    5003     .07       0
Bank Sta=4999,5003
XS Rating Curve= 0 ,0
Exp/Cntr=0.3,0.1

Type RM Length L Ch R = 1 ,17910   ,452,452,452
BEGIN DESCRIPTION:
SOUTH DENTON CREEK 24.0
END DESCRIPTION:
XS GIS Cut Line= 3
      2485224.99       13688475.        2484425.       13688225.
      2483975.03     13687625.04
#Sta/Elev= 30
  4165.6  284.53  4167.3  284.53  4181.8  283.35    4317  278.27  4427.5  272.73
  4511.3  270.12  4576.2     269  4684.7  266.95  4722.4  265.16  4764.7  264.57
  4782.2  265.35  4847.1  264.51  4909.5  264.49  4961.8  265.39  4970.3   260.5
  4970.6     260  4974.3   260.5    4985  264.19  4987.5  265.29  4993.3  266.25
  5040.2  265.74    5061  267.07  5067.3  266.62  5290.2  268.21  5440.2  270.62
  5503.7  272.27  5567.3  275.01  5575.6  274.66    5661  279.67  5753.7  283.95
#Mann= 8 ,-1 , 0
  4165.6    .035       0  4167.3     .07       0  4576.2     .12       0
  4764.7      .1       0  4847.1     .12       0  4970.3     .05       0
  4974.3     .12       0    4985     .05       0
Bank Sta=4970.3,4974.3
XS Rating Curve= 0 ,0
Exp/Cntr=0.3,0.1

Type RM Length L Ch R = 1 ,17458   ,454,454,454
BEGIN DESCRIPTION:
SOUTH DENTON CREEK 23.0
END DESCRIPTION:
XS GIS Cut Line= 3
      2485074.97     13688174.99        2484775.       13688025.
      2483974.97     13687574.98
#Sta/Elev= 30
  4664.4  275.65    4817  269.28  4865.6  267.73    4874  265.87  4910.3  263.43
  4925.5  263.32    4969  263.94  4977.4  263.54  4989.3  260.82  4989.6  260.32
  4993.4  260.82    4997  262.26  5002.7  262.26  5007.7   264.1  5026.6  263.71
  5072.8  263.96  5080.1  262.83  5120.8  264.86  5254.3  265.11    5359  265.79
  5542.5  269.59  5564.2  271.28  5601.8  271.31  5623.5  273.03  5653.8   273.8
  5666.8   275.9  5682.8  275.03  5763.7  277.45  5850.4   283.7  5917.7  286.43
#Mann= 8 ,-1 , 0
  4664.4     .07       0    4817     .12       0  4925.5      .1       0
  4989.3     .05       0  4993.4      .1       0  5026.6     .12       0
  5120.8     .07       0  5254.3     .05       0
Bank Sta=4989.3,4993.4
XS Rating Curve= 0 ,0
Exp/Cntr=0.3,0.1

Type RM Length L Ch R = 1 ,17004   ,472,472,472
BEGIN DESCRIPTION:
SOUTH DENTON CREEK 22.0
END DESCRIPTION:
XS GIS Cut Line= 3
      2485224.99     13687924.99        2484825.       13687625.
      2484025.01       13687525.
#Sta/Elev= 30
  4503.5  275.91  4606.9  271.44  4696.2  268.39  4703.5  268.75  4727.4  267.43
  4845.7  263.17    4867  262.52  4996.2  263.27  5000.4  260.81  5011.5  260.02
  5011.8  259.52  5015.4  259.52  5015.7  260.02  5023.6  262.73    5025  262.67
  5053.9  261.41    5074  262.69  5114.3  262.84  5121.9  263.87  5144.6  263.81
  5235.3  266.07  5426.8  269.47  5444.4  270.64  5557.8  273.46  5648.5  278.02
  5668.6  278.08  5686.3  280.24  5691.3  279.93  5698.9  280.82  5809.7  285.66
#Mann= 7 ,-1 , 0
  4503.5    .035       0  4606.9     .05       0  4727.4     .07       0
  4845.7      .1       0  5011.5     .05       0  5015.7      .1       0
    5025     .05       0
Bank Sta=5011.5,5015.7
XS Rating Curve= 0 ,0
Exp/Cntr=0.3,0.1

Type RM Length L Ch R = 1 ,16532   ,426,426,426
BEGIN DESCRIPTION:
SOUTH DENTON CREEK 21.0
END DESCRIPTION:
XS GIS Cut Line= 3
        2485375.     13687725.01        2485025.       13687325.
      2484225.02     13686625.02
#Sta/Elev= 30
  4468.2  273.18  4515.2  271.77  4560.7  270.29  4567.4  270.77    4590  269.41
    4660  267.03  4724.2  265.72  4737.3  265.98  4804.8  263.44  4865.4  260.81
  4907.2   262.4  4971.7  261.03  4992.6  262.11  5011.6  261.05  5021.1  261.49
  5025.6  257.66  5025.9  257.16  5029.8  257.66  5035.3  257.67    5042  262.07
  5056.2   261.3  5092.3  261.47  5155.8  263.29  5417.8  267.47  5481.4   269.7
  5516.2  269.64    5545  269.63  5642.8  274.05  5814.5   278.9  6062.7   287.8
#Mann= 11 ,-1 , 0
  4468.2     .07       0  4515.2     .05       0    4590     .07       0
    4660      .1       0  4724.2     .07       0  4804.8      .1       0
  5011.6     .05       0  5025.6     .05       0  5029.8     .05       0
  5516.2    .035       0  5642.8     .05       0
Bank Sta=5025.6,5029.8
XS Rating Curve= 0 ,0
Exp/Cntr=0.3,0.1

Type RM Length L Ch R = 1 ,16106   ,446,446,446
BEGIN DESCRIPTION:
SOUTH DENTON CREEK 20.0
END DESCRIPTION:
XS GIS Cut Line= 3
      2485524.99     13687824.96        2485325.       13687075.
      2484524.97     13686774.99
#Sta/Elev= 30
  4223.9  279.86  4268.1  278.59  4420.5  273.73  4503.3   269.5    4632  265.47
    4725  263.87  4827.7  261.86  4872.2  261.36  4907.6  261.51  4930.4  259.54
  4958.7  257.12  4977.4  258.03  4982.6  256.49  4989.7   259.2  5002.7  260.38
  5009.9  256.35  5013.1  255.92  5013.4  255.42  5017.4  255.92  5065.6  258.57
  5097.7  260.71  5117.6  261.93  5169.6  261.87  5273.6  261.76  5369.3  263.03
  5522.5  266.81  5558.1  266.25  5588.4  268.14  5695.6  270.79  5854.5  276.11
#Mann= 14 ,-1 , 0
  4223.9    .035       0  4268.1     .07       0    4725    .035       0
  4827.7     .07       0  4872.2    .035       0  4930.4     .07       0
  5013.1     .05       0  5017.4     .07       0  5065.6    .035       0
  5097.7     .07       0  5169.6    .035       0  5273.6     .05       0
  5369.3    .035       0  5695.6     .05       0
Bank Sta=5013.1,5017.4
XS Rating Curve= 0 ,0
Exp/Cntr=0.3,0.1

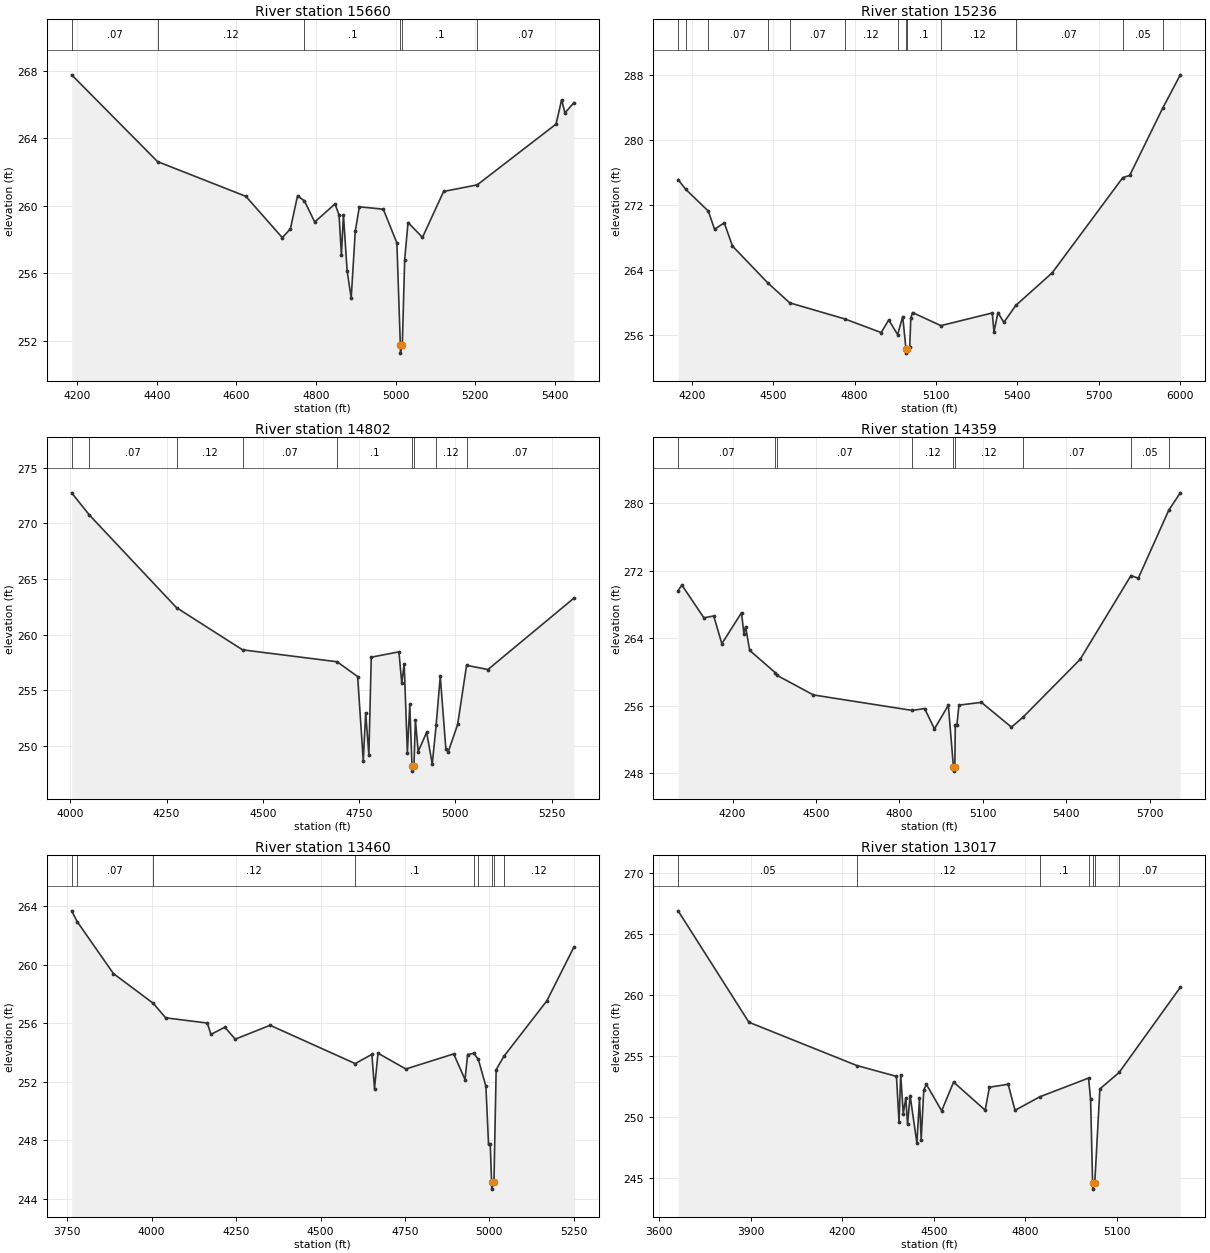
Type RM Length L Ch R = 1 ,15660   ,424,424,424
BEGIN DESCRIPTION:
SOUTH DENTON CREEK 19.0
END DESCRIPTION:
XS GIS Cut Line= 3
        2485725.     13687524.99        2485575.       13686725.
      2485175.04     13686525.02
#Sta/Elev= 30
  4186.4  267.77    4402  262.63  4623.9  260.57  4715.5  258.12  4735.8  258.65
  4753.6   260.6    4771   260.3  4796.8  259.05  4847.7  260.12  4857.9  259.47
  4863.8  257.11  4868.9  259.47  4878.2  256.15  4888.4  254.55  4898.6  258.49
  4908.8  259.95    4969  259.81  5003.1  257.81  5011.8  251.78  5012.2  251.28
  5016.8  251.78  5022.7  256.82  5031.1  259.02  5067.4  258.14  5120.5  260.86
  5204.9  261.25  5402.8  264.85  5416.8  266.29  5425.2  265.52  5447.5  266.11
#Mann= 6 ,-1 , 0
  4186.4     .07       0    4402     .12       0    4771      .1       0
  5011.8     .05       0  5016.8      .1       0  5204.9     .07       0
Bank Sta=5011.8,5016.8
XS Rating Curve= 0 ,0
Exp/Cntr=0.3,0.1

Type RM Length L Ch R = 1 ,15236   ,434,434,434
BEGIN DESCRIPTION:
SOUTH DENTON CREEK 18.0
END DESCRIPTION:
XS GIS Cut Line= 3
      2486575.03     13686825.02        2485825.       13686425.
      2485025.03     13685825.02
#Sta/Elev= 30
  4150.2  275.16  4178.6  273.96  4261.4   271.3  4284.5  269.06  4320.2  269.85
  4350.3     267  4480.7  262.46  4561.5  260.01  4764.6  258.03  4898.2  256.36
  4926.2  257.91  4958.9  256.11  4977.6  258.32  4989.6  254.33  4989.9  253.83
  4994.6  254.33  5003.4  254.56  5007.5  258.18  5013.8  258.82    5118  257.21
  5307.5  258.77  5313.8  256.45  5328.4  258.82  5350.2  257.61    5394  259.69
  5528.4  263.71  5788.5  275.42  5813.8  275.68  5935.1  283.94  6000.2  288.05
#Mann= 13 ,-1 , 0
  4150.2     .05       0  4178.6    .035       0  4261.4     .07       0
  4480.7     .12       0  4561.5     .07       0  4764.6     .12       0
  4958.9      .1       0  4989.6     .05       0  4994.6      .1       0
    5118     .12       0    5394     .07       0  5788.5     .05       0
  5935.1     .07       0
Bank Sta=4989.6,4994.6
XS Rating Curve= 0 ,0
Exp/Cntr=0.3,0.1

Type RM Length L Ch R = 1 ,14802   ,443,443,443
BEGIN DESCRIPTION:
SOUTH DENTON CREEK 17.0
END DESCRIPTION:
XS GIS Cut Line= 3
      2486525.01     13686725.01        2485725.       13686125.
      2485424.95     13686074.99
#Sta/Elev= 30
  4003.6  272.75  4049.8  270.75  4275.9  262.43  4447.5  258.64  4692.8  257.57
  4746.3  256.24  4760.9  248.69  4767.2  252.96  4775.5  249.22  4781.7  257.98
  4853.6  258.46  4860.9  255.64  4867.2  257.39  4875.5  249.39  4881.7  253.75
  4887.5  248.24  4887.9  247.74  4892.6  248.24  4896.3  252.32  4903.6   249.5
  4925.5  251.23  4940.1  248.38  4950.3  251.91  4960.9  256.27  4975.5   249.7
  4981.7  249.48  5006.1  251.94  5029.2  257.25  5084.7  256.87  5307.8  263.28
#Mann= 9 ,-1 , 0
  4003.6    .035       0  4049.8     .07       0  4275.9     .12       0
  4447.5     .07       0  4692.8      .1       0  4887.5     .05       0
  4892.6      .1       0  4950.3     .12       0  5029.2     .07       0
Bank Sta=4887.5,4892.6
XS Rating Curve= 0 ,0
Exp/Cntr=0.3,0.1

Type RM Length L Ch R = 1 ,14359   ,899,899,899
BEGIN DESCRIPTION:
SOUTH DENTON CREEK 16.0
END DESCRIPTION:
XS GIS Cut Line= 3
        2486575.       13686575.        2485975.       13685775.
      2485175.03       13685675.
#Sta/Elev= 30
  4004.4  269.65  4017.9  270.32  4097.1  266.43  4132.5  266.65  4161.7  263.36
  4232.5  267.04  4240.9  264.54  4247.1  265.39  4261.7  262.57  4353.2  259.94
  4359.8  259.61  4490.9  257.28  4846.8  255.44  4890.9  255.67  4926.3  253.25
  4976.3  256.06  4994.6  248.74    4995  248.24  4999.7  248.74  5001.3  253.69
  5006.9  253.69  5014.5  256.07  5095.1   256.4  5203.4  253.46    5244  254.61
  5450.3   261.5  5633.1  271.44  5659.5  271.13  5769.2  279.21  5810.6  281.26
#Mann= 9 ,-1 , 0
  4004.4     .07       0  4353.2     .12       0  4359.8     .07       0
  4846.8     .12       0  4994.6     .05       0  4999.7     .12       0
    5244     .07       0  5633.1     .05       0  5769.2     .07       0
Bank Sta=4994.6,4999.7
XS Rating Curve= 0 ,0
Exp/Cntr=0.3,0.1

Type RM Length L Ch R = 1 ,13460   ,443,443,443
BEGIN DESCRIPTION:
SOUTH DENTON CREEK 15.0
END DESCRIPTION:
XS GIS Cut Line= 3
      2487074.96     13685374.99        2485875.       13685075.
      2485624.99       13685075.
#Sta/Elev= 30
  3763.1  263.69  3779.5  262.95  3886.7   259.4  4004.9  257.36  4041.4  256.37
  4165.1  256.01  4175.4  255.23  4216.6  255.73  4247.5  254.91  4350.6  255.86
  4602.6  253.24  4652.1  253.87  4659.8  251.53  4670.1  253.95  4752.6  252.87
  4894.3   253.9  4927.8  252.15  4935.6  253.86  4953.8  253.94  4967.2  253.53
  4989.7  251.68  4997.4  247.72  5002.5  247.72  5006.5  245.15    5007  244.65
  5013.5  245.15    5020  252.82  5042.7  253.73    5170  257.53    5250   261.2
#Mann= 9 ,-1 , 0
  3763.1     .05       0  3779.5     .07       0  4004.9     .12       0
  4602.6      .1       0  4953.8     .12       0  4967.2     .07       0
  5006.5     .05       0  5013.5     .07       0  5042.7     .12       0
Bank Sta=5006.5,5013.5
XS Rating Curve= 0 ,0
Exp/Cntr=0.3,0.1

Type RM Length L Ch R = 1 ,13017   ,444,444,444
BEGIN DESCRIPTION:
SOUTH DENTON CREEK 14.0
END DESCRIPTION:
XS GIS Cut Line= 3
      2487125.02     13685275.01        2485925.       13684675.
        2485625.       13684725.
#Sta/Elev= 30
  3661.9  266.93  3893.9  257.77  4247.7  254.21  4377.5  253.32  4385.8  249.55
  4391.4  253.45  4399.8  250.26  4408.2  251.56  4413.8  249.38  4422.2  251.74
  4444.5  247.83  4452.9  251.52  4458.5  248.12  4466.9  252.19  4475.3  252.67
  4525.6  250.49  4564.7  252.85  4668.2  250.54  4682.1  252.43  4743.6  252.67
    4766  250.53  4847.2  251.64    5007  253.18  5013.7  251.43  5020.3  244.55
  5020.8  244.05  5027.4  244.55  5044.1  252.29  5107.2  253.64  5307.7  260.64
#Mann= 7 ,-1 , 0
  3661.9     .05       0  4247.7     .12       0  4847.2      .1       0
    5007     .12       0  5020.3     .05       0  5027.4     .12       0
  5107.2     .07       0
Bank Sta=5020.3,5027.4
XS Rating Curve= 0 ,0
Exp/Cntr=0.3,0.1

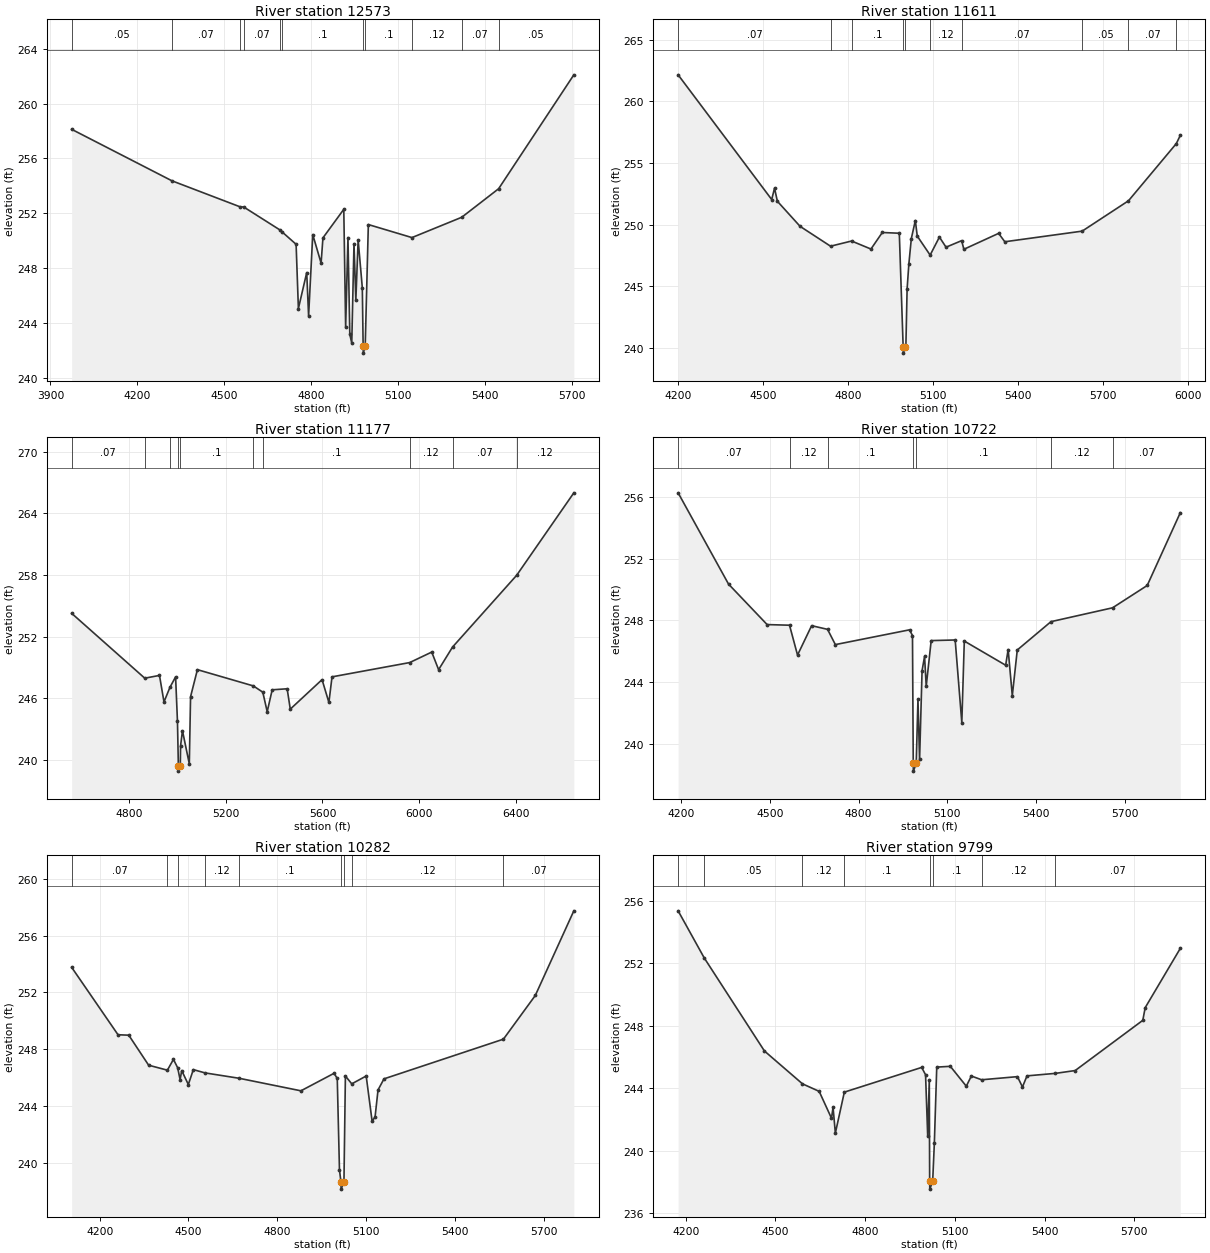
Type RM Length L Ch R = 1 ,12573   ,962,962,962
BEGIN DESCRIPTION:
SOUTH DENTON CREEK 13.0
END DESCRIPTION:
XS GIS Cut Line= 3
      2486975.03     13684975.02        2486175.       13684325.
      2485474.99       13684375.
#Sta/Elev= 30
  3973.1  258.12  4318.8  254.37  4554.3  252.47  4566.7  252.46  4690.7   250.8
  4698.8  250.65  4747.5  249.74  4755.4  245.06  4784.1  247.68  4790.6  244.53
  4804.9  250.45  4833.7  248.37  4840.1  250.21    4912  252.29  4918.4   243.7
  4926.4  250.23  4932.8  243.17  4939.5  242.54  4947.2  249.79  4953.6  245.67
  4961.5  250.07  4975.9  246.58  4978.8  242.31  4979.3  241.81  4985.9  242.31
  4996.7  251.18  5147.2  250.23  5318.9  251.71  5446.2  253.79  5705.7  262.09
#Mann= 11 ,-1 , 0
  3973.1     .05       0  4318.8     .07       0  4554.3     .12       0
  4566.7     .07       0  4690.7     .12       0  4698.8      .1       0
  4978.8     .05       0  4985.9      .1       0  5147.2     .12       0
  5318.9     .07       0  5446.2     .05       0
Bank Sta=4978.8,4985.9
XS Rating Curve= 0 ,0
Exp/Cntr=0.3,0.1

Type RM Length L Ch R = 1 ,11611   ,434,434,434
BEGIN DESCRIPTION:
SOUTH DENTON CREEK 12.0
END DESCRIPTION:
XS GIS Cut Line= 3
      2487175.04       13683725.        2486375.       13683725.
      2485574.97     13684275.02
#Sta/Elev= 30
  4200.6  262.14  4530.6  252.04  4540.6  252.96  4550.6   251.9  4630.6  249.87
  4738.1  248.26  4812.3  248.68  4880.6  248.03  4920.6  249.37  4980.6  249.31
  4994.2   240.1  4994.7   239.6  5002.1   240.1  5003.7   240.1  5008.1  244.79
  5014.2   246.8    5023  248.88  5037.1  250.34  5043.9  249.08  5089.3  247.54
    5122     249  5145.4  248.18  5200.4  248.71  5208.3  248.01  5330.8   249.3
  5352.6  248.62  5625.4  249.48  5788.8  251.94  5957.4  256.57  5971.5  257.24
#Mann= 10 ,-1 , 0
  4200.6     .07       0  4738.1     .12       0  4812.3      .1       0
  4994.2     .05       0  5002.1      .1       0  5089.3     .12       0
  5200.4     .07       0  5625.4     .05       0  5788.8     .07       0
  5957.4     .05       0
Bank Sta=4994.2,5002.1
XS Rating Curve= 0 ,0
Exp/Cntr=0.3,0.1

Type RM Length L Ch R = 1 ,11177   ,455,455,455
BEGIN DESCRIPTION:
SOUTH DENTON CREEK 11.0
END DESCRIPTION:
XS GIS Cut Line= 3
      2486925.03     13683675.01        2486525.       13683525.
      2484924.98     13683124.99
#Sta/Elev= 30
  4562.9  254.27  4865.2  247.96  4926.1  248.23  4944.7  245.65  4969.3  247.07
  4992.7  248.09  5000.4  243.78  5004.2  239.42  5004.7  238.92  5012.1  239.42
  5013.3  241.39  5021.1  242.85  5049.4  239.63  5054.6  246.16  5082.9  248.79
    5314  247.21  5353.3   246.6  5371.5   244.7  5392.1  246.83    5454  246.93
  5466.9  244.95  5598.3  247.82  5626.6   245.6  5639.5  248.09  5960.7  249.48
  6051.8   250.5  6080.2  248.79  6137.9  250.99    6403  257.97  6639.4  265.99
#Mann= 10 ,-1 , 0
  4562.9     .07       0  4865.2     .12       0  4969.3      .1       0
  5004.2     .05       0  5012.1      .1       0    5314     .12       0
  5353.3      .1       0  5960.7     .12       0  6137.9     .07       0
    6403     .12       0
Bank Sta=5004.2,5012.1
XS Rating Curve= 0 ,0
Exp/Cntr=0.3,0.1

Type RM Length L Ch R = 1 ,10722   ,440,440,440
BEGIN DESCRIPTION:
SOUTH DENTON CREEK 10.0
END DESCRIPTION:
XS GIS Cut Line= 3
      2487025.01       13683325.        2486225.       13683275.
        2485425.       13682875.
#Sta/Elev= 30
  4190.6  256.29  4360.9  250.36  4491.2  247.73  4566.8  247.69  4593.9  245.75
  4641.5  247.66  4695.3  247.42  4721.6  246.43  4972.1  247.39  4982.1  247.02
  4984.7  238.71  4985.2  238.21  4994.7  238.71  5000.6  242.87  5006.1  238.97
  5014.5  244.74  5022.9  245.66  5028.5  243.73  5045.3  246.69  5126.3  246.73
  5148.7  241.36  5157.1  246.66  5296.8  245.09  5305.2  246.11  5319.2  243.11
    5336  246.08  5449.8  247.92  5657.8  248.82  5774.8  250.27  5886.6     255
#Mann= 7 ,-1 , 0
  4190.6     .07       0  4566.8     .12       0  4695.3      .1       0
  4984.7     .05       0  4994.7      .1       0  5449.8     .12       0
  5657.8     .07       0
Bank Sta=4984.7,4994.7
XS Rating Curve= 0 ,0
Exp/Cntr=0.3,0.1

Type RM Length L Ch R = 1 ,10282   ,483,483,483
BEGIN DESCRIPTION:
SOUTH DENTON CREEK 9.0
END DESCRIPTION:
XS GIS Cut Line= 3
      2486975.04     13683275.02        2486175.       13682875.
      2485375.03       13682825.
#Sta/Elev= 30
  4105.5  253.77  4262.1  249.03  4298.4     249  4365.5  246.89  4428.8  246.54
  4449.3   247.3  4463.5  246.71  4471.7  245.88  4477.3  246.51  4499.6  245.53
  4516.4  246.58  4555.7  246.35  4671.4  245.97  4879.8  245.09  4991.6  246.32
  5002.5  245.96    5010  239.53    5015  238.68  5015.5  238.18  5025.1  238.68
    5030  246.13  5051.5  245.58  5100.2  246.13  5120.2  242.96  5130.2  243.25
  5140.2  245.15  5160.3  245.93  5563.7  248.72  5671.3  251.79  5801.5  257.74
#Mann= 9 ,-1 , 0
  4105.5     .07       0  4428.8     .12       0  4463.5     .07       0
  4555.7     .12       0  4671.4      .1       0    5015     .05       0
  5025.1      .1       0  5051.5     .12       0  5563.7     .07       0
Bank Sta=5015,5025.1
XS Rating Curve= 0 ,0
Exp/Cntr=0.3,0.1

Type RM Length L Ch R = 1 ,9799    ,436,436,436
BEGIN DESCRIPTION:
SOUTH DENTON CREEK 8.0
END DESCRIPTION:
XS GIS Cut Line= 3
      2487075.02     13682625.01        2486275.       13682425.
      2485475.04     13682724.99
#Sta/Elev= 30
  4174.8  255.34  4262.1  252.33  4463.4  246.38  4590.6  244.28  4646.4   243.8
  4687.6  242.08  4692.8  242.78  4700.5  241.13  4730.5  243.75  4989.1  245.33
  5002.1  244.86  5009.2  240.97  5014.6  244.55  5015.8  238.05  5016.3  237.55
  5025.9  238.05  5031.5   240.5  5039.5  245.35  5084.9   245.4  5138.3  244.13
  5155.2  244.78  5189.5  244.54  5309.2  244.74  5326.1  244.08  5341.2  244.79
  5436.4  244.95  5502.3  245.13  5728.4  248.34  5736.4  249.15  5853.8  252.94
#Mann= 8 ,-1 , 0
  4174.8     .07       0  4262.1     .05       0  4590.6     .12       0
  4730.5      .1       0  5015.8     .05       0  5025.9      .1       0
  5189.5     .12       0  5436.4     .07       0
Bank Sta=5015.8,5025.9
XS Rating Curve= 0 ,0
Exp/Cntr=0.3,0.1