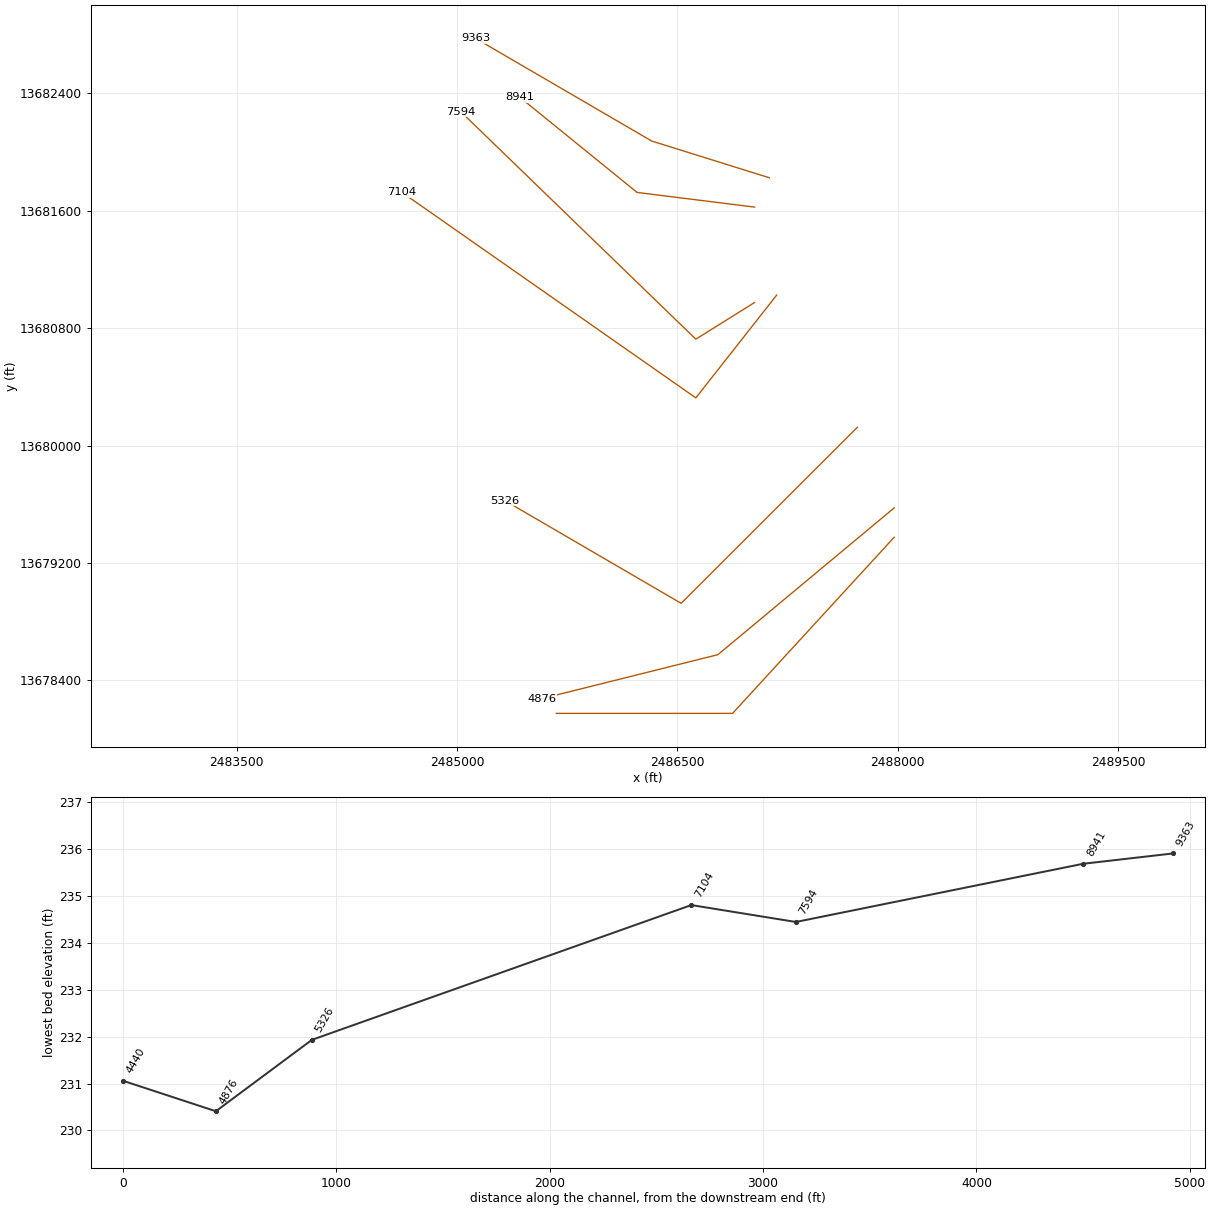
HEC-RAS study SOUTH DENTON CREEK.prj: SOUTH DENTON CREEK Base Level Engineering

--- SOUTH DENTON CREEK.g01 (geometry) --- (continued)

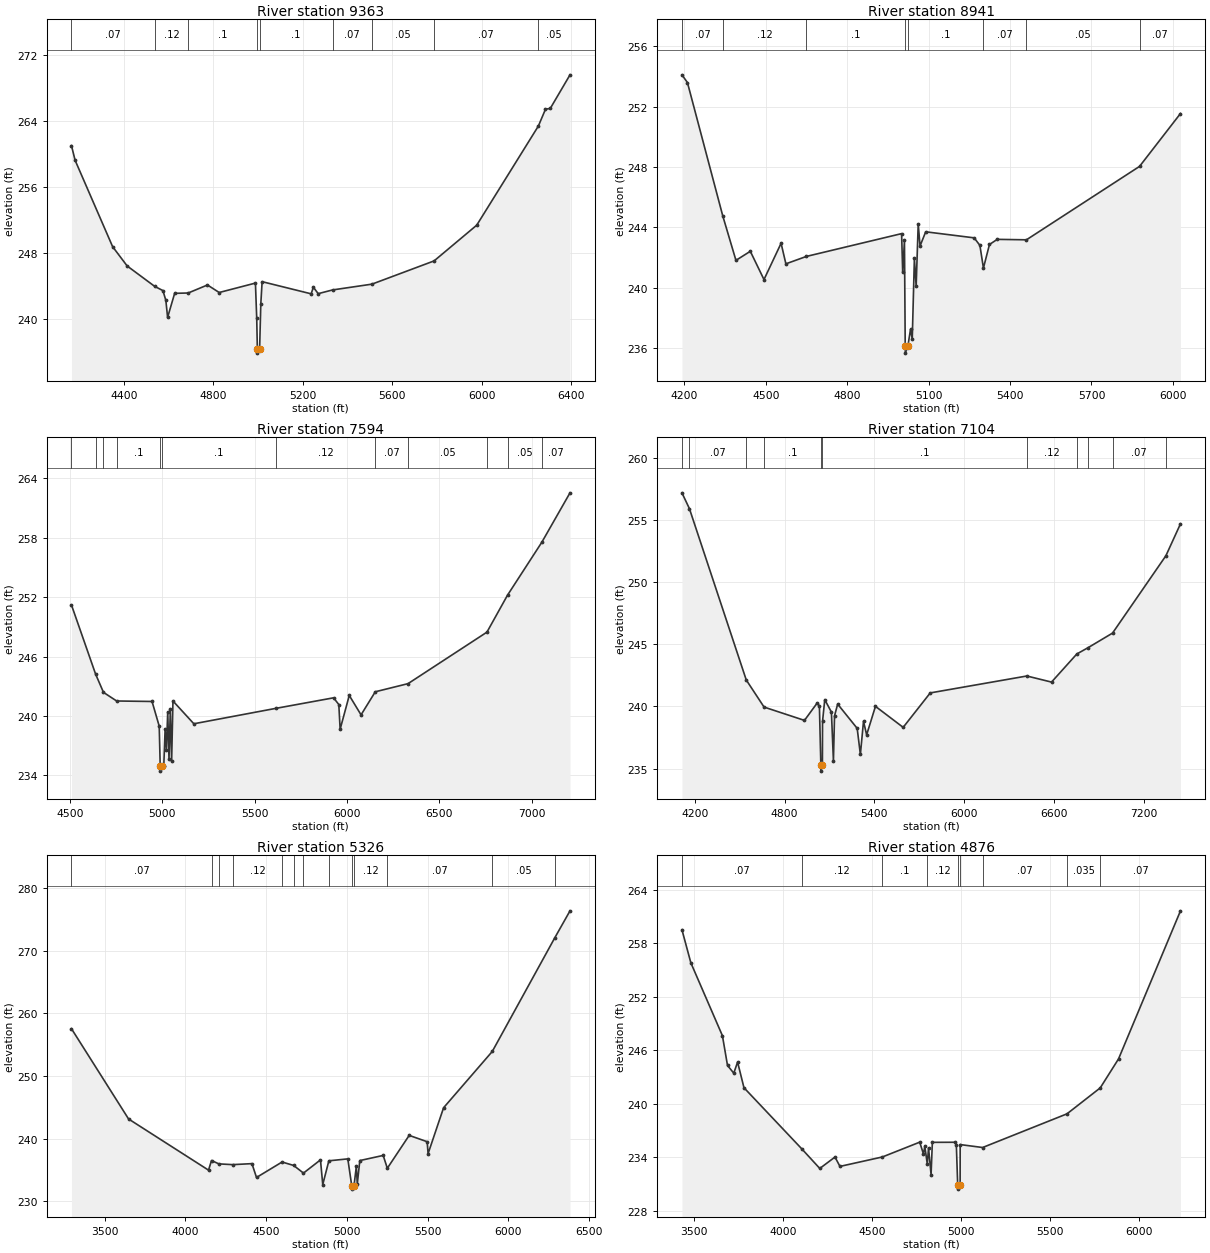
Type RM Length L Ch R = 1 ,9363    ,422,422,422
BEGIN DESCRIPTION:
SOUTH DENTON CREEK 7.0
END DESCRIPTION:
XS GIS Cut Line= 3
      2487124.98     13681825.01        2486325.       13682075.
      2485124.98     13682775.01
#Sta/Elev= 30
  4166.5  260.99  4182.7  259.22  4350.4  248.77  4415.3  246.44  4537.9  243.98
  4575.1  243.46  4588.2  242.28    4596  240.22  4627.5  243.13    4688  243.17
  4774.1  244.14  4826.5  243.23  4988.4  244.37  4994.2   240.1    4997   236.4
  4997.5   235.9  5007.1   236.4  5012.5  241.89  5018.3  244.54  5237.4  243.07
  5247.3  243.87  5268.8  243.09    5333  243.54  5508.9  244.24  5786.6  247.05
  5977.1  251.37  6252.4  263.35  6284.3  265.39  6305.8  265.49  6393.9  269.55
#Mann= 9 ,-1 , 0
  4166.5     .07       0  4537.9     .12       0    4688      .1       0
    4997     .05       0  5007.1      .1       0    5333     .07       0
  5508.9     .05       0  5786.6     .07       0  6252.4     .05       0
Bank Sta=4997,5007.1
XS Rating Curve= 0 ,0
Exp/Cntr=0.3,0.1

Type RM Length L Ch R = 1 ,8941    ,1347,1347,1347
BEGIN DESCRIPTION:
SOUTH DENTON CREEK 6.0
END DESCRIPTION:
XS GIS Cut Line= 3
        2487025.       13681625.        2486225.       13681725.
        2485425.       13682375.
#Sta/Elev= 30
    4191   254.1  4211.2  253.59  4341.3  244.77    4390  241.82  4442.9  242.42
  4493.3  240.55  4556.3  242.95    4574  241.59  4649.5  242.08  5000.4  243.59
  5004.4  241.03  5010.9  243.15  5013.7  236.18  5014.2  235.68  5023.8  236.18
  5033.2  237.25  5039.6  236.61  5047.5  241.95    5054  240.11  5061.6  244.23
  5068.3  242.77  5089.2  243.71  5267.8  243.31  5288.9  242.81  5301.9  241.31
  5324.1  242.87  5352.8  243.21  5460.4  243.18  5877.2  248.04    6028  251.54
#Mann= 8 ,-1 , 0
    4191     .07       0  4341.3     .12       0  4649.5      .1       0
  5013.7     .05       0  5023.8      .1       0  5301.9     .07       0
  5460.4     .05       0  5877.2     .07       0
Bank Sta=5013.7,5023.8
XS Rating Curve= 0 ,0
Exp/Cntr=0.3,0.1

Type RM Length L Ch R = 1 ,7594    ,490,490,490
BEGIN DESCRIPTION:
SOUTH DENTON CREEK 5.0
END DESCRIPTION:
XS GIS Cut Line= 3
      2487024.97     13680974.98        2486625.       13680725.
      2485025.02     13682274.98
#Sta/Elev= 30
  4508.6  251.21  4639.1  244.24  4681.9  242.39  4753.1  241.52  4944.9  241.47
  4983.7  238.98  4989.1  234.94  4989.6  234.44  4999.4  234.94  5008.4  234.96
  5015.6  238.66  5022.6  236.57  5029.8  240.42  5036.7  235.65  5043.9  240.68
  5050.9  235.42  5058.1  241.52  5171.2  239.22  5613.8  240.77  5927.8  241.84
  5956.1  241.16  5963.3  238.67  6012.7  242.08  6076.5  240.12  6153.6  242.45
  6330.9  243.27  6758.2  248.47  6869.5   252.2  7055.2  257.54  7207.9  262.53
#Mann= 12 ,-1 , 0
  4508.6     .07       0  4639.1     .12       0  4681.9     .07       0
  4753.1      .1       0  4989.1     .05       0  4999.4      .1       0
  5613.8     .12       0  6153.6     .07       0  6330.9     .05       0
  6758.2     .07       0  6869.5     .05       0  7055.2     .07       0
Bank Sta=4989.1,4999.4
XS Rating Curve= 0 ,0
Exp/Cntr=0.3,0.1

Type RM Length L Ch R = 1 ,7104    ,1778,1778,1778
BEGIN DESCRIPTION:
SOUTH DENTON CREEK 4.0
END DESCRIPTION:
XS GIS Cut Line= 3
      2487175.01     13681025.01        2486625.       13680325.
      2484625.04     13681724.97
#Sta/Elev= 30
  4113.9  257.18  4163.8  255.91  4543.7  242.13  4662.7  239.95  4932.7  238.88
  5017.7  240.28  5032.5  240.03  5042.1   235.3  5042.6   234.8  5052.5   235.3
  5053.4   238.8  5068.2  240.55  5112.7  239.55  5126.2  235.62  5133.6  239.25
  5154.5  240.19  5284.9  238.24  5306.3  236.14  5327.2  238.81  5348.1  237.72
    5407  240.01  5592.2  238.32  5773.2  241.09  6418.7  242.45  6583.6  241.96
  6752.6  244.22  6829.6  244.74  6991.3   245.9  7347.9  252.12  7445.4  254.69
#Mann= 11 ,-1 , 0
  4113.9     .12       0  4163.8     .07       0  4543.7     .12       0
  4662.7      .1       0  5042.1     .05       0  5052.5      .1       0
  6418.7     .12       0  6752.6     .07       0  6829.6     .12       0
  6991.3     .07       0  7347.9     .05       0
Bank Sta=5042.1,5052.5
XS Rating Curve= 0 ,0
Exp/Cntr=0.3,0.1

Type RM Length L Ch R = 1 ,5326    ,450,450,450
BEGIN DESCRIPTION:
SOUTH DENTON CREEK 3.0
END DESCRIPTION:
XS GIS Cut Line= 3
      2487724.99     13680124.99        2486525.       13678925.
      2485324.98     13679625.01
#Sta/Elev= 30
  3294.9  257.54  3648.4  243.13  4143.4  234.96  4161.9   236.5  4207.3  235.96
  4293.2  235.84  4412.1     236  4440.4  233.79  4598.7  236.26  4670.4  235.71
  4731.1  234.49  4836.4   236.6  4850.5  232.66  4888.3  236.45  5005.6  236.76
  5030.2  232.43  5030.7  231.93  5043.8  232.43  5058.5  235.58  5064.3  232.77
    5080  236.49  5224.7  237.31  5250.2  235.26  5385.6  240.51  5496.8   239.5
  5502.6   237.6  5598.5  244.92    5900  253.91  6286.4  272.03  6381.2  276.36
#Mann= 13 ,-1 , 0
  3294.9     .07       0  4161.9     .12       0  4207.3     .07       0
  4293.2     .12       0  4598.7      .1       0  4670.4     .12       0
  4731.1      .1       0  4888.3     .12       0  5030.2     .05       0
  5043.8     .12       0  5250.2     .07       0    5900     .05       0
  6286.4     .07       0
Bank Sta=5030.2,5043.8
XS Rating Curve= 0 ,0
Exp/Cntr=0.3,0.1

Type RM Length L Ch R = 1 ,4876    ,436,436,436
BEGIN DESCRIPTION:
SOUTH DENTON CREEK 2.0
END DESCRIPTION:
XS GIS Cut Line= 3
      2487975.02     13679575.02        2486775.       13678575.
      2485575.01       13678275.
#Sta/Elev= 30
    3434  259.52  3484.1   255.8  3661.2  247.63  3689.8  244.29    3725  243.42
  3746.4  244.67  3782.2  241.79  4109.1  234.88  4207.9  232.73  4293.2  234.01
  4321.1  232.96  4559.5  234.02  4768.9  235.68  4789.8  234.36  4797.6  235.21
  4811.5  233.22  4818.4  235.05  4832.7  232.05  4839.9  235.66  4968.1  235.67
  4974.6  235.35  4982.1  230.91  4982.6  230.41  4995.8  230.91  4996.1  235.41
  5122.1  235.08  5595.9  238.86  5782.4  241.77  5885.1  245.02    6233  261.64
#Mann= 9 ,-1 , 0
    3434     .07       0  4109.1     .12       0  4559.5      .1       0
  4811.5     .12       0  4982.1     .05       0  4995.8     .12       0
  5122.1     .07       0  5595.9    .035       0  5782.4     .07       0
Bank Sta=4982.1,4995.8
XS Rating Curve= 0 ,0
Exp/Cntr=0.3,0.1

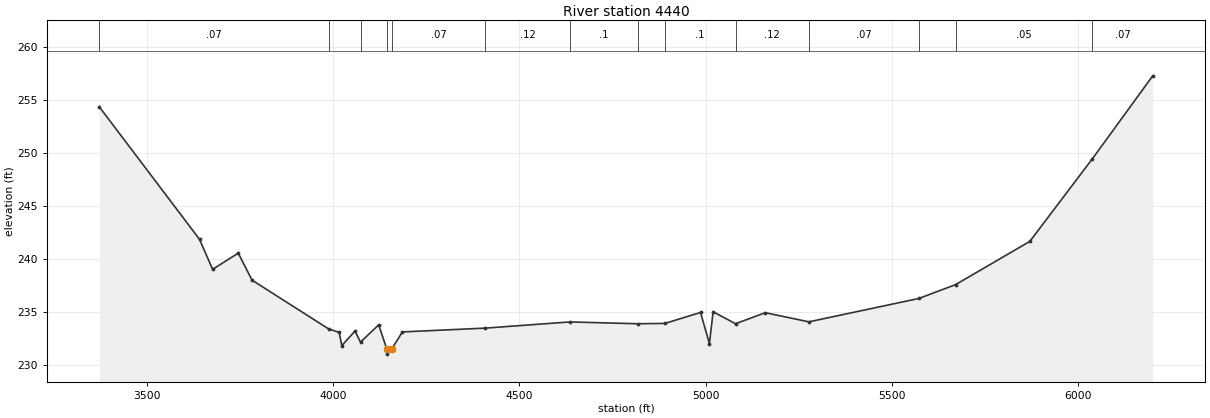
Type RM Length L Ch R = 1 ,4440    ,0,0,0
BEGIN DESCRIPTION:
SOUTH DENTON CREEK 1.0
END DESCRIPTION:
XS GIS Cut Line= 3
      2487975.03     13679375.04        2486875.       13678175.
      2485675.03       13678175.
#Sta/Elev= 30
  3372.2  254.35  3641.4  241.87  3676.6  239.04  3745.3  240.57  3782.6  238.02
  3988.6  233.42  4016.3  233.11  4023.4  231.86  4058.9  233.24  4073.6  232.19
  4122.4  233.82  4143.9  231.56  4144.4  231.06  4157.6  231.56  4186.2  233.15
  4408.7  233.51  4635.4  234.09  4817.2  233.92  4890.4  233.95  4986.3  234.98
  5010.1  232.05  5020.1  235.05  5080.2  233.92  5160.1  234.96    5277   234.1
  5572.3   236.3  5670.7   237.6  5870.1  241.67  6038.3  249.46  6200.1  257.26
#Mann= 14 ,-1 , 0
  3372.2     .07       0  3988.6     .12       0  4073.6     .07       0
  4143.9     .05       0  4157.6     .07       0  4408.7     .12       0
  4635.4      .1       0  4817.2     .12       0  4890.4      .1       0
  5080.2     .12       0    5277     .07       0  5572.3    .035       0
  5670.7     .05       0  6038.3     .07       0
Bank Sta=4143.9,4157.6
XS Rating Curve= 0 ,0
Exp/Cntr=0.3,0.1

Chan Stop Cuts=-1
Use User Specified Reach Order=0
Composite Channel Slope=5