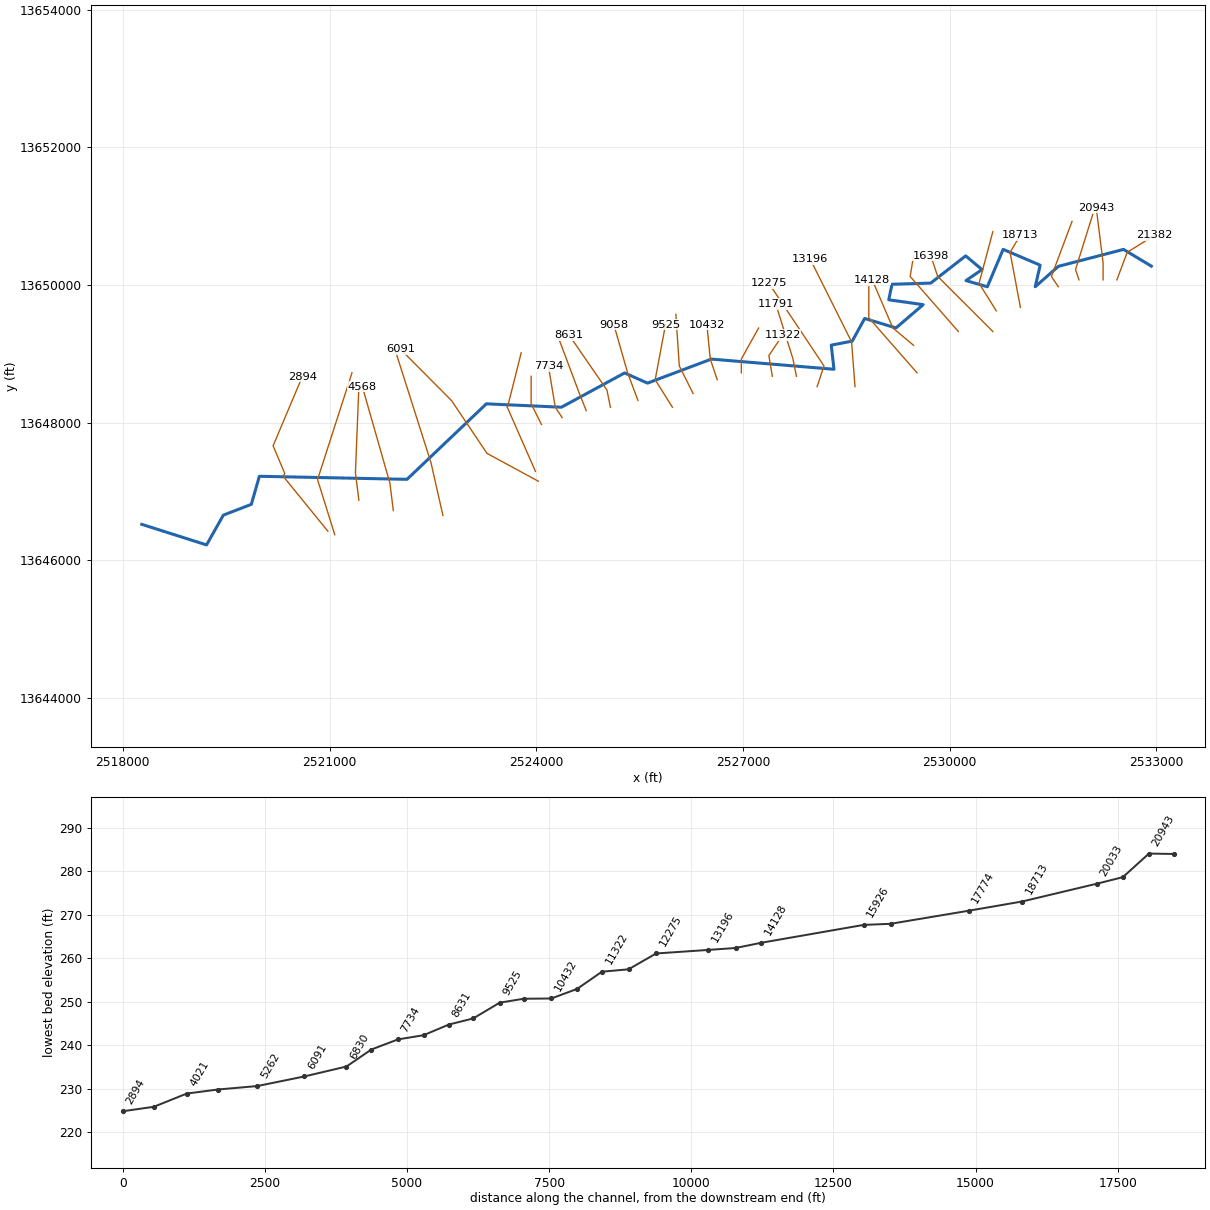
--- SOUTH FORK QUEENS CREEK.prj (project) ---

Proj Title=SOUTH FORK QUEENS CREEK Base Level Engineering
Current Plan=p01
Default Exp/Contr=0.3,0.1
English Units
Geom File=g01
Flow File=f01
Plan File=p01
Y Axis Title=Elevation
X Axis Title(PF)=Main Channel Distance
X Axis Title(XS)=Station
BEGIN DESCRIPTION:
SOUTH FORK QUEENS CREEK
END DESCRIPTION:
DSS Export Rating Curves= 0
DSS Export Rating Curve Sorted= 0
DSS Export Volume Flow Curves= 0
DXF OffsetX= 0
DXF OffsetY= 0
DXF ScaleX= 1
DXF ScaleY= 10

--- SOUTH FORK QUEENS CREEK.p01 (plan) ---

Plan Title=Multiple Run
Short Identifier=Multiple
Geom File=g01
Flow File=f01
Subcritical Flow
K Sum by GR= 0
Std Step Tol= 0.01
Critical Tol= 0.01
Num of Std Step Trials= 20
Max Error Tol= 0.3
Flow Tol Ratio= 0.001
Split Flow NTrial= 30
Split Flow Tol= 0.02
Split Flow Ratio= 0.02
Log Output Level= 0
Friction Slope Method= 1
Unsteady Friction Slope Method= 2
Unsteady Bridges Friction Slope Method= 1
Parabolic Critical Depth
Global Vel Dist=  1 , 1 , 1
Global Log Level= 0
CheckData=True
Encroach Param= -1, 0, 0, 0
BEGIN DESCRIPTION:
Multiple Run
END DESCRIPTION:

--- SOUTH FORK QUEENS CREEK.f01 (steady flow) ---

Flow Title=Multiple
Number of Profiles=7
Profile Names=10-year,25-year,50-year,1pct_min,100-year,1pct_plu,500-year
River Rch & RM= SOUTH FORK QUEEN,Reach-1,21382
     989    1630    2223    1469    2930    5847    5037
River Rch & RM= SOUTH FORK QUEEN,Reach-1,20943
    1163    1909    2595    1705    3402    6787    5787
River Rch & RM= SOUTH FORK QUEEN,Reach-1,12275
    1397    2303    3140    2067    4124    8228    7045
River Rch & RM= SOUTH FORK QUEEN,Reach-1,9058
    1441    2386    3260    2151    4292    8563    7366
River Rch & RM= SOUTH FORK QUEEN,Reach-1,6091
    4023    6979    9843    6685   13339   26614   24268
River Rch & RM= SOUTH FORK QUEEN,Reach-1,654
    4203    7300   10306    7005   13976   27886   25467
Boundary for River Rch & Prof#=SOUTH FORK QUEEN,Reach-1,1
Up Type=0
Dn Type=3
Dn Slope=0.005
Boundary for River Rch & Prof#=SOUTH FORK QUEEN,Reach-1,2
Up Type=0
Dn Type=3
Dn Slope=0.005
Boundary for River Rch & Prof#=SOUTH FORK QUEEN,Reach-1,3
Up Type=0
Dn Type=3
Dn Slope=0.005
Boundary for River Rch & Prof#=SOUTH FORK QUEEN,Reach-1,4
Up Type=0
Dn Type=3
Dn Slope=0.005
Boundary for River Rch & Prof#=SOUTH FORK QUEEN,Reach-1,5
Up Type=0
Dn Type=3
Dn Slope=0.005
Boundary for River Rch & Prof#=SOUTH FORK QUEEN,Reach-1,6
Up Type=0
Dn Type=3
Dn Slope=0.005
Boundary for River Rch & Prof#=SOUTH FORK QUEEN,Reach-1,7
Up Type=0
Dn Type=3
Dn Slope=0.005

--- SOUTH FORK QUEENS CREEK.g01 (geometry) ---

Geom Title=Existing Conditions

River Reach=SOUTH FORK QUEEN,Reach-1
Reach XY= 30
      2532925.00     13650275.00      2532521.67     13650517.40
      2531576.25     13650271.55      2531239.94     13649975.24
      2531312.02     13650288.71      2530774.67     13650517.82
      2530545.29     13649974.61      2530235.79     13650064.63
      2530468.03     13650224.76      2530231.05     13650423.41
      2529723.36     13650028.14      2529161.76     13650011.39
      2529114.56     13649785.93      2529614.06     13649714.98
      2529219.35     13649376.96      2528764.95     13649514.41
      2528584.68     13649185.19      2528280.08     13649127.31
      2528319.32     13648776.87      2526540.22     13648924.48
      2525614.31     13648575.77      2525281.12     13648723.24
      2524364.71     13648225.97      2523275.00     13648275.00
      2522123.50     13647178.62      2519980.84     13647222.95
      2519864.25     13646815.32      2519457.94     13646658.52
      2519214.59     13646225.95      2518275.00     13646525.00

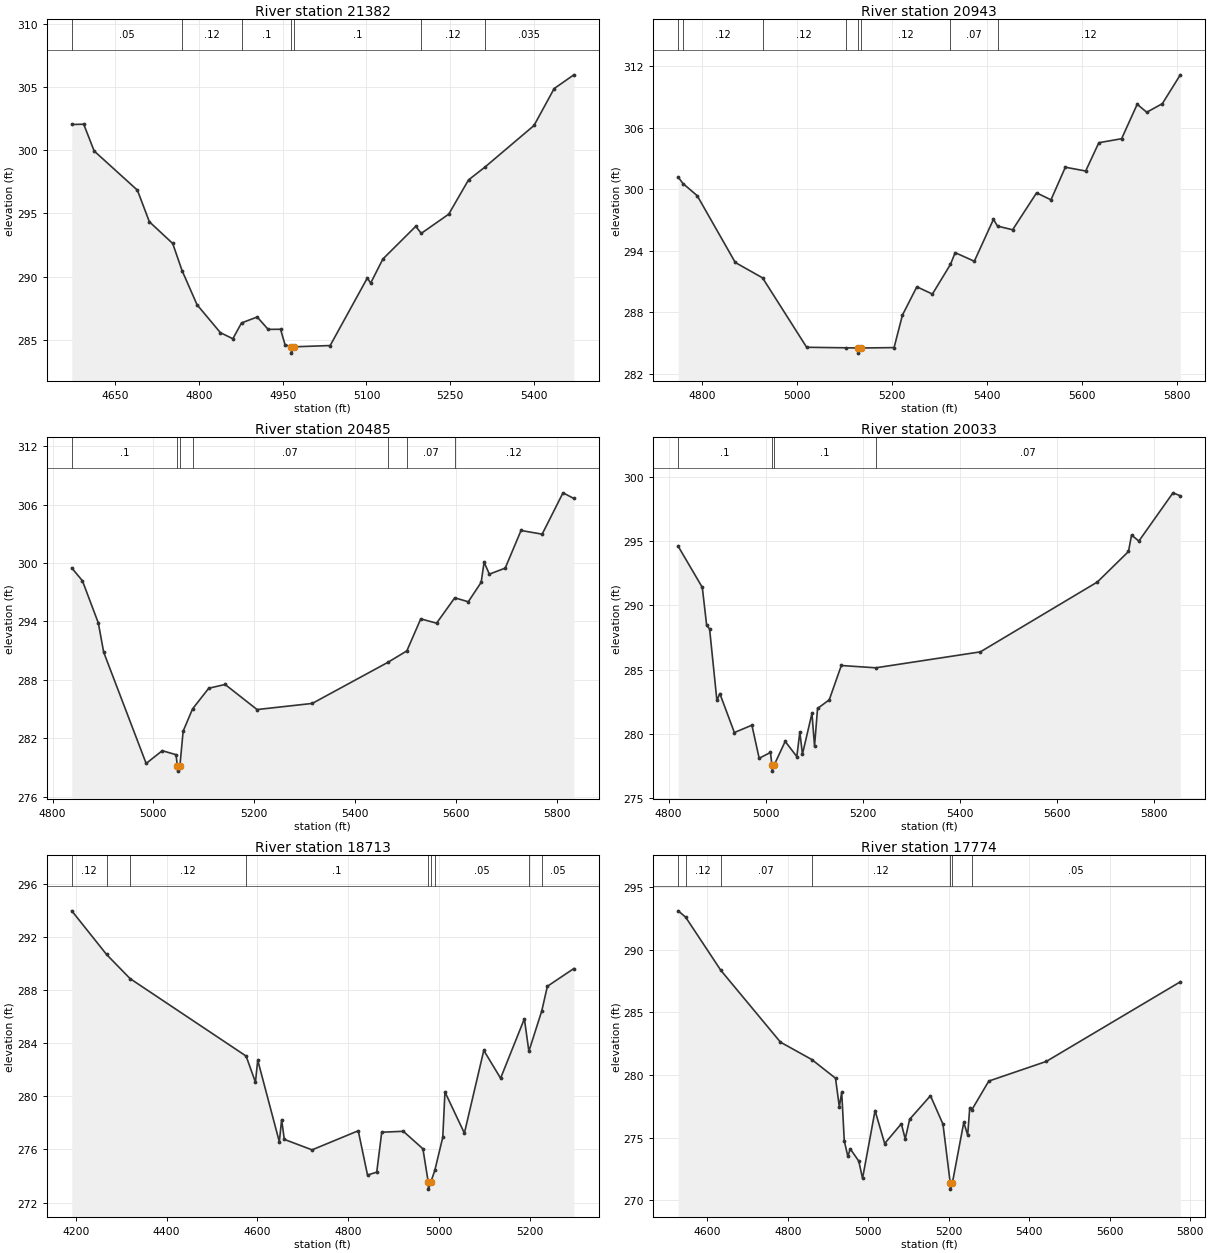
Type RM Length L Ch R = 1,21382,439,439,439
BEGIN DESCRIPTION:
SOUTH FORK QUEENS CREEK 29.0
END DESCRIPTION:
XS GIS Cut Line= 3
      2532424.99     13650074.97      2532575.00     13650475.00
      2532974.97     13650724.98
#Sta/Elev= 30
  4572.4  302.04  4593.8  302.06  4612.5  299.94  4689.9  296.84  4711.3  294.34
  4753.1  292.62  4769.9  290.47  4796.7  287.77  4838.5  285.56  4860.8  285.08
  4876.3  286.33  4904.4  286.80  4924.0  285.82  4946.2  285.83  4954.2  284.61
  4965.4  284.44  4965.7  283.94  4969.8  284.44  5035.0  284.54  5101.6  289.89
  5107.5  289.48  5129.4  291.39  5188.3  293.98  5198.1  293.42  5247.3  294.94
  5282.7  297.65  5312.2  298.67  5400.0  301.96  5436.0  304.88  5471.3  305.97
#Mann=7,-1,0
  4572.4    0.05       0  4769.9    0.12       0  4876.3     0.1       0
  4965.4    0.05       0  4969.8     0.1       0  5198.1    0.12       0
  5312.2   0.035       0
Bank Sta=4965.4,4969.8
Exp/Cntr=0.3,0.1

Type RM Length L Ch R = 1,20943,458,458,458
BEGIN DESCRIPTION:
SOUTH FORK QUEENS CREEK 28.0
END DESCRIPTION:
XS GIS Cut Line= 3
      2532225.00     13650074.97      2532225.00     13650325.00
      2532124.99     13651125.04
#Sta/Elev= 30
  4750.4  301.19  4760.4  300.57  4790.4  299.38  4870.4  292.87  4927.8  291.37
  5020.6  284.60  5103.5  284.55  5129.0  284.53  5129.3  284.03  5133.9  284.53
  5204.5  284.57  5222.1  287.74  5252.4  290.50  5285.1  289.79  5323.2  292.69
  5333.0  293.83  5373.3  292.99  5413.6  297.08  5422.1  296.42  5453.9  296.06
  5504.3  299.66  5534.6  298.98  5564.8  302.16  5607.6  301.79  5635.3  304.55
  5683.2  304.94  5716.0  308.30  5736.1  307.52  5768.9  308.36  5806.7  311.17
#Mann=8,-1,0
  4750.4    0.05       0  4760.4    0.12       0  4927.8    0.12       0
  5103.5    0.12       0  5129.0    0.05       0  5133.9    0.12       0
  5323.2    0.07       0  5422.1    0.12       0
Bank Sta=5129,5133.9
Exp/Cntr=0.3,0.1

Type RM Length L Ch R = 1,20485,452,452,452
BEGIN DESCRIPTION:
SOUTH FORK QUEENS CREEK 27.0
END DESCRIPTION:
XS GIS Cut Line= 3
      2531875.01     13650074.98      2531825.00     13650225.00
      2532075.00     13651025.01
#Sta/Elev= 30
  4838.0  299.50  4859.1  298.18  4890.7  293.84  4901.3  290.84  4985.6  279.40
  5017.6  280.71  5044.9  280.30  5047.6  279.11  5048.0  278.61  5052.5  279.11
  5059.0  282.72  5077.7  285.01  5109.8  287.13  5142.3  287.52  5205.7  284.94
  5315.2  285.57  5465.5  289.80  5502.9  290.97  5530.5  294.26  5561.9  293.82
  5598.0  296.43  5624.8  296.02  5650.4  298.02  5656.2  300.09  5666.7  298.86
  5698.1  299.48  5729.5  303.35  5771.4  302.97  5812.8  307.22  5834.3  306.64
#Mann=7,-1,0
  4838.0     0.1       0  5047.6    0.05       0  5052.5     0.1       0
  5077.7    0.07       0  5465.5    0.12       0  5502.9    0.07       0
  5598.0    0.12       0
Bank Sta=5047.6,5052.5
Exp/Cntr=0.3,0.1

Type RM Length L Ch R = 1,20033,1320,1320,1320
BEGIN DESCRIPTION:
SOUTH FORK QUEENS CREEK 26.0
END DESCRIPTION:
XS GIS Cut Line= 3
      2531575.03     13649974.96      2531475.00     13650125.00
      2531774.99     13650924.98
#Sta/Elev= 30
  4819.9  294.59  4869.5  291.40  4878.5  288.44  4884.5  288.18  4899.6  282.61
  4905.6  283.15  4935.6  280.12  4971.7  280.69  4986.7  278.12  5010.0  278.57
  5012.9  277.62  5013.3  277.12  5017.9  277.62  5040.3  279.43  5064.3  278.25
  5070.5  280.16  5075.9  278.44  5095.5  281.61  5100.8  279.06  5107.0  281.99
  5131.1  282.66  5156.0  285.33  5227.0  285.15  5442.6  286.39  5683.7  291.82
  5747.8  294.19  5754.1  295.47  5769.2  295.00  5839.5  298.75  5854.6  298.52
#Mann=4,-1,0
  4819.9     0.1       0  5012.9    0.05       0  5017.9     0.1       0
  5227.0    0.07       0
Bank Sta=5012.9,5017.9
Exp/Cntr=0.3,0.1

Type RM Length L Ch R = 1,18713,939,939,939
BEGIN DESCRIPTION:
SOUTH FORK QUEENS CREEK 25.0
END DESCRIPTION:
XS GIS Cut Line= 3
      2531025.00     13649675.00      2530875.00     13650475.00
      2531025.00     13650725.01
#Sta/Elev= 30
  4191.3  293.99  4267.9  290.70  4319.7  288.88  4575.2  283.04  4595.7  281.07
  4600.8  282.73  4648.3  276.58  4653.4  278.25  4659.3  276.76  4720.4  275.97
  4822.1  277.41  4842.5  274.07  4862.8  274.29  4873.8  277.30  4921.3  277.37
  4964.5  276.05  4976.3  273.51  4976.7  273.01  4981.6  273.51  4990.7  274.43
  5008.2  276.92  5013.0  280.33  5055.8  277.23  5098.5  283.47  5135.5  281.37
  5187.9  285.85  5197.8  283.40  5226.2  286.45  5238.5  288.30  5296.8  289.64
#Mann=9,-1,0
  4191.3    0.12       0  4267.9    0.07       0  4319.7    0.12       0
  4575.2     0.1       0  4976.3    0.05       0  4981.6     0.1       0
  4990.7    0.05       0  5197.8    0.07       0  5226.2    0.05       0
Bank Sta=4976.3,4981.6
Exp/Cntr=0.3,0.1

Type RM Length L Ch R = 1,17774,1376,1376,1376
BEGIN DESCRIPTION:
SOUTH FORK QUEENS CREEK 24.0
END DESCRIPTION:
XS GIS Cut Line= 3
      2530675.00     13649625.00      2530425.00     13650025.00
      2530625.00     13650774.99
#Sta/Elev= 30
  4527.9  293.12  4546.4  292.61  4633.7  288.37  4782.0  282.63  4859.9  281.24
  4918.8  279.75  4928.3  277.46  4934.2  278.63  4940.6  274.75  4949.5  273.50
  4955.4  274.11  4976.6  273.13  4986.0  271.75  5017.1  277.16  5041.0  274.53
  5082.4  276.11  5092.1  274.90  5103.1  276.47  5154.8  278.35  5185.9  276.08
  5203.9  271.39  5204.3  270.89  5209.3  271.39  5237.6  276.22  5247.3  275.21
  5252.5  277.40  5258.1  277.25  5299.7  279.52  5442.7  281.09  5775.8  287.45
#Mann=7,-1,0
  4527.9    0.07       0  4546.4    0.12       0  4633.7    0.07       0
  4859.9    0.12       0  5203.9    0.05       0  5209.3    0.12       0
  5258.1    0.05       0
Bank Sta=5203.9,5209.3
Exp/Cntr=0.3,0.1

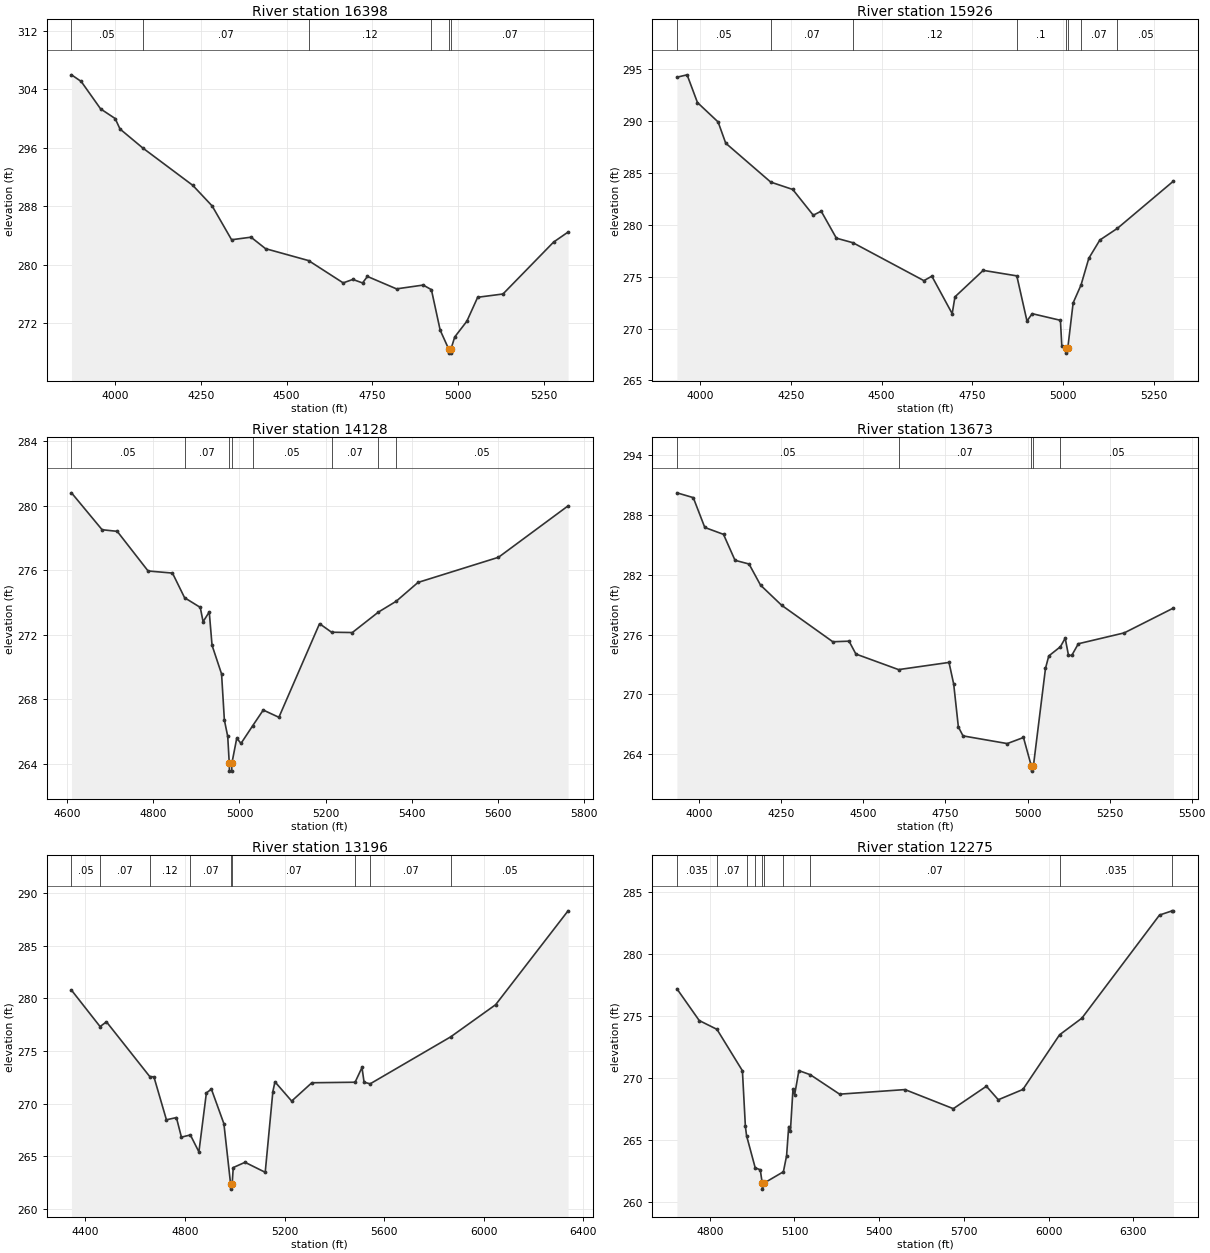
Type RM Length L Ch R = 1,16398,472,472,472
BEGIN DESCRIPTION:
SOUTH FORK QUEENS CREEK 23.0
END DESCRIPTION:
XS GIS Cut Line= 3
      2530625.01     13649324.99      2529825.00     13650125.00
      2529725.00     13650424.99
#Sta/Elev= 30
  3873.0  305.95  3901.3  305.04  3957.9  301.29  4000.3  299.97  4014.4  298.54
  4080.6  295.95  4226.6  290.83  4283.1  288.01  4339.7  283.39  4396.3  283.74
  4438.7  282.17  4564.1  280.54  4665.0  277.49  4693.3  277.96  4721.5  277.48
  4735.7  278.37  4820.5  276.67  4898.3  277.19  4922.2  276.56  4947.8  271.02
  4973.2  268.38  4973.7  267.88  4978.4  267.88  4978.9  268.38  4990.2  270.09
  5025.5  272.24  5057.1  275.52  5130.9  275.97  5278.4  283.07  5320.6  284.44
#Mann=6,-1,0
  3873.0    0.05       0  4080.6    0.07       0  4564.1    0.12       0
  4922.2    0.07       0  4973.2    0.05       0  4978.9    0.07       0
Bank Sta=4973.2,4978.9
Exp/Cntr=0.3,0.1

Type RM Length L Ch R = 1,15926,1798,1798,1798
BEGIN DESCRIPTION:
SOUTH FORK QUEENS CREEK 22.0
END DESCRIPTION:
XS GIS Cut Line= 3
      2530125.00     13649325.00      2529425.00     13650125.00
      2529475.01     13650425.04
#Sta/Elev= 30
  3936.5  294.20  3964.5  294.43  3993.0  291.76  4049.9  289.89  4070.8  287.85
  4194.8  284.10  4255.4  283.39  4311.9  280.91  4333.7  281.30  4375.5  278.70
  4421.2  278.26  4616.5  274.61  4638.4  275.04  4694.4  271.43  4702.0  273.05
  4779.8  275.60  4872.3  275.07  4900.3  270.72  4914.6  271.43  4992.4  270.79
  4996.2  268.31  5006.7  268.13  5007.2  267.63  5012.7  268.13  5027.4  272.47
  5049.1  274.19  5070.5  276.76  5100.9  278.52  5149.4  279.65  5303.7  284.20
#Mann=8,-1,0
  3936.5    0.05       0  4194.8    0.07       0  4421.2    0.12       0
  4872.3     0.1       0  5006.7    0.05       0  5012.7     0.1       0
  5049.1    0.07       0  5149.4    0.05       0
Bank Sta=5006.7,5012.7
Exp/Cntr=0.3,0.1

Type RM Length L Ch R = 1,14128,455,455,455
BEGIN DESCRIPTION:
SOUTH FORK QUEENS CREEK 21.0
END DESCRIPTION:
XS GIS Cut Line= 3
      2529475.01     13649124.99      2529175.00     13649375.00
      2528875.00     13650074.99
#Sta/Elev= 30
  4610.3  280.80  4681.3  278.51  4716.4  278.41  4788.0  275.95  4844.6  275.82
  4872.7  274.29  4909.1  273.69  4915.6  272.80  4929.9  273.41  4936.4  271.34
  4958.5  269.56  4965.0  266.70  4972.8  265.68  4976.3  264.03  4976.8  263.53
  4982.0  263.53  4982.5  264.03  4993.7  265.57  5003.6  265.25  5030.8  266.35
  5055.2  267.32  5091.5  266.87  5185.8  272.68  5213.7  272.15  5261.9  272.13
  5322.4  273.40  5363.6  274.07  5414.3  275.24  5601.0  276.80  5762.4  279.99
#Mann=8,-1,0
  4610.3    0.05       0  4872.7    0.07       0  4976.3    0.05       0
  4982.5    0.07       0  5030.8    0.05       0  5213.7    0.07       0
  5322.4     0.1       0  5363.6    0.05       0
Bank Sta=4976.3,4982.5
Exp/Cntr=0.3,0.1

Type RM Length L Ch R = 1,13673,477,477,477
BEGIN DESCRIPTION:
SOUTH FORK QUEENS CREEK 20.0
END DESCRIPTION:
XS GIS Cut Line= 3
      2529524.99     13648725.01      2528825.00     13649525.00
      2528825.00     13649975.00
#Sta/Elev= 30
  3931.7  290.20  3981.5  289.72  4016.6  286.73  4073.6  286.04  4108.7  283.44
  4151.4  283.07  4186.5  280.95  4250.6  278.94  4406.7  275.28  4456.1  275.34
  4477.0  274.05  4607.0  272.49  4760.7  273.21  4775.0  271.04  4789.2  266.75
  4803.4  265.85  4938.2  265.08  4987.6  265.69  5011.6  262.82  5012.1  262.32
  5017.8  262.82  5054.7  272.62  5064.7  273.86  5100.1  274.78  5114.7  275.64
  5124.7  273.93  5134.7  273.91  5154.7  275.08  5294.7  276.17  5444.7  278.66
#Mann=5,-1,0
  3931.7    0.05       0  4607.0    0.07       0  5011.6    0.05       0
  5017.8    0.07       0  5100.1    0.05       0
Bank Sta=5011.6,5017.8
Exp/Cntr=0.3,0.1

Type RM Length L Ch R = 1,13196,921,921,921
BEGIN DESCRIPTION:
SOUTH FORK QUEENS CREEK 19.0
END DESCRIPTION:
XS GIS Cut Line= 3
      2528625.00     13648525.05      2528575.00     13649175.00
      2527975.01     13650374.99
#Sta/Elev= 30
  4344.6  280.79  4459.3  277.33  4485.0  277.78  4658.7  272.58  4675.5  272.55
  4725.7  268.47  4765.8  268.68  4785.9  266.82  4821.8  267.03  4856.1  265.42
  4886.1  271.02  4906.2  271.39  4956.4  268.10  4983.3  262.38  4983.8  261.88
  4989.6  262.38  4994.0  263.93  5041.2  264.43  5122.3  263.48  5153.0  271.15
  5161.4  272.08  5228.5  270.25  5309.5  271.99  5483.1  272.04  5510.8  273.44
  5519.2  272.04  5543.7  271.89  5866.7  276.35  6047.4  279.41  6338.1  288.33
#Mann=9,-1,0
  4344.6    0.05       0  4459.3    0.07       0  4658.7    0.12       0
  4821.8    0.07       0  4983.3    0.05       0  4989.6    0.07       0
  5483.1    0.05       0  5543.7    0.07       0  5866.7    0.05       0
Bank Sta=4983.3,4989.6
Exp/Cntr=0.3,0.1

Type RM Length L Ch R = 1,12275,484,484,484
BEGIN DESCRIPTION:
SOUTH FORK QUEENS CREEK 18.0
END DESCRIPTION:
XS GIS Cut Line= 3
      2528075.00     13648525.01      2528175.00     13648825.00
      2527375.02     13650024.97
#Sta/Elev= 30
  4683.8  277.22  4762.8  274.66  4825.5  273.95  4915.7  270.61  4926.2  266.12
  4930.3  265.38  4961.0  262.78  4978.9  262.62  4985.7  261.56  4986.2  261.06
  4993.3  261.56  5060.8  262.46  5072.1  263.75  5079.6  266.11  5085.6  265.73
  5094.7  269.12  5100.7  268.68  5115.7  270.62  5156.0  270.29  5259.9  268.72
  5491.3  269.09  5662.5  267.55  5779.7  269.36  5821.8  268.27  5908.9  269.10
  6038.8  273.51  6117.7  274.85  6392.7  283.17  6437.6  283.51  6442.2  283.49
#Mann=10,-1,0
  4683.8   0.035       0  4825.5    0.07       0  4930.3    0.12       0
  4961.0    0.07       0  4985.7    0.05       0  4993.3    0.07       0
  5060.8    0.12       0  5156.0    0.07       0  6038.8   0.035       0
  6437.6    0.07       0
Bank Sta=4985.7,4993.3
Exp/Cntr=0.3,0.1

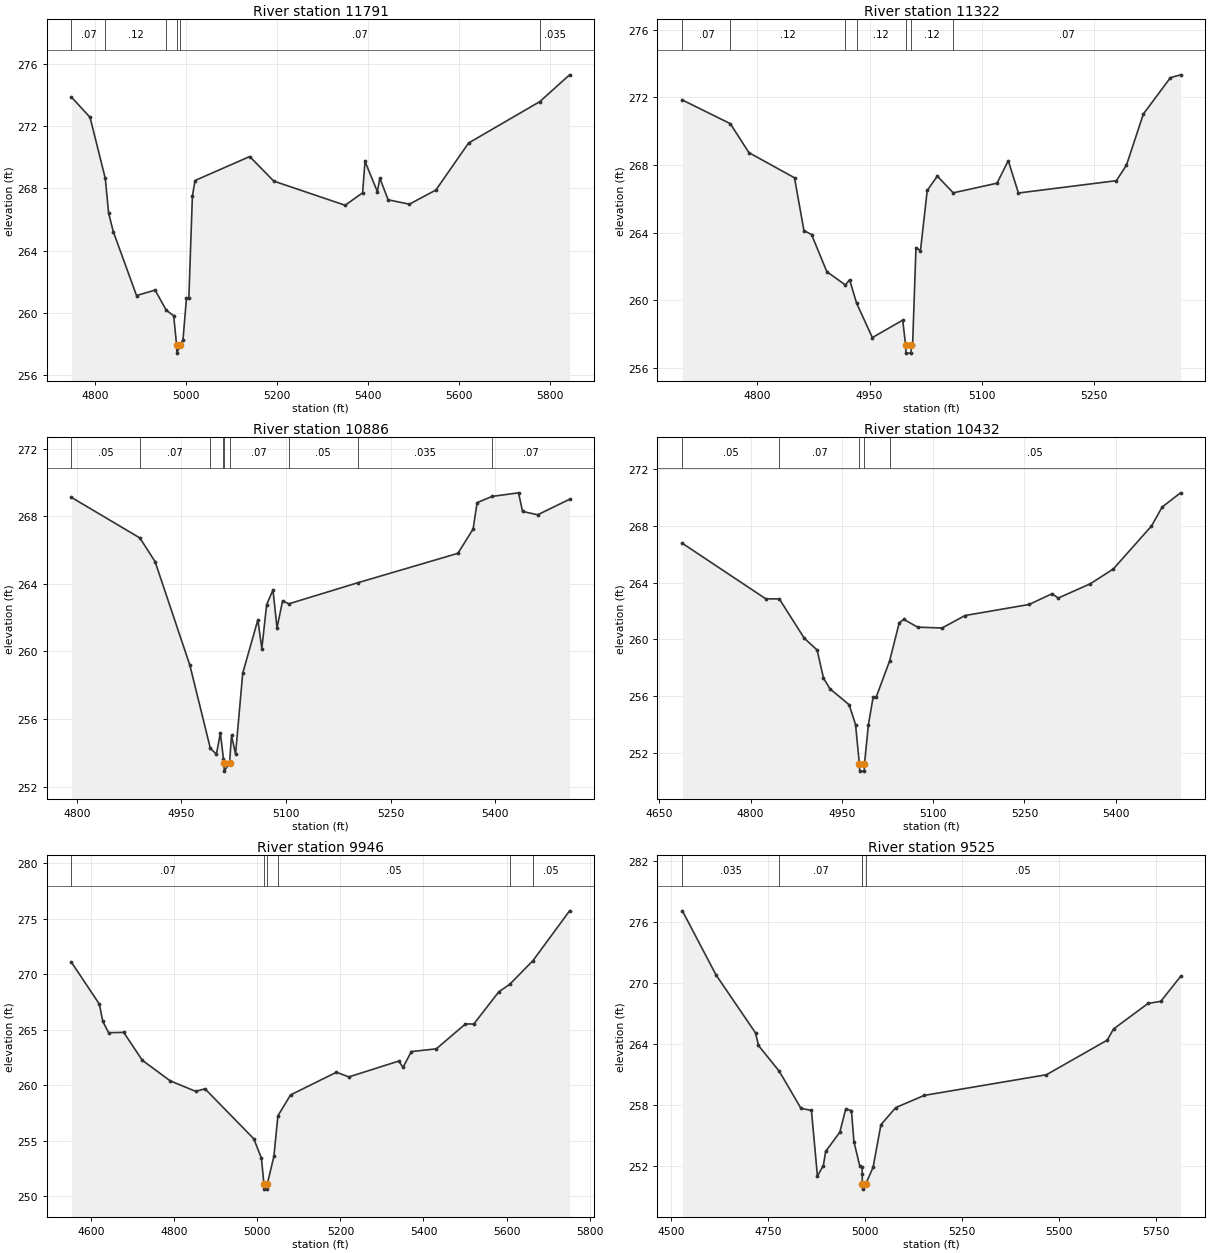
Type RM Length L Ch R = 1,11791,469,469,469
BEGIN DESCRIPTION:
SOUTH FORK QUEENS CREEK 17.0
END DESCRIPTION:
XS GIS Cut Line= 3
      2527775.00     13648674.99      2527725.00     13648925.00
      2527475.01     13649724.98
#Sta/Elev= 30
  4749.0  273.87  4789.8  272.57  4823.3  268.64  4830.6  266.41  4840.8  265.23
  4891.8  261.12  4932.6  261.47  4957.0  260.18  4973.4  259.82  4979.8  257.92
  4980.3  257.42  4987.4  257.92  4993.8  258.28  5001.4  260.95  5006.6  260.95
  5014.4  267.51  5020.2  268.51  5140.2  270.05  5193.1  268.47  5349.7  266.92
  5387.9  267.72  5393.2  269.74  5420.4  267.79  5425.7  268.66  5444.0  267.27
  5490.6  266.99  5548.8  267.90  5620.5  270.92  5776.9  273.58  5842.1  275.30
#Mann=6,-1,0
  4749.0    0.07       0  4823.3    0.12       0  4957.0    0.07       0
  4979.8    0.05       0  4987.4    0.07       0  5776.9   0.035       0
Bank Sta=4979.8,4987.4
Exp/Cntr=0.3,0.1

Type RM Length L Ch R = 1,11322,436,436,436
BEGIN DESCRIPTION:
SOUTH FORK QUEENS CREEK 16.0
END DESCRIPTION:
XS GIS Cut Line= 3
      2527425.01     13648674.97      2527375.00     13648975.00
      2527574.99     13649274.98
#Sta/Elev= 30
  4700.3  271.84  4764.3  270.44  4789.0  268.73  4849.9  267.24  4862.5  264.12
  4872.7  263.88  4893.0  261.69  4917.8  260.90  4923.4  261.21  4932.8  259.82
  4953.8  257.79  4994.3  258.82  4998.1  257.37  4998.6  256.87  5005.3  256.87
  5005.8  257.37  5007.5  257.37  5012.0  263.11  5018.0  262.93  5027.0  266.49
  5040.5  267.34  5061.7  266.35  5120.1  266.92  5135.2  268.25  5148.7  266.34
  5279.4  267.07  5292.9  267.99  5315.4  271.01  5351.5  273.16  5365.0  273.33
#Mann=7,-1,0
  4700.3    0.07       0  4764.3    0.12       0  4917.8    0.07       0
  4932.8    0.12       0  4998.1    0.05       0  5005.8    0.12       0
  5061.7    0.07       0
Bank Sta=4998.1,5005.8
Exp/Cntr=0.3,0.1

Type RM Length L Ch R = 1,10886,454,454,454
BEGIN DESCRIPTION:
SOUTH FORK QUEENS CREEK 15.0
END DESCRIPTION:
XS GIS Cut Line= 3
      2526975.00     13648725.00      2526975.00     13648925.00
      2527225.01     13649375.01
#Sta/Elev= 30
  4792.1  269.11  4890.3  266.71  4912.1  265.31  4962.1  259.17  4991.4  254.26
  5000.1  253.91  5005.8  255.16  5010.2  253.65  5010.9  253.41  5011.4  252.91
  5019.0  253.41  5021.8  255.02  5027.6  253.92  5037.9  258.71  5059.6  261.86
  5065.3  260.16  5072.2  262.76  5081.3  263.63  5087.1  261.39  5095.1  262.99
  5103.9  262.81  5203.1  264.06  5346.7  265.80  5368.5  267.24  5374.2  268.80
  5395.9  269.17  5433.7  269.38  5439.4  268.28  5461.1  268.08  5506.9  269.00
#Mann=9,-1,0
  4792.1    0.05       0  4890.3    0.07       0  4991.4    0.05       0
  5010.2    0.07       0  5010.9    0.05       0  5019.0    0.07       0
  5103.9    0.05       0  5203.1   0.035       0  5395.9    0.07       0
Bank Sta=5010.9,5019
Exp/Cntr=0.3,0.1

Type RM Length L Ch R = 1,10432,486,486,486
BEGIN DESCRIPTION:
SOUTH FORK QUEENS CREEK 14.0
END DESCRIPTION:
XS GIS Cut Line= 3
      2526625.00     13648625.00      2526525.00     13648925.00
      2526475.00     13649424.98
#Sta/Elev= 30
  4687.9  266.77  4824.9  262.86  4847.2  262.85  4888.2  260.08  4909.3  259.25
  4919.8  257.27  4930.3  256.52  4962.0  255.39  4972.5  253.99  4978.8  251.21
  4979.3  250.71  4986.7  250.71  4987.2  251.21  4993.6  253.98  5001.5  255.95
  5006.6  255.95  5028.5  258.48  5044.3  261.17  5051.9  261.41  5074.5  260.86
  5114.7  260.80  5152.4  261.68  5257.9  262.46  5295.6  263.22  5305.6  262.91
  5358.4  263.92  5396.1  264.96  5458.9  267.99  5476.5  269.33  5506.6  270.33
#Mann=5,-1,0
  4687.9    0.05       0  4847.2    0.07       0  4978.8    0.05       0
  4987.2    0.07       0  5028.5    0.05       0
Bank Sta=4978.8,4987.2
Exp/Cntr=0.3,0.1

Type RM Length L Ch R = 1,9946,421,421,421
BEGIN DESCRIPTION:
SOUTH FORK QUEENS CREEK 13.0
END DESCRIPTION:
XS GIS Cut Line= 3
      2526275.02     13648424.96      2526075.00     13648825.00
      2526025.00     13649574.98
#Sta/Elev= 30
  4552.7  271.07  4619.8  267.31  4628.2  265.74  4642.2  264.73  4678.5  264.76
  4723.2  262.25  4790.3  260.40  4851.8  259.45  4874.2  259.68  4991.6  255.18
  5010.0  253.43  5015.8  251.15  5016.3  250.65  5023.8  250.65  5024.3  251.15
  5040.0  253.60  5049.6  257.25  5080.1  259.13  5190.4  261.17  5220.4  260.75
  5340.7  262.18  5350.7  261.61  5370.8  263.03  5430.9  263.28  5501.1  265.52
  5521.1  265.51  5581.2  268.41  5607.1  269.07  5663.6  271.22  5751.6  275.70
#Mann=6,-1,0
  4552.7    0.07       0  5015.8    0.05       0  5024.3    0.07       0
  5049.6    0.05       0  5607.1    0.07       0  5663.6    0.05       0
Bank Sta=5015.8,5024.3
Exp/Cntr=0.3,0.1

Type RM Length L Ch R = 1,9525,467,467,467
BEGIN DESCRIPTION:
SOUTH FORK QUEENS CREEK 12.0
END DESCRIPTION:
XS GIS Cut Line= 3
      2525975.01     13648224.99      2525725.00     13648625.00
      2525874.99     13649424.95
#Sta/Elev= 30
  4528.3  277.09  4615.0  270.80  4717.0  265.10  4724.7  263.86  4778.5  261.32
  4834.3  257.69  4861.4  257.48  4876.8  251.04  4892.1  252.07  4898.0  253.45
  4934.6  255.34  4949.9  257.63  4964.6  257.47  4971.1  254.40  4986.4  251.98
  4992.3  251.89  4992.5  251.23  4992.8  250.25  4993.3  249.75  5001.4  250.25
  5020.4  251.89  5040.7  256.08  5078.9  257.76  5152.6  258.96  5468.0  260.99
  5624.9  264.39  5641.0  265.48  5730.0  267.99  5763.1  268.20  5813.9  270.64
#Mann=5,-1,0
  4528.3   0.035       0  4778.5    0.07       0  4992.5    0.05       0
  4992.8    0.05       0  5001.4    0.05       0
Bank Sta=4992.8,5001.4
Exp/Cntr=0.3,0.1

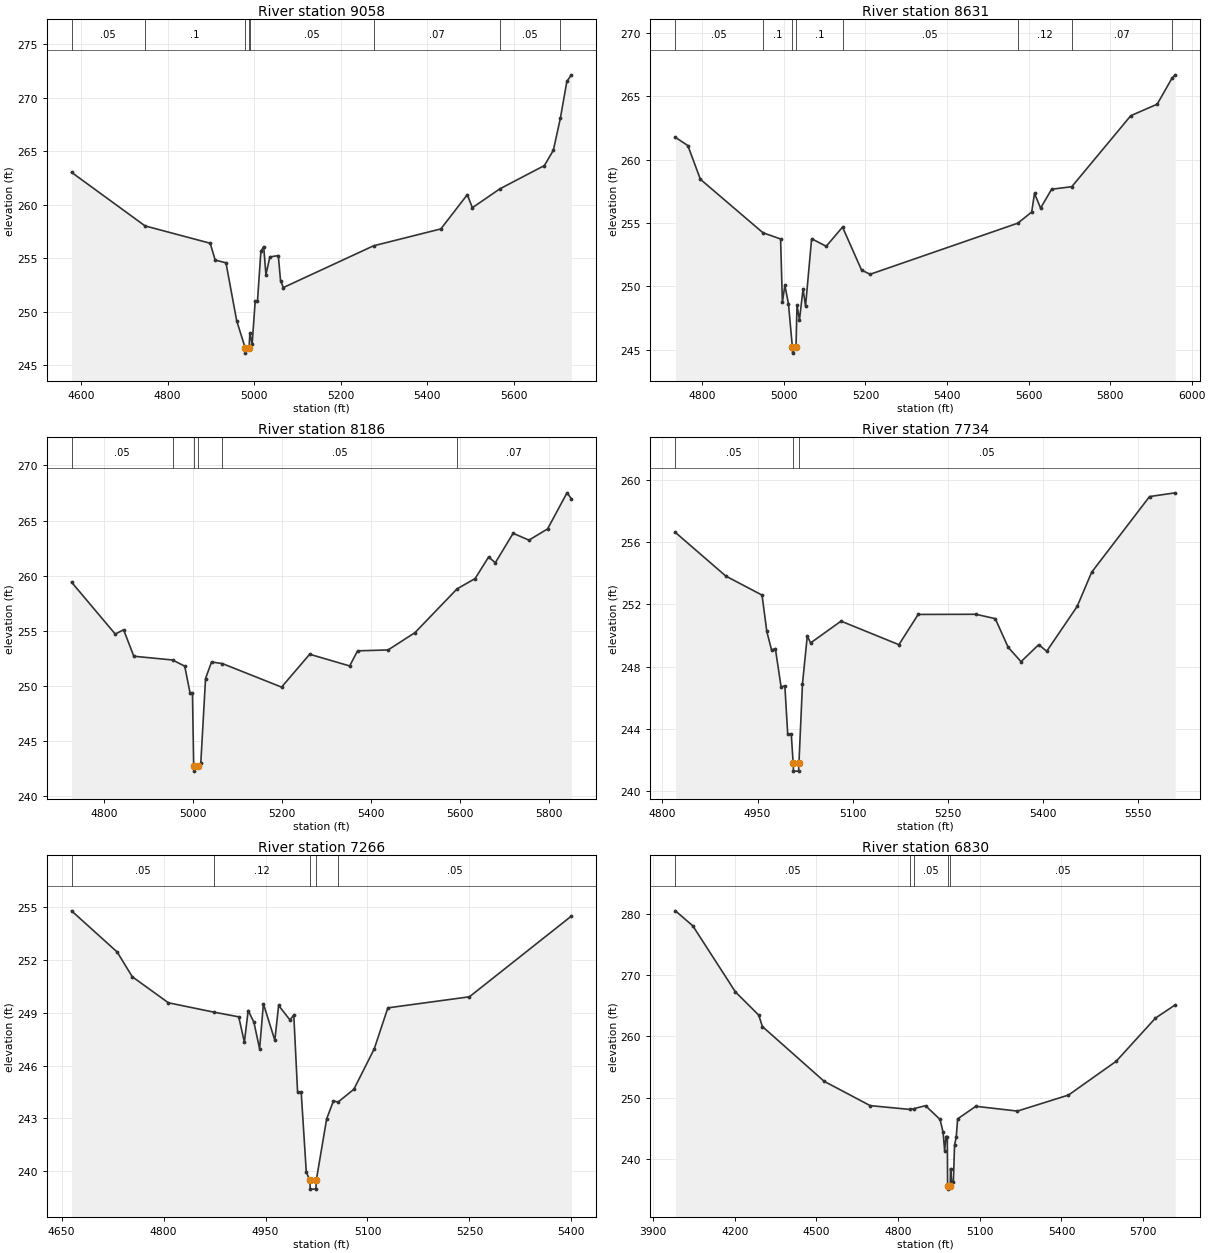
Type RM Length L Ch R = 1,9058,427,427,427
BEGIN DESCRIPTION:
SOUTH FORK QUEENS CREEK 11.0
END DESCRIPTION:
XS GIS Cut Line= 3
      2525475.00     13648325.00      2525325.00     13648725.00
      2525125.00     13649424.99
#Sta/Elev= 30
  4578.0  263.02  4748.0  258.01  4898.4  256.39  4910.0  254.82  4934.9  254.56
  4959.8  249.13  4979.3  246.62  4979.8  246.12  4988.3  246.62  4990.2  248.01
  4995.4  246.93  5002.5  250.99  5007.8  250.99  5015.6  255.62  5022.1  256.08
  5027.3  253.45  5036.4  255.11  5055.9  255.24  5061.1  252.89  5067.6  252.25
  5276.0  256.15  5431.6  257.73  5492.7  260.93  5504.4  259.71  5567.8  261.47
  5670.8  263.65  5691.6  265.08  5707.7  268.05  5722.8  271.51  5733.2  272.13
#Mann=8,-1,0
  4578.0    0.05       0  4748.0     0.1       0  4979.3    0.05       0
  4988.3     0.1       0  4990.2    0.05       0  5276.0    0.07       0
  5567.8    0.05       0  5707.7    0.07       0
Bank Sta=4979.3,4988.3
Exp/Cntr=0.3,0.1

Type RM Length L Ch R = 1,8631,445,445,445
BEGIN DESCRIPTION:
SOUTH FORK QUEENS CREEK 10.0
END DESCRIPTION:
XS GIS Cut Line= 3
      2525075.00     13648225.01      2525025.00     13648475.00
      2524474.98     13649275.03
#Sta/Elev= 30
  4733.9  261.77  4764.5  261.12  4795.1  258.46  4948.7  254.23  4991.9  253.74
  4996.3  248.74  5002.4  250.08  5011.2  248.62  5020.7  245.22  5021.2  244.72
  5029.7  245.22  5032.1  248.50  5038.2  247.35  5047.0  249.80  5053.1  248.44
  5068.0  253.76  5103.8  253.16  5143.8  254.68  5190.5  251.28  5211.4  250.95
  5573.8  254.99  5607.7  255.87  5614.6  257.34  5629.5  256.18  5656.6  257.67
  5706.0  257.87  5850.7  263.48  5915.5  264.39  5951.7  266.44  5959.7  266.71
#Mann=8,-1,0
  4733.9    0.05       0  4948.7     0.1       0  5020.7    0.05       0
  5029.7     0.1       0  5143.8    0.05       0  5573.8    0.12       0
  5706.0    0.07       0  5951.7    0.05       0
Bank Sta=5020.7,5029.7
Exp/Cntr=0.3,0.1

Type RM Length L Ch R = 1,8186,452,452,452
BEGIN DESCRIPTION:
SOUTH FORK QUEENS CREEK 9.0
END DESCRIPTION:
XS GIS Cut Line= 3
      2524725.00     13648174.99      2524625.00     13648425.00
      2524324.99     13649225.03
#Sta/Elev= 30
  4726.8  259.41  4825.1  254.70  4843.9  255.09  4866.8  252.69  4953.9  252.35
  4981.3  251.79  4993.4  249.33  4998.7  249.33  5001.4  242.77  5001.9  242.27
  5010.4  242.77  5017.4  242.99  5028.1  250.67  5041.5  252.17  5066.2  252.02
  5199.0  249.89  5262.2  252.87  5352.1  251.81  5369.9  253.18  5438.4  253.26
  5498.9  254.83  5593.3  258.79  5634.2  259.74  5664.5  261.69  5679.6  261.17
  5719.6  263.84  5755.2  263.22  5797.1  264.24  5840.7  267.51  5850.5  266.98
#Mann=6,-1,0
  4726.8    0.05       0  4953.9     0.1       0  5001.4    0.05       0
  5010.4     0.1       0  5066.2    0.05       0  5593.3    0.07       0
Bank Sta=5001.4,5010.4
Exp/Cntr=0.3,0.1

Type RM Length L Ch R = 1,7734,468,468,468
BEGIN DESCRIPTION:
SOUTH FORK QUEENS CREEK 8.0
END DESCRIPTION:
XS GIS Cut Line= 3
      2524374.98     13648075.04      2524275.00     13648225.00
      2524175.00     13648824.99
#Sta/Elev= 30
  4820.4  256.61  4900.0  253.81  4957.1  252.59  4964.6  250.26  4972.1  249.07
  4978.1  249.16  4987.1  246.71  4993.1  246.76  4997.6  243.67  5003.2  243.67
  5006.2  241.80  5006.7  241.30  5014.8  241.30  5015.3  241.80  5020.9  246.91
  5028.5  249.98  5033.6  249.52  5081.7  250.92  5173.0  249.41  5203.4  251.35
  5294.6  251.36  5325.0  251.08  5345.3  249.25  5365.6  248.32  5393.5  249.41
  5406.2  248.99  5454.3  251.87  5477.1  254.06  5568.4  258.91  5608.9  259.15
#Mann=3,-1,0
  4820.4    0.05       0  5006.2    0.05       0  5015.3    0.05       0
Bank Sta=5006.2,5015.3
Exp/Cntr=0.3,0.1

Type RM Length L Ch R = 1,7266,436,436,436
BEGIN DESCRIPTION:
SOUTH FORK QUEENS CREEK 7.0
END DESCRIPTION:
XS GIS Cut Line= 3
      2524075.00     13647975.00      2523925.00     13648275.00
      2523925.00     13648674.99
#Sta/Elev= 30
  4664.6  254.80  4731.7  252.46  4754.0  251.05  4807.1  249.57  4873.6  249.04
  4910.6  248.77  4918.9  247.33  4924.5  249.13  4932.9  248.47  4941.3  246.95
  4946.9  249.51  4963.7  247.44  4969.3  249.42  4986.0  248.59  4991.6  248.88
  4997.2  244.49  5002.5  244.49  5010.0  239.94  5015.3  239.47  5015.8  238.97
  5024.2  238.97  5024.7  239.47  5040.0  242.97  5050.0  243.99  5056.7  243.92
  5080.0  244.65  5110.0  246.95  5130.0  249.28  5250.0  249.91  5400.0  254.50
#Mann=5,-1,0
  4664.6    0.05       0  4873.6    0.12       0  5015.3    0.05       0
  5024.7    0.12       0  5056.7    0.05       0
Bank Sta=5015.3,5024.7
Exp/Cntr=0.3,0.1

Type RM Length L Ch R = 1,6830,739,739,739
BEGIN DESCRIPTION:
SOUTH FORK QUEENS CREEK 6.0
END DESCRIPTION:
XS GIS Cut Line= 5
      2523987.06     13647294.60      2523586.21     13648209.31
      2523575.00     13648225.00      2523585.91     13648240.28
      2523780.23     13649015.34
#Sta/Elev= 30
  3982.0  280.46  4046.0  278.01  4202.6  267.23  4288.1  263.45  4301.5  261.59
  4528.3  252.66  4697.4  248.69  4845.0  248.06  4859.2  248.21  4900.8  248.68
  4954.1  246.43  4965.1  244.37  4970.9  241.33  4976.0  243.65  4980.7  243.65
  4981.8  235.57  4982.3  235.07  4991.2  235.57  4992.6  238.43  4996.9  236.28
  5003.0  236.28  5007.3  242.25  5013.5  243.54  5018.6  246.53  5085.5  248.58
  5238.1  247.80  5425.7  250.41  5600.9  255.92  5745.3  262.97  5817.8  265.12
#Mann=5,-1,0
  3982.0    0.05       0  4845.0    0.12       0  4859.2    0.05       0
  4981.8    0.05       0  4991.2    0.05       0
Bank Sta=4981.8,4991.2
Exp/Cntr=0.3,0.1

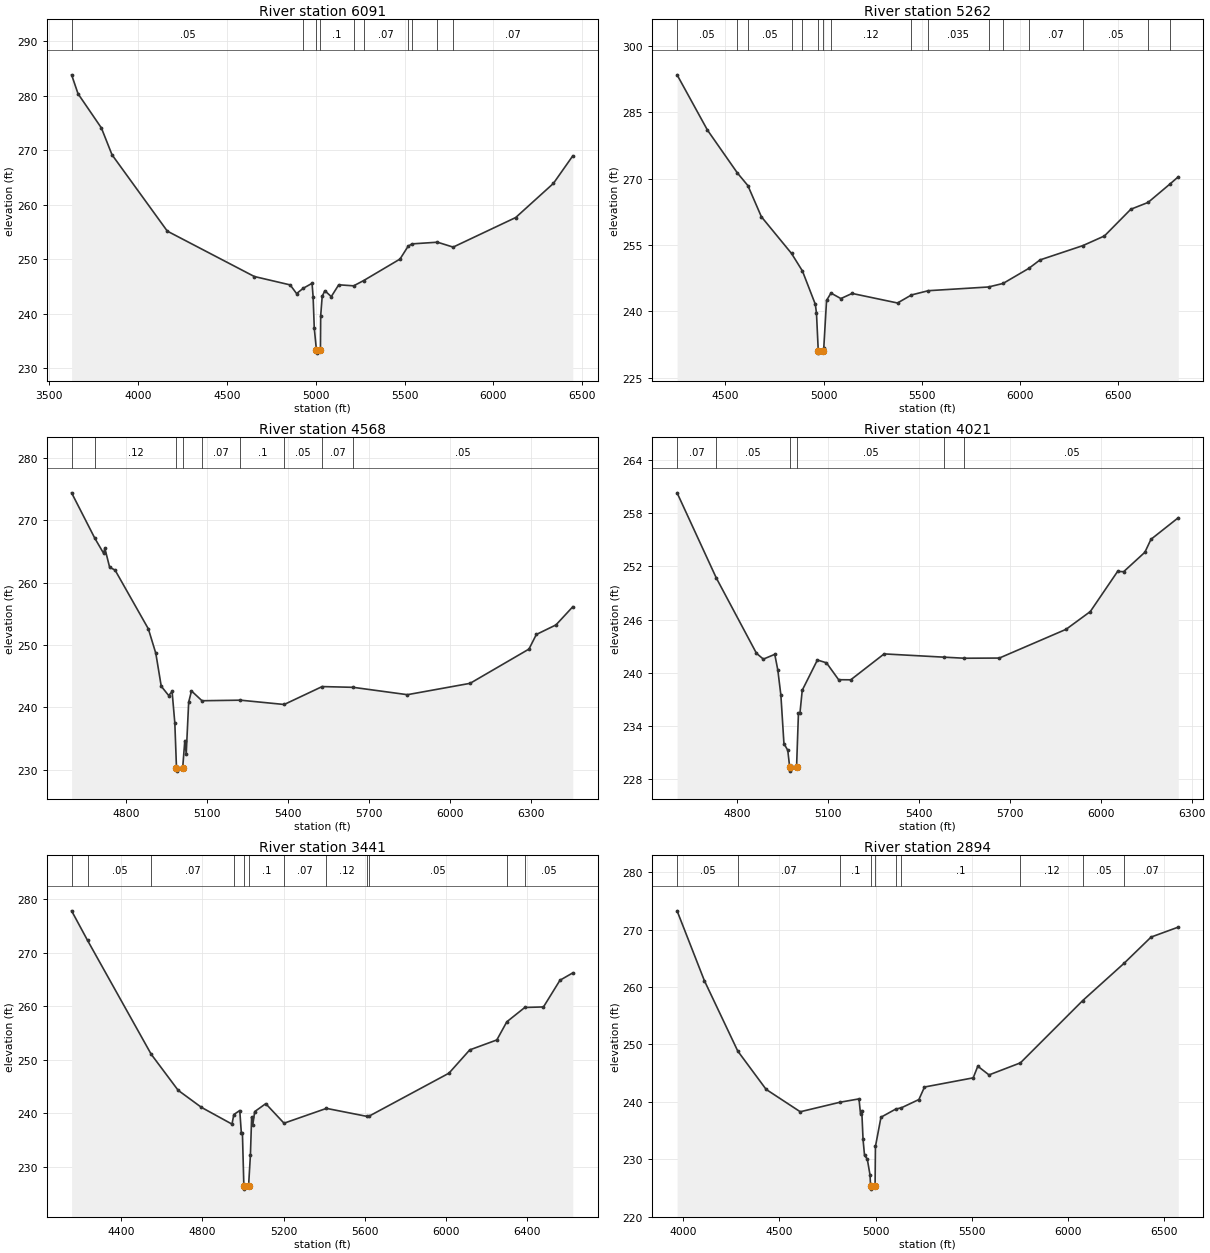
Type RM Length L Ch R = 1,6091,829,829,829
BEGIN DESCRIPTION:
SOUTH FORK QUEENS CREEK 5.3
END DESCRIPTION:
XS GIS Cut Line= 4
      2524029.36     13647151.36      2523284.68     13647555.17
      2522770.74     13648320.84      2522031.31     13649065.51
#Sta/Elev= 30
  3627.2  283.82  3663.4  280.35  3794.6  274.09  3854.5  269.16  4165.5  255.16
  4654.8  246.84  4856.5  245.30  4892.5  243.71  4930.4  244.69  4979.5  245.59
  4985.5  243.14  4992.0  237.37  5004.4  233.29  5004.9  232.79  5026.7  233.29
  5028.1  239.63  5036.6  243.21  5051.5  244.23  5087.6  243.15  5129.6  245.32
  5213.5  245.13  5269.5  246.09  5474.2  250.04  5519.3  252.36  5541.2  252.82
  5684.9  253.13  5773.1  252.23  6124.7  257.65  6336.9  263.91  6445.9  268.96
#Mann=10,-1,0
  3627.2    0.05       0  4930.4     0.1       0  5004.4    0.05       0
  5026.7     0.1       0  5213.5    0.12       0  5269.5    0.07       0
  5519.3    0.12       0  5541.2    0.07       0  5684.9   0.035       0
  5773.1    0.07       0
Bank Sta=5004.4,5026.7
Exp/Cntr=0.3,0.1

Type RM Length L Ch R = 1,5262,694,694,694
BEGIN DESCRIPTION:
SOUTH FORK QUEENS CREEK 5.1
END DESCRIPTION:
XS GIS Cut Line= 3
      2522644.88     13646653.12      2522471.81     13647418.82
      2521937.25     13649101.11
#Sta/Elev= 30
  4254.5  293.52  4408.9  281.03  4561.3  271.33  4614.9  268.46  4683.4  261.43
  4836.9  253.12  4892.3  249.16  4957.9  241.63  4963.8  239.64  4972.9  231.08
  4973.4  230.58  4995.7  231.08  5001.0  231.78  5015.1  242.50  5037.6  244.16
  5088.0  242.92  5145.1  244.08  5376.1  241.92  5447.3  243.74  5533.1  244.70
  5839.2  245.54  5913.2  246.34  6044.1  249.74  6101.3  251.66  6319.0  254.89
  6429.1  257.08  6563.3  263.12  6651.1  264.66  6762.3  268.82  6804.7  270.45
#Mann=16,-1,0
  4254.5    0.05       0  4561.3    0.07       0  4614.9    0.05       0
  4836.9    0.12       0  4892.3     0.1       0  4972.9    0.05       0
  4995.7     0.1       0  5037.6    0.12       0  5447.3    0.07       0
  5533.1   0.035       0  5839.2    0.07       0  5913.2   0.035       0
  6044.1    0.07       0  6319.0    0.05       0  6651.1    0.07       0
  6762.3    0.05       0
Bank Sta=4972.9,4995.7
Exp/Cntr=0.3,0.1

Type RM Length L Ch R = 1,4568,547,547,547
BEGIN DESCRIPTION:
SOUTH FORK QUEENS CREEK 5.0
END DESCRIPTION:
XS GIS Cut Line= 3
      2521925.00     13646725.04      2521875.00     13647125.00
      2521475.00     13648525.00
#Sta/Elev= 30
  4597.0  274.38  4682.9  267.12  4715.4  264.71  4720.4  265.48  4738.1  262.45
  4758.2  262.00  4881.7  252.58  4909.4  248.66  4929.5  243.39  4957.2  241.89
  4969.8  242.55  4979.9  237.49  4986.1  230.28  4986.6  229.78  5009.0  230.28
  5017.0  234.68  5022.2  232.58  5031.3  240.83  5041.7  242.63  5080.7  241.06
  5223.3  241.15  5385.6  240.46  5526.4  243.33  5641.3  243.21  5842.5  242.03
  6075.2  243.85  6293.6  249.34  6320.9  251.68  6393.7  253.21  6456.1  256.12
#Mann=9,-1,0
  4597.0    0.05       0  4682.9    0.12       0  4986.1    0.05       0
  5009.0    0.12       0  5080.7    0.07       0  5223.3     0.1       0
  5385.6    0.05       0  5526.4    0.07       0  5641.3    0.05       0
Bank Sta=4986.1,5009
Exp/Cntr=0.3,0.1

Type RM Length L Ch R = 1,4021,580,580,580
BEGIN DESCRIPTION:
SOUTH FORK QUEENS CREEK 4.0
END DESCRIPTION:
XS GIS Cut Line= 3
      2521424.99     13646875.04      2521375.00     13647275.00
      2521425.00     13648525.03
#Sta/Elev= 30
  4601.8  260.33  4731.1  250.71  4863.8  242.18  4886.5  241.52  4924.2  242.06
  4934.3  240.28  4944.4  237.44  4954.5  231.96  4967.1  231.21  4973.3  229.35
  4973.8  228.85  4996.2  229.35  5002.4  235.43  5007.4  235.43  5014.9  238.00
  5064.9  241.42  5094.9  241.10  5135.0  239.19  5175.0  239.18  5285.1  242.11
  5483.1  241.74  5550.2  241.62  5665.4  241.64  5885.6  244.89  5965.6  246.90
  6055.7  251.44  6075.7  251.41  6145.8  253.61  6165.8  255.07  6255.9  257.51
#Mann=6,-1,0
  4601.8    0.07       0  4731.1    0.05       0  4973.3    0.05       0
  4996.2    0.05       0  5483.1    0.07       0  5550.2    0.05       0
Bank Sta=4973.3,4996.2
Exp/Cntr=0.3,0.1

Type RM Length L Ch R = 1,3441,547,547,547
BEGIN DESCRIPTION:
SOUTH FORK QUEENS CREEK 3.0
END DESCRIPTION:
XS GIS Cut Line= 3
      2521075.00     13646374.99      2520825.00     13647175.00
      2521325.00     13648724.99
#Sta/Elev= 30
  4156.1  277.82  4234.8  272.28  4548.0  251.01  4680.5  244.28  4795.2  241.09
  4945.5  237.96  4954.6  239.75  4983.8  240.50  4991.6  236.27  4996.9  236.27
  5004.0  226.31  5004.5  225.81  5027.0  226.31  5036.3  232.23  5042.3  239.29
  5047.6  237.73  5057.3  240.30  5111.7  241.78  5201.6  238.13  5410.5  240.90
  5611.8  239.39  5619.4  239.43  6013.5  247.48  6115.7  251.83  6249.1  253.69
  6298.2  257.08  6386.7  259.76  6478.7  259.86  6559.9  264.85  6622.9  266.22
#Mann=12,-1,0
  4156.1   0.035       0  4234.8    0.05       0  4548.0    0.07       0
  4954.6     0.1       0  5004.0    0.05       0  5027.0     0.1       0
  5201.6    0.07       0  5410.5    0.12       0  5611.8    0.07       0
  5619.4    0.05       0  6298.2   0.035       0  6386.7    0.05       0
Bank Sta=5004,5027
Exp/Cntr=0.3,0.1

Type RM Length L Ch R = 1,2894,493,493,493
BEGIN DESCRIPTION:
SOUTH FORK QUEENS CREEK 2.0
END DESCRIPTION:
XS GIS Cut Line= 5
      2520975.03     13646424.97      2520325.00     13647225.00
      2520349.73     13647263.65      2520180.05     13647665.30
      2520604.38     13648671.12
#Sta/Elev= 30
  3968.7  273.27  4110.5  261.11  4284.0  248.84  4431.4  242.16  4608.8  238.26
  4816.7  239.93  4914.0  240.50  4922.0  237.91  4928.4  238.47  4935.1  233.44
  4942.8  230.67  4957.1  230.02  4971.5  227.22  4974.2  225.28  4974.7  224.78
  4997.6  225.28  4999.5  232.21  5028.3  237.31  5104.4  238.72  5134.9  238.96
  5225.3  240.39  5254.4  242.57  5507.6  244.17  5531.4  246.20  5589.6  244.68
  5752.8  246.78  6076.8  257.64  6291.2  264.12  6432.0  268.70  6573.1  270.43
#Mann=10,-1,0
  3968.7    0.05       0  4284.0    0.07       0  4816.7     0.1       0
  4974.2    0.05       0  4997.6     0.1       0  5104.4    0.12       0
  5134.9     0.1       0  5752.8    0.12       0  6076.8    0.05       0
  6291.2    0.07       0
Bank Sta=4974.2,4997.6
Exp/Cntr=0.3,0.1