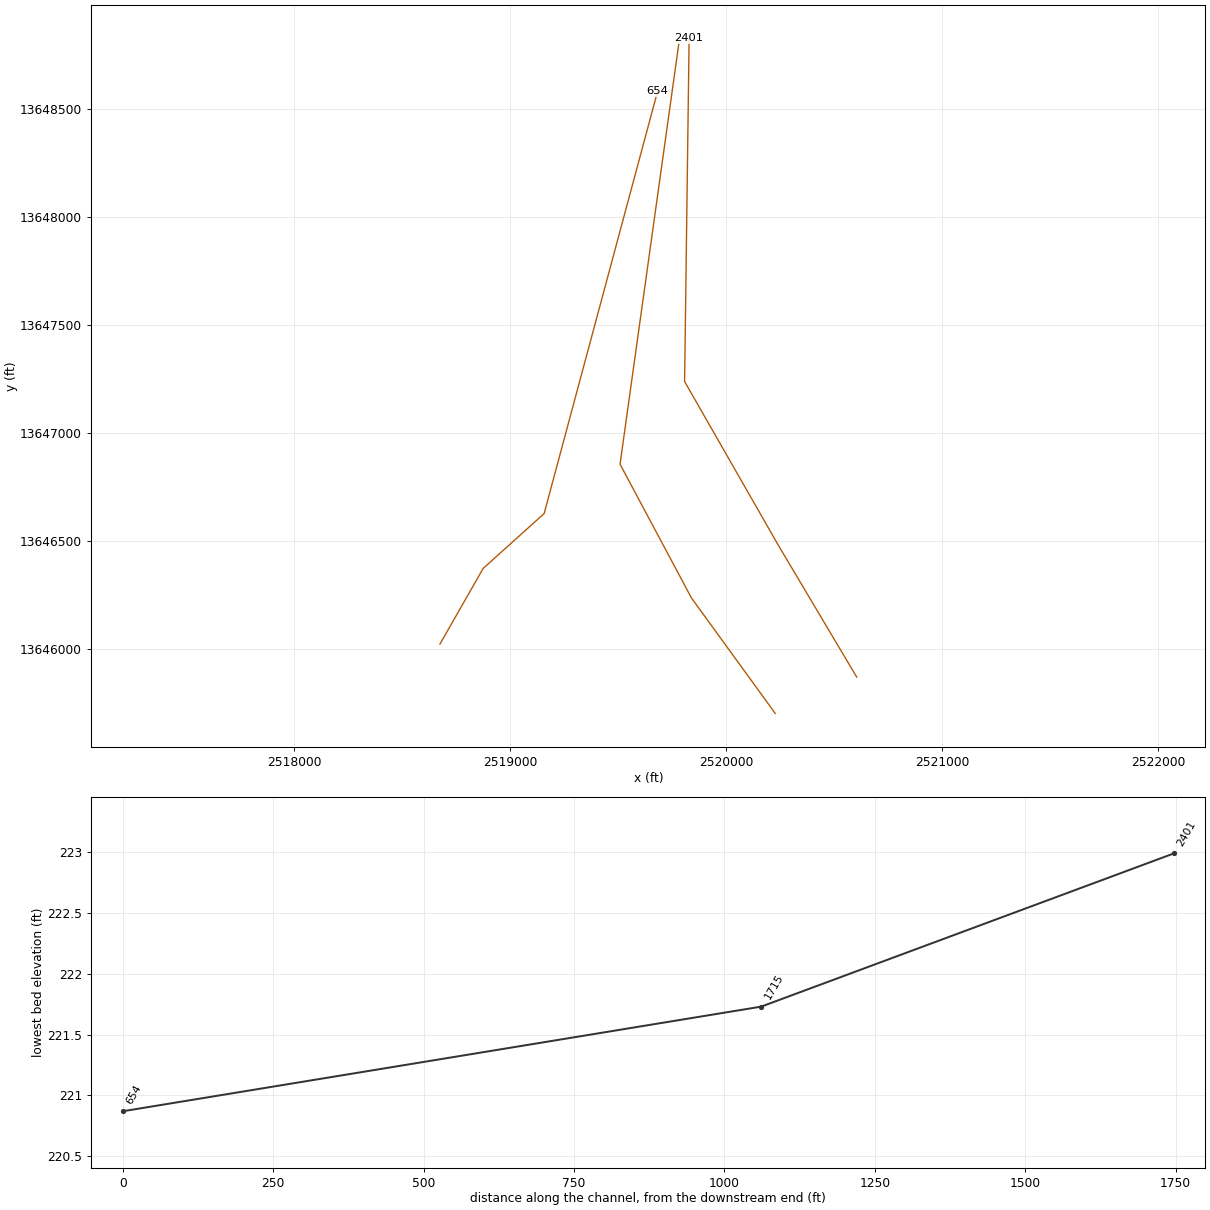
HEC-RAS study SOUTH FORK QUEENS CREEK.prj: SOUTH FORK QUEENS CREEK Base Level Engineering

--- SOUTH FORK QUEENS CREEK.g01 (geometry) --- (continued)

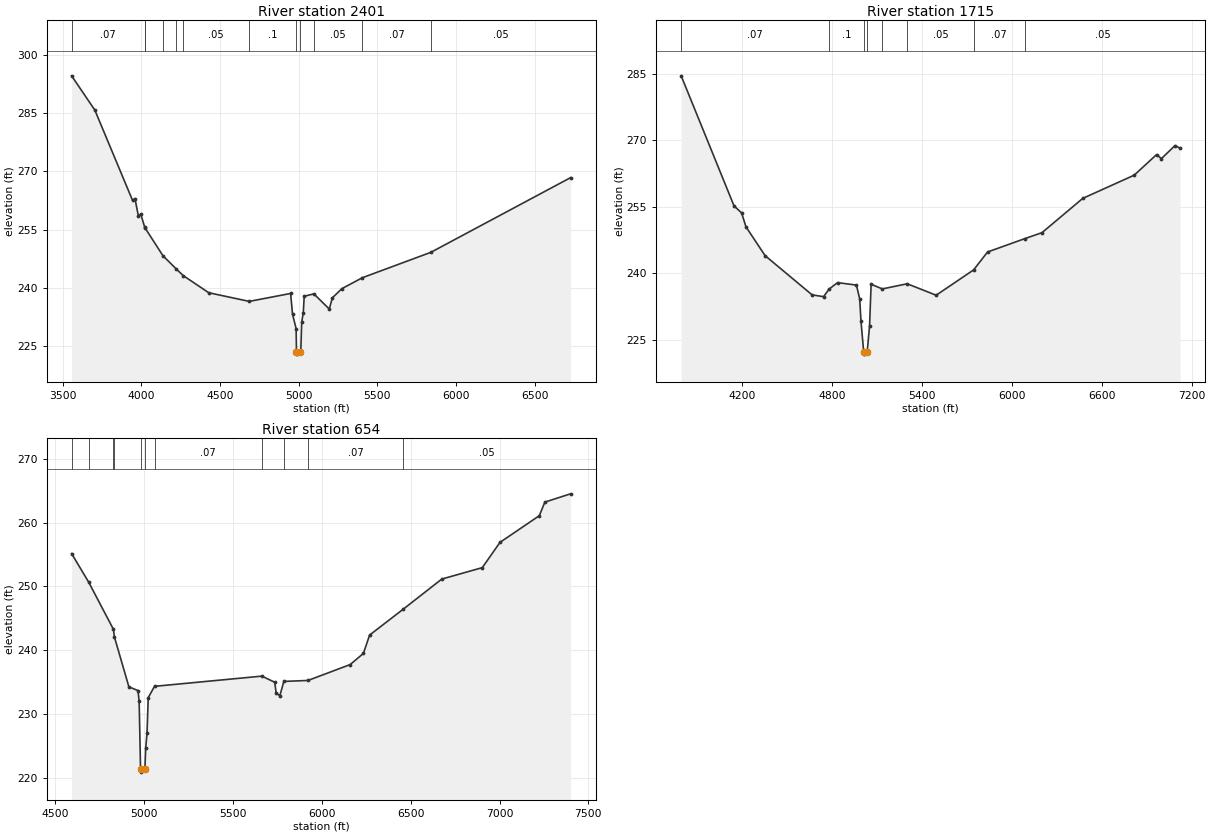
Type RM Length L Ch R = 1,2401,686,686,686
BEGIN DESCRIPTION:
SOUTH FORK QUEENS CREEK 1.3
END DESCRIPTION:
XS GIS Cut Line= 4
      2520604.81     13645871.78      2520242.98     13646480.08
      2519807.70     13647240.51      2519828.68     13648829.50
#Sta/Elev= 30
  3555.7  294.60  3703.5  285.78  3943.4  262.53  3958.6  263.02  3980.0  258.59
  3995.6  259.00  4020.9  255.60  4023.8  255.40  4136.5  248.31  4221.4  244.90
  4265.7  243.19  4427.6  238.79  4685.3  236.56  4948.5  238.60  4960.5  233.29
  4983.5  229.55  4985.8  223.49  4986.3  222.99  5009.2  223.49  5013.3  223.83
  5019.1  231.27  5029.1  233.67  5034.9  237.89  5096.4  238.49  5194.2  234.60
  5214.2  237.49  5274.2  239.83  5405.3  242.66  5840.7  249.19  6728.8  268.40
#Mann=12,-1,0
  3555.7    0.07       0  4020.9    0.12       0  4023.8    0.07       0
  4136.5    0.05       0  4221.4    0.07       0  4265.7    0.05       0
  4685.3     0.1       0  4985.8    0.05       0  5009.2     0.1       0
  5096.4    0.05       0  5405.3    0.07       0  5840.7    0.05       0
Bank Sta=4985.8,5009.2
Exp/Cntr=0.3,0.1

Type RM Length L Ch R = 1,1715,1061,1061,1061
BEGIN DESCRIPTION:
SOUTH FORK QUEENS CREEK 1.1
END DESCRIPTION:
XS GIS Cut Line= 4
      2520227.26     13645703.90      2519839.17     13646238.85
      2519508.77     13646857.67      2519781.48     13648808.60
#Sta/Elev= 30
  3790.5  284.51  4143.7  255.16  4194.0  253.60  4223.3  250.45  4350.9  243.95
  4665.0  235.10  4741.5  234.69  4778.4  236.40  4835.0  237.86  4961.0  237.30
  4983.0  234.18  4991.2  229.25  5009.5  222.23  5010.0  221.73  5032.9  222.23
  5048.8  228.13  5059.2  237.49  5134.2  236.44  5299.8  237.60  5493.5  235.02
  5743.6  240.73  5836.8  244.77  6085.3  247.78  6200.3  249.13  6472.9  256.87
  6816.2  262.10  6965.1  266.73  6998.0  265.84  7088.9  268.78  7122.8  268.18
#Mann=8,-1,0
  3790.5    0.07       0  4778.4     0.1       0  5009.5    0.05       0
  5032.9     0.1       0  5134.2    0.07       0  5299.8    0.05       0
  5743.6    0.07       0  6085.3    0.05       0
Bank Sta=5009.5,5032.9
Exp/Cntr=0.3,0.1

Type RM Length L Ch R = 1,654,0,0,0
BEGIN DESCRIPTION:
SOUTH FORK QUEENS CREEK 1.0
END DESCRIPTION:
XS GIS Cut Line= 4
      2518675.00     13646025.01      2518875.00     13646375.00
      2519157.40     13646629.16      2519682.78     13648584.78
#Sta/Elev= 30
  4591.7  255.15  4686.8  250.72  4827.1  243.27  4832.4  242.09  4914.2  234.24
  4965.3  233.67  4971.8  231.97  4979.7  221.37  4980.2  220.87  5004.2  221.37
  5008.6  224.59  5016.1  226.98  5022.8  232.55  5058.3  234.33  5662.6  235.93
  5734.8  234.97  5743.2  233.22  5763.9  232.88  5786.1  235.10  5921.7  235.25
  6159.1  237.74  6233.9  239.49  6268.7  242.37  6456.0  246.39  6675.1  251.16
  6902.9  252.95  7002.4  256.91  7223.9  261.10  7255.0  263.23  7399.7  264.53
#Mann=11,-1,0
  4591.7    0.05       0  4686.8    0.07       0  4827.1    0.12       0
  4832.4     0.1       0  4979.7    0.05       0  5004.2     0.1       0
  5058.3    0.07       0  5662.6     0.1       0  5786.1    0.05       0
  5921.7    0.07       0  6456.0    0.05       0
Bank Sta=4979.7,5004.2
Exp/Cntr=0.3,0.1

Chan Stop Cuts=-1