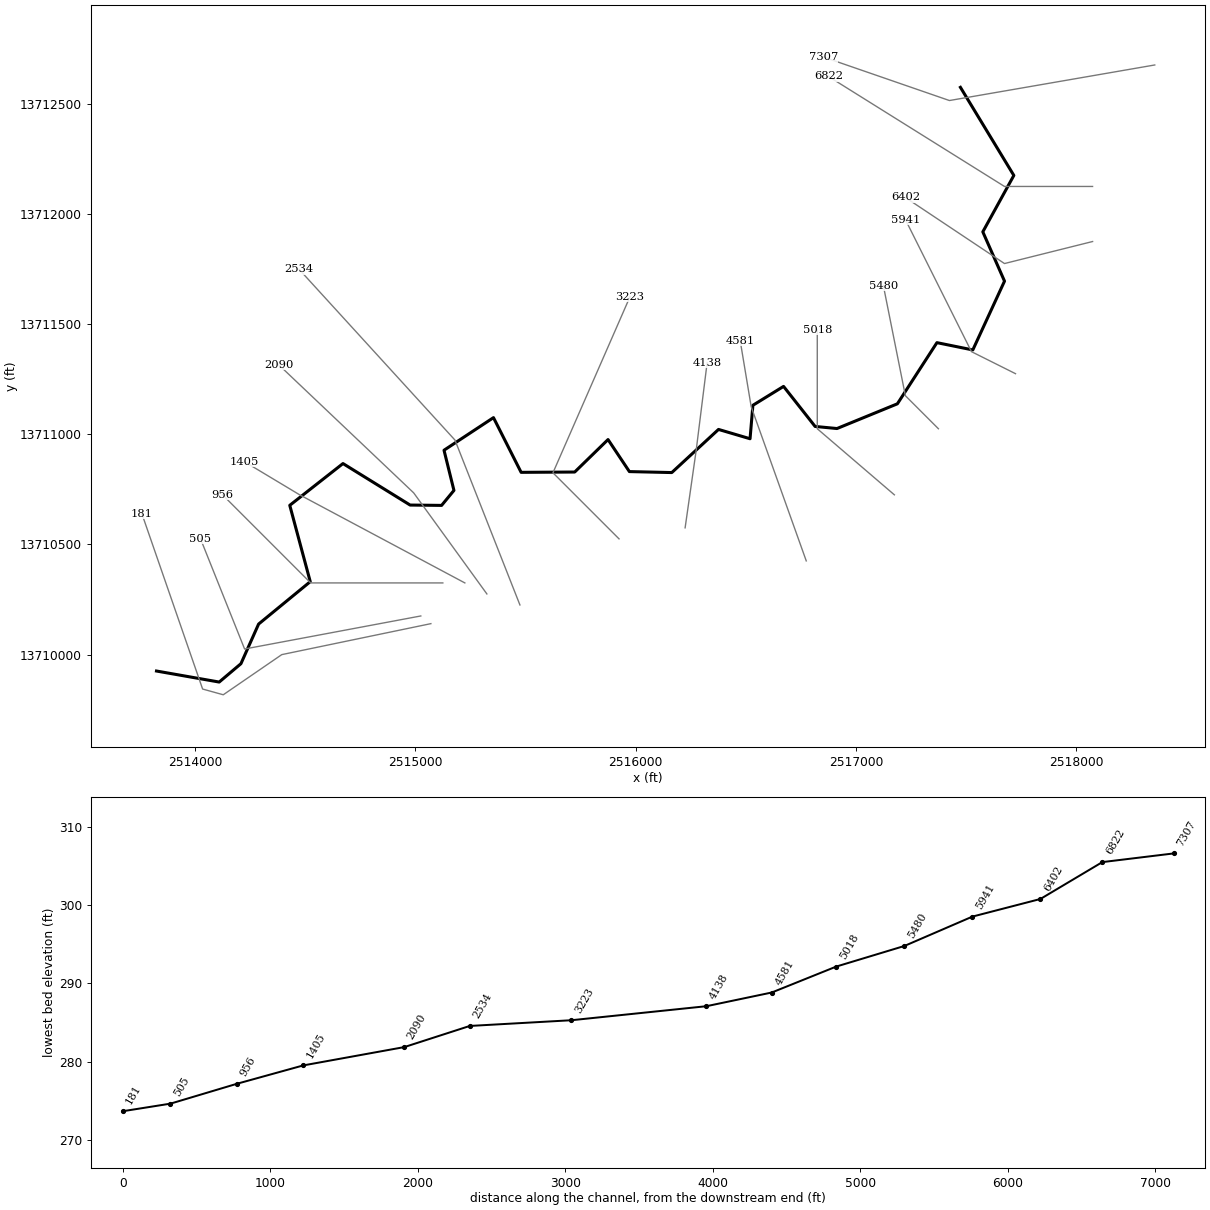
--- Stream0490.prj (project) ---

Proj Title=Stream0490 Base Level Engineering
Current Plan=p01
Default Exp/Contr=0.3,0.1
English Units
Geom File=g01
Flow File=f01
Plan File=p01
BEGIN DESCRIPTION:
Stream0490
END DESCRIPTION:

--- Stream0490.p01 (plan) ---

Plan Title=Multiple Run
Short Identifier=Multiple
Geom File=g01
Flow File=f01
Subcritical Flow
K Sum by GR= 0
Std Step Tol= 0.01
Critical Tol= 0.01
Num of Std Step Trials= 20
Max Error Tol= 0.3
Flow Tol Ratio= 0.001
Split Flow NTrial= 30
Split Flow Tol= 0.02
Split Flow Ratio= 0.02
Log Output Level= 0
Friction Slope Method= 1
Unsteady Friction Slope Method= 2
Unsteady Bridges Friction Slope Method= 1
Parabolic Critical Depth
Global Vel Dist=  1 , 1 , 1
Global Log Level= 0
CheckData=True
Encroach Param= -1, 0, 0, 0
BEGIN DESCRIPTION:
Multiple Run
END DESCRIPTION:

--- Stream0490.f01 (steady flow) ---

Flow Title=Multiple
Number of Profiles=7
Profile Names=10-year,25-year,50-year,1pct_min,100-year,1pct_plu,500-year
River Rch & RM= Stream0490,Reach-1,7307
     829    1357    1842    1212    2417    4824    4120
River Rch & RM= Stream0490,Reach-1,6822
    1013    1665    2265    1491    2974    5934    5078
Boundary for River Rch & Prof#=Stream0490,Reach-1,1
Up Type=0
Dn Type=3
Dn Slope=0.005
Boundary for River Rch & Prof#=Stream0490,Reach-1,2
Up Type=0
Dn Type=3
Dn Slope=0.005
Boundary for River Rch & Prof#=Stream0490,Reach-1,3
Up Type=0
Dn Type=3
Dn Slope=0.005
Boundary for River Rch & Prof#=Stream0490,Reach-1,4
Up Type=0
Dn Type=3
Dn Slope=0.005
Boundary for River Rch & Prof#=Stream0490,Reach-1,5
Up Type=0
Dn Type=3
Dn Slope=0.005
Boundary for River Rch & Prof#=Stream0490,Reach-1,6
Up Type=0
Dn Type=3
Dn Slope=0.005
Boundary for River Rch & Prof#=Stream0490,Reach-1,7
Up Type=0
Dn Type=3
Dn Slope=0.005

--- Stream0490.g01 (geometry) ---

Geom Title=Existing Conditions

River Reach=Stream0490,Reach-1
Reach XY= 30
      2517475.00     13712575.00      2517717.47     13712175.01
      2517576.59     13711918.95      2517675.10     13711695.10
      2517531.19     13711382.75      2517368.26     13711415.87
      2517188.73     13711138.20      2516914.51     13711025.94
      2516815.19     13711035.42      2516671.95     13711217.24
      2516532.70     13711131.47      2516519.82     13710979.60
      2516376.64     13711021.87      2516164.57     13710826.05
      2515972.00     13710830.46      2515875.03     13710975.89
      2515723.75     13710828.45      2515480.46     13710827.06
      2515354.97     13711075.45      2515130.39     13710927.44
      2515175.45     13710745.01      2515119.37     13710676.97
      2514976.47     13710678.53      2514671.68     13710866.96
      2514430.09     13710677.30      2514523.09     13710330.72
      2514288.61     13710138.24      2514208.37     13709958.28
      2514109.67     13709874.95      2513825.00     13709925.00

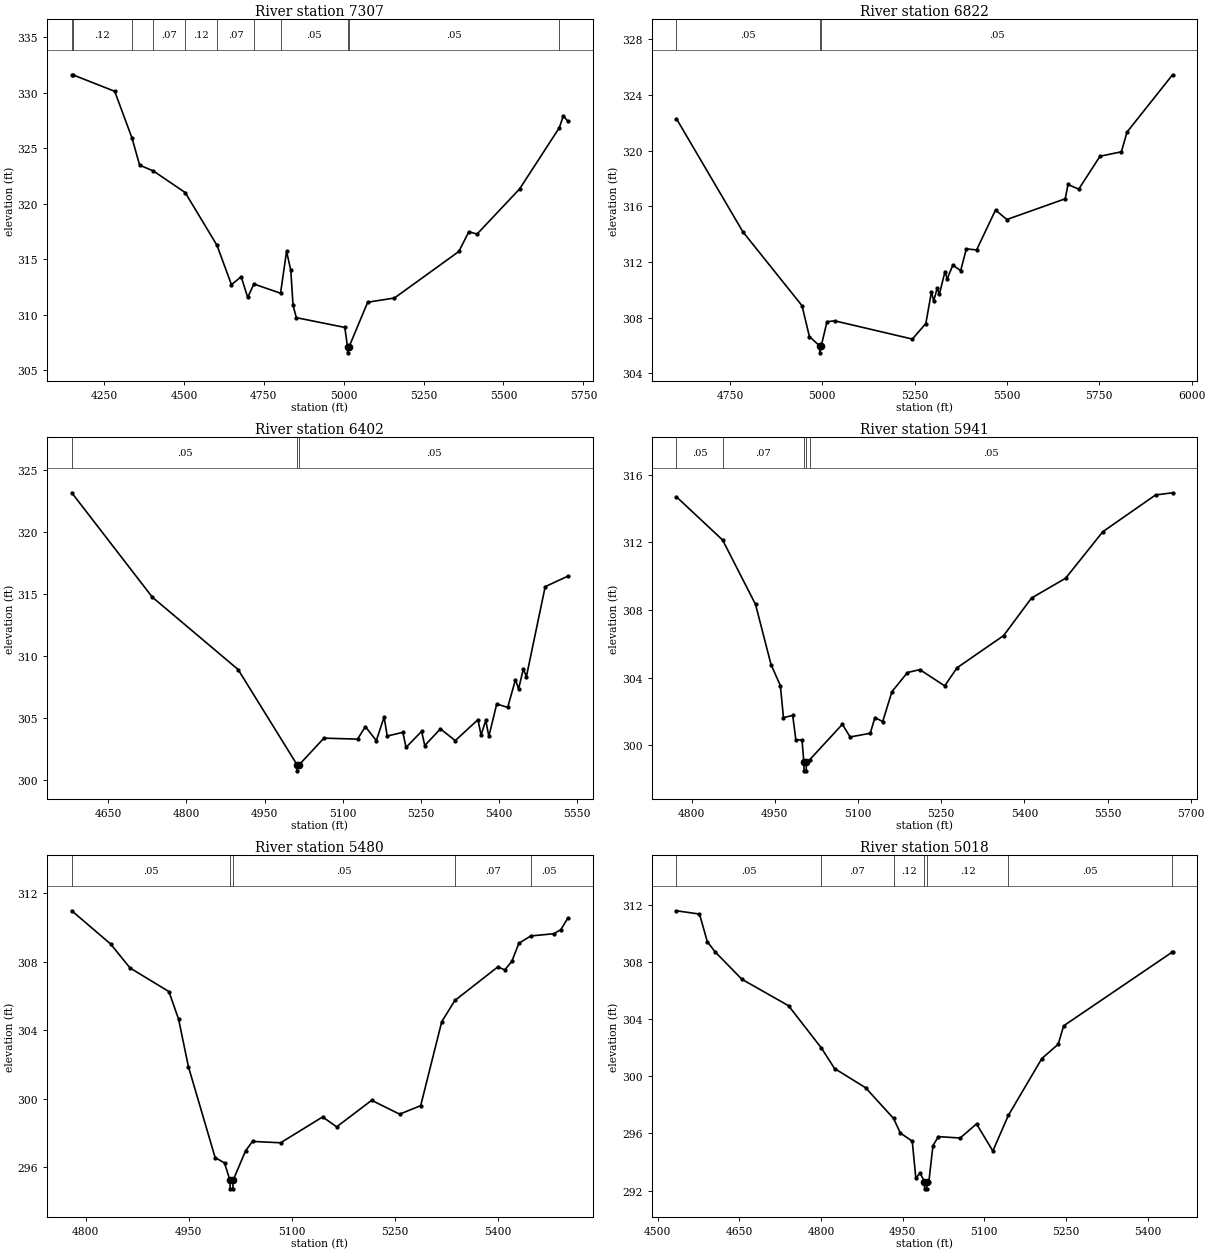
Type RM Length L Ch R = 1,7307,485,485,485
BEGIN DESCRIPTION:
XS6929
END DESCRIPTION:
XS GIS Cut Line= 3
      2518357.29     13712676.56      2517425.00     13712515.10
      2516852.09     13712713.02
#Sta/Elev= 30
  4149.2  331.62  4152.2  331.62  4283.5  330.13  4337.5  325.93  4361.5  323.48
  4404.7  322.95  4504.1  321.01  4603.5  316.26  4648.8  312.71  4679.3  313.43
  4699.6  311.56  4719.1  312.77  4802.4  311.94  4821.3  315.72  4834.4  314.01
  4841.6  310.84  4851.8  309.74  5003.5  308.86  5012.2  307.07  5012.4  306.57
  5016.2  307.07  5075.1  311.13  5158.8  311.51  5360.3  315.70  5391.6  317.48
  5417.3  317.27  5550.3  321.33  5674.5  326.84  5687.4  327.93  5701.5  327.43
#Mann=11,-1,0
  4149.2    0.05       0  4152.2    0.12       0  4337.5    0.05       0
  4404.7    0.07       0  4504.1    0.12       0  4603.5    0.07       0
  4719.1    0.12       0  4802.4    0.05       0  5012.2    0.05       0
  5016.2    0.05       0  5674.5    0.07       0
Bank Sta=5012.2,5016.2
Exp/Cntr=0.3,0.1

Type RM Length L Ch R = 1,6822,420,420,420
BEGIN DESCRIPTION:
Stream0490 13.0
END DESCRIPTION:
XS GIS Cut Line= 3
      2518074.96     13712125.00      2517675.00     13712125.00
      2516874.96     13712625.02
#Sta/Elev= 30
  4604.9  322.30  4784.9  314.16  4944.9  308.85  4964.9  306.63  4992.7  305.96
  4993.0  305.46  4997.0  305.96  5012.5  307.70  5033.7  307.76  5243.7  306.45
  5280.2  307.57  5295.5  309.86  5301.4  309.18  5310.9  310.10  5316.8  309.67
  5332.1  311.31  5338.0  310.78  5353.3  311.77  5374.5  311.37  5389.9  312.94
  5417.6  312.86  5468.9  315.73  5499.6  315.05  5657.6  316.54  5665.2  317.57
  5694.1  317.23  5751.9  319.60  5809.7  319.92  5825.0  321.34  5948.3  325.46
#Mann=3,-1,0
  4604.9    0.05       0  4992.7    0.05       0  4997.0    0.05       0
Bank Sta=4992.7,4997
Exp/Cntr=0.3,0.1

Type RM Length L Ch R = 1,6402,461,461,461
BEGIN DESCRIPTION:
Stream0490 12.0
END DESCRIPTION:
XS GIS Cut Line= 3
      2518075.02     13711875.01      2517675.00     13711775.00
      2517224.97     13712075.02
#Sta/Elev= 30
  4579.6  323.20  4734.2  314.78  4899.2  308.93  5012.3  301.25  5012.6  300.75
  5016.7  301.25  5064.0  303.39  5128.6  303.31  5143.7  304.32  5164.7  303.19
  5179.7  305.09  5185.7  303.56  5215.8  303.86  5221.8  302.64  5251.8  303.94
  5257.8  302.79  5287.9  304.14  5316.4  303.19  5360.0  304.88  5366.0  303.64
  5375.0  304.82  5381.0  303.54  5396.1  306.15  5417.1  305.87  5432.1  308.11
  5438.1  307.36  5447.1  308.97  5453.1  308.36  5489.2  315.62  5532.8  316.47
#Mann=3,-1,0
  4579.6    0.05       0  5012.3    0.05       0  5016.7    0.05       0
Bank Sta=5012.3,5016.7
Exp/Cntr=0.3,0.1

Type RM Length L Ch R = 1,5941,461,461,461
BEGIN DESCRIPTION:
Stream0490 11.0
END DESCRIPTION:
XS GIS Cut Line= 3
      2517725.01     13711275.00      2517525.00     13711375.00
      2517225.02     13711974.97
#Sta/Elev= 30
  4772.6  314.69  4855.8  312.14  4915.2  308.33  4943.1  304.78  4959.9  303.54
  4965.5  301.65  4982.2  301.77  4987.8  300.34  4999.0  300.32  5002.3  299.00
  5002.6  298.50  5006.5  298.50  5006.8  299.00  5012.9  299.16  5071.7  301.25
  5085.7  300.50  5122.0  300.72  5130.4  301.65  5144.4  301.41  5161.1  303.18
  5189.1  304.31  5211.4  304.48  5256.2  303.52  5278.5  304.59  5362.4  306.49
  5412.7  308.71  5474.2  309.88  5541.3  312.63  5636.3  314.80  5667.0  314.93
#Mann=5,-1,0
  4772.6    0.05       0  4855.8    0.07       0  5002.3    0.05       0
  5006.8    0.07       0  5012.9    0.05       0
Bank Sta=5002.3,5006.8
Exp/Cntr=0.3,0.1

Type RM Length L Ch R = 1,5480,462,462,462
BEGIN DESCRIPTION:
Stream0490 10.0
END DESCRIPTION:
XS GIS Cut Line= 3
      2517374.97     13711025.03      2517225.00     13711175.00
      2517125.00     13711675.01
#Sta/Elev= 30
  4779.8  310.99  4836.3  309.05  4864.6  307.65  4921.2  306.27  4935.3  304.65
  4949.5  301.89  4988.4  296.58  5002.1  296.26  5010.0  295.25  5010.3  294.75
  5014.2  294.75  5014.6  295.25  5032.7  296.97  5042.9  297.52  5083.7  297.44
  5144.9  298.95  5165.3  298.37  5216.2  299.92  5257.0  299.11  5287.6  299.61
  5318.2  304.51  5337.3  305.75  5399.8  307.71  5410.0  307.54  5420.2  308.03
  5430.4  309.09  5447.9  309.52  5481.4  309.65  5491.6  309.89  5501.8  310.57
#Mann=5,-1,0
  4779.8    0.05       0  5010.0    0.05       0  5014.6    0.05       0
  5337.3    0.07       0  5447.9    0.05       0
Bank Sta=5010,5014.6
Exp/Cntr=0.3,0.1

Type RM Length L Ch R = 1,5018,437,437,437
BEGIN DESCRIPTION:
Stream0490 9.0
END DESCRIPTION:
XS GIS Cut Line= 3
      2517175.03     13710724.98      2516825.00     13711025.00
      2516825.00     13711474.99
#Sta/Elev= 30
  4534.8  311.60  4577.1  311.37  4591.4  309.44  4605.6  308.73  4655.0  306.80
  4740.6  304.95  4800.7  302.00  4825.1  300.55  4882.2  299.20  4933.5  297.05
  4945.9  296.03  4967.8  295.46  4974.4  292.85  4982.1  293.24  4990.2  292.62
  4990.6  292.12  4994.5  292.12  4994.8  292.62  4998.3  292.62  5005.8  295.15
  5015.8  295.78  5055.8  295.68  5085.8  296.67  5115.8  294.77  5144.3  297.27
  5205.8  301.25  5235.8  302.25  5245.8  303.54  5445.4  308.71  5445.8  308.71
#Mann=7,-1,0
  4534.8    0.05       0  4800.7    0.07       0  4933.5    0.12       0
  4990.2    0.05       0  4994.8    0.12       0  5144.3    0.05       0
  5445.4    0.07       0
Bank Sta=4990.2,4994.8
Exp/Cntr=0.3,0.1

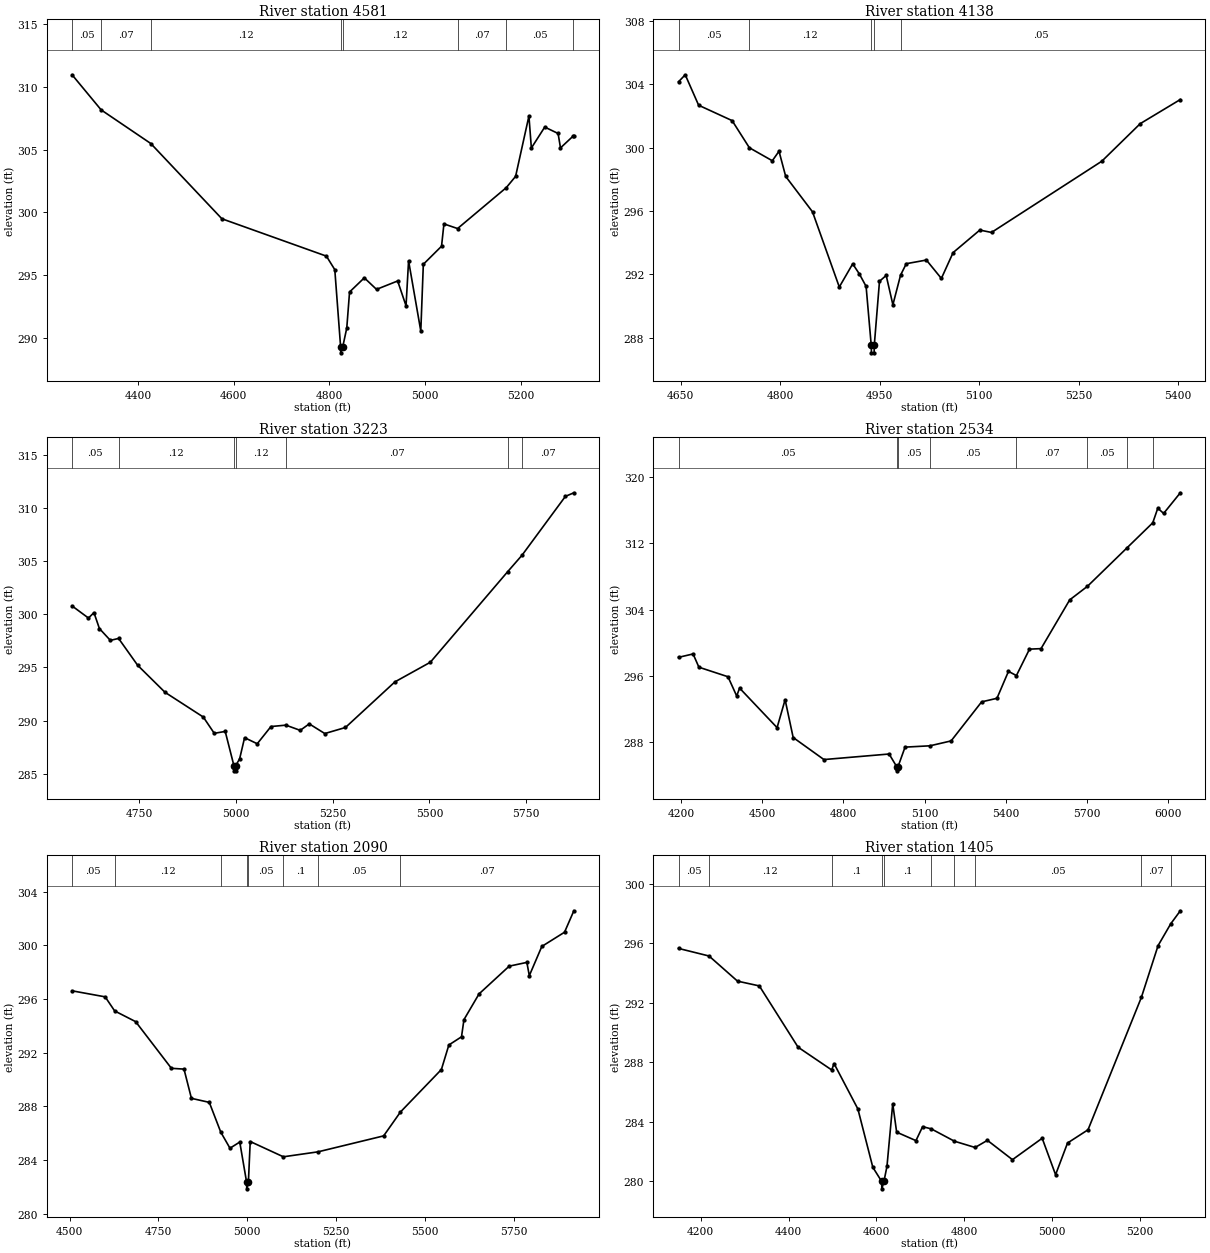
Type RM Length L Ch R = 1,4581,443,443,443
BEGIN DESCRIPTION:
Stream0490 8.0
END DESCRIPTION:
XS GIS Cut Line= 3
      2516774.99     13710425.02      2516525.00     13711125.00
      2516475.00     13711424.98
#Sta/Elev= 30
  4262.7  310.98  4323.4  308.18  4427.0  305.50  4575.4  299.50  4793.6  296.52
  4811.1  295.44  4823.2  289.31  4823.5  288.81  4827.8  289.31  4836.1  290.79
  4841.9  293.66  4872.7  294.79  4898.2  293.87  4942.3  294.54  4959.8  292.56
  4965.1  296.15  4990.6  290.55  4995.9  295.87  5033.9  297.31  5038.9  299.09
  5067.4  298.72  5169.0  301.98  5188.5  302.88  5216.3  307.69  5221.4  305.14
  5249.3  306.81  5277.2  306.30  5282.2  305.15  5309.1  306.11  5310.1  306.11
#Mann=8,-1,0
  4262.7    0.05       0  4323.4    0.07       0  4427.0    0.12       0
  4823.2    0.05       0  4827.8    0.12       0  5067.4    0.07       0
  5169.0    0.05       0  5309.1    0.07       0
Bank Sta=4823.2,4827.8
Exp/Cntr=0.3,0.1

Type RM Length L Ch R = 1,4138,915,915,915
BEGIN DESCRIPTION:
Stream0490 7.0
END DESCRIPTION:
XS GIS Cut Line= 3
      2516225.01     13710575.05      2516275.00     13710925.00
      2516325.00     13711324.98
#Sta/Elev= 30
  4646.5  304.15  4656.6  304.59  4676.8  302.67  4727.3  301.70  4753.3  299.99
  4787.9  299.17  4798.0  299.77  4808.1  298.18  4848.5  295.95  4888.9  291.21
  4909.1  292.67  4919.2  292.03  4929.3  291.25  4937.0  287.56  4937.4  287.06
  4941.4  287.06  4941.7  287.56  4949.5  291.57  4959.6  291.94  4969.7  290.09
  4981.3  291.96  4989.9  292.68  5020.2  292.91  5042.8  291.75  5060.5  293.38
  5100.8  294.80  5118.4  294.65  5284.7  299.14  5342.7  301.51  5403.1  303.03
#Mann=5,-1,0
  4646.5    0.05       0  4753.3    0.12       0  4937.0    0.05       0
  4941.7    0.12       0  4981.3    0.05       0
Bank Sta=4937,4941.7
Exp/Cntr=0.3,0.1

Type RM Length L Ch R = 1,3223,689,689,689
BEGIN DESCRIPTION:
Stream0490 6.0
END DESCRIPTION:
XS GIS Cut Line= 3
      2515924.99     13710525.01      2515625.00     13710825.00
      2515975.01     13711625.03
#Sta/Elev= 30
  4575.9  300.79  4618.3  299.65  4632.5  300.16  4646.6  298.66  4674.9  297.55
  4696.2  297.73  4745.6  295.20  4816.3  292.66  4915.3  290.33  4943.6  288.80
  4971.9  288.98  4994.3  285.77  4994.6  285.27  4998.6  285.27  4999.0  285.77
  5009.1  286.39  5022.0  288.39  5054.7  287.82  5090.2  289.44  5128.8  289.57
  5165.8  289.08  5189.2  289.69  5229.4  288.78  5282.8  289.35  5410.6  293.64
  5502.3  295.49  5702.4  304.02  5739.3  305.56  5851.5  311.10  5873.4  311.44
#Mann=7,-1,0
  4575.9    0.05       0  4696.2    0.12       0  4994.3    0.05       0
  4999.0    0.12       0  5128.8    0.07       0  5702.4    0.05       0
  5739.3    0.07       0
Bank Sta=4994.3,4999
Exp/Cntr=0.3,0.1

Type RM Length L Ch R = 1,2534,444,444,444
BEGIN DESCRIPTION:
Stream0490 5.0
END DESCRIPTION:
XS GIS Cut Line= 3
      2515475.02     13710224.96      2515180.21     13710973.44
      2514471.91     13711749.44
#Sta/Elev= 30
  4190.3  298.23  4244.1  298.64  4265.6  297.04  4373.1  295.89  4405.3  293.57
  4416.0  294.52  4554.6  289.75  4584.3  293.12  4614.1  288.56  4727.8  285.90
  4968.8  286.57  4996.9  285.04  4997.3  284.54  5001.7  285.04  5027.7  287.40
  5119.9  287.56  5198.0  288.15  5310.8  292.86  5367.5  293.29  5410.1  296.54
  5439.4  296.03  5487.8  299.22  5530.4  299.28  5636.4  305.16  5702.1  306.80
  5847.4  311.41  5943.5  314.46  5962.1  316.22  5983.7  315.59  6045.4  318.08
#Mann=8,-1,0
  4190.3    0.05       0  4996.9    0.05       0  5001.7    0.05       0
  5119.9    0.05       0  5439.4    0.07       0  5702.1    0.05       0
  5847.4   0.035       0  5943.5    0.07       0
Bank Sta=4996.9,5001.7
Exp/Cntr=0.3,0.1

Type RM Length L Ch R = 1,2090,685,685,685
BEGIN DESCRIPTION:
Stream0490 4.0
END DESCRIPTION:
XS GIS Cut Line= 3
      2515325.00     13710275.00      2514992.71     13710733.85
      2514379.06     13711316.30
#Sta/Elev= 30
  4506.7  296.61  4599.9  296.16  4626.6  295.11  4685.7  294.31  4786.3  290.83
  4821.8  290.77  4842.7  288.59  4893.0  288.29  4925.3  286.07  4951.2  284.87
  4978.8  285.33  4998.0  282.34  4998.4  281.84  5003.1  282.34  5008.2  285.37
  5101.5  284.23  5199.1  284.60  5383.8  285.79  5431.1  287.57  5546.4  290.74
  5567.4  292.57  5603.0  293.18  5609.9  294.46  5652.4  296.38  5737.3  298.45
  5787.0  298.73  5793.9  297.74  5829.1  299.92  5893.0  300.98  5919.3  302.58
#Mann=8,-1,0
  4506.7    0.05       0  4626.6    0.12       0  4925.3    0.05       0
  4998.0    0.05       0  5003.1    0.05       0  5101.5     0.1       0
  5199.1    0.05       0  5431.1    0.07       0
Bank Sta=4998,5003.1
Exp/Cntr=0.3,0.1

Type RM Length L Ch R = 1,1405,449,449,449
BEGIN DESCRIPTION:
Stream0490 3.0
END DESCRIPTION:
XS GIS Cut Line= 3
      2515225.01     13710325.00      2514475.00     13710725.00
      2514224.96     13710875.02
#Sta/Elev= 30
  4149.7  295.66  4219.1  295.15  4283.9  293.46  4333.5  293.14  4421.7  289.02
  4498.2  287.49  4503.5  287.92  4557.7  284.87  4591.7  280.95  4611.8  280.00
  4612.2  279.50  4617.0  280.00  4623.9  281.01  4637.0  285.22  4645.9  283.31
  4689.8  282.74  4705.0  283.68  4724.7  283.53  4777.5  282.70  4824.4  282.28
  4852.4  282.76  4909.4  281.46  4977.0  282.90  5007.5  280.45  5034.7  282.58
  5081.3  283.47  5202.7  292.37  5240.7  295.85  5269.6  297.32  5291.3  298.19
#Mann=10,-1,0
  4149.7    0.05       0  4219.1    0.12       0  4498.2     0.1       0
  4611.8    0.05       0  4617.0     0.1       0  4724.7    0.12       0
  4777.5     0.1       0  4824.4    0.05       0  5202.7    0.07       0
  5269.6    0.05       0
Bank Sta=4611.8,4617
Exp/Cntr=0.3,0.1

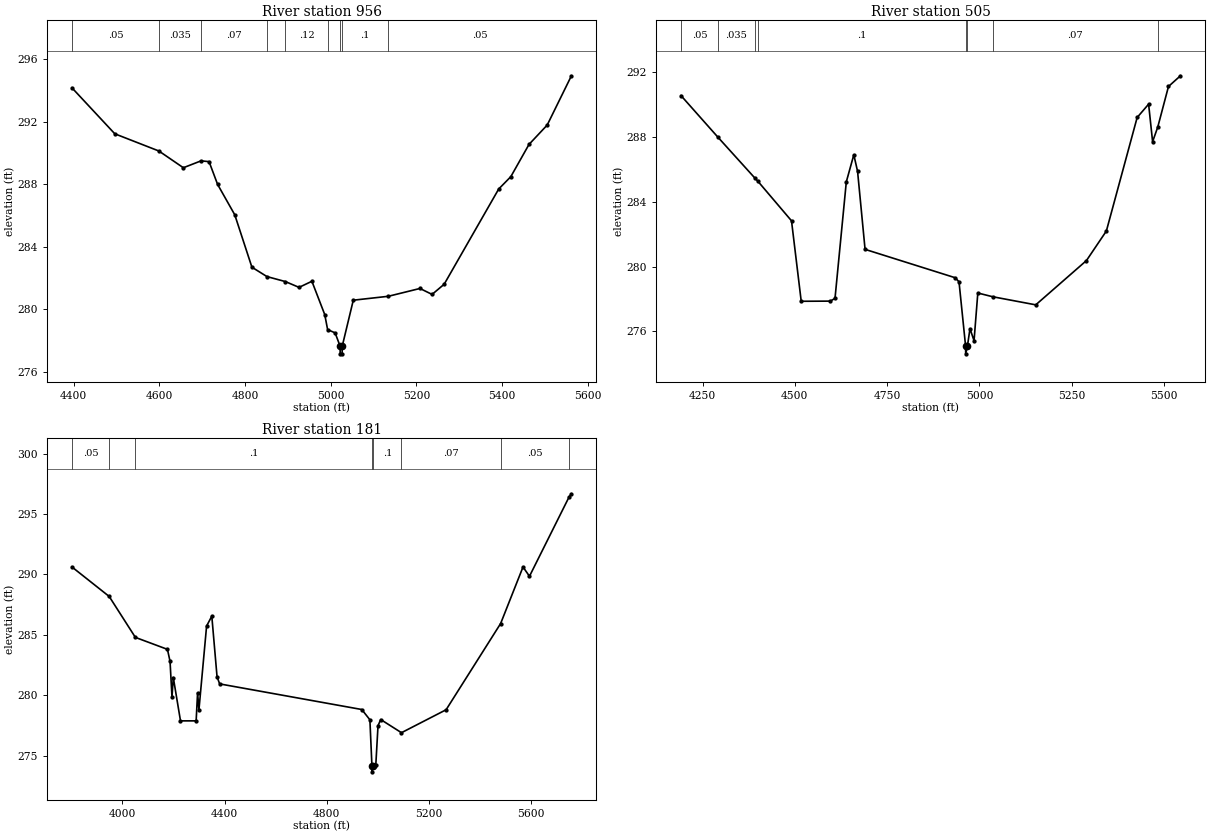
Type RM Length L Ch R = 1,956,451,451,451
BEGIN DESCRIPTION:
Stream0490 2.0
END DESCRIPTION:
XS GIS Cut Line= 3
      2515125.04     13710325.00      2514525.00     13710325.00
      2514125.02     13710724.98
#Sta/Elev= 30
  4395.9  294.17  4495.9  291.23  4598.8  290.13  4655.9  289.06  4697.2  289.50
  4715.9  289.45  4735.9  287.99  4775.9  286.05  4815.9  282.70  4851.0  282.10
  4894.1  281.78  4925.9  281.41  4955.9  281.80  4985.9  279.67  4992.6  278.71
  5010.1  278.50  5021.6  277.66  5022.0  277.16  5026.4  277.16  5026.8  277.66
  5052.5  280.59  5134.3  280.84  5208.1  281.34  5236.4  280.96  5264.6  281.61
  5391.9  287.70  5420.2  288.49  5462.6  290.55  5505.1  291.79  5561.6  294.94
#Mann=9,-1,0
  4395.9    0.05       0  4598.8   0.035       0  4697.2    0.07       0
  4851.0     0.1       0  4894.1    0.12       0  4992.6     0.1       0
  5021.6    0.05       0  5026.8     0.1       0  5134.3    0.05       0
Bank Sta=5021.6,5026.8
Exp/Cntr=0.3,0.1

Type RM Length L Ch R = 1,505,324,324,324
BEGIN DESCRIPTION:
Stream0490 1.0
END DESCRIPTION:
XS GIS Cut Line= 3
      2515025.00     13710175.00      2514225.00     13710025.00
      2514024.98     13710525.04
#Sta/Elev= 30
  4191.7  290.54  4291.5  287.98  4391.2  285.47  4399.9  285.26  4491.0  282.82
  4517.3  277.86  4596.1  277.87  4608.8  278.04  4639.4  285.22  4659.7  286.89
  4669.9  285.87  4690.2  281.06  4934.4  279.31  4944.6  279.06  4962.3  275.12
  4962.7  274.62  4967.5  275.12  4974.3  276.17  4985.3  275.43  4995.5  278.37
  5035.7  278.14  5152.4  277.64  5289.7  280.37  5343.6  282.19  5427.0  289.19
  5458.0  290.01  5468.8  287.70  5482.8  288.60  5511.8  291.10  5544.2  291.76
#Mann=8,-1,0
  4191.7    0.05       0  4291.5   0.035       0  4391.2    0.07       0
  4399.9     0.1       0  4962.3    0.05       0  4967.5     0.1       0
  5035.7    0.07       0  5482.8    0.05       0
Bank Sta=4962.3,4967.5
Exp/Cntr=0.3,0.1

Type RM Length L Ch R = 1,181,0,0,0
BEGIN DESCRIPTION:
XS6930
END DESCRIPTION:
XS GIS Cut Line= 5
      2515070.80     13710140.10      2514393.75     13709999.48
      2514128.13     13709817.19      2514034.37     13709843.23
      2513758.36     13710640.02
#Sta/Elev= 30
  3802.7  290.61  3948.4  288.17  4050.9  284.78  4176.3  283.79  4186.5  282.80
  4194.1  279.84  4199.2  281.46  4227.4  277.87  4288.6  277.87  4294.3  280.20
  4299.5  278.78  4329.5  285.72  4349.9  286.54  4370.4  281.52  4380.6  280.93
  4936.7  278.81  4968.4  277.96  4976.4  274.15  4976.8  273.65  4981.6  274.15
  4991.5  274.20  5000.2  277.47  5010.8  277.98  5092.0  276.89  5266.6  278.79
  5480.0  285.93  5567.5  290.61  5592.8  289.84  5747.6  296.40  5756.9  296.67
#Mann=8,-1,0
  3802.7    0.05       0  3948.4   0.035       0  4050.9     0.1       0
  4976.4    0.05       0  4981.6     0.1       0  5092.0    0.07       0
  5480.0    0.05       0  5747.6    0.07       0
Bank Sta=4976.4,4981.6
Exp/Cntr=0.3,0.1

Chan Stop Cuts=-1