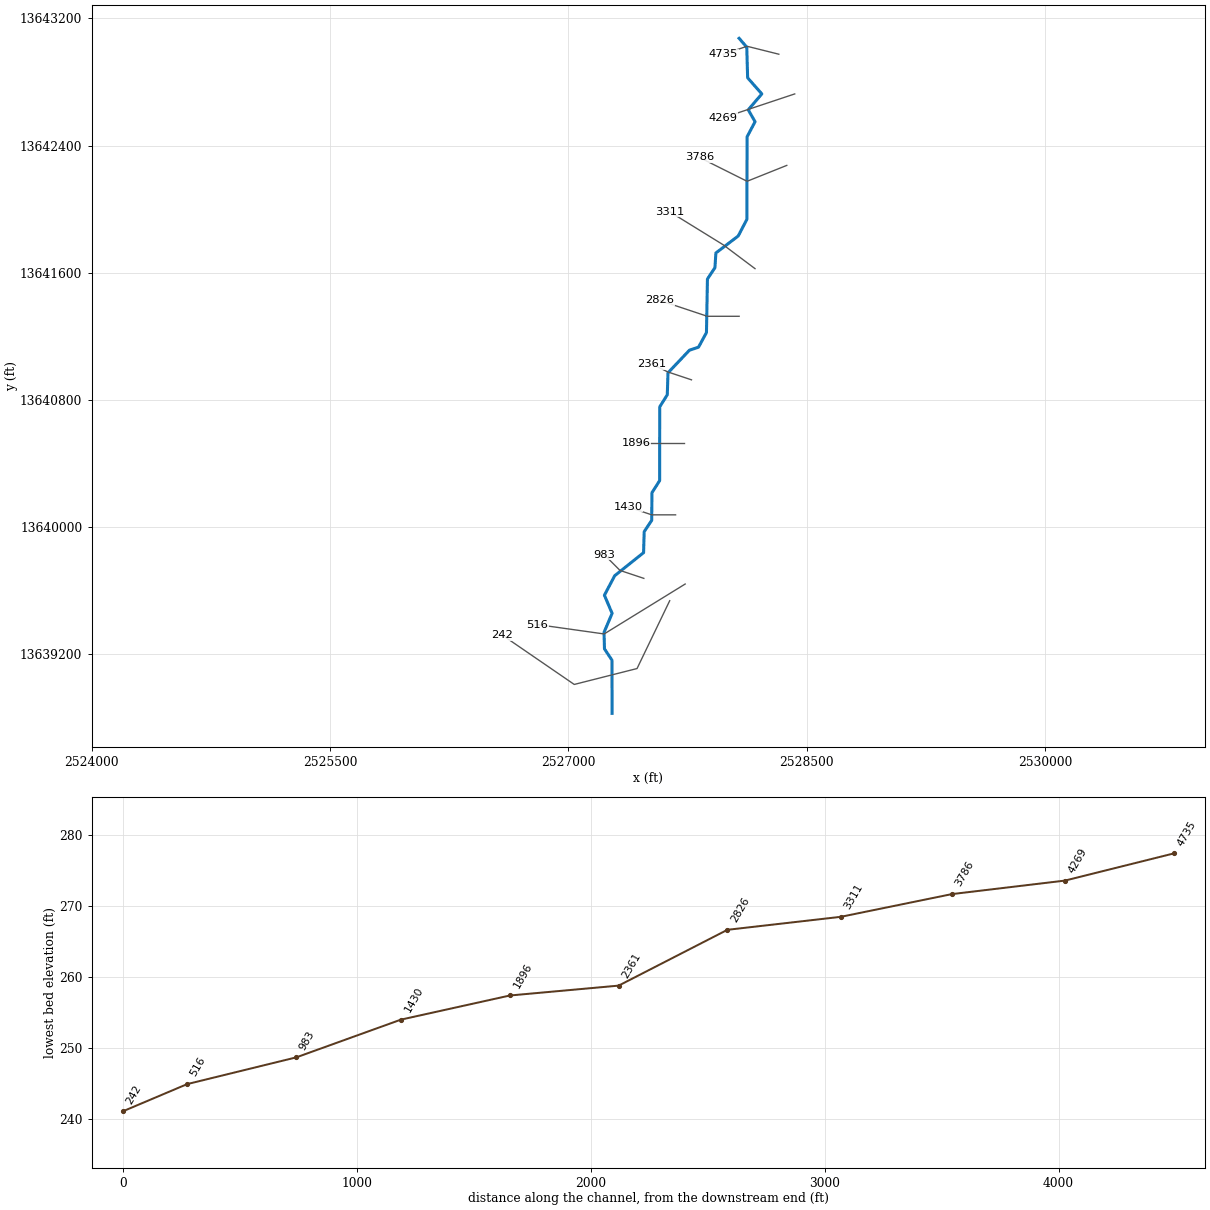
--- Stream0494.prj (project) ---

Proj Title=Stream0494 Base Level Engineering
Current Plan=p01
Default Exp/Contr=0.3,0.1
English Units
Geom File=g01
Flow File=f01
Plan File=p01
BEGIN DESCRIPTION:
Stream0494
END DESCRIPTION:

--- Stream0494.p01 (plan) ---

Plan Title=Multiple Run
Short Identifier=Multiple
Geom File=g01
Flow File=f01
Subcritical Flow
K Sum by GR= 0
Std Step Tol= 0.01
Critical Tol= 0.01
Num of Std Step Trials= 20
Max Error Tol= 0.3
Flow Tol Ratio= 0.001
Split Flow NTrial= 30
Split Flow Tol= 0.02
Split Flow Ratio= 0.02
Log Output Level= 0
Friction Slope Method= 1
Unsteady Friction Slope Method= 2
Unsteady Bridges Friction Slope Method= 1
Parabolic Critical Depth
Global Vel Dist=  1 , 1 , 1
Global Log Level= 0
CheckData=True
Encroach Param= -1, 0, 0, 0
BEGIN DESCRIPTION:
Multiple Run
END DESCRIPTION:

--- Stream0494.f01 (steady flow) ---

Flow Title=Multiple
Number of Profiles=7
Profile Names=10-year,25-year,50-year,1pct_min,100-year,1pct_plu,500-year
River Rch & RM= Stream0494,Reach-1,4735
     631    1012    1355     880    1757    3505    2918
Boundary for River Rch & Prof#=Stream0494,Reach-1,1
Up Type=0
Dn Type=3
Dn Slope=0.005
Boundary for River Rch & Prof#=Stream0494,Reach-1,2
Up Type=0
Dn Type=3
Dn Slope=0.005
Boundary for River Rch & Prof#=Stream0494,Reach-1,3
Up Type=0
Dn Type=3
Dn Slope=0.005
Boundary for River Rch & Prof#=Stream0494,Reach-1,4
Up Type=0
Dn Type=3
Dn Slope=0.005
Boundary for River Rch & Prof#=Stream0494,Reach-1,5
Up Type=0
Dn Type=3
Dn Slope=0.005
Boundary for River Rch & Prof#=Stream0494,Reach-1,6
Up Type=0
Dn Type=3
Dn Slope=0.005
Boundary for River Rch & Prof#=Stream0494,Reach-1,7
Up Type=0
Dn Type=3
Dn Slope=0.005

--- Stream0494.g01 (geometry) ---

Geom Title=Existing Conditions

River Reach=Stream0494,Reach-1
Reach XY= 30
      2528075.00     13643075.00      2528123.11     13643019.22
      2528128.56     13642826.46      2528217.89     13642725.00
      2528132.37     13642625.09      2528175.31     13642550.04
      2528125.08     13642454.97      2528123.81     13641935.48
      2528069.41     13641830.61      2527928.61     13641723.51
      2527922.64     13641630.98      2527875.52     13641559.78
      2527869.31     13641222.61      2527819.41     13641130.61
      2527762.02     13641111.27      2527627.07     13640969.14
      2527622.73     13640830.94      2527575.07     13640754.97
      2527574.48     13640290.22      2527526.22     13640214.49
      2527524.48     13640040.22      2527477.28     13639969.05
      2527473.36     13639836.83      2527291.64     13639691.68
      2527226.80     13639568.89      2527275.27     13639454.83
      2527224.50     13639335.17      2527227.25     13639230.94
      2527274.48     13639159.78      2527275.00     13638825.00

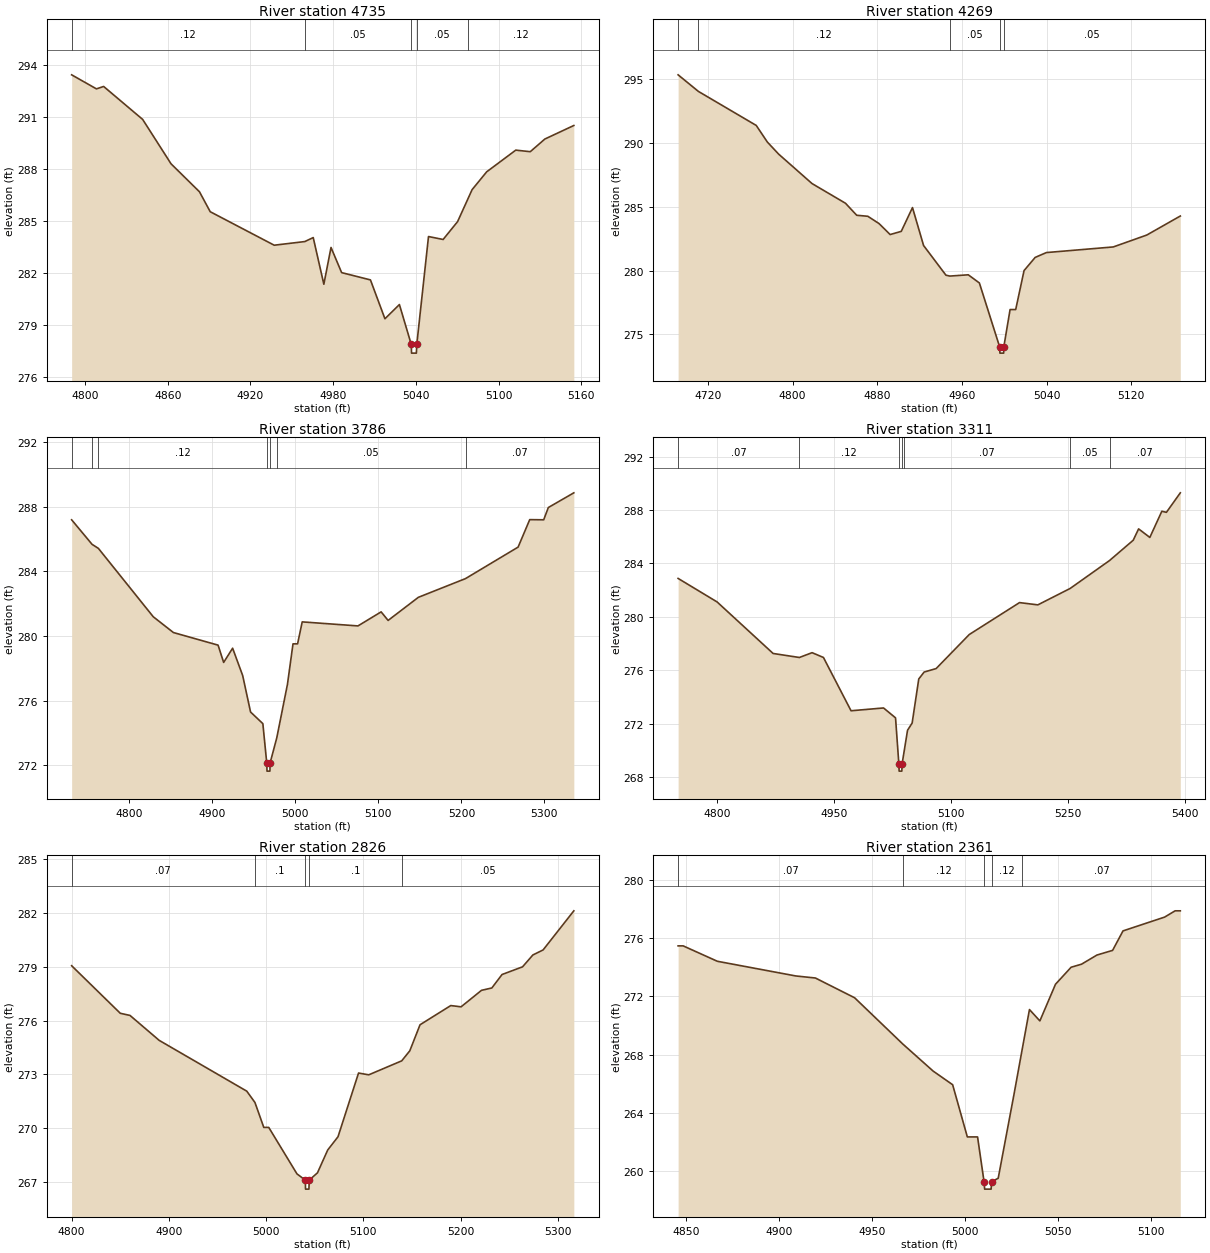
Type RM Length L Ch R = 1,4735,466,466,466
BEGIN DESCRIPTION:
Stream0494 10.0
END DESCRIPTION:
XS GIS Cut Line= 3
      2528324.97     13642975.01      2528125.00     13643025.00
      2527975.03     13642975.01
#Sta/Elev= 30
  4790.3  293.41  4808.3  292.60  4813.5  292.74  4841.8  290.84  4862.4  288.28
  4883.0  286.67  4890.8  285.52  4937.2  283.59  4959.4  283.80  4965.5  284.03
  4973.2  281.34  4978.4  283.46  4986.1  282.01  5007.0  281.59  5017.5  279.35
  5028.0  280.17  5036.6  277.87  5036.8  277.37  5040.3  277.37  5040.6  277.87
  5049.1  284.09  5059.7  283.92  5070.2  284.95  5077.4  286.21  5080.7  286.79
  5091.3  287.82  5112.4  289.07  5122.9  288.98  5133.5  289.71  5154.5  290.49
#Mann=5,-1,0
  4790.3    0.12       0  4959.4    0.05       0  5036.6    0.05       0
  5040.6    0.05       0  5077.4    0.12       0
Bank Sta=5036.6,5040.6
Exp/Cntr=0.3,0.1

Type RM Length L Ch R = 1,4269,483,483,483
BEGIN DESCRIPTION:
Stream0494 9.0
END DESCRIPTION:
XS GIS Cut Line= 3
      2528425.02     13642725.01      2528125.00     13642625.00
      2527974.96     13642574.99
#Sta/Elev= 30
  4691.9  295.32  4711.1  294.02  4765.7  291.36  4776.2  290.06  4786.8  289.12
  4818.4  286.81  4850.0  285.27  4860.6  284.33  4871.1  284.25  4881.7  283.68
  4892.2  282.82  4902.7  283.07  4913.3  284.93  4923.8  281.96  4944.9  279.64
  4948.6  279.57  4966.0  279.67  4976.5  279.03  4995.6  274.04  4995.9  273.54
  4999.4  273.54  4999.6  274.04  5005.5  276.95  5010.8  276.95  5018.7  280.00
  5029.2  281.03  5039.8  281.41  5103.0  281.85  5134.6  282.78  5166.3  284.27
#Mann=5,-1,0
  4691.9    0.05       0  4711.1    0.12       0  4948.6    0.05       0
  4995.6    0.05       0  4999.6    0.05       0
Bank Sta=4995.6,4999.6
Exp/Cntr=0.3,0.1

Type RM Length L Ch R = 1,3786,475,475,475
BEGIN DESCRIPTION:
Stream0494 8.0
END DESCRIPTION:
XS GIS Cut Line= 3
      2528374.96     13642274.98      2528125.00     13642175.00
      2527825.02     13642324.99
#Sta/Elev= 30
  4730.8  287.20  4755.4  285.68  4763.0  285.43  4829.0  281.20  4853.3  280.22
  4907.1  279.44  4913.8  278.37  4924.6  279.25  4936.7  277.56  4946.2  275.30
  4961.0  274.58  4965.7  272.14  4966.0  271.64  4969.5  271.64  4969.7  272.14
  4977.7  273.69  4990.6  277.01  4997.3  279.52  5002.8  279.52  5008.4  280.88
  5075.5  280.63  5103.4  281.50  5111.8  280.97  5148.2  282.40  5205.0  283.56
  5268.3  285.51  5282.3  287.21  5299.1  287.20  5304.7  287.96  5335.4  288.87
#Mann=7,-1,0
  4730.8    0.12       0  4755.4    0.05       0  4763.0    0.12       0
  4965.7    0.05       0  4969.7    0.12       0  4977.7    0.05       0
  5205.0    0.07       0
Bank Sta=4965.7,4969.7
Exp/Cntr=0.3,0.1

Type RM Length L Ch R = 1,3311,485,485,485
BEGIN DESCRIPTION:
Stream0494 7.0
END DESCRIPTION:
XS GIS Cut Line= 3
      2528175.04     13641624.97      2527975.00     13641775.00
      2527639.49     13641982.24
#Sta/Elev= 30
  4749.5  282.87  4799.5  281.11  4871.4  277.25  4905.1  276.95  4921.4  277.31
  4936.0  276.95  4971.4  272.96  5013.1  273.17  5028.5  272.43  5032.8  268.94
  5033.1  268.44  5036.6  268.44  5036.8  268.94  5039.6  269.95  5043.9  271.50
  5049.8  272.04  5058.3  275.34  5065.2  275.86  5080.6  276.12  5123.1  278.67
  5187.6  281.06  5211.1  280.89  5252.6  282.12  5303.1  284.21  5333.5  285.73
  5340.4  286.58  5354.8  285.94  5370.2  287.90  5376.1  287.82  5393.9  289.28
#Mann=7,-1,0
  4749.5    0.07       0  4905.1    0.12       0  5032.8    0.05       0
  5036.8    0.12       0  5039.6    0.07       0  5252.6    0.05       0
  5303.1    0.07       0
Bank Sta=5032.8,5036.8
Exp/Cntr=0.3,0.1

Type RM Length L Ch R = 1,2826,465,465,465
BEGIN DESCRIPTION:
Stream0494 6.0
END DESCRIPTION:
XS GIS Cut Line= 3
      2528074.99     13641325.00      2527875.00     13641325.00
      2527575.02     13641424.99
#Sta/Elev= 30
  4800.1  279.06  4850.1  276.41  4860.1  276.29  4890.1  274.90  4980.1  272.07
  4988.5  271.44  4997.6  270.05  5002.7  270.05  5031.7  267.46  5040.3  267.11
  5040.5  266.61  5044.0  266.61  5044.3  267.11  5052.8  267.52  5063.3  268.79
  5073.9  269.53  5095.0  273.08  5105.5  272.98  5139.4  273.76  5147.7  274.32
  5158.2  275.77  5189.8  276.84  5200.4  276.77  5221.4  277.69  5232.0  277.82
  5242.5  278.57  5263.6  279.00  5274.2  279.66  5284.7  279.94  5316.3  282.12
#Mann=5,-1,0
  4800.1    0.07       0  4988.5     0.1       0  5040.3    0.05       0
  5044.3     0.1       0  5139.4    0.05       0
Bank Sta=5040.3,5044.3
Exp/Cntr=0.3,0.1

Type RM Length L Ch R = 1,2361,465,465,465
BEGIN DESCRIPTION:
Stream0494 5.0
END DESCRIPTION:
XS GIS Cut Line= 3
      2527775.05     13640924.98      2527625.00     13640975.00
      2527524.97     13641025.02
#Sta/Elev= 29
  4845.7  275.48  4848.4  275.48  4866.8  274.42  4909.0  273.41  4919.5  273.27
  4940.6  271.91  4966.5  268.73  4982.8  266.87  4993.3  265.93  5001.2  262.34
  5006.7  262.34  5010.2  259.25  5010.5  258.75  5014.0  258.75  5014.2  259.25
  5017.8  259.50  5026.2  265.21  5030.8  268.44  5034.6  271.10  5040.2  270.32
  5048.6  272.84  5057.0  274.01  5062.6  274.22  5070.9  274.85  5079.3  275.17
  5084.9  276.51  5107.3  277.46  5112.9  277.89  5115.7  277.89
#Mann=5,-1,0
  4845.7    0.07       0  4966.5    0.12       0  5010.2    0.05       0
  5014.2    0.12       0  5030.8    0.07       0
Bank Sta=5010.2,5014.2
Exp/Cntr=0.3,0.1

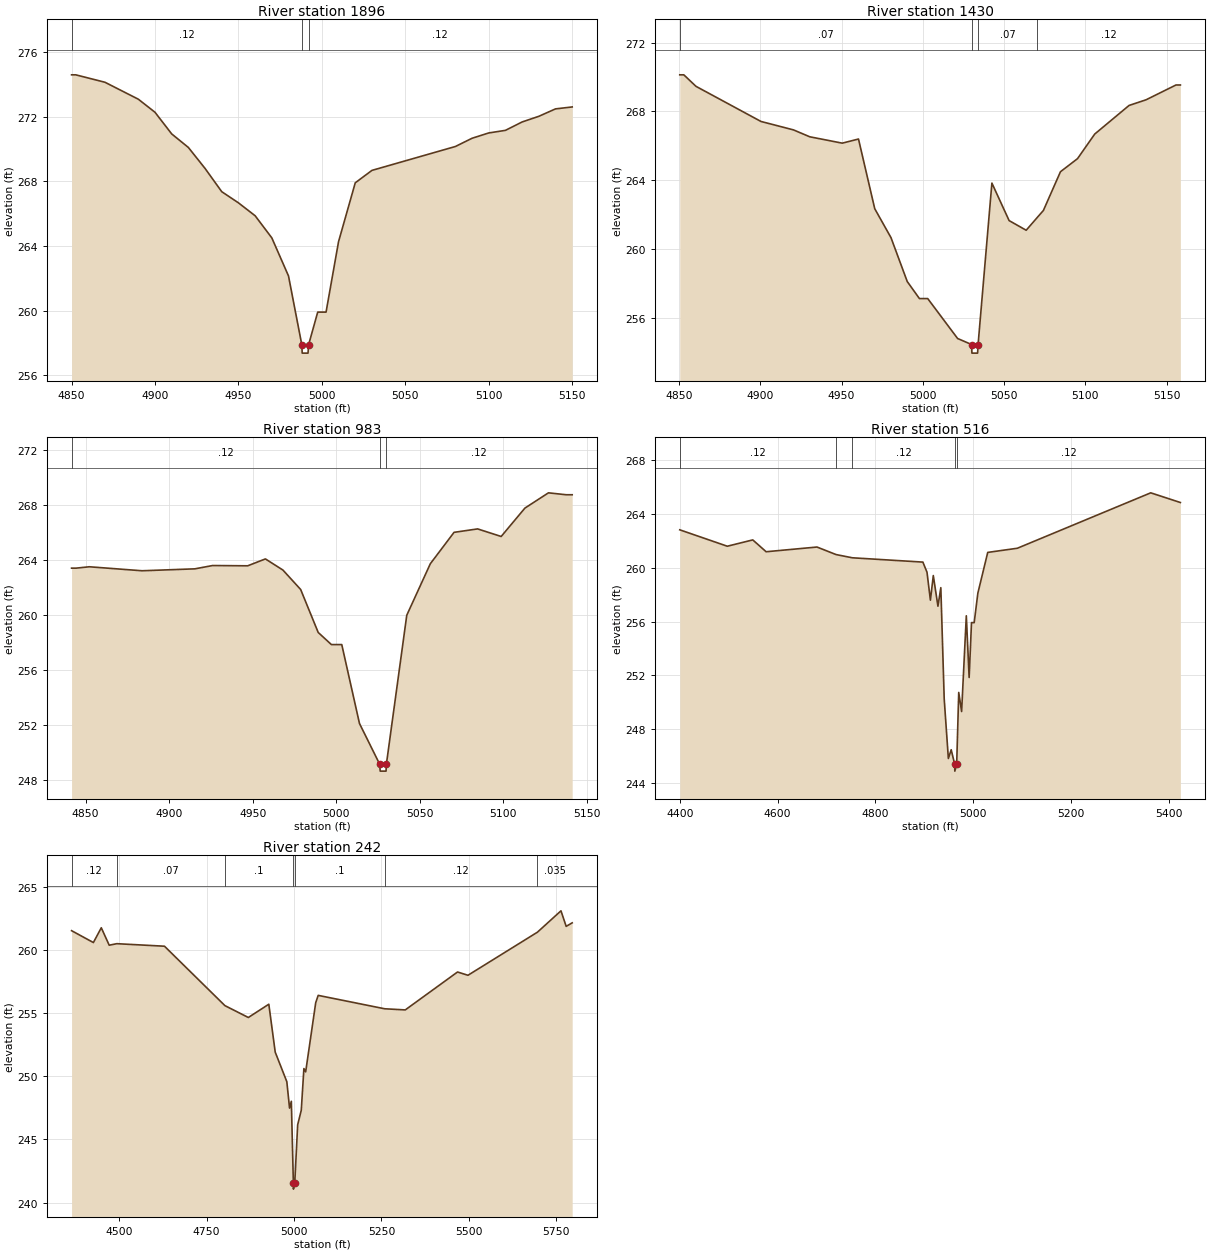
Type RM Length L Ch R = 1,1896,466,466,466
BEGIN DESCRIPTION:
Stream0494 4.0
END DESCRIPTION:
XS GIS Cut Line= 3
      2527724.99     13640525.00      2527575.00     13640525.00
      2527424.99     13640525.00
#Sta/Elev= 30
  4850.0  274.60  4852.5  274.60  4870.0  274.14  4890.0  273.09  4900.0  272.28
  4910.0  270.94  4920.0  270.10  4930.0  268.80  4940.0  267.36  4950.0  266.67
  4960.0  265.87  4970.0  264.50  4980.0  262.14  4988.0  257.86  4988.2  257.36
  4991.7  257.36  4992.0  257.86  4997.5  259.90  5002.5  259.90  5010.0  264.27
  5020.0  267.91  5030.0  268.68  5080.0  270.16  5090.0  270.67  5100.0  271.00
  5110.0  271.16  5120.0  271.68  5130.0  272.03  5140.0  272.49  5150.0  272.61
#Mann=3,-1,0
  4850.0    0.12       0  4988.0    0.05       0  4992.0    0.12       0
Bank Sta=4988,4992
Exp/Cntr=0.3,0.1

Type RM Length L Ch R = 1,1430,447,447,447
BEGIN DESCRIPTION:
Stream0494 3.0
END DESCRIPTION:
XS GIS Cut Line= 3
      2527674.97     13640075.00      2527525.00     13640075.00
      2527374.98     13640125.01
#Sta/Elev= 30
  4850.4  270.13  4852.9  270.13  4860.4  269.46  4900.4  267.42  4920.4  266.93
  4930.4  266.53  4950.4  266.16  4960.4  266.40  4970.4  262.35  4980.4  260.67
  4990.4  258.12  4997.9  257.13  5003.0  257.13  5021.4  254.81  5030.0  254.46
  5030.2  253.96  5033.7  253.96  5034.0  254.46  5042.5  263.84  5053.1  261.66
  5063.6  261.10  5070.4  261.84  5074.2  262.25  5084.7  264.50  5095.2  265.26
  5105.8  266.69  5126.9  268.35  5137.4  268.68  5155.8  269.54  5158.5  269.54
#Mann=4,-1,0
  4850.4    0.07       0  5030.0    0.05       0  5034.0    0.07       0
  5070.4    0.12       0
Bank Sta=5030,5034
Exp/Cntr=0.3,0.1

Type RM Length L Ch R = 1,983,467,467,467
BEGIN DESCRIPTION:
Stream0494 2.0
END DESCRIPTION:
XS GIS Cut Line= 3
      2527475.03     13639674.99      2527325.00     13639725.00
      2527224.97     13639825.03
#Sta/Elev= 28
  4841.6  263.39  4844.3  263.39  4852.2  263.49  4883.8  263.20  4915.4  263.34
  4926.0  263.58  4947.0  263.56  4957.6  264.06  4968.1  263.25  4978.7  261.84
  4989.2  258.72  4997.1  257.84  4999.7  257.84  5003.3  257.84  5013.9  252.11
  5026.0  249.15  5026.3  248.65  5029.8  248.65  5030.0  249.15  5042.2  259.97
  5056.3  263.71  5070.5  265.99  5084.6  266.24  5098.7  265.69  5112.9  267.75
  5127.0  268.86  5137.6  268.72  5141.2  268.72
#Mann=3,-1,0
  4841.6    0.12       0  5026.0    0.05       0  5030.0    0.12       0
Bank Sta=5026,5030
Exp/Cntr=0.3,0.1

Type RM Length L Ch R = 1,516,274,274,274
BEGIN DESCRIPTION:
Stream0494 1.0
END DESCRIPTION:
XS GIS Cut Line= 3
      2527735.36     13639639.40      2527225.00     13639325.00
      2526804.96     13639384.10
#Sta/Elev= 30
  4400.1  262.82  4497.3  261.60  4549.4  262.07  4576.7  261.19  4680.7  261.54
  4719.7  260.98  4753.1  260.74  4897.2  260.42  4905.6  259.67  4912.6  257.59
  4918.5  259.42  4928.0  257.14  4933.9  258.52  4940.8  250.25  4949.3  245.82
  4955.1  246.47  4962.3  245.38  4962.5  244.88  4966.3  245.38  4970.5  250.73
  4976.4  249.31  4986.0  256.43  4991.8  251.84  4996.6  255.92  5002.1  255.92
  5009.6  258.11  5029.8  261.14  5090.4  261.45  5363.1  265.57  5423.7  264.85
#Mann=5,-1,0
  4400.1    0.12       0  4719.7    0.07       0  4753.1    0.12       0
  4962.3    0.05       0  4966.3    0.12       0
Bank Sta=4962.3,4966.3
Exp/Cntr=0.3,0.1

Type RM Length L Ch R = 1,242,0,0,0
BEGIN DESCRIPTION:
XS6934
END DESCRIPTION:
XS GIS Cut Line= 4
      2527637.94     13639534.37      2527432.32     13639107.31
      2527036.92     13639007.15      2526583.53     13639318.19
#Sta/Elev= 30
  4363.8  261.51  4426.2  260.57  4448.8  261.74  4471.4  260.36  4493.2  260.48
  4629.5  260.28  4802.3  255.58  4869.3  254.64  4927.9  255.69  4946.2  251.90
  4979.4  249.56  4987.2  247.47  4992.3  248.01  4998.1  241.56  4998.3  241.06
  5002.1  241.56  5010.4  246.15  5020.7  247.30  5028.2  250.60  5033.3  250.34
  5062.0  255.81  5069.1  256.39  5259.3  255.33  5318.1  255.24  5467.6  258.24
  5497.4  257.98  5696.1  261.39  5763.4  263.08  5778.3  261.85  5795.5  262.13
#Mann=7,-1,0
  4363.8    0.12       0  4493.2    0.07       0  4802.3     0.1       0
  4998.1    0.05       0  5002.1     0.1       0  5259.3    0.12       0
  5696.1   0.035       0
Bank Sta=4998.1,5002.1
Exp/Cntr=0.3,0.1

Chan Stop Cuts=-1