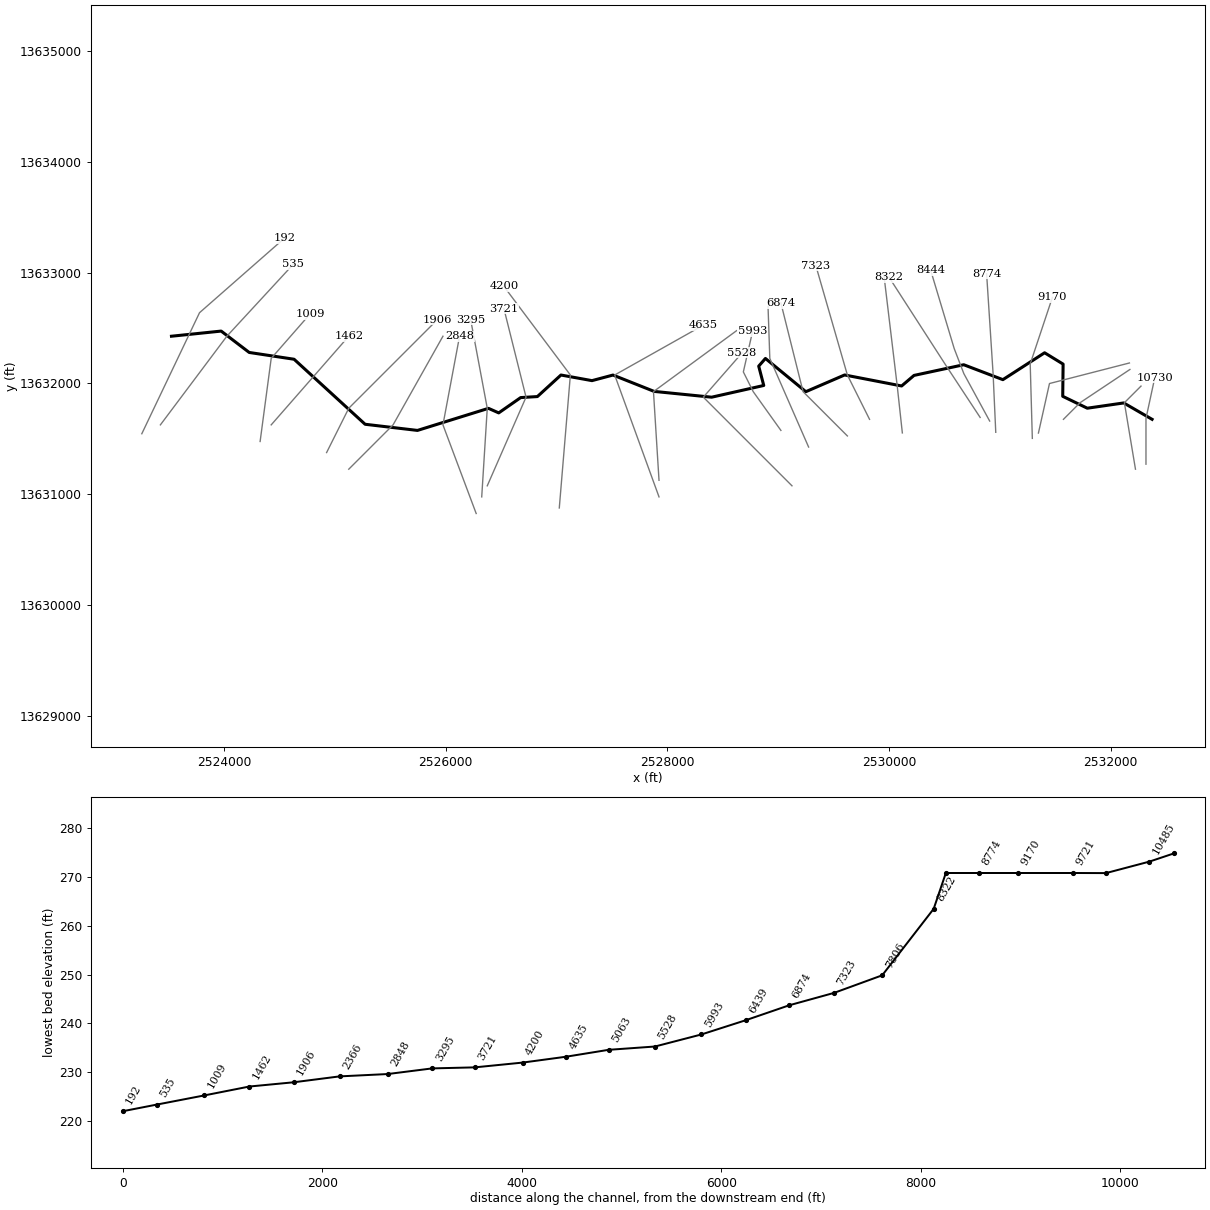
--- Stream0495.prj (project) ---

Proj Title=Stream0495 Base Level Engineering
Current Plan=p01
Default Exp/Contr=0.3,0.1
English Units
Geom File=g01
Flow File=f01
Plan File=p01
Y Axis Title=Elevation
X Axis Title(PF)=Main Channel Distance
X Axis Title(XS)=Station
BEGIN DESCRIPTION:
Stream0495
END DESCRIPTION:
DSS File=dss
DSS Export Rating Curves= 0
DSS Export Rating Curve Sorted= 0
DSS Export Volume Flow Curves= 0
DXF OffsetX= 0
DXF OffsetY= 0
DXF ScaleX= 1
DXF ScaleY= 10

--- Stream0495.p01 (plan) ---

Plan Title=Multiple Run
Program Version=4.10
Short Identifier=Multiple Run
Geom File=g01
Flow File=f01
Subcritical Flow
K Sum by GR= 0
Std Step Tol= 0.01
Critical Tol= 0.01
Num of Std Step Trials= 20
Max Error Tol= 0.3
Flow Tol Ratio= 0.001
Split Flow NTrial= 30
Split Flow Tol= 0.02
Split Flow Ratio= 0.02
Log Output Level= 0
Friction Slope Method= 1
Unsteady Friction Slope Method= 2
Unsteady Bridges Friction Slope Method= 1
Parabolic Critical Depth
Global Vel Dist= 1 , 1 , 1
Global Log Level= 0
CheckData=True
Encroach Param=-1 ,0,0, 0
BEGIN DESCRIPTION:
Multiple Run
END DESCRIPTION:
Computation Interval=1HOUR
Output Interval=1HOUR
Run HTab= 0
Run UNet= 0
Run PostProcess= 0
Run WQNet= 0
UNET Theta= 1
UNET Theta Warmup= 1
UNET ZTol= 0.02
UNET ZSATol= 0.05
UNET MxIter= 20
UNET MaxInSteps= 0
UNET DtIC= 0
UNET DtMin= 0
UNET MaxCRTS= 20
UNET WFStab= 2
UNET SFStab= 1
UNET WFX= 1
UNET SFX= 1
UNET DSS MLevel= 4
UNET DZMax Abort= 100
UNET Convert EG Bridges= 0
UNET Use Existing IB Tables=-1
UNET Froude Reduction=False
UNET Froude Limit= 1
UNET Froude Power= 10
UNET Time Slicing=0,0, 5
UNET Junction Losses=0
Instantaneous Interval=1HOUR
DSS File=dss
Write IC File= 0
Write IC File at Sim End=0
Echo Input=False
Echo Parameters=False
Echo Output=False
Write Detailed= 0
WQ AD Non Conservative
WQ ULTIMATE=-1
WQ Max Comp Step=1HOUR
WQ Output Interval=15MIN
WQ Output Selected Increments= 0
WQ Output face flow=0
WQ Output face velocity=0
WQ Output face area=0
WQ Output face dispersion=0
WQ Output cell volume=0
WQ Output cell surface area=0
WQ Output cell continuity=0
WQ Output cumulative cell continuity=0
WQ Output face conc=0
WQ Output face dconc_dx=0
WQ Output face courant=0
WQ Output face peclet=0
WQ Output face adv mass=0
WQ Output face disp mass=0
WQ Output cell mass=0
WQ Output cell source sink temp=0
WQ Output cell source sink nsm=0
WQ Output MaxMinRange=-1
WQ Daily Max Min Mean=-1
WQ Daily Range=0
WQ Daily Time=0
WQ Create Restart=0
WQ Fixed Restart=0
WQ System Summary=0
WQ Use Fixed Temperature=0
Sorting and Armoring Iterations= 10
XS Update Threshold= 0.02
Hydraulics Update Threshold= 0.02
Energy Slope Method= 1
Volume Change Method= 0
XS Weighting Method= 0
Number of US Weighted Cross Sections= 1
Number of DS Weighted Cross Sections= 1
Upstream XS Weight=0.25
Main XS Weight=0.5
Downstream XS Weight=0.25
Number of DS XS's Weighted with US Boundary= 1
Upstream Boundary Weight= 1
Weight of XSs Associated with US Boundary= 0
Number of US XS's Weighted with DS Boundary= 1
Downstream Boundary Weight= 0.5
Weight of XSs Associated with DS Boundary= 0.5
Sediment Output Level= 4
Mass or Volume Output= 0
Output Increment Type= 1
Profile and TS Output Increment= 10
XS Output Flag= 0
XS Output Increment= 10
Disregard all LS=0
Disregard all Conn=0
Disregard all Breaches=0
Disregard all Pumps=0

--- Stream0495.f01 (steady flow) ---

Flow Title=Multiple
Number of Profiles=7
Profile Names=10-year,25-year,50-year,1pct_min,100-year,1pct_plu,500-year
River Rch & RM= Stream0495,Reach-1,10730
     730    1172    1571    1020    2036    4062    3380
River Rch & RM= Stream0495,Reach-1,7323
     781    1264    1703    1111    2217    4423    3718
River Rch & RM= Stream0495,Reach-1,5063
     957    1568    2129    1399    2791    5569    4748
River Rch & RM= Stream0495,Reach-1,4200
    1270    2109    2888    1912    3814    7611    6591
River Rch & RM= Stream0495,Reach-1,3295
    1532    2557    3513    2331    4651    9281    8076
Boundary for River Rch & Prof#=Stream0495,Reach-1,1
Up Type=0
Dn Type=3
Dn Slope=0.005
Boundary for River Rch & Prof#=Stream0495,Reach-1,2
Up Type=0
Dn Type=3
Dn Slope=0.005
Boundary for River Rch & Prof#=Stream0495,Reach-1,3
Up Type=0
Dn Type=3
Dn Slope=0.005
Boundary for River Rch & Prof#=Stream0495,Reach-1,4
Up Type=0
Dn Type=3
Dn Slope=0.005
Boundary for River Rch & Prof#=Stream0495,Reach-1,5
Up Type=0
Dn Type=3
Dn Slope=0.005
Boundary for River Rch & Prof#=Stream0495,Reach-1,6
Up Type=0
Dn Type=3
Dn Slope=0.005
Boundary for River Rch & Prof#=Stream0495,Reach-1,7
Up Type=0
Dn Type=3
Dn Slope=0.005

--- Stream0495.g01 (geometry) ---

Geom Title=Existing Conditions
Program Version=4.10

River Reach=Stream0495      ,Reach-1
Reach XY= 30
        2532375.       13631675.      2532119.14     13631822.95
      2531790.17     13631775.37       2531568.5     13631882.73
      2531571.88     13632173.38      2531404.93     13632275.68
      2531028.32     13632033.04       2530675.1     13632167.67
       2530226.5     13632071.38      2530114.56     13631976.06
        2529600.      13632075.4      2529249.96     13631924.49
      2528885.45     13632224.48      2528824.75     13632155.08
      2528870.24     13631980.58      2528400.08      13631874.8
      2527880.85     13631927.08      2527509.73     13632074.62
      2527319.97     13632024.19      2527040.05     13632074.88
      2526827.45     13631880.47      2526676.53     13631871.25
      2526478.34     13631733.06      2526385.71     13631774.19
       2525745.1     13631574.91      2525272.55     13631630.46
      2524631.48     13632217.31      2524226.47     13632278.55
      2523973.53     13632471.45        2523525.       13632425.

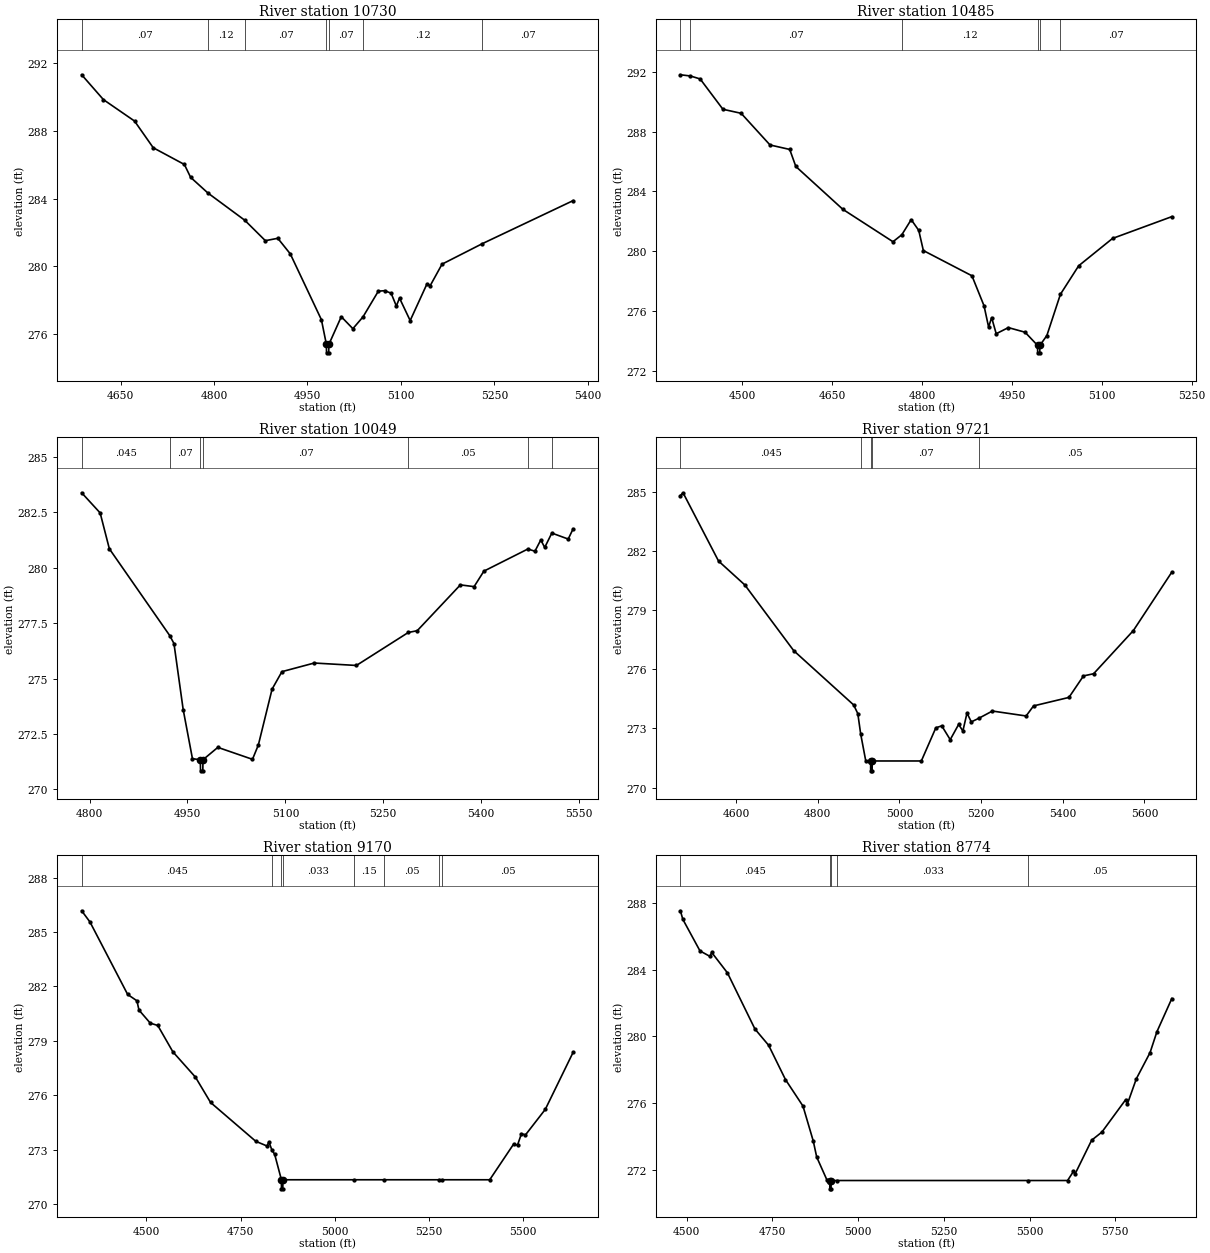
Type RM Length L Ch R = 1 ,10730   ,245,245,245
BEGIN DESCRIPTION:
XS6935
END DESCRIPTION:
XS GIS Cut Line= 3
      2532319.71     13631270.14      2532319.71      13631682.4
      2532399.14     13632050.67
#Sta/Elev= 30
  4587.5  291.33  4622.4  289.86  4672.4  288.59  4702.4  287.01  4752.4  286.02
  4762.4  285.26  4790.2  284.33  4849.3  282.72  4882.4  281.51  4902.4  281.65
  4922.4  280.73  4972.4  276.83  4980.4  275.37  4980.6  274.87  4984.1  274.87
  4984.4  275.37  5004.3  277.01  5022.9   276.3  5039.2     277  5063.8  278.52
    5074  278.55  5084.3   278.4  5092.7  277.64  5097.8  278.11  5114.9  276.78
    5142  278.96  5147.1  278.85  5166.1  280.12  5230.6  281.33  5376.5  283.88
#Mann= 7 ,-1 , 0
  4587.5     .07       0  4790.2     .12       0  4849.3     .07       0
  4980.4     .05       0  4984.4     .07       0  5039.2     .12       0
  5230.6     .07       0
Bank Sta=4980.4,4984.4
XS Rating Curve= 0 ,0
Exp/Cntr=0.3,0.1

Type RM Length L Ch R = 1 ,10485   ,436,436,436
BEGIN DESCRIPTION:
Stream0495 23.0
END DESCRIPTION:
XS GIS Cut Line= 3
      2532225.01     13631224.97        2532125.       13631825.
      2532274.97     13631974.97
#Sta/Elev= 30
  4396.4  291.81  4413.1  291.73  4429.4  291.53  4467.4   289.5  4497.8  289.23
    4546  287.11  4578.9  286.81  4589.1  285.67  4667.6   282.8  4751.3  280.63
  4766.1   281.1  4781.7  282.11  4794.3  281.39    4802  280.04  4883.1  278.35
  4903.3  276.34  4910.9  274.92    4916  275.55  4923.6  274.47  4943.9  274.88
  4971.8  274.57  4992.6  273.69  4992.8  273.19  4996.3  273.19  4996.6  273.69
  5008.2  274.35  5030.8  277.11  5061.3  279.02  5117.8  280.85  5216.8  282.31
#Mann= 6 ,-1 , 0
  4396.4     .05       0  4413.1     .07       0  4766.1     .12       0
  4992.6     .05       0  4996.6     .12       0  5030.8     .07       0
Bank Sta=4992.6,4996.6
XS Rating Curve= 0 ,0
Exp/Cntr=0.3,0.1

Type RM Length L Ch R = 1 ,10049   ,328,328,328
BEGIN DESCRIPTION:
Stream0495 22.0
END DESCRIPTION:
XS GIS Cut Line= 3
      2531575.01     13631675.01        2531725.       13631825.
      2532174.96     13632124.98
#Sta/Elev= 30
  4787.9  283.39  4816.2  282.48  4830.3  280.86  4922.8  276.94  4929.3  276.58
  4943.4   273.6  4957.6  271.38  4969.7  271.33    4970  270.83  4973.5  270.83
  4973.7  271.33  4996.5  271.89  5049.6  271.35  5058.6     272  5079.6  274.52
  5094.7  275.31  5144.2   275.7  5208.8  275.59  5288.3  277.08    5302  277.16
  5368.1  279.23  5389.1  279.15  5404.1  279.85  5471.5  280.85  5482.3  280.75
  5491.3  281.26  5497.3  280.92  5508.2  281.57  5533.3   281.3  5540.8  281.76
#Mann= 7 ,-1 , 0
  4787.9    .045       0  4922.8     .07       0  4969.7     .05       0
  4973.7     .07       0  5288.3     .05       0  5471.5     .07       0
  5508.2     .05       0
Bank Sta=4969.7,4973.7
XS Rating Curve= 0 ,0
Exp/Cntr=0.3,0.1

Type RM Length L Ch R = 1 ,9721    ,551,551,551
BEGIN DESCRIPTION:
Stream0495 21.0
END DESCRIPTION:
XS GIS Cut Line= 3
      2531349.18     13631551.08      2531448.89     13631998.08
      2532170.43     13632183.62
#Sta/Elev= 30
  4463.9   284.8  4470.4  284.94  4557.3  281.48  4621.6  280.27  4741.3  276.94
    4888  274.19  4898.2  273.75  4905.2  272.72  4917.7  271.35  4929.5  271.35
  4929.7  270.85  4933.2  270.85  4933.5  271.35  5053.7  271.35  5089.2  273.03
  5103.7  273.13  5124.4  272.43    5145   273.2  5155.4  272.87  5165.5  273.78
    5176  273.33  5194.1  273.51  5227.6  273.88  5310.2  273.63  5328.4  274.14
    5415  274.57  5450.6  275.66  5475.4  275.77  5572.8  277.96  5666.9  280.92
#Mann= 5 ,-1 , 0
  4463.9    .045       0  4905.2     .07       0  4929.5     .05       0
  4933.5     .07       0  5194.1     .05       0
Bank Sta=4929.5,4933.5
XS Rating Curve= 0 ,0
Exp/Cntr=0.3,0.1

Type RM Length L Ch R = 1 ,9170    ,396,396,396
BEGIN DESCRIPTION:
Stream0495 20.0
END DESCRIPTION:
XS GIS Cut Line= 3
      2531294.17     13631502.96        2531275.       13632175.
      2531475.01     13632775.03
#Sta/Elev= 30
    4328  286.17  4350.1  285.55  4450.1  281.56  4474.7  281.21  4480.1   280.7
  4510.1  279.98  4530.1  279.85  4570.1   278.4  4630.2     277  4670.2  275.61
  4790.2  273.47  4820.1  273.21  4825.1  273.44  4833.2  272.98  4840.3  272.76
  4858.3  271.35  4858.5  270.85    4862  270.85  4862.3  271.35  5050.4  271.35
  5130.7  271.35  5276.4  271.35  5283.8  271.35  5411.4  271.35  5474.7  273.31
  5485.2  273.26  5495.7  273.89  5506.3  273.82    5559  275.23  5632.8  278.37
#Mann= 8 ,-1 , 0
    4328    .045       0  4833.2    .033       0  4858.3    .033       0
  4862.3    .033       0  5050.4     .15       0  5130.7     .05       0
  5276.4     .07       0  5283.8     .05       0
Bank Sta=4858.3,4862.3
XS Rating Curve= 0 ,0
Exp/Cntr=0.3,0.1

Type RM Length L Ch R = 1 ,8774    ,330,330,330
BEGIN DESCRIPTION:
Stream0495 19.0
END DESCRIPTION:
XS GIS Cut Line= 3
       2530964.1     13631557.97      2530940.03     13632087.47
      2530881.58     13632988.33
#Sta/Elev= 30
  4482.1  287.55  4489.1  287.04  4539.2  285.14  4568.3  284.81  4573.3  285.05
  4619.3  283.82  4699.4  280.45  4739.4  279.47  4788.5  277.41  4839.5  275.82
  4869.5  273.72  4879.5  272.76  4909.6  271.37  4917.6  271.35  4917.8  270.85
  4921.3  270.85  4921.6  271.35  4940.1  271.35  5494.4  271.35  5610.9  271.35
  5628.2   271.9  5633.2  271.76  5681.1  273.77  5711.1  274.26  5780.5  276.21
  5785.6  275.96  5811.4  277.46  5851.4  279.03  5871.5  280.29  5914.9  282.28
#Mann= 5 ,-1 , 0
  4482.1    .045       0  4917.6    .033       0  4921.6    .045       0
  4940.1    .033       0  5494.4     .05       0
Bank Sta=4917.6,4921.6
XS Rating Curve= 0 ,0
Exp/Cntr=0.3,0.1

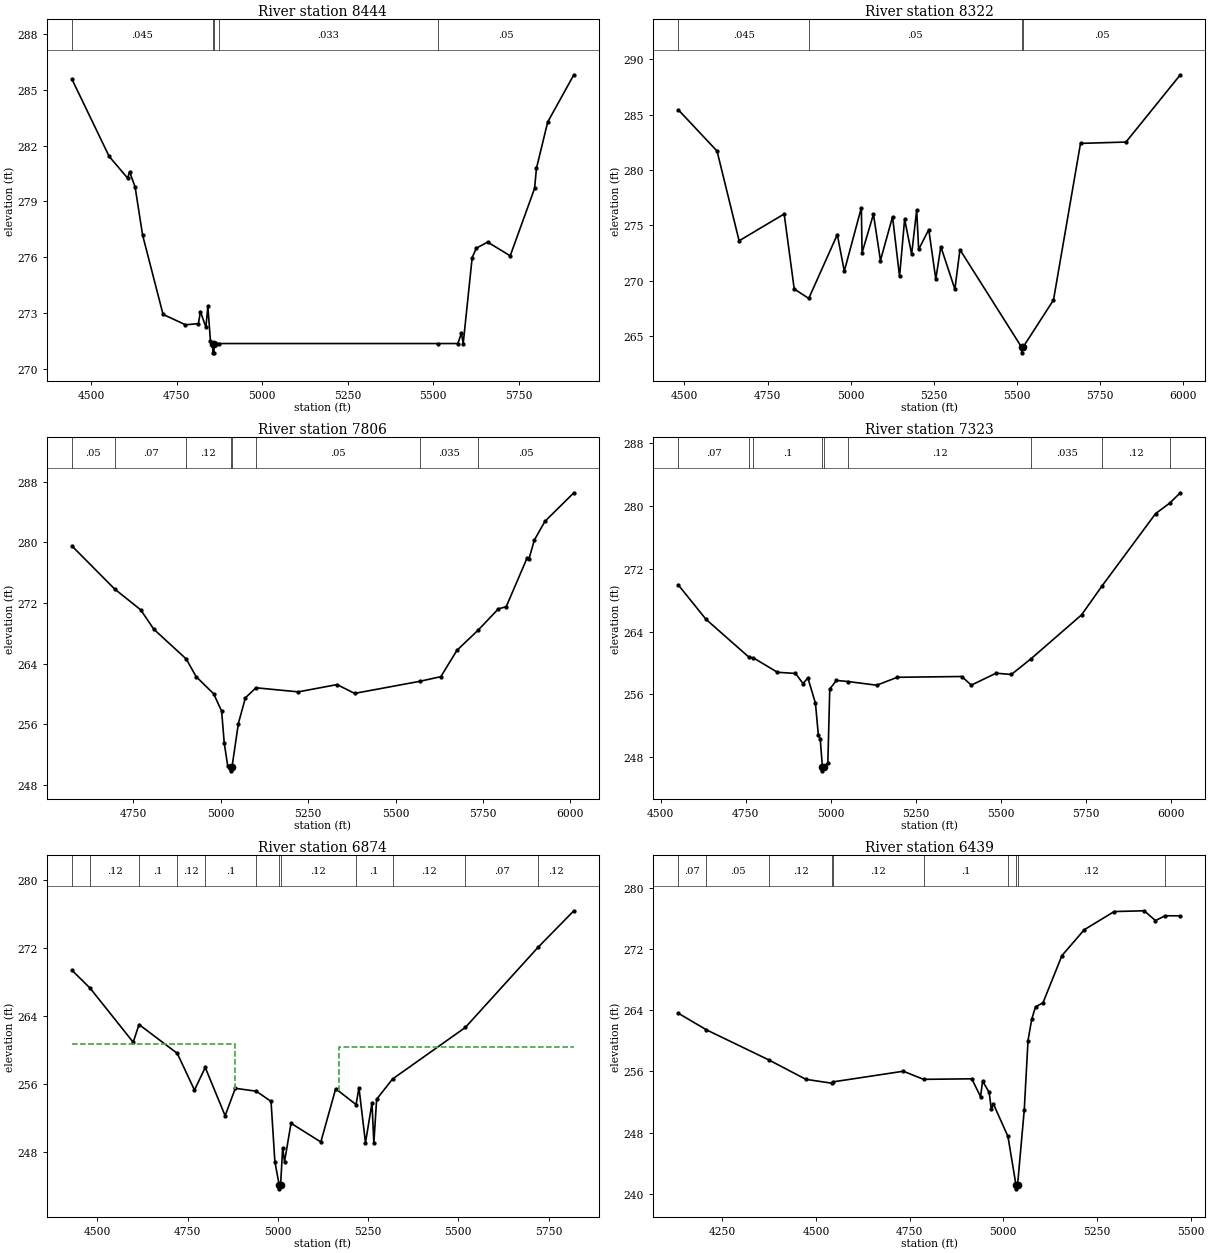
Type RM Length L Ch R = 1 ,8444    ,122,122,122
BEGIN DESCRIPTION:
E21108
END DESCRIPTION:
XS GIS Cut Line= 4
      2530909.15     13631659.56      2530676.08     13632087.42
      2530589.12     13632313.53      2530376.93     13633019.66
#Sta/Elev= 30
    4444  285.57  4552.7  281.42  4606.7  280.25  4612.4  280.59  4628.5  279.78
  4650.4  277.19  4710.2  272.92  4775.7  272.36  4813.7  272.42  4819.4  273.07
  4835.5  272.23  4841.2  273.35  4848.8  271.47  4855.4  271.35  4855.6  270.85
  4859.1  270.85  4859.4  271.35  4873.1  271.35  5514.4  271.35  5571.8  271.35
  5582.2  271.91  5587.4  271.35  5613.6  275.97  5625.7  276.48  5658.7  276.81
  5724.8  276.07  5796.1   279.7  5801.5  280.78  5834.4  283.27  5910.8  285.81
#Mann= 5 ,-1 , 0
    4444    .045       0  4855.4    .033       0  4859.4    .045       0
  4873.1    .033       0  5514.4     .05       0
Bank Sta=4855.4,4859.4
XS Rating Curve= 0 ,0
Exp/Cntr=0.3,0.1

Type RM Length L Ch R = 1 ,8322    ,516,516,516
BEGIN DESCRIPTION:
Stream0495 18.0
END DESCRIPTION:
XS GIS Cut Line= 3
      2530823.15     13631692.04      2530519.55     13632153.52
      2530001.24     13632957.07
#Sta/Elev= 30
  4481.9  285.42    4598  281.71  4664.3  273.61  4799.8  276.03    4830  269.26
  4873.7  268.41  4959.5  274.17  4980.5  270.87  5031.8   276.6  5033.9  272.53
  5068.1  276.01  5089.2  271.83  5125.5  275.78  5146.6  270.39  5161.8  275.55
  5182.9   272.4  5198.1  276.37    5204  272.83  5234.4  274.62  5255.5  270.15
  5270.7  273.08  5312.9  269.24  5328.1  272.81  5513.6     264  5513.8   263.5
  5517.6     264  5609.3  268.27  5690.5   282.4  5827.1  282.52  5990.5  288.59
#Mann= 4 ,-1 , 0
  4481.9    .045       0  4873.7     .05       0  5513.6     .05       0
  5517.6     .05       0
Bank Sta=5513.6,5517.6
XS Rating Curve= 0 ,0
Exp/Cntr=0.3,0.1

Type RM Length L Ch R = 1 ,7806    ,483,483,483
BEGIN DESCRIPTION:
Stream0495 17.0
END DESCRIPTION:
XS GIS Cut Line= 3
      2530121.01     13631552.26        2530075.       13631975.
      2529954.66     13632977.06
#Sta/Elev= 30
  4575.2  279.53  4697.3  273.85  4771.8   271.1  4809.3  268.54  4901.8  264.62
    4930   262.3  4980.3  260.02    5003  257.74  5010.5  253.51  5020.6  250.46
  5028.7  250.36  5028.9  249.86  5032.7  250.36  5050.8   256.1  5070.9  259.49
    5101  260.82    5222  260.28  5332.8  261.24  5383.2  260.08  5570.1  261.68
  5629.7  262.29  5675.3  265.75    5737  268.46  5794.1  271.24  5816.3  271.51
  5876.4  277.98  5881.4  277.82  5896.8  280.31    5927  282.78  6009.7  286.55
#Mann= 8 ,-1 , 0
  4575.2     .05       0  4697.3     .07       0  4901.8     .12       0
  5028.7     .05       0  5032.7     .12       0    5101     .05       0
  5570.1    .035       0    5737     .05       0
Bank Sta=5028.7,5032.7
XS Rating Curve= 0 ,0
Exp/Cntr=0.3,0.1

Type RM Length L Ch R = 1 ,7323    ,449,449,449
BEGIN DESCRIPTION:
Stream0495 16.0
END DESCRIPTION:
XS GIS Cut Line= 3
      2529825.02     13631674.97        2529625.       13632075.
       2529340.5     13633061.75
#Sta/Elev= 30
  4551.9  269.94    4633  265.57  4758.9  260.75  4772.3  260.65  4842.6  258.82
  4895.7  258.67  4918.1  257.38  4932.1   258.1  4954.4  254.88  4962.8  250.85
  4968.4  250.36  4974.8  246.75    4975  246.25  4978.8  246.75  4990.8  247.28
  4996.4  256.68    5016  257.78    5050  257.64  5134.4  257.17  5194.7  258.18
  5384.2  258.28  5412.2  257.18  5484.8   258.7  5529.9  258.54  5587.8  260.55
    5736  266.14  5796.7  269.86  5953.6  279.06  5994.6  280.38  6026.1  281.71
#Mann= 9 ,-1 , 0
  4551.9     .07       0  4758.9     .12       0  4772.3      .1       0
  4974.8     .05       0  4978.8      .1       0    5050     .12       0
  5587.8    .035       0  5796.7     .12       0  5994.6    .035       0
Bank Sta=4974.8,4978.8
XS Rating Curve= 0 ,0
Exp/Cntr=0.3,0.1

Type RM Length L Ch R = 1 ,6874    ,435,435,435
BEGIN DESCRIPTION:
Stream0495 15.0
END DESCRIPTION:
XS GIS Cut Line= 3
      2529624.99     13631525.01        2529225.       13631925.
        2529025.     13632725.01
#Sta/Elev= 30
  4429.7  269.37  4479.9  267.27  4599.4  260.92  4615.5     263  4721.5  259.61
  4769.1   255.3  4798.9  257.96    4854  252.29  4882.2  255.51  4940.4  255.17
  4981.2  253.97  4991.8   246.9  5003.6  244.21  5003.9  243.71  5007.7  244.21
  5013.4  248.48  5018.6  246.91  5036.6  251.41  5119.1  249.21  5160.3  255.46
  5216.8   253.6  5224.7  255.59  5242.8  249.12  5260.8  253.78    5266  249.09
  5273.7  254.23  5317.7   256.6  5519.3  262.65    5721  272.07    5820  276.35
#Mann= 12 ,-1 , 0
  4429.7     .05       0  4479.9     .12       0  4615.5      .1       0
  4721.5     .12       0  4798.9      .1       0  4940.4     .12       0
  5003.6     .05       0  5007.7     .12       0  5216.8      .1       0
  5317.7     .12       0  5519.3     .07       0    5721     .12       0
#XS Ineff= 2 , 0
       0  4881.9  260.76  5168.7       0  260.39
Permanent Ineff=
       F       F
Bank Sta=5003.6,5007.7
XS Rating Curve= 0 ,0
Exp/Cntr=0.3,0.1

Type RM Length L Ch R = 1 ,6439    ,446,446,446
BEGIN DESCRIPTION:
Stream0495 14.0
END DESCRIPTION:
XS GIS Cut Line= 3
      2529275.01     13631424.97        2528925.       13632225.
      2528909.02     13632691.38
#Sta/Elev= 30
  4132.7  263.59  4207.2  261.44  4375.6  257.46    4473  254.96  4542.8  254.45
  4545.6  254.63  4733.1  256.02  4787.1  254.96  4915.9  255.03  4939.3  252.69
  4944.7  254.73  4962.3  253.26  4968.1  251.02  4973.6  251.75  5012.4   247.5
  5033.9  241.15  5034.2  240.65  5038.1  241.15    5056  250.99    5066  260.03
    5076  262.84    5086  264.43    5106  264.97  5156.5  271.13  5216.1  274.51
  5296.1  276.89  5376.2  276.99  5406.2  275.71  5432.2  276.34  5472.6  276.33
#Mann= 10 ,-1 , 0
  4132.7     .07       0  4207.2     .05       0  4375.6     .12       0
  4542.8      .1       0  4545.6     .12       0  4787.1      .1       0
  5012.4     .12       0  5033.9     .05       0  5038.1     .12       0
  5432.2     .07       0
Bank Sta=5033.9,5038.1
XS Rating Curve= 0 ,0
Exp/Cntr=0.3,0.1

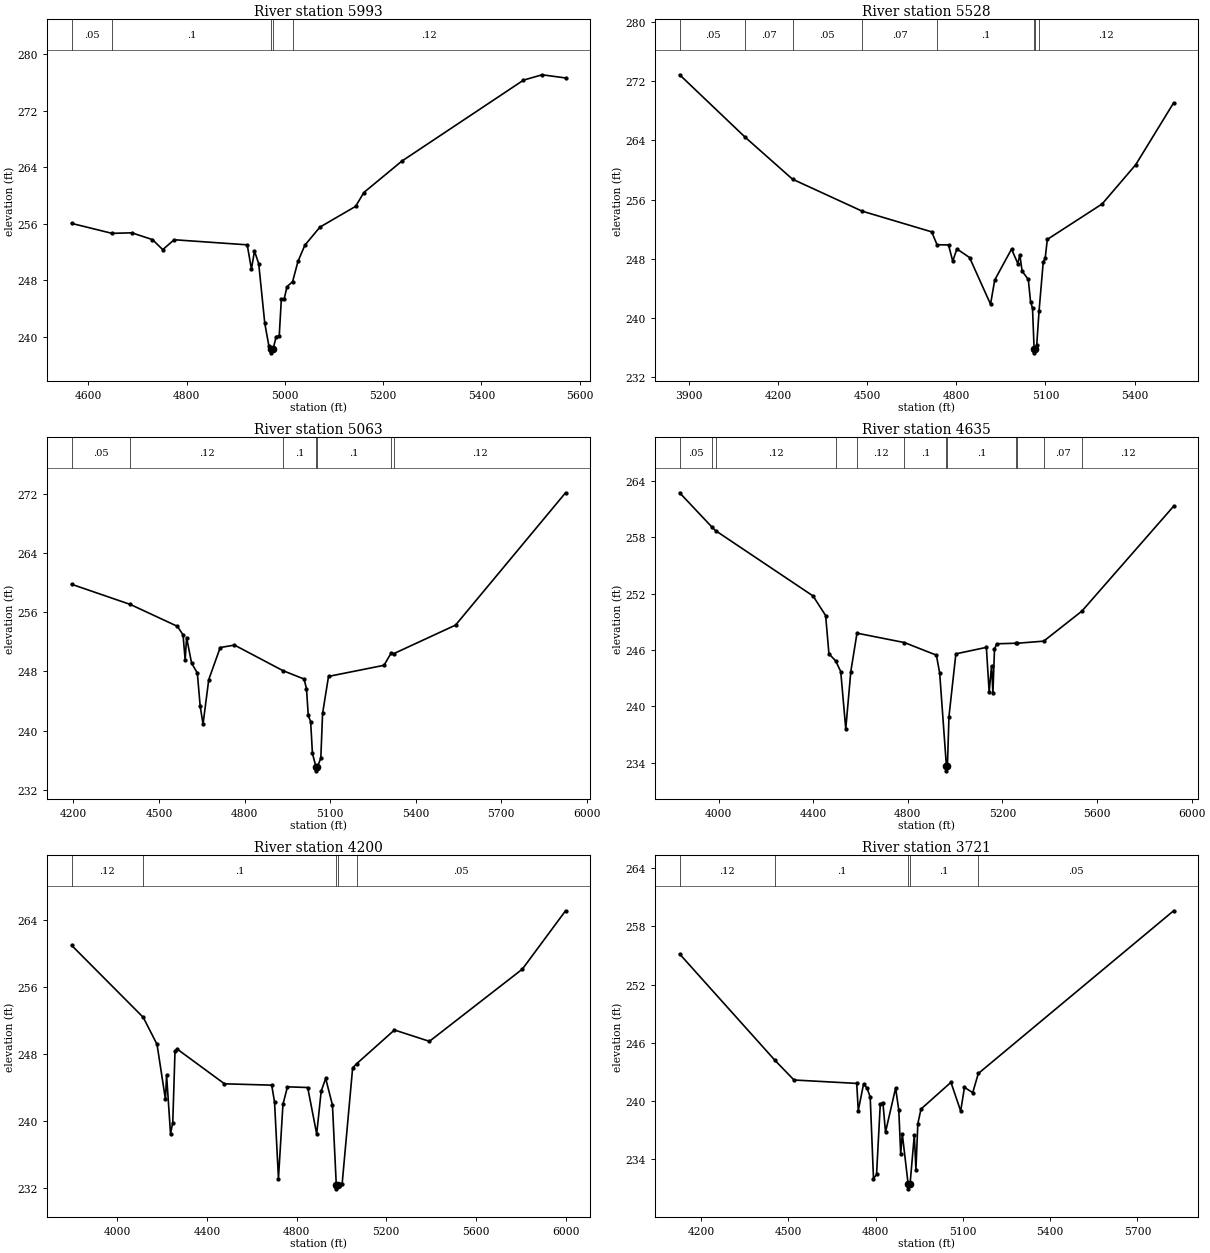
Type RM Length L Ch R = 1 ,5993    ,465,465,465
BEGIN DESCRIPTION:
Stream0495 13.0
END DESCRIPTION:
XS GIS Cut Line= 4
      2529025.01     13631574.98        2528775.       13631925.
      2528686.04     13632102.92      2528769.83     13632470.02
#Sta/Elev= 30
  4565.8  256.06  4647.9  254.65  4688.7  254.72  4730.5  253.76  4751.4  252.34
  4774.7  253.74  4923.4  253.02    4932  249.58  4938.2  252.14  4946.8  250.35
  4959.1  241.93  4967.7  238.62  4971.7  238.22    4972  237.72  4975.9  238.22
  4982.4  240.02  4988.6  240.16  4992.9  245.35  4998.7  245.35  5004.3  247.09
  5015.8  247.81  5026.7  250.67  5040.7  252.96  5071.4  255.53  5144.1  258.47
  5160.8  260.43    5238  264.87  5485.8  276.35  5523.7  277.11  5571.4  276.66
#Mann= 5 ,-1 , 0
  4565.8     .05       0  4647.9      .1       0  4971.7     .05       0
  4975.9      .1       0  5015.8     .12       0
Bank Sta=4971.7,4975.9
XS Rating Curve= 0 ,0
Exp/Cntr=0.3,0.1

Type RM Length L Ch R = 1 ,5528    ,465,465,465
BEGIN DESCRIPTION:
Stream0495 12.0
END DESCRIPTION:
XS GIS Cut Line= 3
      2529124.97     13631075.03        2528325.       13631875.
      2528674.98     13632274.97
#Sta/Elev= 30
  3868.8  272.88  4089.9  264.41  4248.8  258.75  4482.7  254.43  4717.3  251.62
  4735.2  249.88  4773.9  249.85    4788  247.66  4802.1  249.31  4844.6  248.15
  4915.3  241.83  4929.4  245.11    4986  249.29  5007.2  247.33  5013.9  248.53
  5021.5  246.32  5042.4  245.18    5050  242.17  5056.6  241.29    5062  235.75
  5062.3  235.25  5066.3  235.75  5070.8  236.34  5078.7  240.95  5092.7  247.55
  5099.3  248.06  5106.4   250.6    5291   255.4    5404  260.71  5531.6  269.08
#Mann= 8 ,-1 , 0
  3868.8     .05       0  4089.9     .07       0  4248.8     .05       0
  4482.7     .07       0  4735.2      .1       0    5062     .05       0
  5066.3      .1       0  5078.7     .12       0
Bank Sta=5062,5066.3
XS Rating Curve= 0 ,0
Exp/Cntr=0.3,0.1

Type RM Length L Ch R = 1 ,5063    ,428,428,428
BEGIN DESCRIPTION:
Stream0495 11.0
END DESCRIPTION:
XS GIS Cut Line= 3
        2527925.     13631124.95        2527875.       13631925.
      2528625.03     13632475.02
#Sta/Elev= 30
  4193.7  259.78  4399.8  257.05  4564.5   254.1  4584.5  252.95    4592  249.53
    4597  252.58  4614.6   249.1  4634.6   247.8  4644.6  243.32  4654.6  240.89
  4674.7   246.9  4714.8  251.23  4764.9  251.56  4934.1  248.12  5008.8  246.97
  5017.3  245.67  5023.5  242.07  5031.9   241.2  5038.1  236.93  5050.7  235.07
    5051  234.57    5055  235.07  5067.5  236.27  5073.7  242.32  5094.5  247.33
    5289  248.83  5313.8  250.47  5323.6  250.41  5539.8  254.26  5925.4  272.14
#Mann= 7 ,-1 , 0
  4193.7     .05       0  4399.8     .12       0  4934.1      .1       0
  5050.7     .05       0    5055      .1       0  5313.8     .07       0
  5323.6     .12       0
Bank Sta=5050.7,5055
XS Rating Curve= 0 ,0
Exp/Cntr=0.3,0.1

Type RM Length L Ch R = 1 ,4635    ,435,435,435
BEGIN DESCRIPTION:
Stream0495 10.0
END DESCRIPTION:
XS GIS Cut Line= 3
        2527925.     13630974.99        2527525.       13632075.
      2528325.03     13632525.02
#Sta/Elev= 30
  3835.4  262.74  3970.9  259.12  3987.8   258.7  4399.4  251.76  4452.6  249.68
  4466.5  245.61    4495  244.85  4516.4  243.72  4537.7  237.62    4559  243.71
  4585.1   247.8  4785.8   246.8  4920.8  245.46  4934.7  243.57  4963.2  233.65
  4963.5  233.15  4967.5  233.65    4974  238.93  5003.2   245.6  5132.1  246.29
  5143.9  241.55  5154.1  244.33  5159.8  241.45  5166.5  246.09  5175.8  246.67
  5257.2  246.73  5263.4  246.73  5374.5  246.95  5536.1  250.15  5923.8  261.31
#Mann= 12 ,-1 , 0
  3835.4     .05       0  3970.9    .035       0  3987.8     .12       0
    4495      .1       0  4585.1     .12       0  4785.8      .1       0
  4963.2     .05       0  4967.5      .1       0  5257.2     .12       0
  5263.4      .1       0  5374.5     .07       0  5536.1     .12       0
Bank Sta=4963.2,4967.5
XS Rating Curve= 0 ,0
Exp/Cntr=0.3,0.1

Type RM Length L Ch R = 1 ,4200    ,479,479,479
BEGIN DESCRIPTION:
Stream0495 9.0
END DESCRIPTION:
XS GIS Cut Line= 3
        2527025.     13630874.96        2527125.       13632075.
        2526525.       13632875.
#Sta/Elev= 30
  3795.8  260.96  4115.6  252.38  4177.2  249.16  4214.8   242.6  4219.8  245.49
  4237.4  238.52  4247.4  239.83  4257.4  248.36  4267.5  248.59  4478.2  244.46
  4688.9   244.3  4701.5   242.3    4719  233.18  4739.1  242.01  4759.2   244.1
  4849.5  244.02  4889.6  238.49  4909.7  243.59  4929.8   245.1  4959.9  241.93
    4977  232.45  4977.5  231.95  4982.8  232.45  5003.1  232.52    5050  246.35
  5067.9  246.85  5236.5  250.87  5392.7  249.52  5807.3  258.12    6000  265.07
#Mann= 5 ,-1 , 0
  3795.8     .12       0  4115.6      .1       0    4977     .05       0
  4982.8      .1       0  5067.9     .05       0
Bank Sta=4977,4982.8
XS Rating Curve= 0 ,0
Exp/Cntr=0.3,0.1

Type RM Length L Ch R = 1 ,3721    ,426,426,426
BEGIN DESCRIPTION:
Stream0495 8.0
END DESCRIPTION:
XS GIS Cut Line= 3
      2526374.98     13631074.96        2526725.       13631875.
      2526524.99     13632675.02
#Sta/Elev= 30
  4126.4  255.16  4454.2   244.2  4519.4  242.18    4735  241.83  4740.4  239.03
  4758.4  241.75  4770.4  241.36  4781.4  240.42  4792.7  232.01  4803.2  232.47
    4816  239.68    4825  239.86    4834  236.81  4868.7  241.35  4879.6  239.08
  4886.2  234.59  4891.7  236.63  4911.7  231.47  4912.2  230.97  4918.4  231.47
    4933  236.52  4938.5  232.94  4945.1  237.68    4956  239.19  5058.9  241.94
  5092.4  238.98  5105.3  241.42  5133.7  240.88    5153  242.85  5824.3  259.61
#Mann= 5 ,-1 , 0
  4126.4     .12       0  4454.2      .1       0  4911.7     .05       0
  4918.4      .1       0    5153     .05       0
Bank Sta=4911.7,4918.4
XS Rating Curve= 0 ,0
Exp/Cntr=0.3,0.1

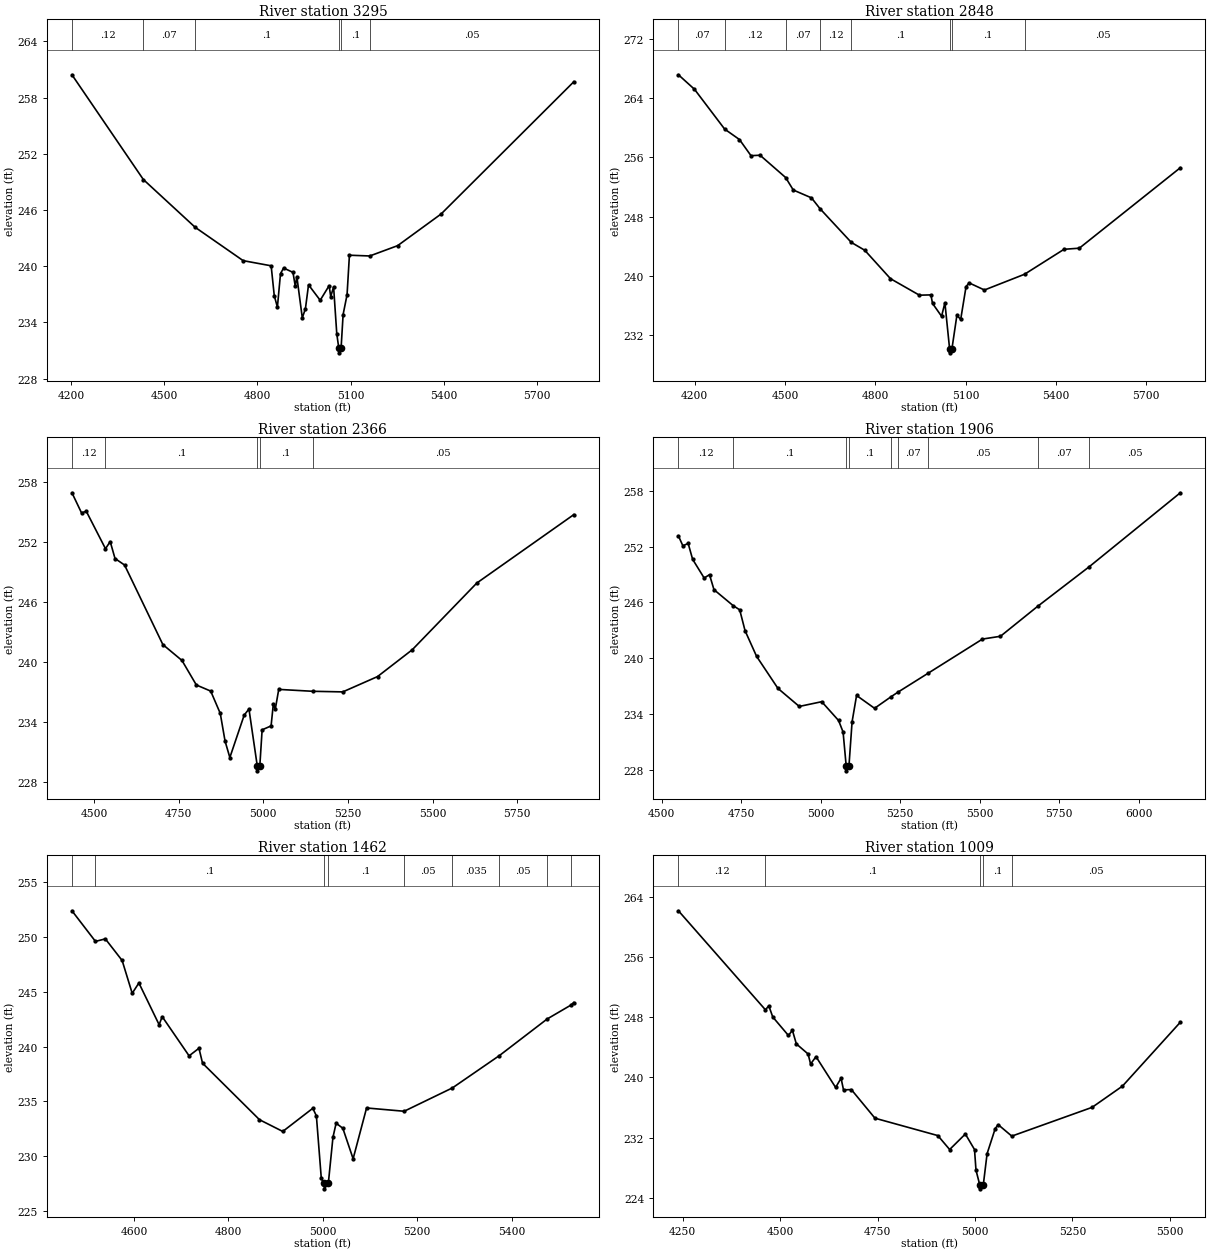
Type RM Length L Ch R = 1 ,3295    ,447,447,447
BEGIN DESCRIPTION:
Stream0495 7.0
END DESCRIPTION:
XS GIS Cut Line= 3
        2526325.     13630975.02        2526375.       13631775.
        2526225.     13632575.02
#Sta/Elev= 30
  4202.9  260.44  4432.7  249.26  4599.5  244.16    4754   240.6  4844.1  240.05
  4854.1  236.86  4864.2  235.64  4874.2  239.22  4884.2  239.81  4914.3  239.35
  4921.8  237.86  4926.8   238.9  4944.3   234.5  4954.3  235.45  4964.4  238.02
  5001.9  236.37  5030.7  237.93  5035.8  236.77  5045.1  237.79  5055.3   232.8
  5061.8  231.26  5062.3  230.76  5069.2  231.26  5075.7  234.85  5088.4  236.96
    5096  241.18  5161.5   241.1  5251.2   242.2  5391.1  245.58  5818.4   259.7
#Mann= 6 ,-1 , 0
  4202.9     .12       0  4432.7     .07       0  4599.5      .1       0
  5061.8     .05       0  5069.2      .1       0  5161.5     .05       0
Bank Sta=5061.8,5069.2
XS Rating Curve= 0 ,0
Exp/Cntr=0.3,0.1

Type RM Length L Ch R = 1 ,2848    ,482,482,482
BEGIN DESCRIPTION:
Stream0495 6.0
END DESCRIPTION:
XS GIS Cut Line= 3
        2526275.       13630825.        2525975.       13631625.
      2526124.99     13632424.96
#Sta/Elev= 30
  4145.6  267.17    4199  265.21  4299.3  259.83  4348.5  258.42  4386.8  256.24
    4417   256.3  4501.9  253.29  4527.4   251.6  4587.9  250.54  4616.2  249.08
  4720.3  244.52    4765  243.46  4850.5  239.62  4946.6  237.39  4984.9  237.43
  4990.2  236.28  5020.3  234.54  5031.4  236.36  5047.1   230.1  5047.6   229.6
  5054.6   230.1  5071.2  234.66  5083.9  234.12  5101.7  238.55  5111.9  239.05
  5162.8  238.09  5296.2  240.22  5427.3  243.59  5478.2  243.74  5813.9  254.61
#Mann= 8 ,-1 , 0
  4145.6     .07       0  4299.3     .12       0  4501.9     .07       0
  4616.2     .12       0  4720.3      .1       0  5047.1     .05       0
  5054.6      .1       0  5296.2     .05       0
Bank Sta=5047.1,5054.6
XS Rating Curve= 0 ,0
Exp/Cntr=0.3,0.1

Type RM Length L Ch R = 1 ,2366    ,460,460,460
BEGIN DESCRIPTION:
Stream0495 5.0
END DESCRIPTION:
XS GIS Cut Line= 3
      2525125.02     13631225.02        2525525.       13631625.
      2525974.98     13632424.97
#Sta/Elev= 30
  4434.3  256.91  4462.6   254.9  4476.7  255.06  4533.4  251.32  4547.4  252.03
  4561.6  250.34  4589.8  249.69    4703  241.74  4759.5  240.15    4802   237.7
  4844.4  237.09  4872.7  234.86  4886.8   232.1    4901  230.45  4943.4  234.69
  4957.5   235.3    4982  229.62  4982.5  229.12  4989.6  229.62  4996.4  233.22
  5022.9  233.61  5029.6  235.82  5035.3  235.28  5045.5  237.26  5146.2  237.07
  5234.8  237.01  5337.5  238.54  5440.1  241.22    5631  247.89  5917.8  254.73
#Mann= 5 ,-1 , 0
  4434.3     .12       0  4533.4      .1       0    4982     .05       0
  4989.6      .1       0  5146.2     .05       0
Bank Sta=4982,4989.6
XS Rating Curve= 0 ,0
Exp/Cntr=0.3,0.1

Type RM Length L Ch R = 1 ,1906    ,444,444,444
BEGIN DESCRIPTION:
Stream0495 4.0
END DESCRIPTION:
XS GIS Cut Line= 3
      2524925.02     13631375.03        2525125.       13631775.
      2525924.97     13632574.97
#Sta/Elev= 30
  4552.8  253.16  4566.7   252.1  4583.5  252.34  4597.5  250.64  4633.8  248.63
  4650.6  248.99  4664.6  247.38  4724.7  245.67  4745.6  245.21  4762.4  242.97
  4798.7  240.21  4865.8  236.77  4932.9  234.83  5003.5  235.34  5056.5  233.32
  5070.7  232.08  5080.5  228.41    5081  227.91  5089.1  228.41    5099  233.18
  5113.1  236.01  5169.7  234.63  5221.9  235.88    5243  236.36  5339.1  238.42
  5509.1  242.07  5565.7  242.37  5682.3  245.58  5845.1  249.85  6131.3  257.79
#Mann= 9 ,-1 , 0
  4552.8     .12       0  4724.7      .1       0  5080.5     .05       0
  5089.1      .1       0  5221.9     .05       0    5243     .07       0
  5339.1     .05       0  5682.3     .07       0  5845.1     .05       0
Bank Sta=5080.5,5089.1
XS Rating Curve= 0 ,0
Exp/Cntr=0.3,0.1

Type RM Length L Ch R = 1 ,1462    ,453,453,453
BEGIN DESCRIPTION:
Stream0495 3.0
END DESCRIPTION:
XS GIS Cut Line= 3
      2524425.03     13631625.04        2524775.       13632025.
      2525125.02     13632425.02
#Sta/Elev= 30
  4468.8  252.38  4518.6  249.59  4539.5  249.82  4575.1  247.85  4596.4  244.86
  4610.6   245.8  4653.4     242    4660  242.73  4716.9  239.16  4737.8  239.85
  4745.4  238.49    4866  233.34  4915.3  232.27  4978.9  234.38  4986.5  233.69
  4996.9  227.99    5003  227.54  5003.5  227.04  5011.8  227.54  5021.6  231.74
  5028.3  233.02  5042.5  232.56  5064.3  229.78  5092.8  234.41  5172.4  234.11
  5274.7  236.24  5374.3  239.19  5475.3  242.52    5525  243.77  5531.8  244.02
#Mann= 9 ,-1 , 0
  4468.8     .12       0  4518.6      .1       0    5003     .05       0
  5011.8      .1       0  5172.4     .05       0  5274.7    .035       0
  5374.3     .05       0  5475.3    .035       0    5525     .05       0
Bank Sta=5003,5011.8
XS Rating Curve= 0 ,0
Exp/Cntr=0.3,0.1

Type RM Length L Ch R = 1 ,1009    ,474,474,474
BEGIN DESCRIPTION:
Stream0495 2.0
END DESCRIPTION:
XS GIS Cut Line= 3
      2524325.01     13631475.04        2524425.       13632225.
        2524775.       13632625.
#Sta/Elev= 30
    4239  262.13  4462.3  248.98    4471  249.51  4481.1  248.03  4521.4  245.57
  4531.5  246.27  4541.6  244.46  4571.9  243.11  4578.2  241.78  4592.1  242.76
  4642.5  238.67  4656.4   239.9  4662.7  238.35  4682.8  238.39  4743.4  234.59
  4904.8  232.28  4935.1  230.43  4975.4  232.49  4998.9  230.43  5002.7  227.69
  5012.5  225.71    5013  225.21  5021.4  225.71  5031.2  229.88  5052.1  233.22
  5059.7  233.73  5094.6  232.21  5300.7  236.03  5378.6  238.85  5527.1  247.33
#Mann= 5 ,-1 , 0
    4239     .12       0  4462.3      .1       0  5012.5     .05       0
  5021.4      .1       0  5094.6     .05       0
Bank Sta=5012.5,5021.4
XS Rating Curve= 0 ,0
Exp/Cntr=0.3,0.1

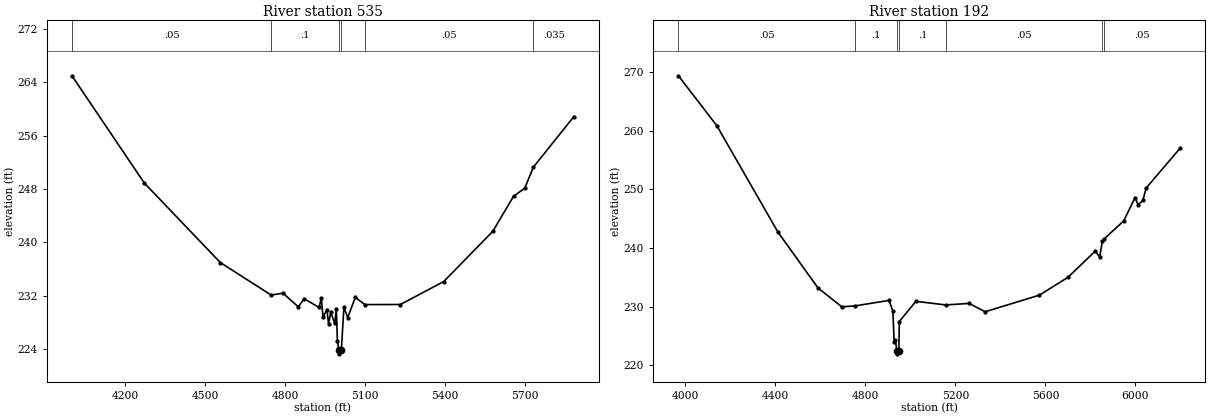
Type RM Length L Ch R = 1 ,535     ,343,343,343
BEGIN DESCRIPTION:
Stream0495 1.0
END DESCRIPTION:
XS GIS Cut Line= 3
      2523425.02     13631625.02        2524025.       13632425.
      2524625.03     13633075.03
#Sta/Elev= 30
    4000  264.94  4271.8  248.89  4557.3  236.99    4748  232.14  4792.7  232.41
    4850  230.37  4871.8  231.58  4928.1  230.28  4936.4  231.69  4942.7  228.82
  4957.3  229.97  4963.5  227.84  4971.8  229.54  4986.4  227.91  4992.7  230.02
  4996.8  225.26  5002.6  223.84  5003.1  223.34  5011.5  223.84  5021.2  230.31
  5035.4  228.76  5063.8  231.78  5100.3  230.71  5233.3  230.72  5396.1  234.16
  5580.3  241.67    5658   246.9  5700.3  248.13  5732.7  251.28  5884.6  258.83
#Mann= 6 ,-1 , 0
    4000     .05       0    4748      .1       0  5002.6     .05       0
  5011.5      .1       0  5100.3     .05       0  5732.7    .035       0
Bank Sta=5002.6,5011.5
XS Rating Curve= 0 ,0
Exp/Cntr=0.3,0.1

Type RM Length L Ch R = 1 ,192     ,0,0,0
BEGIN DESCRIPTION:
XS6936
END DESCRIPTION:
XS GIS Cut Line= 3
      2523257.34     13631544.98      2523778.08     13632637.09
      2524544.73     13633309.72
#Sta/Elev= 30
  3969.4  269.33  4139.7  260.85    4412  242.68  4589.8  233.18  4695.5  229.98
  4751.8  230.12  4905.3  231.07  4922.2  229.21    4928  223.95  4933.5   224.3
  4939.8  222.47  4940.3  221.97  4948.9  222.47  4950.7  227.47  5024.3  230.91
  5157.7   230.3  5260.6  230.56  5331.8  229.14  5572.8  231.96    5700     235
  5820.5  239.44  5841.4  238.48  5852.5  241.13  5860.2  241.52  5947.7  244.62
  5997.9  248.57  6012.2  247.36  6032.8   248.1  6047.3  250.21  6199.2  257.03
#Mann= 7 ,-1 , 0
  3969.4     .05       0  4751.8      .1       0  4939.8     .05       0
  4948.9      .1       0  5157.7     .05       0  5852.5    .035       0
  5860.2     .05       0
Bank Sta=4939.8,4948.9
XS Rating Curve= 0 ,0
Exp/Cntr=0.3,0.1

Chan Stop Cuts=-1
Use User Specified Reach Order=0
Composite Channel Slope=5