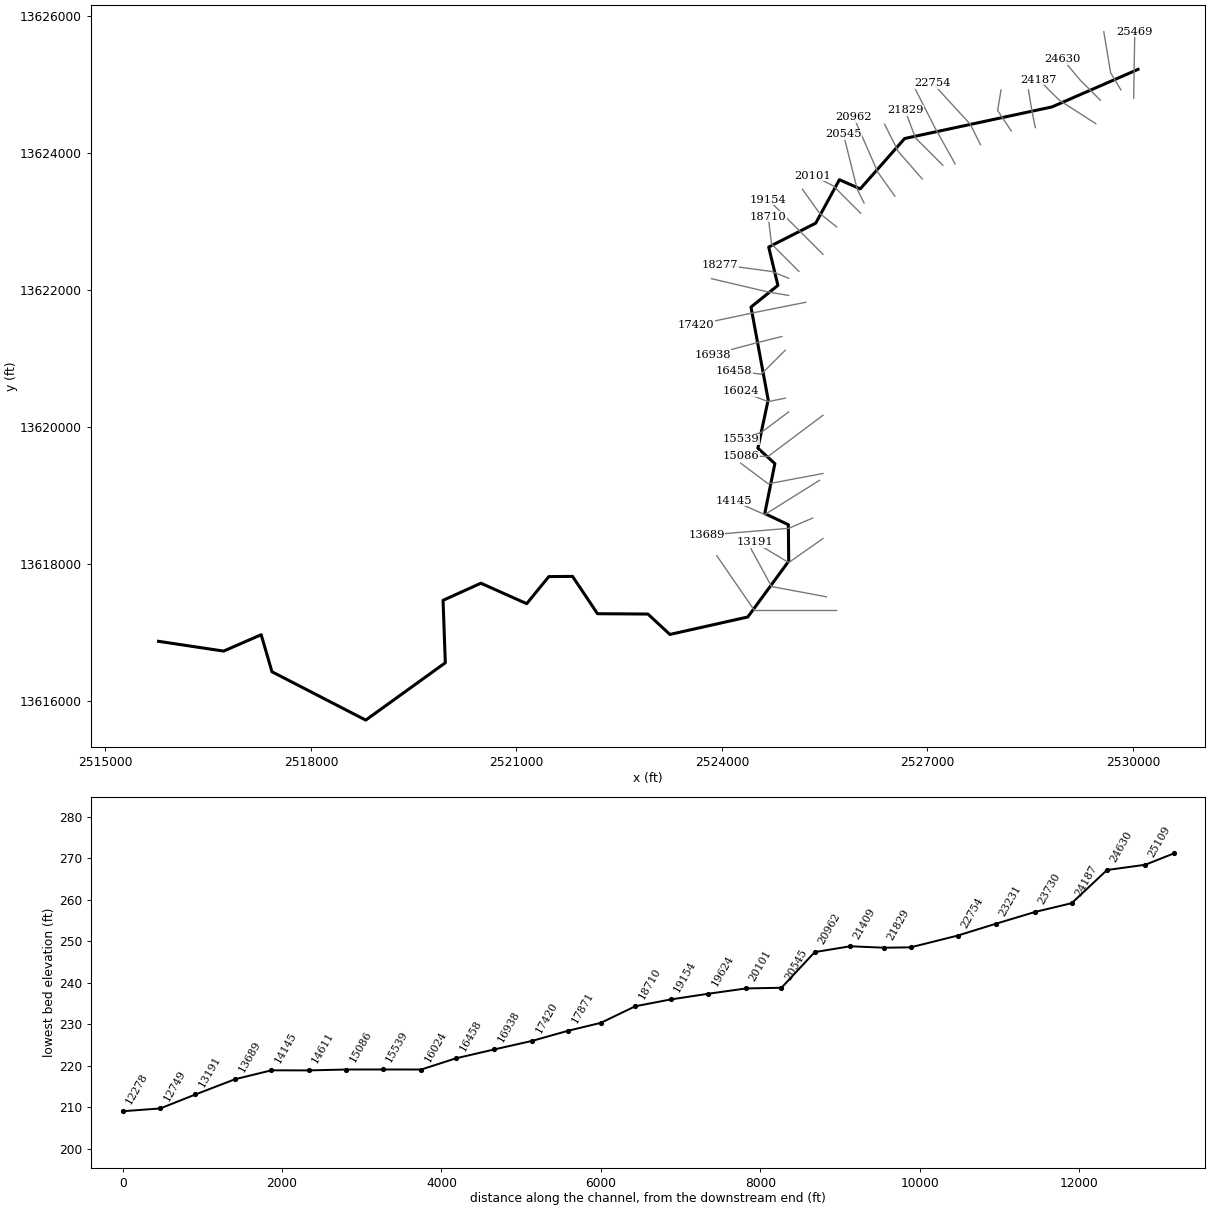
--- Stream0498.prj (project) ---

Proj Title=Stream0498 Base Level Engineering
Current Plan=p01
Default Exp/Contr=0.3,0.1
English Units
Geom File=g01
Flow File=f01
Plan File=p01
Y Axis Title=Elevation
X Axis Title(PF)=Main Channel Distance
X Axis Title(XS)=Station
BEGIN DESCRIPTION:
Stream0498
END DESCRIPTION:
DSS Export Rating Curves= 0
DSS Export Rating Curve Sorted= 0
DSS Export Volume Flow Curves= 0
DXF OffsetX= 0
DXF OffsetY= 0
DXF ScaleX= 1
DXF ScaleY= 10

--- Stream0498.p01 (plan) ---

Plan Title=Multiple Run
Short Identifier=Multiple
Geom File=g01
Flow File=f01
Subcritical Flow
K Sum by GR= 0
Std Step Tol= 0.01
Critical Tol= 0.01
Num of Std Step Trials= 20
Max Error Tol= 0.3
Flow Tol Ratio= 0.001
Split Flow NTrial= 30
Split Flow Tol= 0.02
Split Flow Ratio= 0.02
Log Output Level= 0
Friction Slope Method= 1
Unsteady Friction Slope Method= 2
Unsteady Bridges Friction Slope Method= 1
Parabolic Critical Depth
Global Vel Dist=  1 , 1 , 1
Global Log Level= 0
CheckData=True
Encroach Param= -1, 0, 0, 0
BEGIN DESCRIPTION:
Multiple Run
END DESCRIPTION:

--- Stream0498.f01 (steady flow) ---

Flow Title=Multiple
Number of Profiles=7
Profile Names=10-year,25-year,50-year,1pct_min,100-year,1pct_plu,500-year
River Rch & RM= Stream0498,Reach-1,25469
     884    1453    1977    1304    2601    5189    4454
River Rch & RM= Stream0498,Reach-1,22166
    1255    2088    2864    1899    3790    7562    6572
River Rch & RM= Stream0498,Reach-1,15086
    1231    2039    2788    1843    3677    7337    6334
River Rch & RM= Stream0498,Reach-1,12749
    1564    2629    3630    2421    4830    9638    8476
River Rch & RM= Stream0498,Reach-1,12278
    2094    3541    4908    3280    6544   13057   11534
River Rch & RM= Stream0498,Reach-1,4146
    2155    3640    5040    3364    6712   13392   11800
Boundary for River Rch & Prof#=Stream0498,Reach-1,1
Up Type=0
Dn Type=3
Dn Slope=0.005
Boundary for River Rch & Prof#=Stream0498,Reach-1,2
Up Type=0
Dn Type=3
Dn Slope=0.005
Boundary for River Rch & Prof#=Stream0498,Reach-1,3
Up Type=0
Dn Type=3
Dn Slope=0.005
Boundary for River Rch & Prof#=Stream0498,Reach-1,4
Up Type=0
Dn Type=3
Dn Slope=0.005
Boundary for River Rch & Prof#=Stream0498,Reach-1,5
Up Type=0
Dn Type=3
Dn Slope=0.005
Boundary for River Rch & Prof#=Stream0498,Reach-1,6
Up Type=0
Dn Type=3
Dn Slope=0.005
Boundary for River Rch & Prof#=Stream0498,Reach-1,7
Up Type=0
Dn Type=3
Dn Slope=0.005

--- Stream0498.g01 (geometry) ---

Geom Title=Existing Conditions
Program Version=4.10

River Reach=Stream0498      ,Reach-1
Reach XY= 30
        2530075.       13625225.      2528819.16     13624677.05
        2526668.     13624215.96      2526019.56     13623480.18
        2525715.     13623614.05      2525369.59     13622980.18
      2524682.81     13622631.19      2524817.24     13622071.58
      2524424.61     13621754.87       2524675.2     13620400.08
      2524524.91     13619694.88      2524772.94     13619469.15
      2524625.24     13618740.21      2524969.66     13618577.74
      2524975.04     13618044.98      2524377.59     13617230.14
      2523240.16     13616975.38      2522919.33     13617273.02
      2522183.28     13617278.06      2521819.15     13617822.94
       2521472.3     13617819.64      2521150.12     13617424.47
      2520481.11     13617723.21      2519928.61     13617473.52
      2519961.67     13616561.67      2518800.08     13615724.79
      2517430.62     13616430.62      2517273.48     13616971.27
       2516724.9     13616732.32        2515775.       13616875.

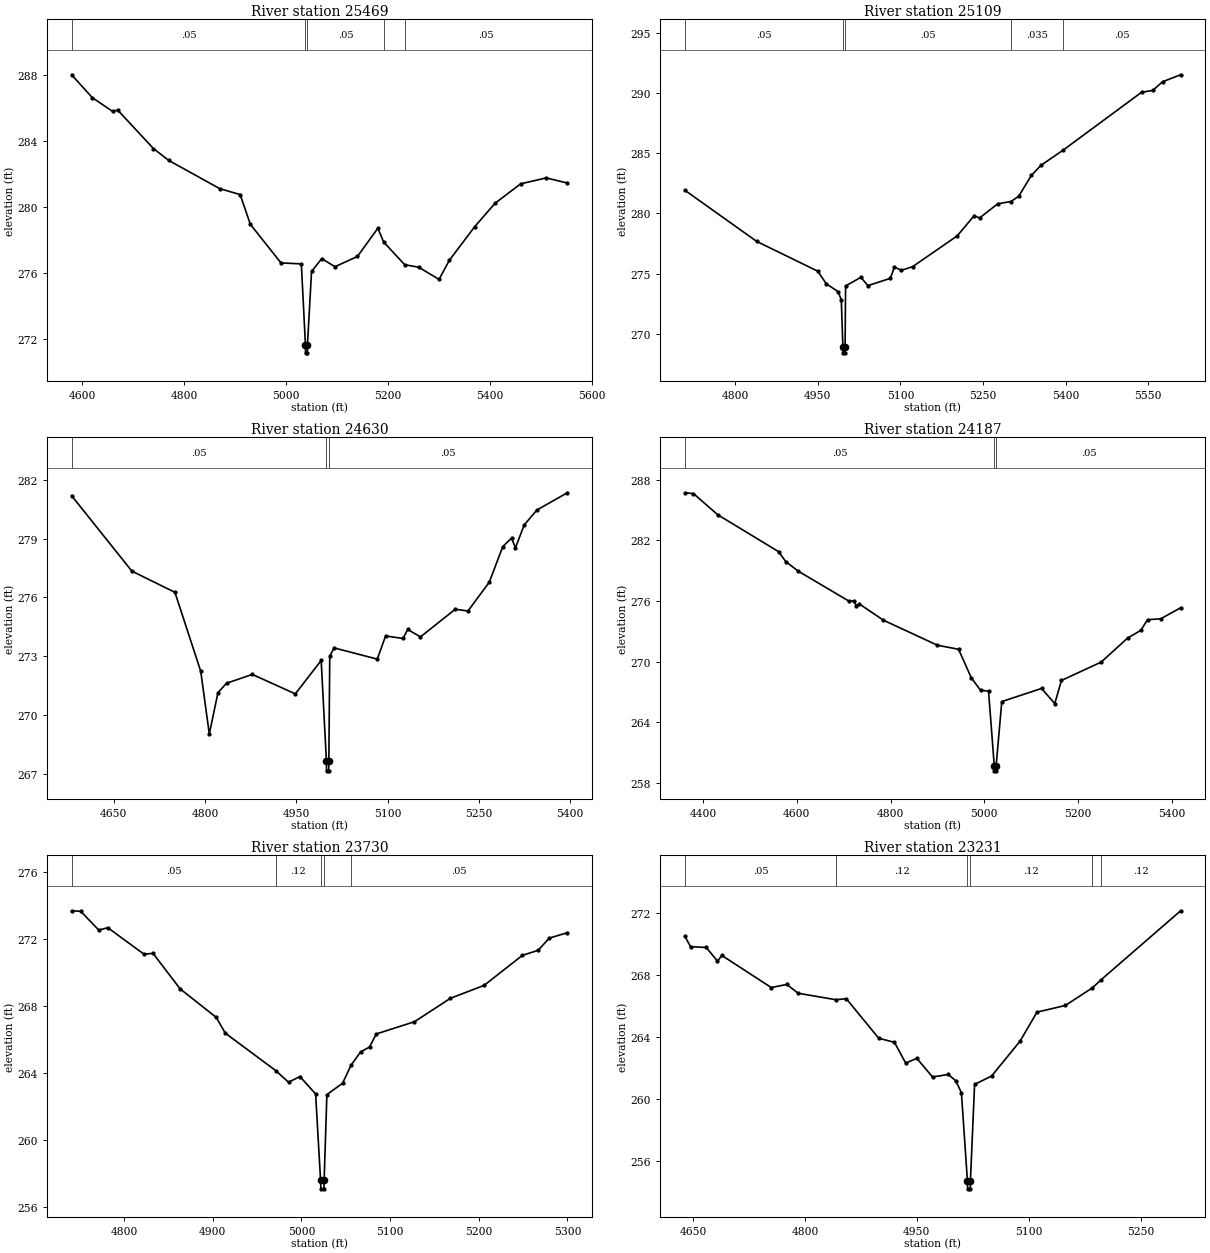
Type RM Length L Ch R = 1 ,25469   ,360,360,360
BEGIN DESCRIPTION:
XS6943
END DESCRIPTION:
XS GIS Cut Line= 2
      2530011.66     13624804.67      2530027.33     13625776.44
#Sta/Elev= 30
  4579.6  288.02  4619.9  286.64  4659.9   285.8  4669.9  285.88    4740  283.55
    4770  282.83    4870  281.12    4910  280.76    4930  278.96    4990  276.62
    5030  276.56    5038  271.67  5038.2  271.17  5041.7  271.17    5042  271.67
    5050   276.1    5070  276.88  5095.9  276.39    5140  277.01    5180  278.72
  5191.3  277.89  5232.6  276.51    5260  276.36    5300  275.62    5320  276.77
    5370  278.82    5410  280.24    5460  281.41  5510.1  281.77  5551.5  281.46
#Mann= 5 ,-1 , 0
  4579.6     .05       0    5038     .05       0    5042     .05       0
  5191.3    .035       0  5232.6     .05       0
Bank Sta=5038,5042
XS Rating Curve= 0 ,0
Exp/Cntr=0.3,0.1

Type RM Length L Ch R = 1 ,25109   ,479,479,479
BEGIN DESCRIPTION:
Stream0498 46.0
END DESCRIPTION:
XS GIS Cut Line= 3
      2529825.01     13624924.98        2529675.       13625175.
      2529575.01     13625774.96
#Sta/Elev= 30
  4708.9  281.92  4839.1  277.68  4949.9  275.21  4965.5  274.16  4986.9  273.51
  4992.7  272.83  4995.6  268.93  4995.8  268.43  4999.3  268.43  4999.6  268.93
  5000.5  273.98  5028.3   274.7    5041  274.01  5081.6  274.61  5089.2  275.55
  5101.8  275.28  5122.1  275.58  5203.2  278.14  5233.6   279.8  5243.8  279.63
  5276.7   280.8  5300.5  280.99  5314.7  281.42  5337.6  283.15  5355.3     284
  5395.9  285.27  5537.8  290.06  5558.1  290.21  5575.8  290.93  5608.7  291.51
#Mann= 5 ,-1 , 0
  4708.9     .05       0  4995.6     .05       0  4999.6     .05       0
  5300.5    .035       0  5395.9     .05       0
Bank Sta=4995.6,4999.6
XS Rating Curve= 0 ,0
Exp/Cntr=0.3,0.1

Type RM Length L Ch R = 1 ,24630   ,443,443,443
BEGIN DESCRIPTION:
Stream0498 45.0
END DESCRIPTION:
XS GIS Cut Line= 3
      2529525.03     13624774.97        2529225.       13625075.
      2528975.01     13625374.98
#Sta/Elev= 30
  4580.7  281.18  4679.7  277.34  4750.5  276.26  4792.9  272.24    4807  269.05
  4821.2  271.15  4835.3  271.63  4877.7  272.08  4948.4  271.09  4990.9  272.79
  4999.5  267.67  4999.7  267.17  5003.2  267.17  5003.5  267.67    5005  273.01
  5012.2  273.43  5083.1  272.86  5096.8  274.04  5125.4  273.91  5133.2  274.37
  5154.1  273.99  5211.3   275.4  5232.2  275.31  5267.3  276.78  5289.4  278.59
  5303.8  279.02  5310.3  278.53  5324.6  279.69  5345.4  280.45  5395.5  281.33
#Mann= 3 ,-1 , 0
  4580.7     .05       0  4999.5     .05       0  5003.5     .05       0
Bank Sta=4999.5,5003.5
XS Rating Curve= 0 ,0
Exp/Cntr=0.3,0.1

Type RM Length L Ch R = 1 ,24187   ,457,457,457
BEGIN DESCRIPTION:
Stream0498 44.0
END DESCRIPTION:
XS GIS Cut Line= 3
      2529458.58     13624432.22        2528925.       13624775.
      2528624.97     13625075.03
#Sta/Elev= 30
    4361  286.72  4379.2  286.64  4430.8  284.55  4560.9  280.89  4576.1  279.91
  4603.2  278.95  4712.2  275.96  4721.4  276.02  4727.3  275.51  4733.7   275.7
  4784.8   274.1  4900.1  271.62  4945.3  271.22  4972.4   268.4  4992.2  267.16
  5009.3  267.07  5021.5  259.68  5021.7  259.18  5025.2  259.18  5025.5  259.68
  5037.6  266.04  5122.5  267.34  5150.8  265.84  5164.9  268.13  5249.8  269.95
  5306.3  272.33  5334.6   273.1  5348.8  274.15    5377  274.24  5419.5  275.33
#Mann= 3 ,-1 , 0
    4361     .05       0  5021.5     .05       0  5025.5     .05       0
Bank Sta=5021.5,5025.5
XS Rating Curve= 0 ,0
Exp/Cntr=0.3,0.1

Type RM Length L Ch R = 1 ,23730   ,499,499,499
BEGIN DESCRIPTION:
Stream0498 43.0
END DESCRIPTION:
XS GIS Cut Line= 3
        2528575.     13624375.02        2528525.       13624625.
      2528474.99     13624925.04
#Sta/Elev= 30
  4740.8  273.67    4751  273.64  4771.4  272.52  4781.6  272.66  4822.4  271.08
  4832.6  271.13  4863.2  269.01  4903.9  267.31  4914.1  266.37  4971.1  264.13
  4985.5  263.44  4998.3  263.78    5016  262.74  5021.6  257.58  5021.9  257.08
  5025.4  257.08  5025.6  257.58  5028.7   262.7  5046.4  263.38  5055.8  264.44
  5066.7  265.25  5076.8  265.54  5084.4  266.32  5127.5  267.05  5168.1  268.45
  5206.1  269.22  5249.2  271.01  5266.9  271.31  5279.6  272.04  5299.9  272.36
#Mann= 5 ,-1 , 0
  4740.8     .05       0  4971.1     .12       0  5021.6     .05       0
  5025.6     .12       0  5055.8     .05       0
Bank Sta=5021.6,5025.6
XS Rating Curve= 0 ,0
Exp/Cntr=0.3,0.1

Type RM Length L Ch R = 1 ,23231   ,477,477,477
BEGIN DESCRIPTION:
Stream0498 42.0
END DESCRIPTION:
XS GIS Cut Line= 3
        2528225.       13624325.        2528025.       13624625.
        2528075.       13624925.
#Sta/Elev= 30
    4639  270.51  4646.5  269.85  4667.5   269.8  4682.6  268.92  4688.6  269.28
  4754.7  267.21  4775.7  267.41  4790.7  266.84  4841.7  266.42  4855.3  266.49
  4898.9  263.93  4919.9  263.67    4935  262.33    4950  262.63    4971  261.43
    4992  261.59  5002.1  261.19  5009.7  260.42  5017.8   254.7  5018.1   254.2
  5021.6   254.2  5021.8   254.7  5027.4  260.95  5050.2  261.49  5088.3  263.74
  5111.1  265.62  5149.1  266.05  5185.4  267.19  5196.8   267.7  5303.7  272.17
#Mann= 6 ,-1 , 0
    4639     .05       0  4841.7     .12       0  5017.8     .05       0
  5021.8     .12       0  5185.4     .05       0  5196.8     .12       0
Bank Sta=5017.8,5021.8
XS Rating Curve= 0 ,0
Exp/Cntr=0.3,0.1

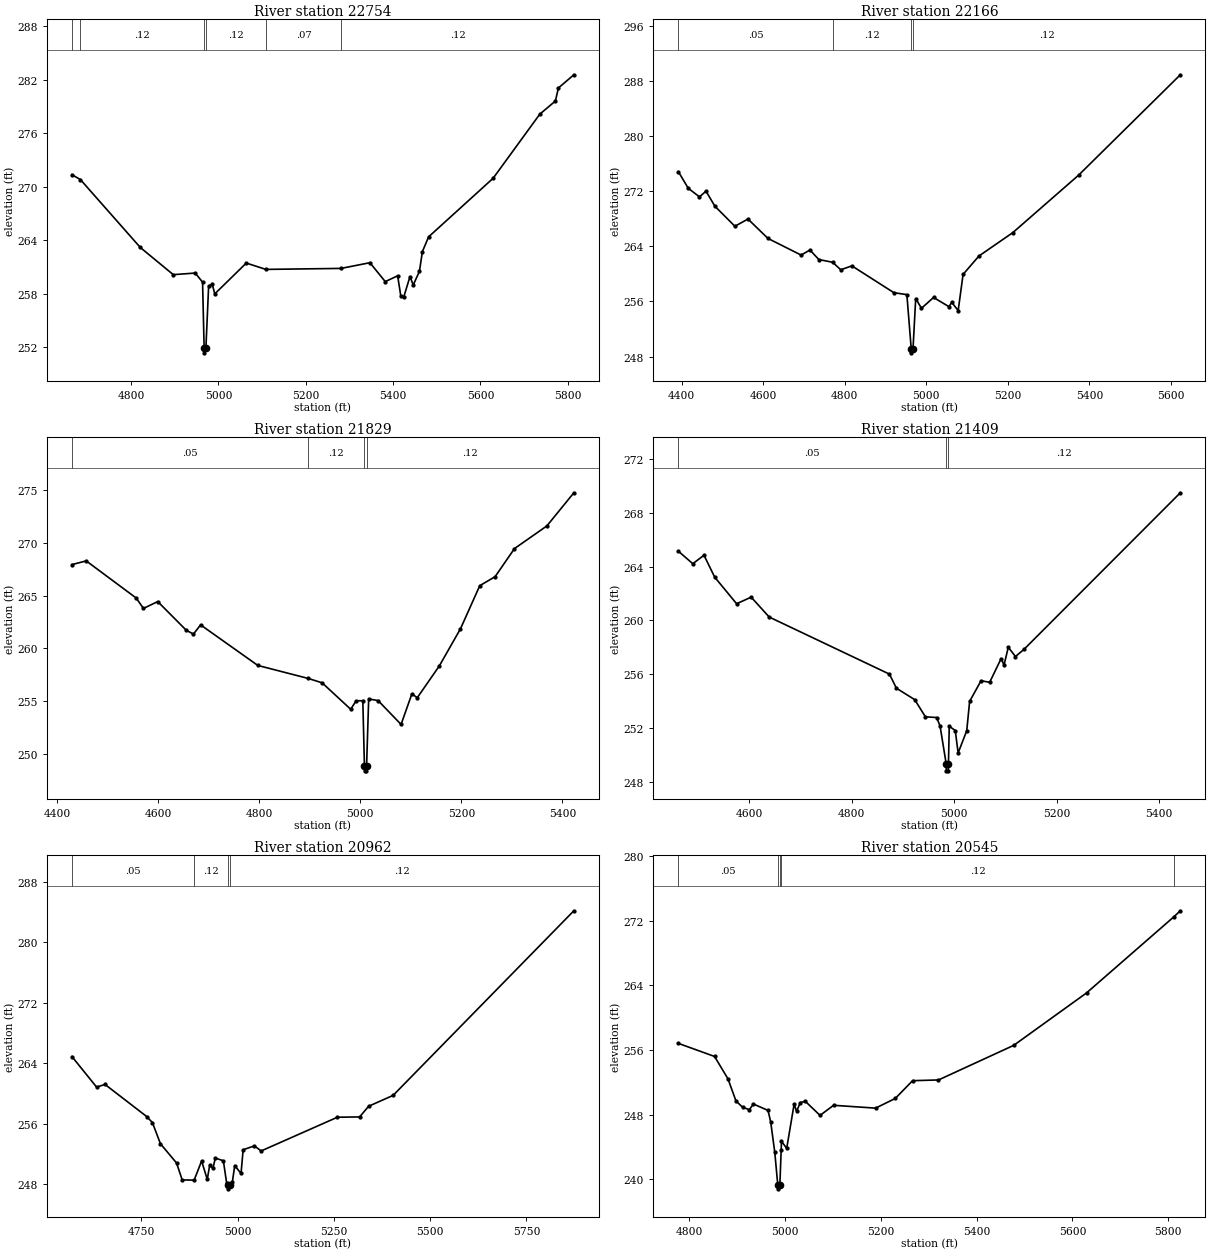
Type RM Length L Ch R = 1 ,22754   ,588,588,588
BEGIN DESCRIPTION:
Stream0498 41.0
END DESCRIPTION:
XS GIS Cut Line= 3
        2527775.     13624125.01        2527625.       13624425.
      2527075.03     13625024.97
#Sta/Elev= 30
  4664.6  271.34  4683.9   270.8  4821.1  263.18  4896.6  260.13  4946.9  260.31
  4963.7  259.29  4967.3  251.86  4967.5  251.36  4971.3  251.86  4977.6  258.86
    4986  259.04  4991.6  257.97  5063.8  261.43  5108.7  260.72  5280.8  260.83
  5346.9  261.47    5382  259.35  5410.4     260  5417.8  257.69  5424.5  257.64
  5438.7  259.92  5446.1  258.97  5460.3   260.5  5467.1  262.72  5481.3  264.37
    5629  270.94  5735.9  278.13  5771.7  279.61  5778.5  281.07  5813.9  282.55
#Mann= 6 ,-1 , 0
  4664.6     .05       0  4683.9     .12       0  4967.3     .05       0
  4971.3     .12       0  5108.7     .07       0  5280.8     .12       0
Bank Sta=4967.3,4971.3
XS Rating Curve= 0 ,0
Exp/Cntr=0.3,0.1

Type RM Length L Ch R = 1 ,22166   ,337,337,337
BEGIN DESCRIPTION:
Stream0498 40.0
END DESCRIPTION:
XS GIS Cut Line= 3
      2527404.67     13623843.98      2527105.88     13624380.85
      2526826.24     13624930.82
#Sta/Elev= 30
  4391.7  274.84  4415.8  272.44  4443.4  271.19  4459.4  272.02  4481.1  269.84
  4530.3  266.92  4562.3  267.97  4611.5  265.15  4692.7  262.74  4714.4  263.47
  4736.2  262.09  4770.3  261.69  4789.9   260.6  4817.3  261.17  4920.2  257.28
  4952.2  256.99    4963  249.04  4963.2  248.54  4967.2  249.04  4973.9  256.43
    4988  255.01  5017.7  256.58  5055.6  255.24  5062.2  255.88  5078.1  254.68
  5090.1  259.93    5129   262.6  5212.4  266.01  5373.7  274.35  5623.1  288.92
#Mann= 4 ,-1 , 0
  4391.7     .05       0  4770.3     .12       0    4963     .05       0
  4967.2     .12       0
Bank Sta=4963,4967.2
XS Rating Curve= 0 ,0
Exp/Cntr=0.3,0.1

Type RM Length L Ch R = 1 ,21829   ,420,420,420
BEGIN DESCRIPTION:
Stream0498 39.0
END DESCRIPTION:
XS GIS Cut Line= 3
      2527224.98     13623825.02        2526825.       13624225.
      2526674.98     13624625.05
#Sta/Elev= 30
  4429.6  267.92  4457.8  268.27  4556.8  264.76    4571  263.78  4599.3  264.43
  4655.8  261.72    4670  261.36  4684.1  262.23  4797.3   258.4  4897.2  257.17
  4924.5  256.76  4981.1  254.26  4991.7  255.06    5005  255.07  5008.2  248.95
  5008.5  248.45  5012.2  248.45  5012.5  248.95  5016.6  255.24  5035.3  255.08
  5080.7  252.83  5102.1  255.72  5112.7  255.35  5156.3  258.35  5198.2  261.86
  5236.4  265.93  5266.7  266.78    5305  269.43  5369.1  271.57  5422.5   274.7
#Mann= 4 ,-1 , 0
  4429.6     .05       0  4897.2     .12       0  5008.2     .05       0
  5012.5     .12       0
Bank Sta=5008.2,5012.5
XS Rating Curve= 0 ,0
Exp/Cntr=0.3,0.1

Type RM Length L Ch R = 1 ,21409   ,447,447,447
BEGIN DESCRIPTION:
Stream0498 38.0
END DESCRIPTION:
XS GIS Cut Line= 3
      2526925.02     13623624.98        2526575.       13624025.
      2526374.98     13624425.04
#Sta/Elev= 30
  4462.4  265.15  4490.4  264.22  4512.3  264.85  4533.1  263.22  4575.9  261.24
  4604.3  261.73  4639.4  260.25  4873.9     256  4887.6  254.95  4923.2   254.1
  4944.1  252.82  4965.9  252.77  4972.6  252.15  4984.7   249.3  4984.9   248.8
  4988.7   248.8    4989   249.3  4990.6  252.12  5002.3   251.8  5007.9  250.13
  5024.7  251.79  5030.3  253.97  5052.6  255.51  5069.4  255.39  5091.8  257.16
  5097.4  256.67  5105.7     258  5119.7  257.31  5136.5  257.85  5441.2   269.5
#Mann= 3 ,-1 , 0
  4462.4     .05       0  4984.7     .05       0    4989     .12       0
Bank Sta=4984.7,4989
XS Rating Curve= 0 ,0
Exp/Cntr=0.3,0.1

Type RM Length L Ch R = 1 ,20962   ,417,417,417
BEGIN DESCRIPTION:
Stream0498 37.0
END DESCRIPTION:
XS GIS Cut Line= 3
      2526524.99     13623375.02        2526275.       13623725.
        2525925.     13624524.99
#Sta/Elev= 30
  4569.9  264.88  4633.8  260.85  4655.9  261.19    4764  256.95  4778.8  256.16
  4799.7  253.35  4841.5  250.81  4856.2  248.57  4887.2  248.54  4906.6  251.07
  4921.3  248.64  4927.5  250.49  4936.1  250.12  4942.2  251.46  4963.1   251.1
  4971.7  248.11  4975.7  247.89    4976  247.39  4980.1  247.89  4986.5  248.32
  4992.6  250.46    5009  249.42  5014.4  252.56  5043.7  253.07  5061.2   252.4
  5259.2  256.86  5316.9   256.9  5340.3  258.31  5403.9  259.75  5873.2  284.16
#Mann= 4 ,-1 , 0
  4569.9     .05       0  4887.2     .12       0  4975.7     .05       0
  4980.1     .12       0
Bank Sta=4975.7,4980.1
XS Rating Curve= 0 ,0
Exp/Cntr=0.3,0.1

Type RM Length L Ch R = 1 ,20545   ,444,444,444
BEGIN DESCRIPTION:
Stream0498 36.0
END DESCRIPTION:
XS GIS Cut Line= 3
      2526075.02     13623274.96        2525975.       13623475.
      2525774.99     13624275.03
#Sta/Elev= 30
  4777.1  256.82  4852.6   255.2  4880.6  252.43  4897.3  249.69  4911.3   248.9
  4925.3  248.61  4933.7  249.31  4964.4  248.51    4970  247.02  4978.4  243.31
  4984.6   239.3  4984.9   238.8    4989   239.3  4991.7  243.57  4992.4  244.68
  5003.3  243.82  5018.8   249.3  5023.9   248.4  5031.7  249.49    5042  249.65
  5072.9   247.9  5101.2  249.15  5188.9   248.8  5230.1     250  5266.2   252.2
  5320.3  252.29  5477.5  256.58  5629.5  263.07  5811.7  272.49  5825.4  273.25
#Mann= 5 ,-1 , 0
  4777.1     .05       0  4984.6     .05       0    4989     .05       0
  4991.7     .12       0  5811.7     .07       0
Bank Sta=4984.6,4989
XS Rating Curve= 0 ,0
Exp/Cntr=0.3,0.1

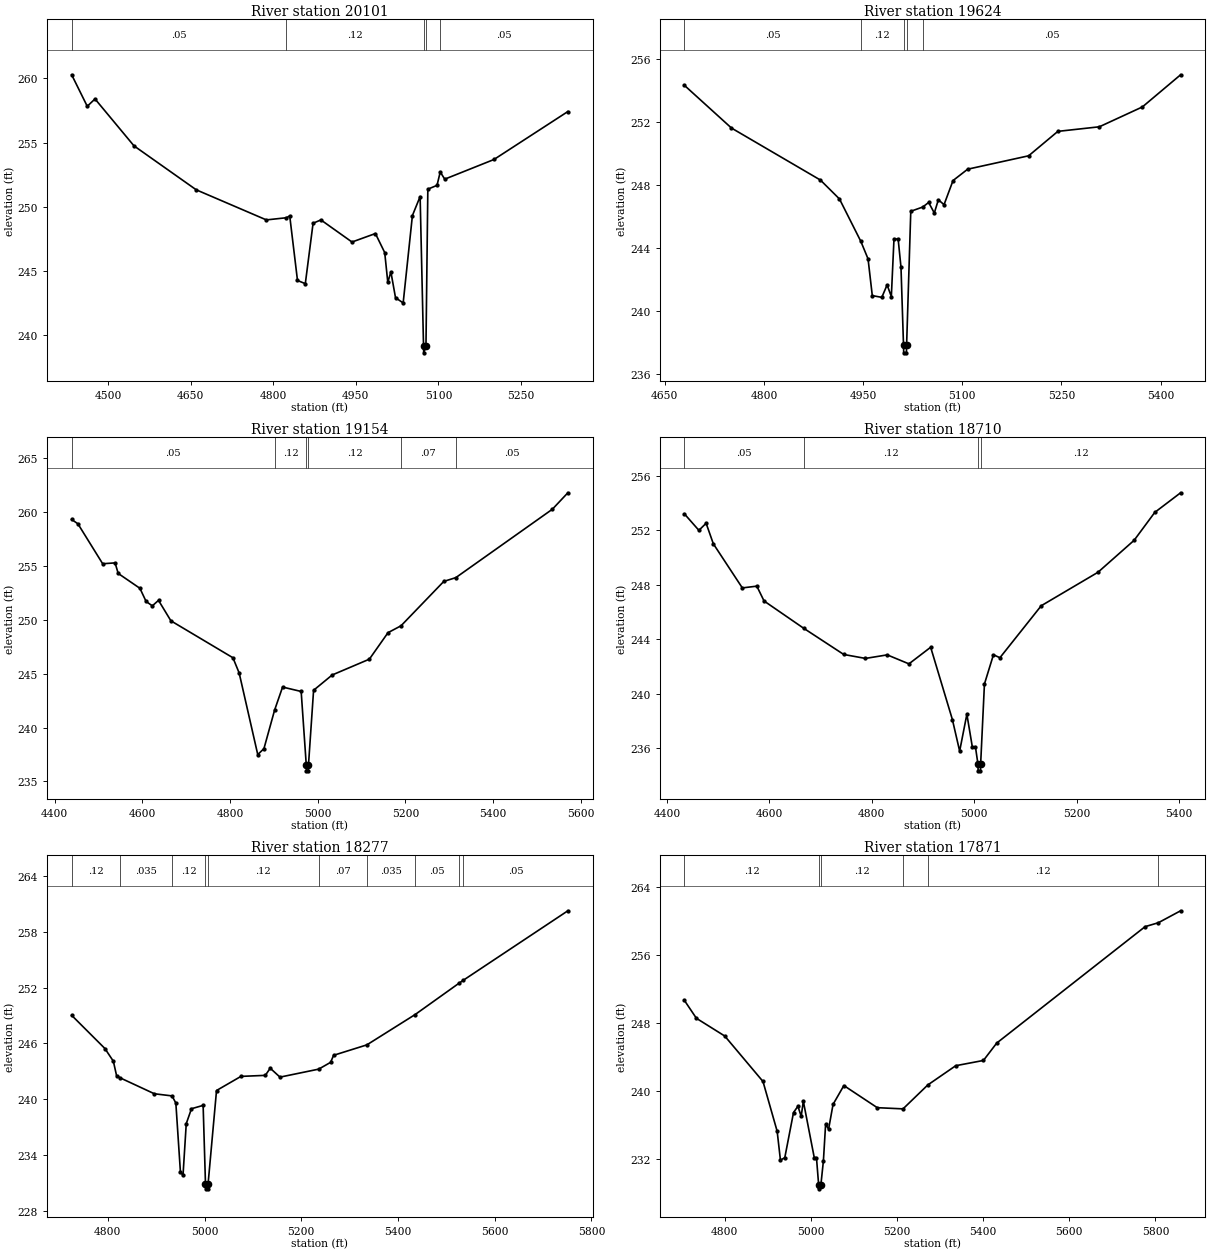
Type RM Length L Ch R = 1 ,20101   ,477,477,477
BEGIN DESCRIPTION:
Stream0498 35.0
END DESCRIPTION:
XS GIS Cut Line= 3
      2526025.01     13623124.99        2525625.       13623525.
      2525325.01       13623675.
#Sta/Elev= 30
    4434  260.27  4462.3  257.82  4476.4  258.39  4547.2  254.74  4660.3  251.32
  4787.6  248.98  4824.1  249.15    4830  249.29  4844.1  244.27  4858.3  244.02
  4872.4  248.72  4886.6  248.98  4943.1  247.26  4985.6  247.92  5002.5  246.44
  5008.1  244.12  5013.7  244.94  5022.1  242.93    5036  242.52  5052.8  249.32
  5066.8   250.8    5073  239.14  5073.3  238.64  5077.4  239.14  5080.8  251.37
  5097.5  251.67  5103.3  252.71  5111.5  252.15  5200.9  253.68  5335.1  257.41
#Mann= 5 ,-1 , 0
    4434     .05       0  4824.1     .12       0    5073     .05       0
  5077.4     .12       0  5103.3     .05       0
Bank Sta=5073,5077.4
XS Rating Curve= 0 ,0
Exp/Cntr=0.3,0.1

Type RM Length L Ch R = 1 ,19624   ,470,470,470
BEGIN DESCRIPTION:
Stream0498 34.0
END DESCRIPTION:
XS GIS Cut Line= 3
      2525674.99     13622925.01        2525425.       13623125.
      2525174.98     13623475.03
#Sta/Elev= 30
  4679.8  254.32    4751  251.61  4885.5  248.31  4914.3  247.11  4946.6  244.42
  4957.5  243.31  4963.9  240.98  4978.3  240.87  4986.3  241.66  4992.7  240.92
  4996.7  244.57    5003  244.57  5007.3  242.78  5011.1  237.85  5011.4  237.35
  5015.5  237.35  5015.8  237.85  5022.1  246.33  5040.2   246.6  5049.1  246.89
  5057.7  246.22  5063.8  247.06  5072.4  246.75    5086  248.28  5108.1     249
  5200.3  249.85  5244.5   251.4  5307.2  251.69  5372.3  252.95  5430.1  254.99
#Mann= 5 ,-1 , 0
  4679.8     .05       0  4946.6     .12       0  5011.1     .05       0
  5015.8     .12       0  5040.2     .05       0
Bank Sta=5011.1,5015.8
XS Rating Curve= 0 ,0
Exp/Cntr=0.3,0.1

Type RM Length L Ch R = 1 ,19154   ,444,444,444
BEGIN DESCRIPTION:
Stream0498 33.0
END DESCRIPTION:
XS GIS Cut Line= 3
      2525475.01     13622524.99        2525075.       13622925.
      2524674.99     13623325.01
#Sta/Elev= 30
  4438.9  259.32  4453.1  258.92  4509.6  255.21  4537.9  255.29    4545  254.31
  4594.5  252.93  4608.6  251.71  4622.8   251.3  4636.9  251.81  4665.2  249.91
  4806.6  246.48  4820.8  245.07  4863.2  237.49  4877.3  238.04  4901.7  241.63
  4919.8  243.76  4962.2  243.35  4973.9  236.48  4974.3  235.98  4978.4  235.98
  4978.8  236.48  4990.5  243.46  5032.9  244.88  5117.7  246.35  5160.2  248.81
  5189.9  249.45  5287.4  253.57  5314.8  253.92  5534.9  260.27  5570.3   261.8
#Mann= 6 ,-1 , 0
  4438.9     .05       0  4901.7     .12       0  4973.9     .05       0
  4978.8     .12       0  5189.9     .07       0  5314.8     .05       0
Bank Sta=4973.9,4978.8
XS Rating Curve= 0 ,0
Exp/Cntr=0.3,0.1

Type RM Length L Ch R = 1 ,18710   ,433,433,433
BEGIN DESCRIPTION:
Stream0498 32.0
END DESCRIPTION:
XS GIS Cut Line= 3
      2525124.98     13622275.02        2524725.       13622675.
        2524675.     13623075.03
#Sta/Elev= 30
    4434  253.22  4462.3  252.01  4476.4  252.53  4490.5  251.02  4547.1  247.78
  4575.4  247.91  4589.5  246.82  4666.7  244.82  4745.1  242.89  4787.5   242.6
    4830  242.86  4872.4   242.2  4914.8  243.42  4957.2  238.11  4971.4  235.79
  4985.5   238.5  4996.1  236.11  5002.2  236.11  5007.1  234.84  5007.5  234.34
    5012  234.34  5012.4  234.84  5019.8  240.72  5037.4  242.87    5050  242.65
  5130.7  246.47  5241.5  248.93  5312.1  251.28  5352.4  253.33  5402.8  254.77
#Mann= 4 ,-1 , 0
    4434     .05       0  4666.7     .12       0  5007.1     .05       0
  5012.4     .12       0
Bank Sta=5007.1,5012.4
XS Rating Curve= 0 ,0
Exp/Cntr=0.3,0.1

Type RM Length L Ch R = 1 ,18277   ,406,406,406
BEGIN DESCRIPTION:
Stream0498 31.0
END DESCRIPTION:
XS GIS Cut Line= 3
      2524974.99       13622175.        2524725.       13622275.
      2523974.99       13622375.
#Sta/Elev= 30
  4725.3  249.01    4794  245.44  4811.5  244.07  4818.2  242.51  4825.6  242.28
  4896.3  240.57  4932.8  240.34  4940.7  239.57  4950.1  232.19  4955.5  231.78
  4962.2  237.35    4973  238.96  4997.1  239.32    5002  230.84  5002.4  230.34
  5006.9  230.34  5007.3  230.84  5024.8  240.92  5075.3  242.44  5125.7  242.55
  5135.8  243.32    5156  242.36    5236  243.22  5260.6  243.95  5266.9  244.71
  5335.6  245.83  5435.3  249.09  5527.1   252.5  5534.9  252.78  5751.2  260.26
#Mann= 10 ,-1 , 0
  4725.3     .12       0  4825.6    .035       0  4932.8     .12       0
    5002     .05       0  5007.3     .12       0    5236     .07       0
  5335.6    .035       0  5435.3     .05       0  5527.1     .12       0
  5534.9     .05       0
Bank Sta=5002,5007.3
XS Rating Curve= 0 ,0
Exp/Cntr=0.3,0.1

Type RM Length L Ch R = 1 ,17871   ,451,451,451
BEGIN DESCRIPTION:
Stream0498 30.0
END DESCRIPTION:
XS GIS Cut Line= 3
      2524974.97       13621925.        2524675.       13621975.
      2523849.22     13622168.69
#Sta/Elev= 30
  4706.1  250.68    4734  248.57  4799.8  246.48  4888.6  241.12  4921.5  235.25
  4929.1  231.85  4939.2  232.13  4959.5  237.46  4969.7   238.2  4977.3  237.01
  4982.3  238.79  5007.7  232.13  5012.8  232.13  5017.8  228.96  5018.2  228.46
  5023.1  228.96  5028.9  231.76    5034  236.06    5041  235.51  5051.3  238.42
  5076.4  240.64    5154  238.03  5213.8  237.89  5271.3  240.71  5336.2  242.98
  5400.5   243.6  5431.4  245.65    5776  259.38  5806.7  259.84  5858.4  261.25
#Mann= 6 ,-1 , 0
  4706.1     .12       0  5017.8     .05       0  5023.1     .12       0
  5213.8     .07       0  5271.3     .12       0  5806.7     .07       0
Bank Sta=5017.8,5023.1
XS Rating Curve= 0 ,0
Exp/Cntr=0.3,0.1

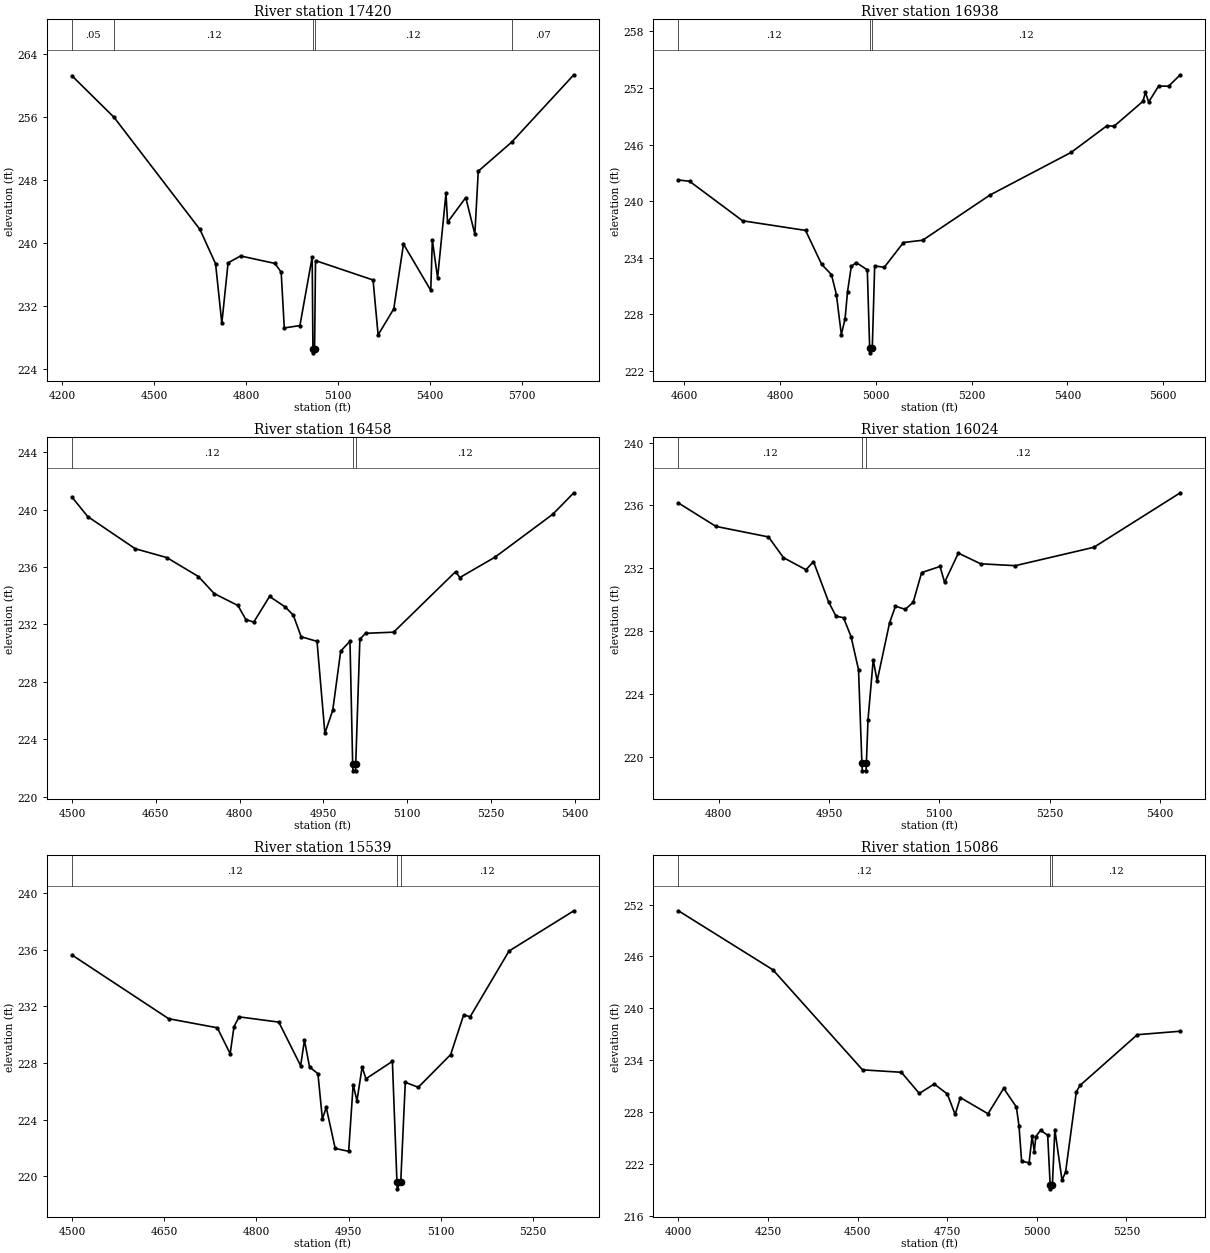
Type RM Length L Ch R = 1 ,17420   ,482,482,482
BEGIN DESCRIPTION:
Stream0498 29.0
END DESCRIPTION:
XS GIS Cut Line= 3
      2525224.99       13621825.        2524475.       13621675.
       2523619.6     13621493.92
#Sta/Elev= 30
  4231.2  261.28  4368.6     256  4649.3  241.72  4700.3  237.35  4720.7  229.79
  4741.1  237.47  4781.9  238.35  4894.1   237.4  4914.5  236.29  4924.7  229.19
  4975.7  229.49  5015.8  238.21  5018.2  226.52  5018.6  226.02  5023.6  226.52
  5026.7  237.76  5214.6  235.29  5231.1   228.3  5282.3  231.62    5314  239.86
  5403.1  233.97  5408.2  240.36  5425.4  235.56  5452.8  246.33  5457.9  242.64
  5517.3  245.78  5547.1  241.13  5558.2  249.14  5666.9  252.82  5870.4  261.41
#Mann= 5 ,-1 , 0
  4231.2     .05       0  4368.6     .12       0  5018.2     .05       0
  5023.6     .12       0  5666.9     .07       0
Bank Sta=5018.2,5023.6
XS Rating Curve= 0 ,0
Exp/Cntr=0.3,0.1

Type RM Length L Ch R = 1 ,16938   ,480,480,480
BEGIN DESCRIPTION:
Stream0498 28.0
END DESCRIPTION:
XS GIS Cut Line= 3
      2524874.99       13621325.        2524475.       13621225.
      2523861.19     13621060.78
#Sta/Elev= 30
  4588.1  242.24  4611.3  242.11  4722.1  237.92  4853.5   236.9    4887  233.31
  4907.6  232.22  4917.9  230.09  4928.2  225.86    4936  227.55  4941.1   230.4
  4948.9  233.08  4959.2   233.5  4982.4  232.72  4987.3  224.43  4987.8  223.93
  4992.8  224.43  4997.8  233.14  5017.8  232.99  5057.9  235.62  5097.9  235.86
  5238.5  240.65    5408  245.17  5482.9     248  5497.3  247.93  5557.8  250.58
    5563  251.53  5569.7   250.5  5590.4  252.19  5611.2  252.18  5635.8  253.39
#Mann= 3 ,-1 , 0
  4588.1     .12       0  4987.3     .05       0  4992.8     .12       0
Bank Sta=4987.3,4992.8
XS Rating Curve= 0 ,0
Exp/Cntr=0.3,0.1

Type RM Length L Ch R = 1 ,16458   ,434,434,434
BEGIN DESCRIPTION:
Stream0498 27.0
END DESCRIPTION:
XS GIS Cut Line= 3
      2524925.03     13621125.03        2524575.       13620775.
      2524175.03       13620825.
#Sta/Elev= 30
  4500.1  240.88  4528.4  239.52  4613.3  237.28  4669.9  236.66  4726.4  235.34
  4754.7  234.15  4797.1  233.32  4811.3  232.34  4825.4  232.16  4853.7  233.95
    4882  233.21  4896.1  232.65  4910.3  231.14  4938.6  230.82  4952.7  224.41
  4966.8  226.02    4981  230.14  4997.6  230.83  5002.4  222.29  5002.9  221.79
  5007.5  221.79  5007.9  222.29  5015.3  230.97  5025.4  231.38  5075.7  231.46
  5186.6  235.68  5194.2  235.27  5257.1  236.69  5360.4  239.68  5398.2  241.18
#Mann= 3 ,-1 , 0
  4500.1     .12       0  5002.4     .05       0  5007.9     .12       0
Bank Sta=5002.4,5007.9
XS Rating Curve= 0 ,0
Exp/Cntr=0.3,0.1

Type RM Length L Ch R = 1 ,16024   ,485,485,485
BEGIN DESCRIPTION:
Stream0498 26.0
END DESCRIPTION:
XS GIS Cut Line= 3
      2524925.04     13620425.01        2524675.       13620375.
      2524274.99       13620525.
#Sta/Elev= 30
  4745.4  236.15  4796.4  234.66  4867.8  233.99  4888.2  232.67  4918.8   231.9
    4929  232.42  4949.4  229.87  4959.6  228.94  4969.8  228.85    4980  227.65
  4990.2  225.54  4994.8   219.6  4995.3   219.1  5000.4   219.1  5000.9   219.6
  5003.1  222.35  5010.2  226.17  5015.5  224.82  5032.4  228.52  5040.4  229.58
  5053.8  229.38  5064.5  229.83    5076  231.72    5101  232.11  5107.2   231.1
  5125.9  232.96  5156.1  232.28  5203.3  232.16  5310.1  233.33  5427.6   236.8
#Mann= 3 ,-1 , 0
  4745.4     .12       0  4994.8     .05       0  5000.9     .12       0
Bank Sta=4994.8,5000.9
XS Rating Curve= 0 ,0
Exp/Cntr=0.3,0.1

Type RM Length L Ch R = 1 ,15539   ,453,453,453
BEGIN DESCRIPTION:
Stream0498 25.0
END DESCRIPTION:
XS GIS Cut Line= 3
      2524974.99     13620224.99        2524575.       13619925.
      2524275.01       13619825.
#Sta/Elev= 30
    4500  235.62  4657.3  231.12  4736.4  230.48  4757.3  228.65  4763.5  230.56
  4771.9  231.25  4836.4  230.88  4871.9   227.8  4878.1  229.61  4886.4  227.71
    4900  227.24  4907.3  224.03  4913.5  224.86  4928.1  221.96    4950  221.76
  4957.3  226.47  4963.5  225.33  4971.9  227.71  4978.1  226.88  5021.1  228.11
  5028.5  219.61    5029  219.11  5034.7  219.61  5042.1  226.63  5063.2  226.28
  5115.9  228.59    5137  231.39  5147.6  231.26  5210.8   235.9  5316.2  238.74
#Mann= 3 ,-1 , 0
    4500     .12       0  5028.5     .05       0  5034.7     .12       0
Bank Sta=5028.5,5034.7
XS Rating Curve= 0 ,0
Exp/Cntr=0.3,0.1

Type RM Length L Ch R = 1 ,15086   ,475,475,475
BEGIN DESCRIPTION:
Stream0498 24.0
END DESCRIPTION:
XS GIS Cut Line= 3
      2525475.02     13620175.02        2524675.       13619575.
      2524275.03       13619575.
#Sta/Elev= 30
  4000.2  251.28  4263.8  244.45  4513.8  232.87  4622.1  232.59  4672.1  230.14
  4713.8  231.23  4750.2  230.08  4772.1  227.71  4786.7  229.66  4863.8  227.79
  4907.5  230.73  4942.9  228.57  4950.2  226.38  4957.5   222.3  4978.4  222.11
  4986.7  225.19  4992.9   223.4  4997.1  225.14  5010.2  225.88  5030.2  225.31
  5037.1   219.6  5037.6   219.1  5043.4   219.6  5050.2  225.96  5070.2   220.1
  5080.2  221.06  5110.2  230.32  5120.2  231.06  5280.2  236.94  5400.2  237.34
#Mann= 3 ,-1 , 0
  4000.2     .12       0  5037.1     .05       0  5043.4     .12       0
Bank Sta=5037.1,5043.4
XS Rating Curve= 0 ,0
Exp/Cntr=0.3,0.1

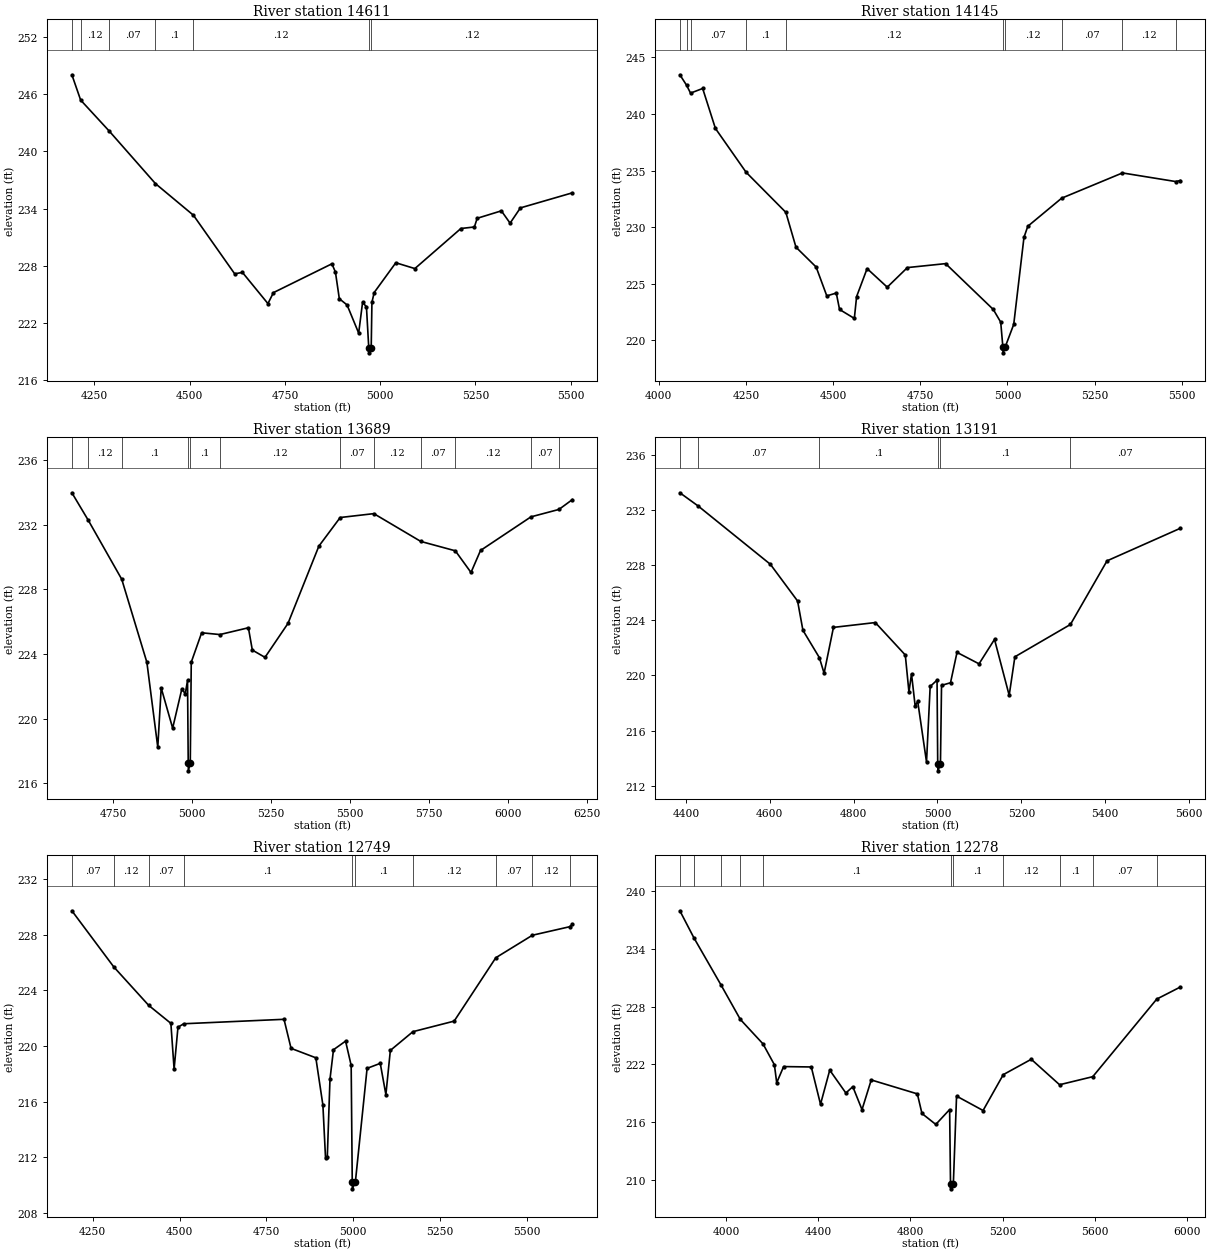
Type RM Length L Ch R = 1 ,14611   ,466,466,466
BEGIN DESCRIPTION:
Stream0498 23.0
END DESCRIPTION:
XS GIS Cut Line= 3
      2525475.05     13619325.01        2524675.       13619175.
      2524274.99     13619475.01
#Sta/Elev= 30
  4190.8  248.03  4213.8  245.38  4289.3  242.11  4410.3  236.62  4509.9  233.31
  4618.2  227.17  4638.5  227.32  4705.5  224.05  4719.9   225.2  4873.4  228.22
  4882.7  227.35  4892.9  224.56  4913.2  223.91  4943.7  220.96  4953.9  224.17
  4964.1  223.72  4970.2  219.39  4970.7  218.89  4976.6  219.39  4978.5  224.18
  4984.4  225.21  5041.2  228.33  5091.2  227.72  5212.1  231.92  5247.5  232.08
  5254.8  232.99  5318.3  233.77  5341.2  232.48  5368.3  234.08  5504.8  235.66
#Mann= 7 ,-1 , 0
  4190.8     .07       0  4213.8     .12       0  4289.3     .07       0
  4410.3      .1       0  4509.9     .12       0  4970.2     .05       0
  4976.6     .12       0
Bank Sta=4970.2,4976.6
XS Rating Curve= 0 ,0
Exp/Cntr=0.3,0.1

Type RM Length L Ch R = 1 ,14145   ,456,456,456
BEGIN DESCRIPTION:
Stream0498 22.0
END DESCRIPTION:
XS GIS Cut Line= 3
      2525424.96     13619224.97        2524625.       13618725.
      2524174.99       13618925.
#Sta/Elev= 30
  4060.5  243.47  4079.7  242.55  4091.1  241.85  4125.9  242.26  4162.5  238.73
  4250.5  234.86  4364.5  231.32  4393.6  228.24  4451.4  226.49    4482  223.94
  4509.2  224.19  4518.6  222.74    4561  221.95  4567.5  223.88  4597.6  226.35
  4655.4  224.71  4713.2  226.44  4822.8  226.79  4959.6  222.74  4980.9  221.62
  4987.1  219.41  4987.6  218.91  4993.5  219.41  5018.2  221.42  5047.6  229.11
  5058.6  230.09  5155.7  232.57  5330.1   234.8  5482.7  234.04  5496.3  234.13
#Mann= 10 ,-1 , 0
  4060.5     .07       0  4079.7     .12       0  4091.1     .07       0
  4250.5      .1       0  4364.5     .12       0  4987.1     .05       0
  4993.5     .12       0  5155.7     .07       0  5330.1     .12       0
  5482.7     .07       0
Bank Sta=4987.1,4993.5
XS Rating Curve= 0 ,0
Exp/Cntr=0.3,0.1

Type RM Length L Ch R = 1 ,13689   ,498,498,498
BEGIN DESCRIPTION:
Stream0498 21.0
END DESCRIPTION:
XS GIS Cut Line= 3
      2525324.97     13618674.99        2524975.       13618525.
      2523775.01       13618425.
#Sta/Elev= 30
  4619.7  233.97  4671.9  232.26  4777.6  228.62  4857.2  223.48  4891.7  218.23
  4902.5   221.9  4938.8  219.41  4967.8  221.83  4978.7  221.54  4985.9  222.36
  4988.1  217.27  4988.6  216.77  4994.6  217.27  4997.7  223.49  5030.6  225.31
  5088.4   225.2  5178.6  225.62  5191.1  224.24  5231.2  223.79    5304  225.89
  5401.8  230.67  5469.3  232.44  5575.8  232.68  5724.6  230.96  5833.9  230.38
  5883.5  229.04  5913.6   230.4  6073.3  232.48    6162  232.94  6204.6  233.55
#Mann= 12 ,-1 , 0
  4619.7     .05       0  4671.9     .12       0  4777.6      .1       0
  4988.1     .05       0  4994.6      .1       0  5088.4     .12       0
  5469.3     .07       0  5575.8     .12       0  5724.6     .07       0
  5833.9     .12       0  6073.3     .07       0    6162     .05       0
Bank Sta=4988.1,4994.6
XS Rating Curve= 0 ,0
Exp/Cntr=0.3,0.1

Type RM Length L Ch R = 1 ,13191   ,442,442,442
BEGIN DESCRIPTION:
Stream0498 20.0
END DESCRIPTION:
XS GIS Cut Line= 3
      2525474.97     13618374.98        2524975.       13618025.
      2524474.99     13618325.01
#Sta/Elev= 30
  4385.8  233.23  4429.5  232.27  4601.6  228.05  4666.5  225.39  4679.2  223.27
  4718.4  221.29  4729.7  220.16    4752  223.48  4851.8  223.83  4923.3  221.48
    4932   218.8  4938.1  220.11  4946.8  217.79  4952.9  218.12  4973.9  213.73
  4982.6   219.2    4999  219.66  5000.6  213.59  5001.1  213.09  5007.1  213.59
  5009.7  219.28  5031.1  219.47  5046.6  221.67  5099.1  220.84    5136  222.61
    5171  218.56  5184.6  221.35    5317  223.69  5404.3   228.3  5579.2  230.66
#Mann= 6 ,-1 , 0
  4385.8     .05       0  4429.5     .07       0  4718.4      .1       0
  5000.6     .05       0  5007.1      .1       0    5317     .07       0
Bank Sta=5000.6,5007.1
XS Rating Curve= 0 ,0
Exp/Cntr=0.3,0.1

Type RM Length L Ch R = 1 ,12749   ,471,471,471
BEGIN DESCRIPTION:
Stream0498 19.0
END DESCRIPTION:
XS GIS Cut Line= 3
      2525525.03     13617524.99        2524725.       13617675.
      2524424.98     13618225.03
#Sta/Elev= 30
  4190.1  229.73  4310.7  225.69  4411.3  222.92    4475  221.63  4484.3  218.34
  4495.4  221.35  4511.9   221.6  4800.6  221.92  4820.9  219.83  4892.2  219.15
  4912.5  215.75  4920.1  211.94  4925.2  212.02  4932.9  217.61    4943  219.73
  4977.8  220.35  4993.9   218.6    4997  210.22  4997.5  209.72    5006  210.22
  5039.7  218.39  5077.6  218.75  5093.8   216.5  5106.6  219.68  5171.6  221.03
  5290.3  221.79  5410.1  226.35  5515.5  227.97  5622.3  228.58  5630.6  228.75
#Mann= 10 ,-1 , 0
  4190.1     .07       0  4310.7     .12       0  4411.3     .07       0
  4511.9      .1       0    4997     .05       0    5006      .1       0
  5171.6     .12       0  5410.1     .07       0  5515.5     .12       0
  5622.3     .07       0
Bank Sta=4997,5006
XS Rating Curve= 0 ,0
Exp/Cntr=0.3,0.1

Type RM Length L Ch R = 1 ,12278   ,455,455,455
BEGIN DESCRIPTION:
Stream0498 18.0
END DESCRIPTION:
XS GIS Cut Line= 3
      2525674.95       13617325.        2524475.       13617325.
      2523924.99     13618125.02
#Sta/Elev= 30
  3800.1  237.98  3860.9  235.17  3979.3  230.23  4062.3  226.68  4160.7  224.13
  4210.1  221.96  4220.1  220.09  4250.1  221.77  4370.1  221.73  4410.1  217.85
  4450.1   221.4  4520.1  219.02  4550.1  219.68  4590.1  217.29  4630.1  220.38
  4830.1  218.93  4850.1  216.89  4910.1  215.75  4970.1   217.3  4973.9  209.55
  4974.4  209.05  4986.2  209.55  5000.1   218.7  5115.1   217.2  5202.7  220.93
  5324.1  222.53  5446.9  219.88  5590.9  220.72  5868.3  228.79  5970.9  230.05
#Mann= 11 ,-1 , 0
  3800.1    .035       0  3860.9     .12       0  3979.3     .07       0
  4062.3     .12       0  4160.7      .1       0  4973.9     .05       0
  4986.2      .1       0  5202.7     .12       0  5446.9      .1       0
  5590.9     .07       0  5868.3     .12       0
Bank Sta=4973.9,4986.2
XS Rating Curve= 0 ,0
Exp/Cntr=0.3,0.1