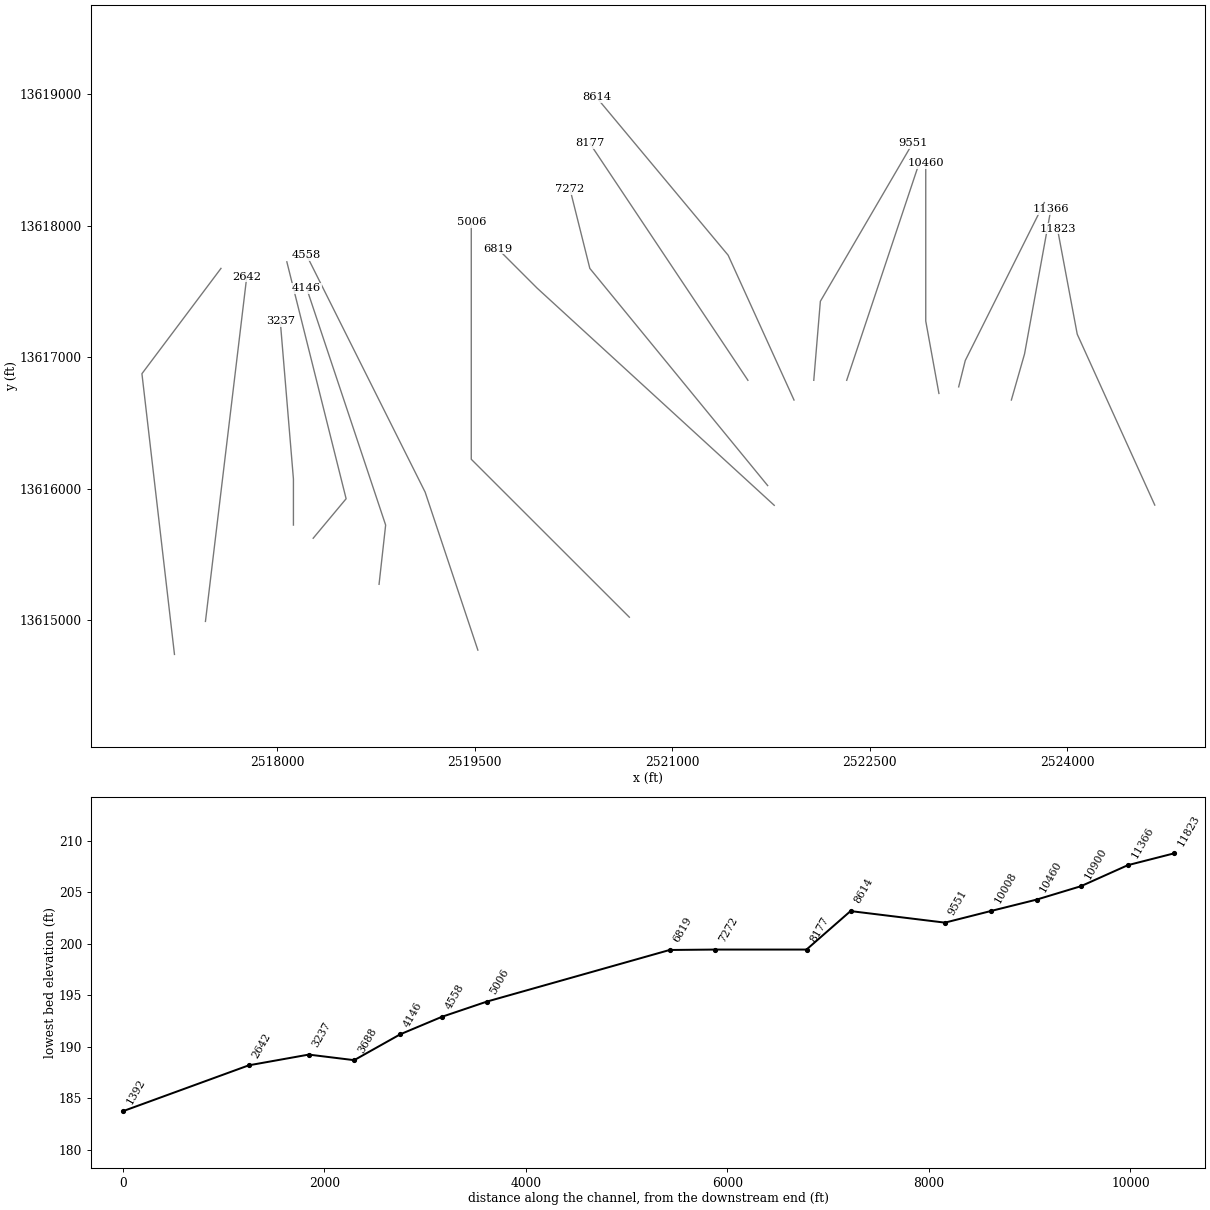
HEC-RAS study Stream0498.prj: Stream0498 Base Level Engineering

--- Stream0498.g01 (geometry) --- (continued)

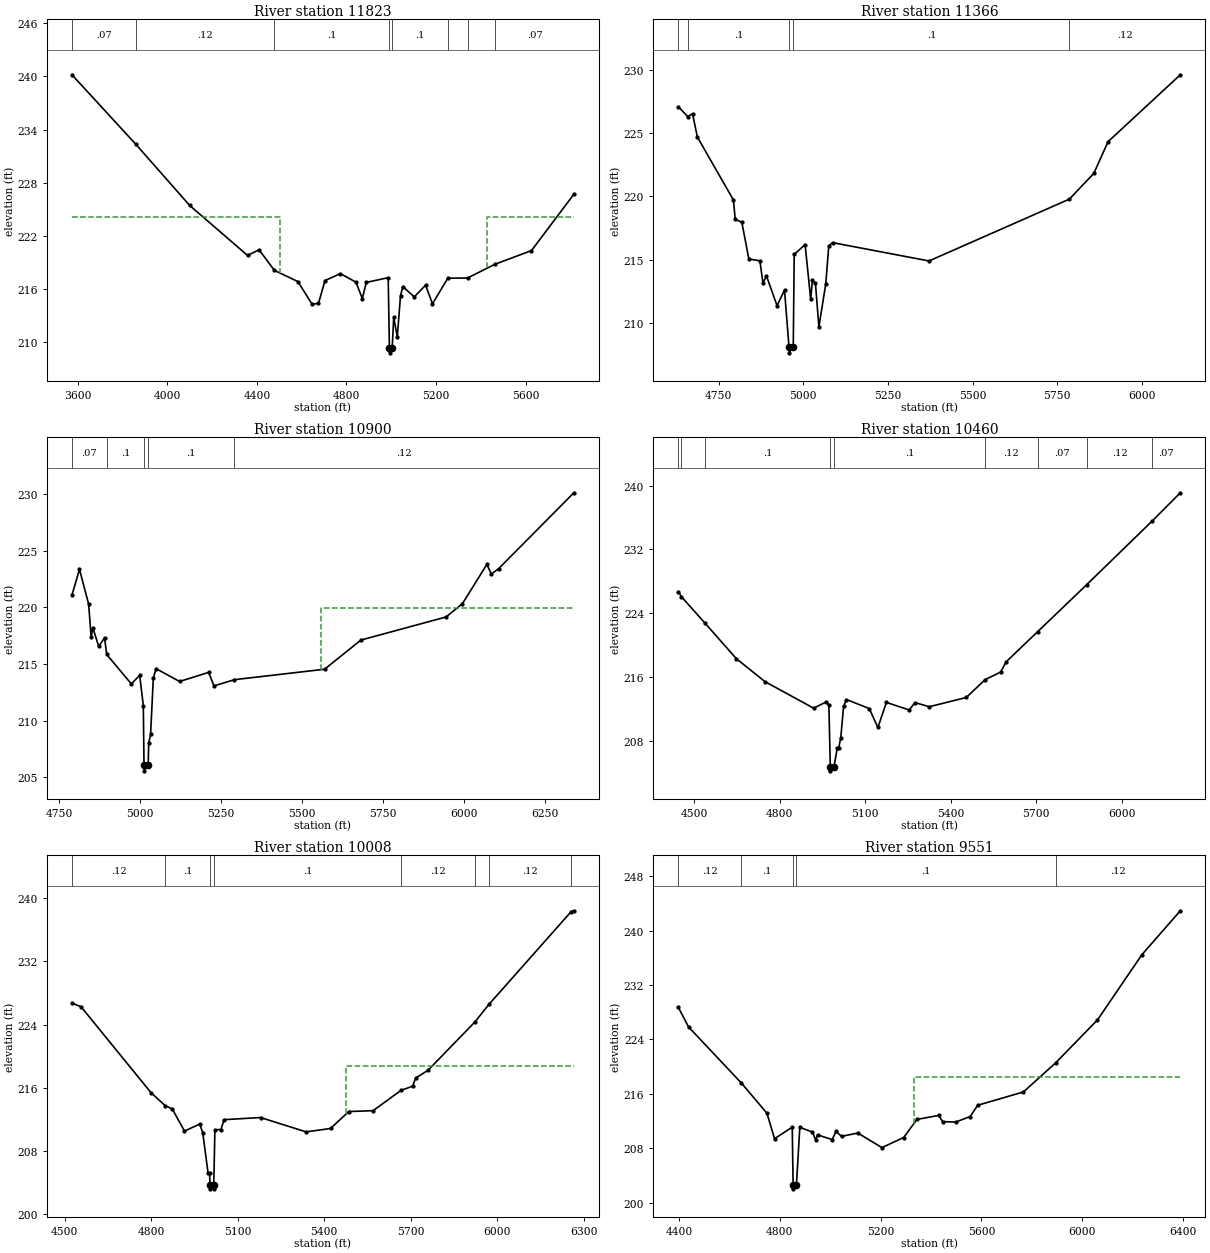
Type RM Length L Ch R = 1 ,11823   ,457,457,457
BEGIN DESCRIPTION:
Stream0498 17.0
END DESCRIPTION:
XS GIS Cut Line= 3
      2524663.58     13615876.87        2524075.       13617175.
      2523924.99     13617975.03
#Sta/Elev= 30
  3575.1  240.19  3859.4  232.35  4100.1  225.42  4358.4  219.77  4410.1   220.4
  4478.4  218.07  4583.2  216.81  4646.4  214.25    4675  214.34    4704  216.92
  4772.9  217.71  4842.1  216.74  4870.7  214.89  4888.3  216.71  4986.1  217.25
  4991.5  209.25    4992  208.75  5003.9  209.25  5010.6  212.75  5026.7  210.57
  5041.1  215.23  5051.3  216.24  5102.2  215.08    5153   216.4  5183.6  214.29
    5252  217.19  5339.9  217.21  5462.7  218.77  5625.3  220.31  5814.4  226.68
#Mann= 8 ,-1 , 0
  3575.1     .07       0  3859.4     .12       0  4478.4      .1       0
  4991.5     .05       0  5003.9      .1       0    5252     .12       0
  5339.9      .1       0  5462.7     .07       0
#XS Ineff= 2 , 0
       0  4503.5  224.11  5429.1       0  224.11
Permanent Ineff=
       F       F
Bank Sta=4991.5,5003.9
XS Rating Curve= 0 ,0
Exp/Cntr=0.3,0.1

Type RM Length L Ch R = 1 ,11366   ,466,466,466
BEGIN DESCRIPTION:
Stream0498 16.0
END DESCRIPTION:
XS GIS Cut Line= 3
      2523575.01     13616675.04        2523675.       13617025.
        2523875.     13618125.01
#Sta/Elev= 30
  4631.2   227.1  4658.6  226.33  4672.8  226.56  4687.1  224.71  4793.7  219.72
  4798.9  218.18  4818.4  217.96  4839.2  215.05  4871.7   214.9  4880.8  213.15
  4891.2   213.7  4922.4  211.35  4944.5  212.58  4957.6  208.11  4958.1  207.61
  4970.3  208.11  4973.1  215.41  5005.3  216.18  5021.8  211.86  5026.9  213.36
  5035.8  213.11    5046  209.66  5066.3  213.08  5075.2  216.09  5086.6  216.34
  5371.2  214.89  5785.7  219.79  5857.8  221.83  5899.8  224.34  6113.2  229.64
#Mann= 5 ,-1 , 0
  4631.2     .12       0  4658.6      .1       0  4957.6     .05       0
  4970.3      .1       0  5785.7     .12       0
Bank Sta=4957.6,4970.3
XS Rating Curve= 0 ,0
Exp/Cntr=0.3,0.1

Type RM Length L Ch R = 1 ,10900   ,440,440,440
BEGIN DESCRIPTION:
Stream0498 15.0
END DESCRIPTION:
XS GIS Cut Line= 3
        2523175.     13616775.01        2523225.       13616975.
      2523825.01     13618175.01
#Sta/Elev= 30
    4790  221.06  4813.2  223.34  4841.5  220.27  4849.3  217.34  4854.4   218.2
  4872.5  216.54  4890.5   217.3  4897.2  215.83    4973  213.24  4998.9  213.99
  5010.1  211.32  5012.2  206.07  5012.7  205.57  5024.9  206.07  5026.9  208.04
  5032.5  208.78  5040.9  213.73  5049.3  214.58  5121.9  213.45  5211.4  214.25
  5228.1  213.06  5291.1  213.61  5569.1  214.53  5680.9   217.1  5943.7  219.14
    5994   220.3  6069.5  223.77  6083.4  222.92  6105.8   223.4  6337.8  230.09
#Mann= 5 ,-1 , 0
    4790     .07       0  4897.2      .1       0  5012.2     .05       0
  5024.9      .1       0  5291.1     .12       0
#XS Ineff= 2 , 0
       0                  5558.6       0  219.97
Permanent Ineff=
       F       F
Bank Sta=5012.2,5024.9
XS Rating Curve= 0 ,0
Exp/Cntr=0.3,0.1

Type RM Length L Ch R = 1 ,10460   ,452,452,452
BEGIN DESCRIPTION:
Stream0498 14.0
END DESCRIPTION:
XS GIS Cut Line= 3
        2523025.       13616725.        2522925.       13617275.
        2522925.     13618474.98
#Sta/Elev= 30
  4445.5   226.7  4456.1  226.08  4537.2  222.83  4648.8  218.31  4749.1  215.44
  4919.4  212.12  4963.9  212.91  4972.8  212.53  4977.8  204.77  4978.3  204.27
  4990.6  204.77    5002  207.07    5007  207.07  5014.5  208.42  5024.5  212.37
  5034.5   213.2  5114.5  212.07  5144.5   209.7  5174.5  212.84  5254.5  211.89
  5274.5  212.82  5324.5   212.3  5454.5  213.46  5520.3  215.69  5574.5  216.64
  5594.5  217.94  5704.2  221.69    5877  227.61  6106.1  235.57  6204.5   239.1
#Mann= 9 ,-1 , 0
  4445.5     .05       0  4456.1     .07       0  4537.2      .1       0
  4977.8     .05       0  4990.6      .1       0  5520.3     .12       0
  5704.2     .07       0    5877     .12       0  6106.1     .07       0
Bank Sta=4977.8,4990.6
XS Rating Curve= 0 ,0
Exp/Cntr=0.3,0.1

Type RM Length L Ch R = 1 ,10008   ,457,457,457
BEGIN DESCRIPTION:
Stream0498 13.0
END DESCRIPTION:
XS GIS Cut Line= 3
      2522325.01     13616825.02        2522475.       13617275.
      2522874.99     13618474.97
#Sta/Elev= 30
  4525.7  226.72  4557.3  226.25  4799.7  215.36  4848.4  213.73  4873.5  213.29
  4915.7  210.49  4968.4  211.38  4978.9   210.3  4997.4  205.17  5002.7  205.17
  5004.1  203.67  5004.6  203.17  5016.6  203.17  5017.1  203.67  5021.1  210.65
  5042.2  210.69  5052.7  211.94  5179.2  212.21  5337.3  210.39  5421.7  210.82
  5484.9  212.97  5569.2  213.08  5666.3  215.66  5706.3  216.18  5716.8  217.22
    5759  218.18    5921  224.28  5970.4  226.54  6255.7  238.32  6264.9  238.42
#Mann= 8 ,-1 , 0
  4525.7     .12       0  4848.4      .1       0  5004.1     .05       0
  5017.1      .1       0  5666.3     .12       0    5921     .07       0
  5970.4     .12       0  6255.7     .07       0
#XS Ineff= 2 , 0
       0                  5475.5       0   218.8
Permanent Ineff=
       F       F
Bank Sta=5004.1,5017.1
XS Rating Curve= 0 ,0
Exp/Cntr=0.3,0.1

Type RM Length L Ch R = 1 ,9551    ,937,937,937
BEGIN DESCRIPTION:
Stream0498 12.0
END DESCRIPTION:
XS GIS Cut Line= 3
        2522075.     13616824.96        2522125.       13617425.
      2522825.02     13618625.03
#Sta/Elev= 30
  4397.9  228.69  4438.1  225.83  4647.2  217.61  4749.2  213.15  4779.3  209.41
  4849.5   211.1    4853  202.54  4853.5  202.04    4866  202.54  4879.6  211.07
  4929.8  210.39  4942.3  209.21  4949.8  209.97  5007.9  209.28  5023.2  210.48
  5045.1  209.75  5109.6  210.24  5205.5   208.1  5291.5  209.58  5344.4  212.24
  5430.4  212.83  5446.2  211.92  5497.8  211.85  5555.7  212.67  5585.1  214.32
    5767  216.28  5895.6  220.59  6060.6  226.86  6236.7  236.44  6389.3   242.9
#Mann= 5 ,-1 , 0
  4397.9     .12       0  4647.2      .1       0    4853     .05       0
    4866      .1       0  5895.6     .12       0
#XS Ineff= 2 , 0
       0                  5332.4       0  218.51
Permanent Ineff=
       F       F
Bank Sta=4853,4866
XS Rating Curve= 0 ,0
Exp/Cntr=0.3,0.1

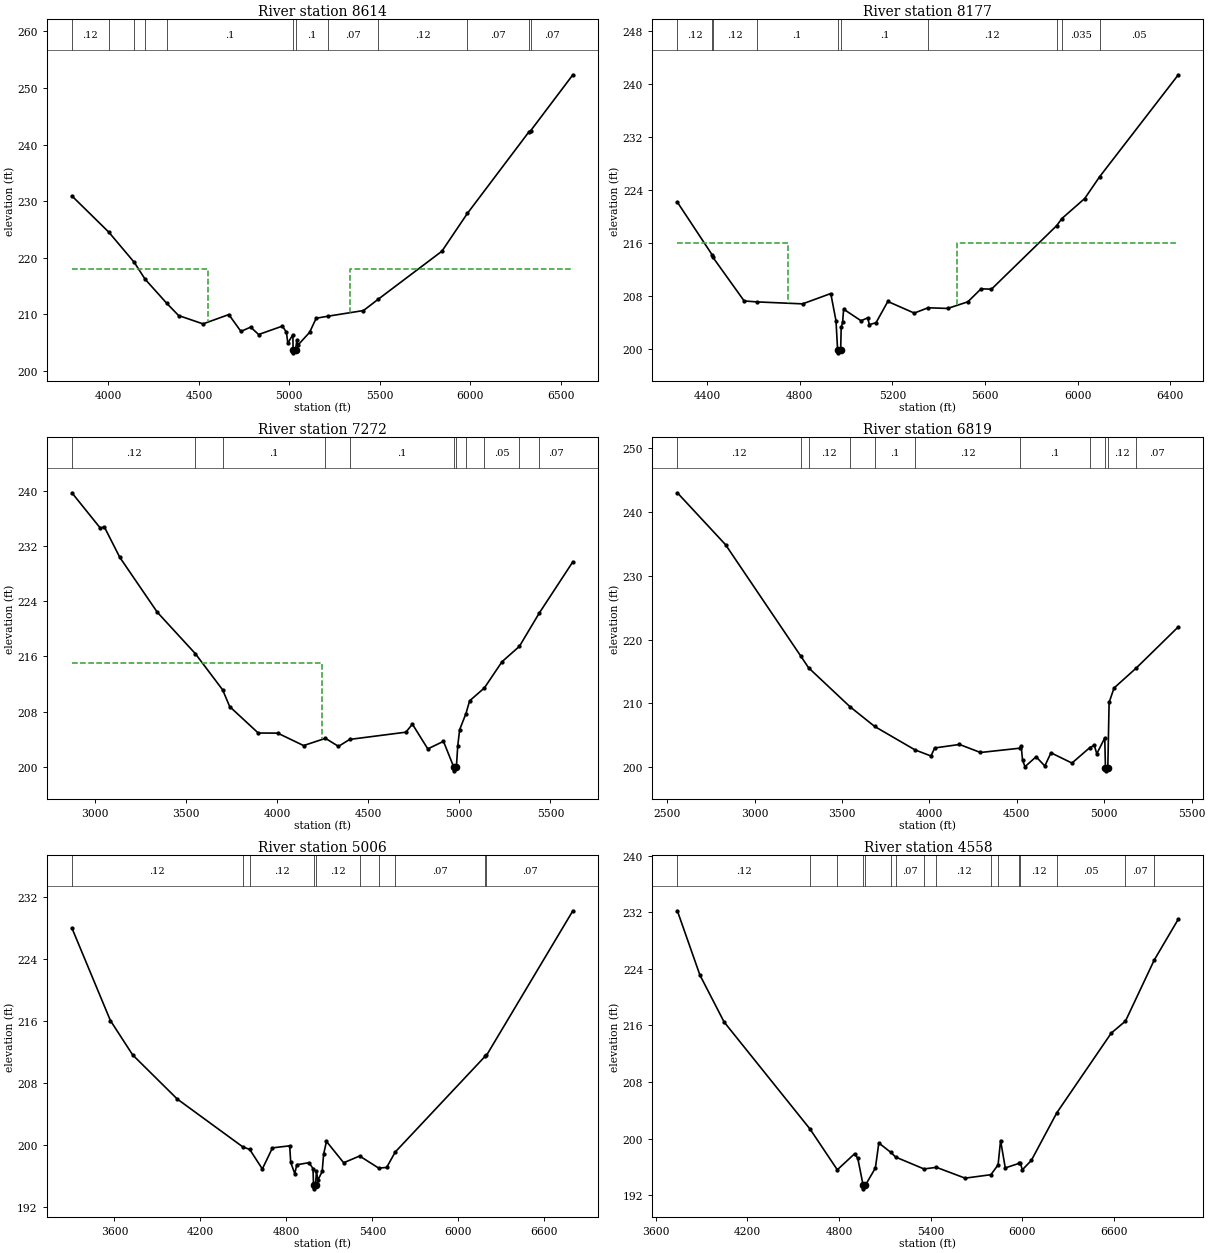
Type RM Length L Ch R = 1 ,8614    ,437,437,437
BEGIN DESCRIPTION:
Stream0498 11.0
END DESCRIPTION:
XS GIS Cut Line= 3
      2521925.01     13616674.98        2521425.       13617775.
      2520424.98     13618975.02
#Sta/Elev= 30
  3797.8  230.91  4001.5  224.52    4143  219.15  4202.7  216.18  4322.1  211.93
  4387.7  209.76  4522.8  208.28  4665.6  209.93  4732.6  206.95  4786.4  207.71
  4830.4   206.4  4962.2  207.89  4984.2  206.79  4991.8  204.87  5019.8  206.38
    5021  203.66  5021.5  203.16  5034.3  203.66  5041.9  205.44  5048.4  204.55
  5112.2  206.78  5148.7  209.28  5215.8  209.65  5410.3  210.64  5491.7  212.64
  5843.8  221.13  5984.6  227.81  6325.8  242.27  6335.3  242.47  6568.2  252.34
#Mann= 12 ,-1 , 0
  3797.8     .12       0  4001.5     .07       0    4143     .12       0
  4202.7     .07       0  4322.1      .1       0    5021     .05       0
  5034.3      .1       0  5215.8     .07       0  5491.7     .12       0
  5984.6     .07       0  6325.8     .05       0  6335.3     .07       0
#XS Ineff= 2 , 0
       0  4548.9  218.02  5334.4       0  218.02
Permanent Ineff=
       F       F
Bank Sta=5021,5034.3
XS Rating Curve= 0 ,0
Exp/Cntr=0.3,0.1

Type RM Length L Ch R = 1 ,8177    ,905,905,905
BEGIN DESCRIPTION:
Stream0498 10.0
END DESCRIPTION:
XS GIS Cut Line= 3
      2521575.02     13616824.97        2521175.       13617425.
      2520374.98     13618625.03
#Sta/Elev= 30
  4270.9  222.17    4421  214.23  4424.4  213.85  4559.4  207.26    4613  207.12
  4811.8  206.82  4933.5  208.38    4956  204.27  4962.9  199.93  4963.4  199.43
  4976.2  199.93  4978.5  203.27  4984.5  204.03    4989  206.02  5064.2  204.27
  5092.7  204.71  5100.2  203.69  5128.8  203.97  5179.8  207.18    5294  205.43
  5353.7  206.23  5438.2  206.13  5525.4  207.13  5582.5  209.09  5627.5  209.04
  5909.2  218.63    5931  219.68  6030.1  222.72  6094.4     226  6434.3  241.39
#Mann= 10 ,-1 , 0
  4270.9     .12       0    4421     .07       0  4424.4     .12       0
    4613      .1       0  4962.9     .05       0  4976.2      .1       0
  5353.7     .12       0  5909.2     .07       0    5931    .035       0
  6094.4     .05       0
#XS Ineff= 2 , 0
       0  4746.6  216.04  5478.2       0  216.04
Permanent Ineff=
       F       F
Bank Sta=4962.9,4976.2
XS Rating Curve= 0 ,0
Exp/Cntr=0.3,0.1

Type RM Length L Ch R = 1 ,7272    ,453,453,453
BEGIN DESCRIPTION:
Stream0498 9.0
END DESCRIPTION:
XS GIS Cut Line= 3
      2521725.02     13616024.98        2520375.       13617675.
        2520225.     13618275.01
#Sta/Elev= 30
  2872.9   239.7  3028.7  234.59  3050.9  234.76  3135.6  230.36  3341.7   222.4
  3550.6   216.4  3700.4  211.16  3739.3  208.73  3895.8  204.91  4002.8  204.89
  4144.9  203.09  4265.1  204.14  4336.5  202.97  4397.7  203.98  4706.9  205.03
  4742.1   206.2  4826.8  202.61  4912.9   203.7    4970  199.93  4970.5  199.43
  4983.6  199.93  4991.2  203.04  5001.6  205.39  5036.4  207.73  5056.4  209.57
  5137.2  211.43  5234.2  215.23  5329.7  217.46  5439.7  222.32  5623.3  229.71
#Mann= 11 ,-1 , 0
  2872.9     .12       0  3550.6     .07       0  3700.4      .1       0
  4265.1     .12       0  4397.7      .1       0    4970     .05       0
  4983.6      .1       0  5036.4     .12       0  5137.2     .05       0
  5329.7    .035       0  5439.7     .07       0
#XS Ineff= 2 , 0
       0  4248.1  215.03               0
Permanent Ineff=
       F       F
Bank Sta=4970,4983.6
XS Rating Curve= 0 ,0
Exp/Cntr=0.3,0.1

Type RM Length L Ch R = 1 ,6819    ,1813,1813,1813
BEGIN DESCRIPTION:
Stream0498 8.0
END DESCRIPTION:
XS GIS Cut Line= 3
      2521774.98     13615875.02        2519975.       13617525.
      2519674.97     13617825.03
#Sta/Elev= 30
  2557.7  243.03  2833.6  234.88  3262.6  217.45  3308.6  215.56  3545.5  209.45
  3686.9  206.35  3917.9  202.67  4008.9  201.72  4029.9  202.98  4171.7  203.53
  4291.9  202.27  4518.9  202.95    4525  203.31  4532.4   201.1  4546.6  200.04
  4610.1   201.6    4660  200.15  4695.2  202.22  4815.4  200.61  4917.5  203.04
  4943.1  203.41  4957.3  202.07    5003  204.55  5006.8  199.89  5007.3  199.39
  5020.5  199.89  5027.8  210.12  5056.1  212.39  5184.5  215.56  5423.8  221.99
#Mann= 11 ,-1 , 0
  2557.7     .12       0  3262.6     .07       0  3308.6     .12       0
  3545.5     .07       0  3686.9      .1       0  3917.9     .12       0
  4518.9      .1       0  4917.5     .12       0  5006.8     .05       0
  5020.5     .12       0  5184.5     .07       0
Bank Sta=5006.8,5020.5
XS Rating Curve= 0 ,0
Exp/Cntr=0.3,0.1

Type RM Length L Ch R = 1 ,5006    ,448,448,448
BEGIN DESCRIPTION:
Stream0498 7.0
END DESCRIPTION:
XS GIS Cut Line= 3
      2520675.03     13615024.97        2519475.       13616225.
        2519475.       13618025.
#Sta/Elev= 30
  3302.9  227.99  3571.6  216.07  3727.2  211.64  4038.3  205.96  4494.7  199.81
  4544.2  199.46  4632.3  196.95    4703  199.67  4823.2  199.93  4830.3   197.8
  4858.6  196.34  4872.7  197.49  4957.6  197.76  4985.9  197.01  4989.5  194.89
    4990  194.39  5003.5  194.89    5010  196.65    5020  195.49    5050  196.64
    5060  198.85    5080   200.5    5200  197.75  5311.4  198.62  5443.7  197.07
    5500  197.14  5559.9  199.13  6188.7  211.49    6197  211.58    6800  230.21
#Mann= 10 ,-1 , 0
  3302.9     .12       0  4494.7     .07       0  4544.2     .12       0
  4989.5     .05       0  5003.5     .12       0  5311.4     .07       0
  5443.7     .12       0  5559.9     .07       0  6188.7     .12       0
    6197     .07       0
Bank Sta=4989.5,5003.5
XS Rating Curve= 0 ,0
Exp/Cntr=0.3,0.1

Type RM Length L Ch R = 1 ,4558    ,412,412,412
BEGIN DESCRIPTION:
Stream0498 6.0
END DESCRIPTION:
XS GIS Cut Line= 3
      2519524.99     13614775.04        2519125.       13615975.
      2518225.01     13617774.98
#Sta/Elev= 30
  3742.5  232.21    3890  223.13  4048.1   216.5  4611.2  201.34    4789   195.6
    4902  197.87    4923  197.21    4958  193.41  4958.5  192.91  4972.4  193.41
  5038.1  195.86  5060.5  199.39  5138.8  198.07  5170.7   197.4  5356.1  195.72
  5437.1  195.95  5625.1  194.42  5793.9  194.91  5840.7   196.3  5857.1  199.74
  5887.8  195.87  5978.1  196.51  5985.7  196.58  5999.6   195.6  6058.3  196.93
    6225  203.66    6581  214.92  6674.1  216.62  6862.8  225.27  7019.8  231.03
#Mann= 16 ,-1 , 0
  3742.5     .12       0  4611.2     .07       0    4789     .12       0
    4958     .05       0  4972.4     .12       0  5138.8     .12       0
  5170.7     .07       0  5356.1      .1       0  5437.1     .12       0
  5793.9     .07       0  5840.7     .12       0  5978.1     .07       0
  5985.7     .12       0    6225     .05       0  6674.1     .07       0
  6862.8     .05       0
Bank Sta=4958,4972.4
XS Rating Curve= 0 ,0
Exp/Cntr=0.3,0.1

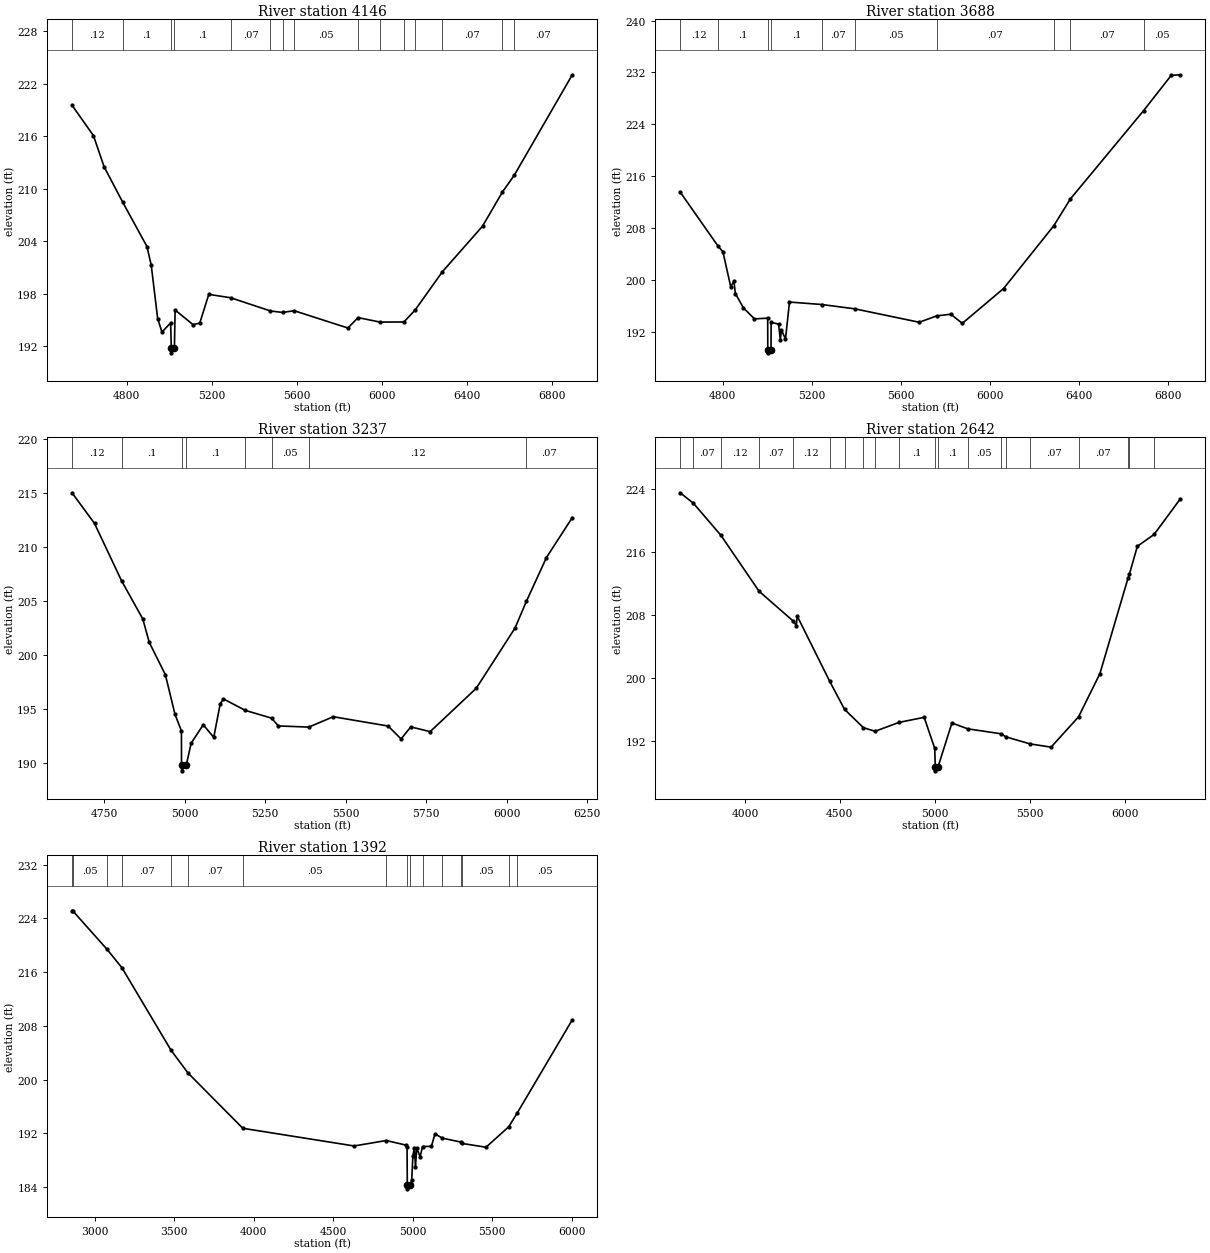
Type RM Length L Ch R = 1 ,4146    ,458,458,458
BEGIN DESCRIPTION:
Stream0498 5.0
END DESCRIPTION:
XS GIS Cut Line= 3
        2518775.     13615274.96        2518825.       13615725.
      2518224.99     13617525.02
#Sta/Elev= 30
  4543.1  219.55  4643.8  216.07  4694.1   212.5  4782.1  208.42  4895.3  203.38
  4915.4  201.24  4945.6  195.13  4965.7   193.6  5006.5  194.64  5009.7  191.72
  5010.2  191.22  5024.2  191.72  5027.5  196.12  5111.9  194.44  5143.5  194.63
  5185.6  197.91  5288.6  197.52  5475.5  196.01  5532.7  195.84  5586.5  196.04
  5839.2  194.06  5887.1  195.25    5990  194.74  6102.2  194.75  6154.8  196.11
  6283.2   200.5  6471.6  205.71  6565.3  209.62  6621.1  211.55  6893.3  223.03
#Mann= 15 ,-1 , 0
  4543.1     .12       0  4782.1      .1       0  5009.7     .05       0
  5024.2      .1       0  5288.6     .07       0  5475.5     .12       0
  5532.7     .07       0  5586.5     .05       0  5887.1     .07       0
    5990     .12       0  6102.2     .07       0  6154.8     .12       0
  6283.2     .07       0  6565.3     .05       0  6621.1     .07       0
Bank Sta=5009.7,5024.2
XS Rating Curve= 0 ,0
Exp/Cntr=0.3,0.1

Type RM Length L Ch R = 1 ,3688    ,451,451,451
BEGIN DESCRIPTION:
Stream0498 4.0
END DESCRIPTION:
XS GIS Cut Line= 3
      2518274.99     13615624.98        2518525.       13615925.
      2518075.01     13617724.97
#Sta/Elev= 30
  4609.4  213.54    4780  205.17  4801.4  204.32  4836.6  198.92  4850.9  199.77
  4857.4  197.86  4893.8  195.64  4943.3  193.95  5002.5  194.06    5003  189.21
  5003.5  188.71  5017.5  189.21    5018  193.41  5051.5  193.14  5059.2  190.74
  5064.4  192.22  5082.4  190.85  5100.4  196.55  5245.3  196.17  5393.9   195.5
  5682.8  193.43  5760.9  194.41  5824.6  194.67  5876.1  193.26  6061.6  198.64
    6287  208.33  6361.1  212.45  6690.2   226.1  6814.1  231.54  6855.3  231.63
#Mann= 10 ,-1 , 0
  4609.4     .12       0    4780      .1       0    5003     .05       0
  5017.5      .1       0  5245.3     .07       0  5393.9     .05       0
  5760.9     .07       0    6287     .12       0  6361.1     .07       0
  6690.2     .05       0
Bank Sta=5003,5017.5
XS Rating Curve= 0 ,0
Exp/Cntr=0.3,0.1

Type RM Length L Ch R = 1 ,3237    ,595,595,595
BEGIN DESCRIPTION:
Stream0498 3.0
END DESCRIPTION:
XS GIS Cut Line= 3
        2518125.     13615724.96        2518125.       13616075.
        2518025.       13617275.
#Sta/Elev= 30
    4650     215    4720  212.16  4803.8  206.86    4870  203.31    4890  201.15
    4940  198.16    4970  194.48    4990  192.95  4990.2  189.75  4990.7  189.25
  5004.8  189.75  5020.1   191.8  5057.7  193.52  5090.4  192.35  5110.4  195.45
  5120.5  195.91  5188.3  194.85    5270  194.13    5291  193.41  5385.6   193.3
  5461.6  194.26  5632.2   193.4  5672.4   192.2  5702.5  193.32  5762.7  192.88
  5905.7  196.89  6026.1  202.46  6061.8  204.96  6123.9     209  6204.2   212.7
#Mann= 8 ,-1 , 0
    4650     .12       0  4803.8      .1       0  4990.2     .05       0
  5004.8      .1       0  5188.3     .12       0    5270     .05       0
  5385.6     .12       0  6061.8     .07       0
Bank Sta=4990.2,5004.8
XS Rating Curve= 0 ,0
Exp/Cntr=0.3,0.1

Type RM Length L Ch R = 1 ,2642    ,1250,1250,1250
BEGIN DESCRIPTION:
XS6942
END DESCRIPTION:
XS GIS Cut Line= 2
      2517457.13     13614993.02      2517770.56     13617610.21
#Sta/Elev= 30
  3658.6  223.55  3728.3  222.23  3873.3  218.15  4074.8  211.03  4253.8  207.26
  4270.7  206.68  4275.7  207.87  4447.2  199.57  4524.8  196.03  4624.3  193.69
    4686  193.24  4812.6  194.37  4944.5  195.01  5000.1  191.06  5002.9  188.71
  5003.4  188.21  5017.5  188.71  5090.7  194.29  5173.9  193.55  5349.3  192.92
  5375.8  192.52  5503.4  191.63  5613.2  191.22    5758  195.08  5870.3  200.56
  6018.2  212.67  6025.7   213.2  6067.7  216.75  6156.1  218.26  6294.5  222.79
#Mann= 20 ,-1 , 0
  3658.6     .12       0  3728.3     .07       0  3873.3     .12       0
  4074.8     .07       0  4253.8     .12       0  4447.2     .07       0
  4524.8     .12       0  4624.3     .07       0    4686     .12       0
  4812.6      .1       0  5002.9     .05       0  5017.5      .1       0
  5173.9     .05       0  5349.3     .07       0  5375.8     .05       0
  5503.4     .07       0    5758     .07       0  6018.2     .12       0
  6025.7     .07       0  6156.1     .05       0
Bank Sta=5002.9,5017.5
XS Rating Curve= 0 ,0
Exp/Cntr=0.3,0.1

Type RM Length L Ch R = 1 ,1392    ,435,435,435
BEGIN DESCRIPTION:
Stream0498 2.0
END DESCRIPTION:
XS GIS Cut Line= 3
      2517222.02      13614742.2        2516975.       13616875.
      2517575.03     13617675.03
#Sta/Elev= 30
  2857.5  225.14  2862.7  225.12  3077.3  219.42  3171.7  216.66  3480.9  204.37
  3587.2     201  3932.1  192.77  4632.1  190.14  4834.1  190.95  4960.2  190.26
  4965.2  189.92  4966.9  184.26  4967.4  183.76  4981.8  184.26  4994.5  185.02
    5002  188.67  5011.8   189.9  5018.1  187.01  5026.4  189.83  5047.3  188.53
  5062.4  190.06  5118.1  190.08    5141  191.93  5188.2   191.3  5304.1  190.72
    5314  190.51  5461.8  189.95  5605.1     193  5658.4  195.05  6004.6  208.91
#Mann= 16 ,-1 , 0
  2857.5     .07       0  2862.7     .05       0  3077.3     .12       0
  3171.7     .07       0  3480.9     .12       0  3587.2     .07       0
  3932.1     .05       0  4834.1      .1       0  4966.9     .05       0
  4981.8      .1       0  5062.4     .12       0  5188.2     .05       0
  5304.1     .12       0    5314     .05       0  5605.1     .12       0
  5658.4     .05       0
Bank Sta=4966.9,4981.8
XS Rating Curve= 0 ,0
Exp/Cntr=0.3,0.1