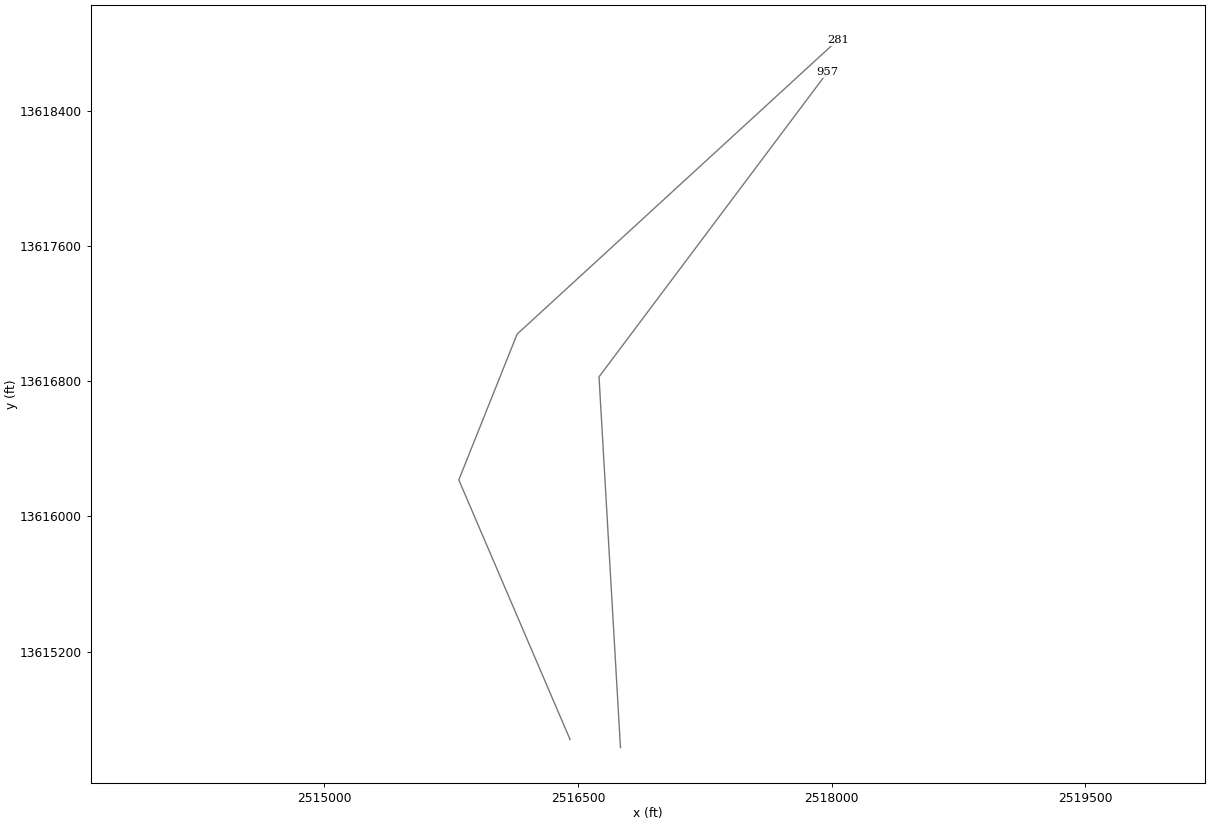
HEC-RAS study Stream0498.prj: Stream0498 Base Level Engineering

--- Stream0498.g01 (geometry) --- (continued)

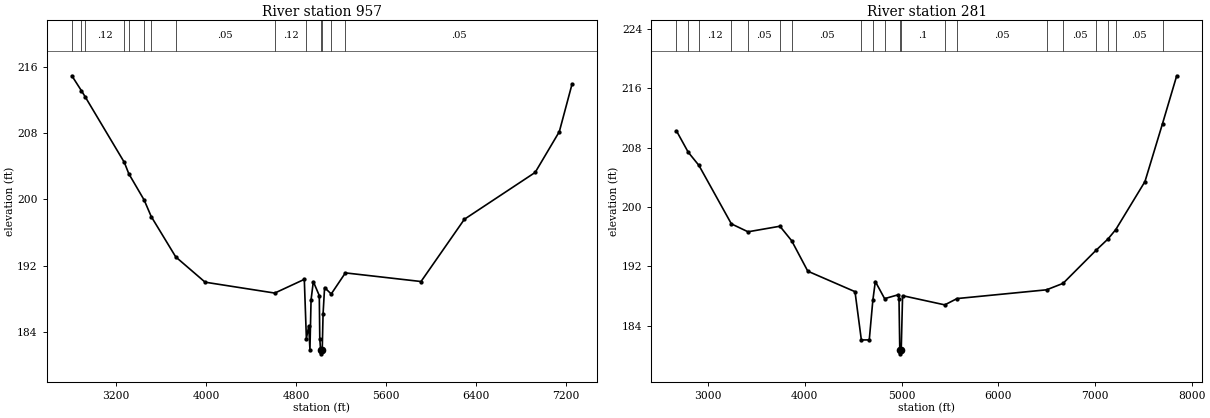
Type RM Length L Ch R = 1 ,957     ,676,676,676
BEGIN DESCRIPTION:
Stream0498 1.0
END DESCRIPTION:
XS GIS Cut Line= 3
      2516751.82     13614632.47        2516625.       13616825.
        2517975.       13618625.
#Sta/Elev= 30
  2808.7  214.89  2893.7  213.09  2926.1  212.38  3275.3  204.45  3314.8  203.09
  3451.8  199.91  3513.9  197.94  3732.2  193.07  3993.2  190.03    4612  188.72
  4874.7  190.37  4893.3  183.22    4914  184.77  4924.8  181.91  4934.8   187.9
  4954.8   190.1    5008  188.41  5012.2  183.23  5019.3   181.9  5019.8   181.4
  5034.2   181.9  5041.4  186.18  5054.9  189.38    5114  188.61  5239.8  191.15
  5912.2  190.11  6297.6  197.61  6926.8  203.25  7141.4  208.16  7254.9  213.91
#Mann= 14 ,-1 , 0
  2808.7     .07       0  2893.7     .05       0  2926.1     .12       0
  3275.3     .07       0  3314.8     .12       0  3451.8     .07       0
  3513.9     .12       0  3732.2     .05       0    4612     .12       0
  4893.3      .1       0  5019.3     .05       0  5034.2      .1       0
    5114     .12       0  5239.8     .05       0
Bank Sta=5019.3,5034.2
XS Rating Curve= 0 ,0
Exp/Cntr=0.3,0.1

Type RM Length L Ch R = 1 ,281     ,0,0,0
BEGIN DESCRIPTION:
XS6941
END DESCRIPTION:
XS GIS Cut Line= 4
      2516454.02     13614679.52      2515795.73     13616215.54
      2516140.54     13617077.59      2518037.03     13618817.35
#Sta/Elev= 30
  2672.3  210.24  2793.6  207.37  2904.3  205.59  3239.9  197.71  3412.1  196.64
  3741.9  197.39  3863.3  195.44  4030.4  191.33  4518.5  188.57  4584.2  182.06
    4666  182.07  4702.9  187.39  4728.6  189.94  4824.8  187.63  4967.5  188.16
  4973.6  187.61  4981.6  180.69  4982.1  180.19  4996.5  180.69  5010.6  188.03
    5447  186.79  5573.8  187.64  6499.6  188.82  6670.3  189.69  7010.6  194.14
  7135.5  195.68  7215.4  196.94  7517.1  203.41  7698.7  211.22  7845.5  217.67
#Mann= 20 ,-1 , 0
  2672.3     .12       0  2793.6     .07       0  2904.3     .12       0
  3239.9     .07       0  3412.1     .05       0  3741.9     .07       0
  3863.3     .05       0  4584.2      .1       0  4702.9     .05       0
  4824.8      .1       0  4981.6     .05       0  4996.5      .1       0
    5447    .035       0  5573.8     .05       0  6499.6     .05       0
  6670.3     .05       0  7010.6     .07       0  7135.5     .07       0
  7215.4     .05       0  7698.7     .05       0
Bank Sta=4981.6,4996.5
XS Rating Curve= 0 ,0
Exp/Cntr=0.3,0.1

Chan Stop Cuts=-1
Use User Specified Reach Order=0
Composite Channel Slope=5