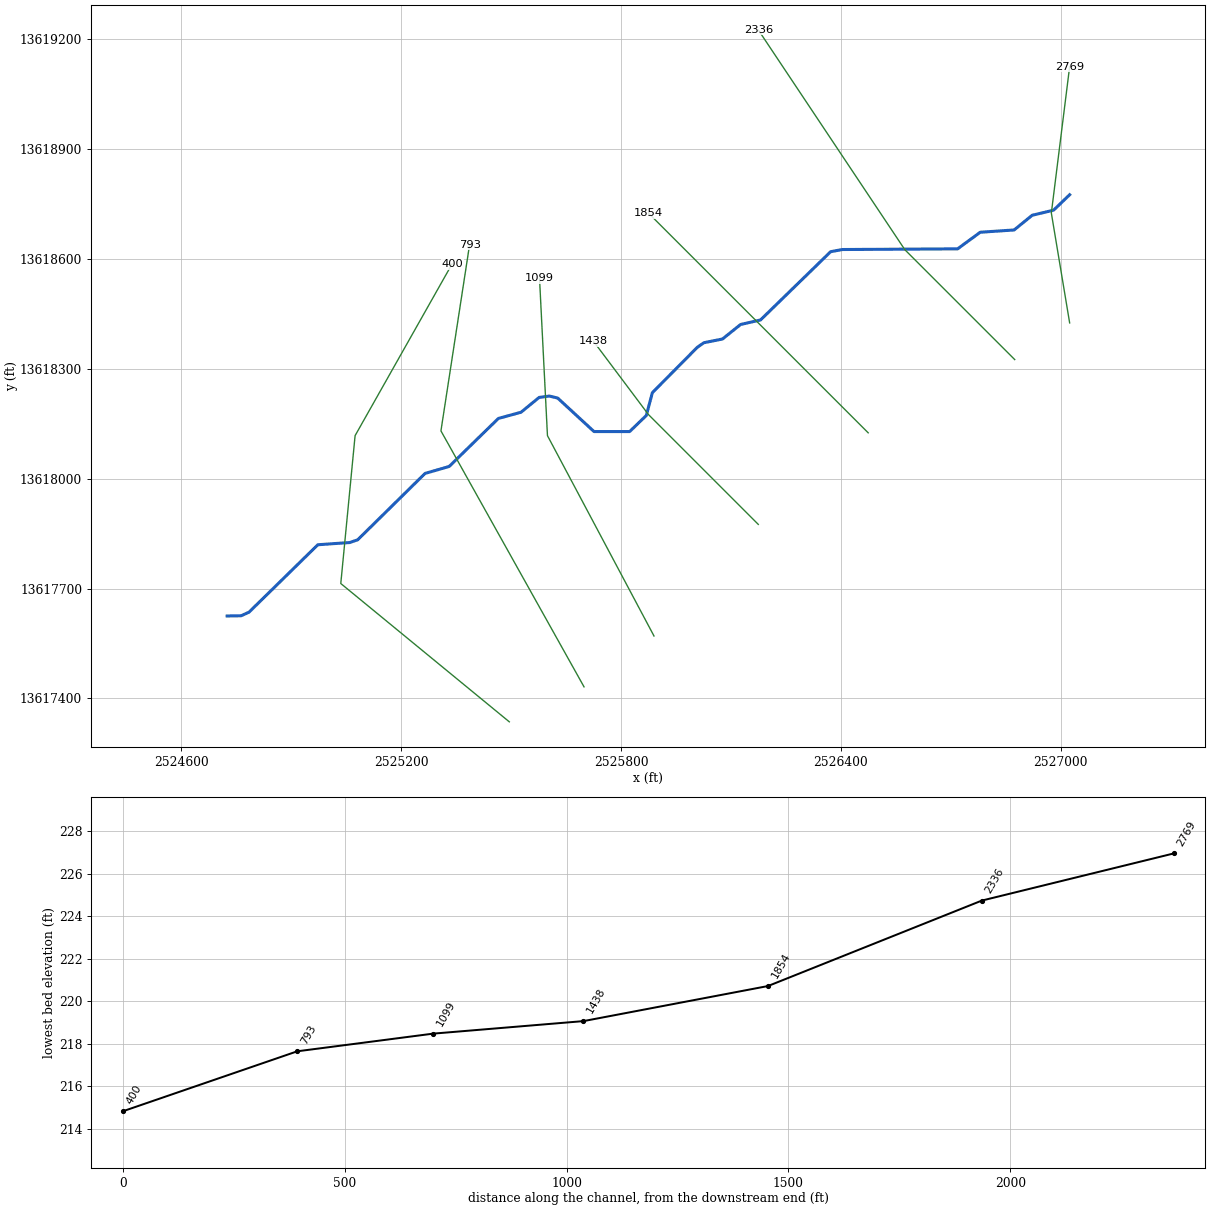
--- Stream0499.prj (project) ---

Proj Title=Stream0499 Base Level Engineering
Current Plan=p01
Default Exp/Contr=0.3,0.1
English Units
Geom File=g01
Flow File=f01
Plan File=p01
BEGIN DESCRIPTION:
Stream0499
END DESCRIPTION:

--- Stream0499.p01 (plan) ---

Plan Title=Multiple Run
Short Identifier=Multiple
Geom File=g01
Flow File=f01
Subcritical Flow
K Sum by GR= 0
Std Step Tol= 0.01
Critical Tol= 0.01
Num of Std Step Trials= 20
Max Error Tol= 0.3
Flow Tol Ratio= 0.001
Split Flow NTrial= 30
Split Flow Tol= 0.02
Split Flow Ratio= 0.02
Log Output Level= 0
Friction Slope Method= 1
Unsteady Friction Slope Method= 2
Unsteady Bridges Friction Slope Method= 1
Parabolic Critical Depth
Global Vel Dist=  1 , 1 , 1
Global Log Level= 0
CheckData=True
Encroach Param= -1, 0, 0, 0
BEGIN DESCRIPTION:
Multiple Run
END DESCRIPTION:

--- Stream0499.f01 (steady flow) ---

Flow Title=Multiple
Number of Profiles=7
Profile Names=10-year,25-year,50-year,1pct_min,100-year,1pct_plu,500-year
River Rch & RM= Stream0499,Reach-1,2769
     773    1256    1696    1110    2214    4418    3735
Boundary for River Rch & Prof#=Stream0499,Reach-1,1
Up Type=0
Dn Type=3
Dn Slope=0.005
Boundary for River Rch & Prof#=Stream0499,Reach-1,2
Up Type=0
Dn Type=3
Dn Slope=0.005
Boundary for River Rch & Prof#=Stream0499,Reach-1,3
Up Type=0
Dn Type=3
Dn Slope=0.005
Boundary for River Rch & Prof#=Stream0499,Reach-1,4
Up Type=0
Dn Type=3
Dn Slope=0.005
Boundary for River Rch & Prof#=Stream0499,Reach-1,5
Up Type=0
Dn Type=3
Dn Slope=0.005
Boundary for River Rch & Prof#=Stream0499,Reach-1,6
Up Type=0
Dn Type=3
Dn Slope=0.005
Boundary for River Rch & Prof#=Stream0499,Reach-1,7
Up Type=0
Dn Type=3
Dn Slope=0.005

--- Stream0499.g01 (geometry) ---

Geom Title=Existing Conditions

River Reach=Stream0499,Reach-1
Reach XY= 30
      2527025.00     13618775.00      2526981.15     13618732.91
      2526922.78     13618718.97      2526873.42     13618678.82
      2526780.98     13618672.64      2526719.06     13618627.26
      2526404.82     13618625.43      2526372.55     13618619.54
      2526181.06     13618433.14      2526126.74     13618420.81
      2526077.19     13618381.10      2526026.63     13618371.05
      2526008.32     13618358.36      2525885.79     13618234.66
      2525869.26     13618172.42      2525823.72     13618128.37
      2525726.50     13618128.47      2525627.29     13618219.90
      2525604.87     13618225.40      2525576.73     13618221.69
      2525527.19     13618181.18      2525465.32     13618164.24
      2525331.05     13618033.16      2525265.32     13618014.22
      2525081.17     13617832.86      2525059.78     13617825.53
      2524972.57     13617819.48      2524784.79     13617635.52
      2524763.16     13617625.59      2524725.00     13617625.00

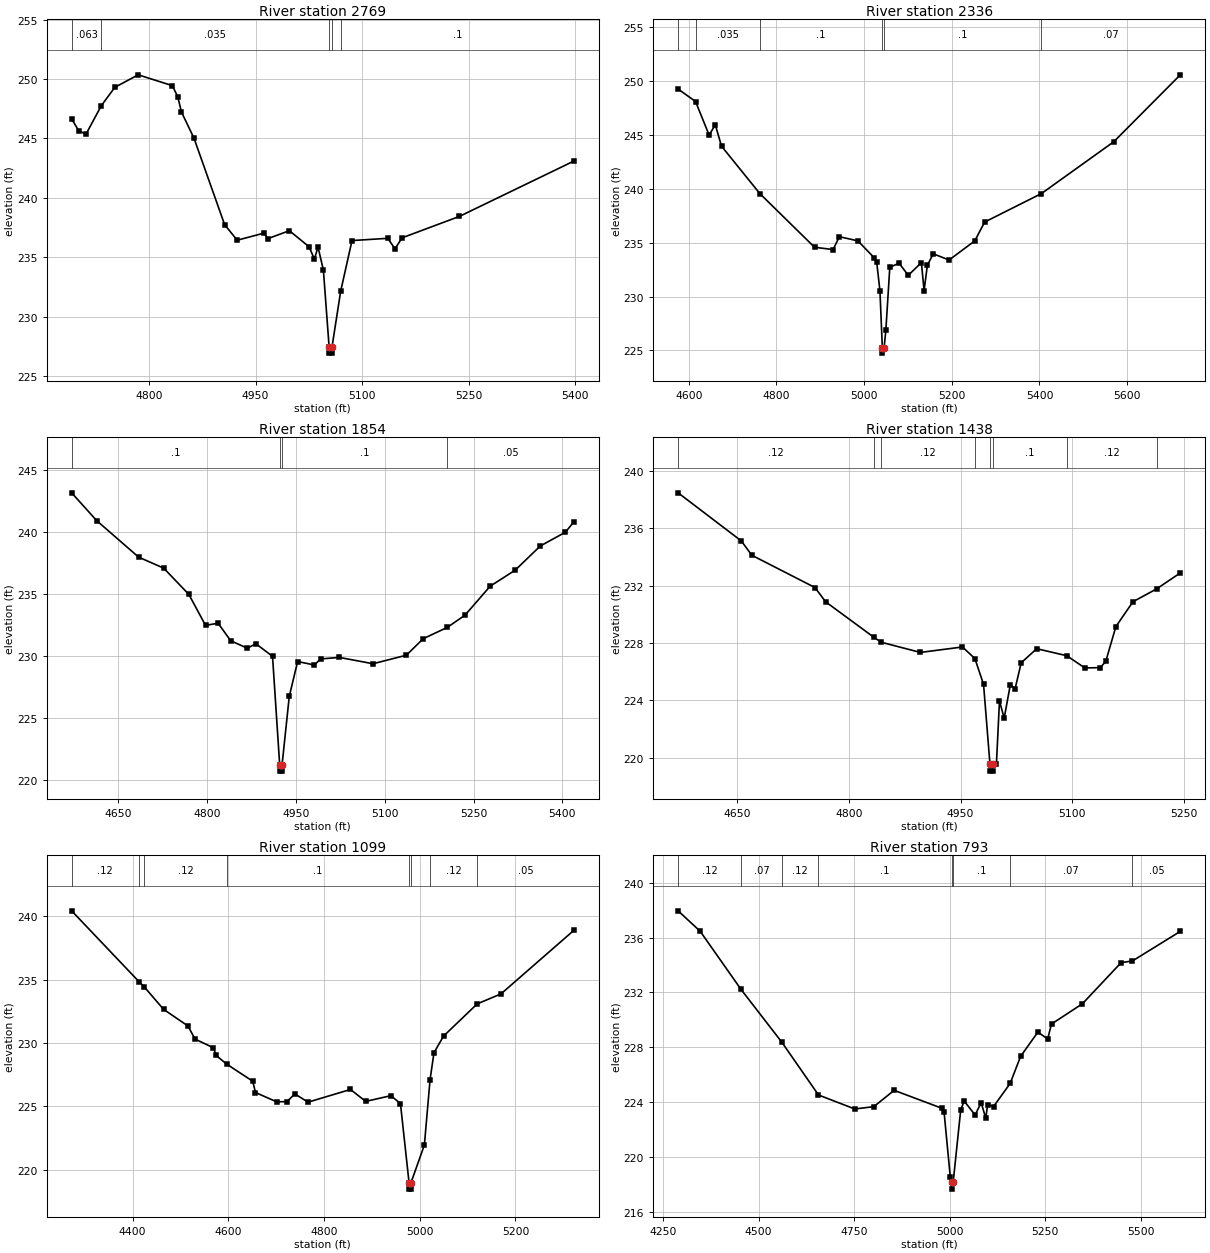
Type RM Length L Ch R = 1,2769,433,433,433
BEGIN DESCRIPTION:
Stream0499 5.0
END DESCRIPTION:
XS GIS Cut Line= 3
      2527024.99     13618425.05      2526975.00     13618725.00
      2527025.00     13619125.00
#Sta/Elev= 30
  4691.0  246.64  4701.1  245.64  4711.2  245.36  4732.8  247.76  4751.8  249.30
  4784.7  250.35  4832.9  249.44  4840.5  248.49  4845.6  247.23  4863.3  245.02
  4906.4  237.76  4924.1  236.45  4962.1  237.05  4967.2  236.58  4997.6  237.25
  5025.3  235.90  5032.9  234.86  5037.9  235.89  5045.5  233.94  5053.6  227.46
  5053.8  226.96  5057.3  226.96  5057.6  227.46  5069.9  232.18  5085.8  236.42
  5136.2  236.61  5146.3  235.73  5156.3  236.65  5237.0  238.45  5398.2  243.10
#Mann=5,-1,0
  4691.0   0.063       0  4732.8   0.035       0  5053.6   0.035       0
  5057.6   0.035       0  5069.9     0.1       0
Bank Sta=5053.6,5057.6
Exp/Cntr=0.3,0.1

Type RM Length L Ch R = 1,2336,482,482,482
BEGIN DESCRIPTION:
Stream0499 4.0
END DESCRIPTION:
XS GIS Cut Line= 3
      2526874.99     13618325.01      2526575.00     13618625.00
      2526174.97     13619225.04
#Sta/Elev= 30
  4575.8  249.28  4615.6  248.12  4646.5  245.00  4660.6  245.96  4674.8  243.97
  4762.3  239.56  4886.9  234.58  4929.3  234.36  4943.5  235.56  4985.9  235.17
  5022.6  233.62  5028.6  233.25  5036.1  230.54  5041.6  225.24  5041.9  224.74
  5045.6  225.24  5049.6  226.87  5058.6  232.71  5079.7  233.10  5100.7  231.97
  5130.7  233.15  5136.8  230.55  5144.3  232.91  5157.8  233.97  5193.8  233.39
  5252.4  235.17  5275.0  236.92  5404.6  239.57  5569.4  244.38  5721.2  250.60
#Mann=6,-1,0
  4575.8   0.063       0  4615.6   0.035       0  4762.3     0.1       0
  5041.6    0.05       0  5045.6     0.1       0  5404.6    0.07       0
Bank Sta=5041.6,5045.6
Exp/Cntr=0.3,0.1

Type RM Length L Ch R = 1,1854,416,416,416
BEGIN DESCRIPTION:
Stream0499 3.0
END DESCRIPTION:
XS GIS Cut Line= 3
      2526474.97     13618125.03      2526175.00     13618425.00
      2525874.99     13618725.01
#Sta/Elev= 30
  4571.0  243.19  4613.4  240.94  4684.1  238.00  4726.5  237.11  4769.0  234.99
  4797.2  232.49  4818.5  232.66  4839.7  231.25  4867.9  230.64  4882.1  231.01
  4910.4  229.99  4922.5  221.22  4922.8  220.72  4926.3  220.72  4926.5  221.22
  4938.7  226.76  4952.8  229.57  4981.1  229.29  4991.7  229.78  5023.5  229.90
  5080.1  229.39  5136.6  230.08  5164.9  231.41  5205.5  232.32  5235.6  233.31
  5278.1  235.65  5320.5  236.95  5362.9  238.90  5405.3  240.01  5419.5  240.85
#Mann=4,-1,0
  4571.0     0.1       0  4922.5    0.05       0  4926.5     0.1       0
  5205.5    0.05       0
Bank Sta=4922.5,4926.5
Exp/Cntr=0.3,0.1

Type RM Length L Ch R = 1,1438,339,339,339
BEGIN DESCRIPTION:
Stream0499 2.0
END DESCRIPTION:
XS GIS Cut Line= 3
      2526174.99     13617875.01      2525875.00     13618175.00
      2525724.97     13618375.04
#Sta/Elev= 30
  4570.7  238.46  4655.5  235.11  4669.7  234.11  4754.5  231.86  4768.7  230.87
  4833.7  228.39  4843.4  228.05  4896.0  227.34  4952.5  227.72  4969.2  226.91
  4980.8  225.12  4989.4  219.57  4989.7  219.07  4993.2  219.07  4993.4  219.57
  4998.1  219.57  5002.2  223.96  5008.5  222.76  5016.8  225.10  5023.1  224.80
  5031.4  226.62  5052.2  227.60  5092.6  227.11  5116.8  226.26  5137.7  226.28
  5145.0  226.73  5158.5  229.14  5181.4  230.87  5213.3  231.77  5245.0  232.88
#Mann=8,-1,0
  4570.7    0.12       0  4833.7     0.1       0  4843.4    0.12       0
  4969.2     0.1       0  4989.4    0.05       0  4993.4     0.1       0
  5092.6    0.12       0  5213.3    0.05       0
Bank Sta=4989.4,4993.4
Exp/Cntr=0.3,0.1

Type RM Length L Ch R = 1,1099,306,306,306
BEGIN DESCRIPTION:
E21114
END DESCRIPTION:
XS GIS Cut Line= 3
      2525890.19     13617570.41      2525599.39     13618117.29
      2525577.69     13618546.96
#Sta/Elev= 30
  4272.5  240.43  4413.3  234.84  4423.8  234.45  4464.6  232.66  4515.5  231.35
  4530.5  230.31  4568.8  229.63  4574.5  229.02  4596.9  228.33  4651.0  226.99
  4656.7  226.10  4700.7  225.37  4722.6  225.38  4738.9  225.99  4766.6  225.34
  4855.3  226.34  4887.1  225.40  4939.7  225.85  4959.7  225.23  4977.7  218.98
  4978.0  218.48  4981.5  218.48  4981.7  218.98  5009.7  221.96  5021.6  227.12
  5029.8  229.24  5049.8  230.55  5120.1  233.09  5169.9  233.88  5322.1  238.89
#Mann=8,-1,0
  4272.5    0.12       0  4413.3    0.07       0  4423.8    0.12       0
  4596.9     0.1       0  4977.7    0.05       0  4981.7     0.1       0
  5021.6    0.12       0  5120.1    0.05       0
Bank Sta=4977.7,4981.7
Exp/Cntr=0.3,0.1

Type RM Length L Ch R = 1,793,393,393,393
BEGIN DESCRIPTION:
E21113
END DESCRIPTION:
XS GIS Cut Line= 3
      2525699.24     13617431.49      2525308.59     13618130.31
      2525386.72     13618638.14
#Sta/Elev= 30
  4289.2  237.96  4346.9  236.47  4454.0  232.22  4560.7  228.37  4656.6  224.52
  4751.5  223.50  4801.5  223.67  4854.6  224.86  4979.7  223.55  4985.4  223.25
  5001.4  218.57  5005.1  218.15  5005.3  217.65  5009.1  218.15  5028.8  223.42
  5037.9  224.08  5066.5  223.06  5082.4  223.96  5094.4  222.82  5099.3  223.82
  5114.8  223.68  5158.2  225.36  5185.6  227.34  5230.8  229.11  5256.4  228.61
  5266.5  229.70  5347.5  231.18  5448.7  234.18  5478.2  234.30  5603.6  236.46
#Mann=8,-1,0
  4289.2    0.12       0  4454.0    0.07       0  4560.7    0.12       0
  4656.6     0.1       0  5005.1    0.05       0  5009.1     0.1       0
  5158.2    0.07       0  5478.2    0.05       0
Bank Sta=5005.1,5009.1
Exp/Cntr=0.3,0.1

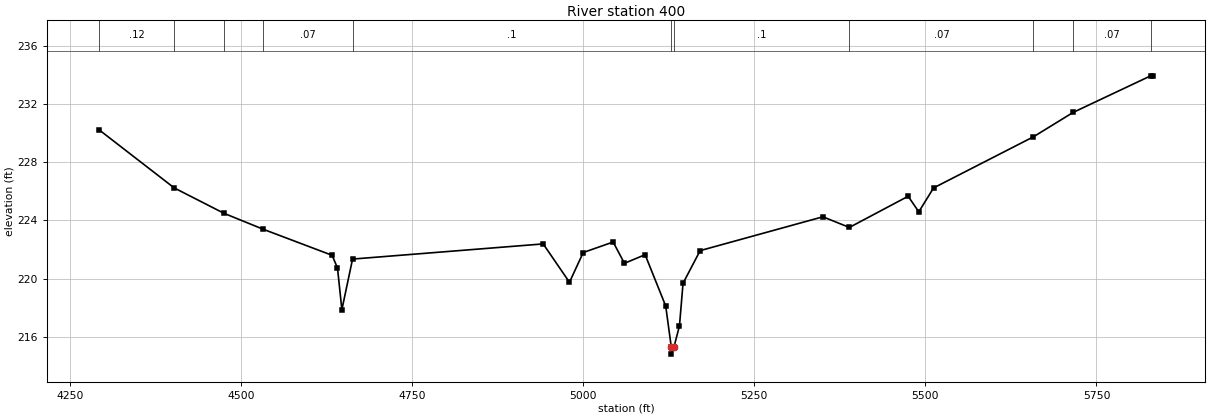
Type RM Length L Ch R = 1,400,0,0,0
BEGIN DESCRIPTION:
E21112
END DESCRIPTION:
XS GIS Cut Line= 4
      2525495.22     13617336.04      2525035.16     13617713.64
      2525074.22     13618117.29      2525338.99     13618586.06
#Sta/Elev= 30
  4293.1  230.21  4402.7  226.23  4475.8  224.48  4533.0  223.39  4633.3  221.61
  4641.2  220.74  4647.6  217.88  4663.2  221.35  4941.7  222.39  4980.1  219.76
  5000.2  221.80  5043.9  222.52  5060.4  221.06  5090.6  221.65  5120.7  218.13
  5128.8  215.33  5129.0  214.83  5132.8  215.33  5140.8  216.77  5146.0  219.69
  5171.0  221.93  5350.3  224.25  5389.0  223.52  5474.9  225.66  5490.4  224.59
  5512.0  226.23  5658.0  229.74  5715.9  231.41  5829.2  233.92  5832.2  233.92
#Mann=11,-1,0
  4293.1    0.12       0  4402.7    0.07       0  4475.8    0.12       0
  4533.0    0.07       0  4663.2     0.1       0  5128.8    0.05       0
  5132.8     0.1       0  5389.0    0.07       0  5658.0    0.12       0
  5715.9    0.07       0  5829.2    0.05       0
Bank Sta=5128.8,5132.8
Exp/Cntr=0.3,0.1

Chan Stop Cuts=-1