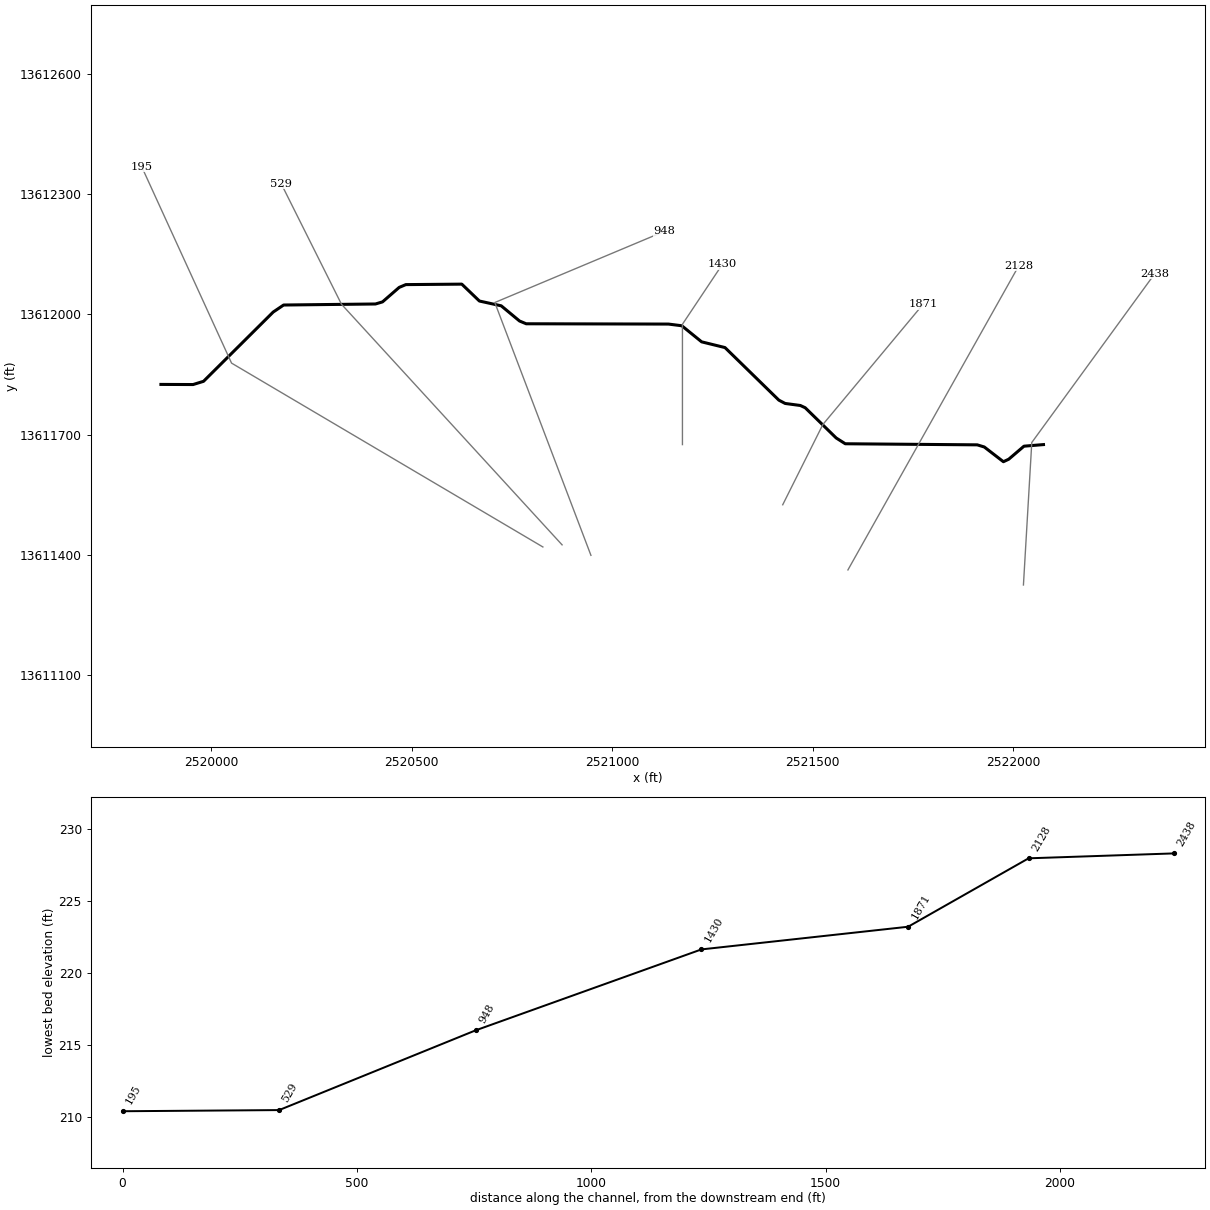
--- Stream0504.prj (project) ---

Proj Title=Stream0504 Base Level Engineering
Current Plan=p01
Default Exp/Contr=0.3,0.1
English Units
Geom File=g01
Flow File=f01
Plan File=p01
BEGIN DESCRIPTION:
Stream0504
END DESCRIPTION:

--- Stream0504.p01 (plan) ---

Plan Title=Multiple Run
Short Identifier=Multiple
Geom File=g01
Flow File=f01
Subcritical Flow
K Sum by GR= 0
Std Step Tol= 0.01
Critical Tol= 0.01
Num of Std Step Trials= 20
Max Error Tol= 0.3
Flow Tol Ratio= 0.001
Split Flow NTrial= 30
Split Flow Tol= 0.02
Split Flow Ratio= 0.02
Log Output Level= 0
Friction Slope Method= 1
Unsteady Friction Slope Method= 2
Unsteady Bridges Friction Slope Method= 1
Parabolic Critical Depth
Global Vel Dist=  1 , 1 , 1
Global Log Level= 0
CheckData=True
Encroach Param= -1, 0, 0, 0
BEGIN DESCRIPTION:
Multiple Run
END DESCRIPTION:

--- Stream0504.f01 (steady flow) ---

Flow Title=Multiple
Number of Profiles=7
Profile Names=10-year,25-year,50-year,1pct_min,100-year,1pct_plu,500-year
River Rch & RM= Stream0504,Reach-1,2438
     361     564     741     474     946    1887    1520
River Rch & RM= Stream0504,Reach-1,529
     553     887    1187     771    1538    3068    2554
Boundary for River Rch & Prof#=Stream0504,Reach-1,1
Up Type=0
Dn Type=3
Dn Slope=0.005
Boundary for River Rch & Prof#=Stream0504,Reach-1,2
Up Type=0
Dn Type=3
Dn Slope=0.005
Boundary for River Rch & Prof#=Stream0504,Reach-1,3
Up Type=0
Dn Type=3
Dn Slope=0.005
Boundary for River Rch & Prof#=Stream0504,Reach-1,4
Up Type=0
Dn Type=3
Dn Slope=0.005
Boundary for River Rch & Prof#=Stream0504,Reach-1,5
Up Type=0
Dn Type=3
Dn Slope=0.005
Boundary for River Rch & Prof#=Stream0504,Reach-1,6
Up Type=0
Dn Type=3
Dn Slope=0.005
Boundary for River Rch & Prof#=Stream0504,Reach-1,7
Up Type=0
Dn Type=3
Dn Slope=0.005

--- Stream0504.g01 (geometry) ---

Geom Title=Existing Conditions

River Reach=Stream0504,Reach-1
Reach XY= 30
      2522075.00     13611675.00      2522026.36     13611671.00
      2521988.28     13611638.48      2521975.04     13611632.31
      2521927.45     13611669.00      2521909.84     13611674.35
      2521580.86     13611677.06      2521558.25     13611691.46
      2521481.04     13611766.82      2521468.95     13611772.46
      2521431.05     13611777.53      2521415.32     13611785.78
      2521281.06     13611916.86      2521222.83     13611931.14
      2521173.45     13611971.25      2521140.18     13611975.44
      2520785.49     13611976.19      2520768.92     13611983.08
      2520723.31     13612020.92      2520668.85     13612032.91
      2520625.00     13612075.00      2520485.48     13612073.83
      2520468.94     13612066.87      2520427.34     13612030.74
      2520409.78     13612025.52      2520180.85     13612022.94
      2520154.84     13612005.40      2519981.22     13611832.74
      2519955.14     13611824.67      2519875.00     13611825.00

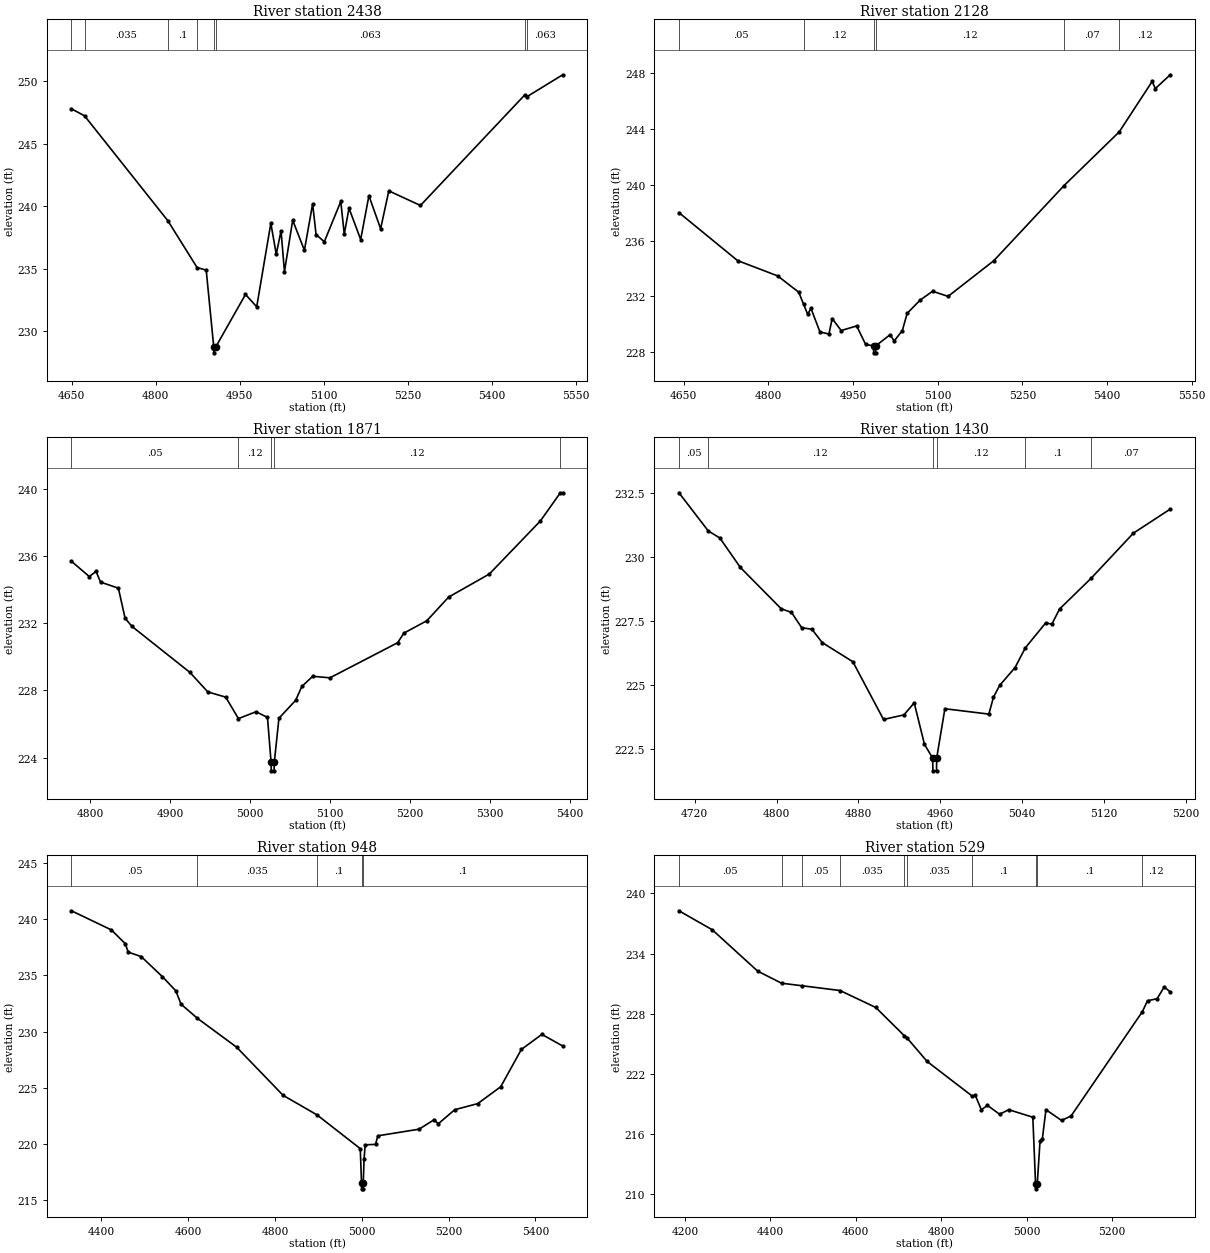
Type RM Length L Ch R = 1,2438,310,310,310
BEGIN DESCRIPTION:
Stream0504 5.0
END DESCRIPTION:
XS GIS Cut Line= 3
      2522025.00     13611324.96      2522045.83     13611680.21
      2522352.37     13612101.04
#Sta/Elev= 30
  4649.5  247.80  4672.9  247.24  4821.6  238.85  4873.7  235.11  4890.0  234.90
  4903.4  228.79  4903.6  228.29  4907.4  228.79  4960.1  232.96  4980.1  231.97
  5005.3  238.65  5015.0  236.17  5023.5  238.05  5029.6  234.78  5044.3  238.89
  5065.2  236.49  5079.9  240.20  5086.0  237.75  5100.7  237.17  5130.1  240.39
  5136.3  237.79  5144.8  239.85  5165.6  237.35  5180.3  240.85  5201.2  238.21
  5215.8  241.24  5272.2  240.07  5458.0  248.89  5462.0  248.76  5526.0  250.52
#Mann=8,-1,0
  4649.5    0.07       0  4672.9   0.035       0  4821.6     0.1       0
  4873.7   0.063       0  4903.4    0.05       0  4907.4   0.063       0
  5458.0    0.07       0  5462.0   0.063       0
Bank Sta=4903.4,4907.4
Exp/Cntr=0.3,0.1

Type RM Length L Ch R = 1,2128,257,257,257
BEGIN DESCRIPTION:
XS6951
END DESCRIPTION:
XS GIS Cut Line= 2
      2521587.51     13611362.52      2522013.74     13612121.41
#Sta/Elev= 30
  4641.6  238.01  4745.4  234.57  4816.5  233.47  4853.8  232.30  4862.3  231.45
  4869.7  230.71  4875.4  231.15  4891.4  229.45  4907.3  229.30  4913.1  230.41
  4929.0  229.55  4956.4  229.88  4972.4  228.55  4986.3  228.45  4986.6  227.95
  4990.1  227.95  4990.3  228.45  5015.7  229.25  5022.9  228.80  5037.4  229.55
  5045.9  230.78  5068.8  231.73  5091.0  232.37  5118.4  232.00  5199.4  234.56
  5323.9  239.95  5421.8  243.81  5480.0  247.42  5485.7  246.91  5512.0  247.90
#Mann=6,-1,0
  4641.6    0.05       0  4862.3    0.12       0  4986.3    0.05       0
  4990.3    0.12       0  5323.9    0.07       0  5421.8    0.12       0
Bank Sta=4986.3,4990.3
Exp/Cntr=0.3,0.1

Type RM Length L Ch R = 1,1871,441,441,441
BEGIN DESCRIPTION:
Stream0504 4.0
END DESCRIPTION:
XS GIS Cut Line= 3
      2521424.99     13611524.98      2521525.00     13611725.00
      2521774.97     13612024.97
#Sta/Elev= 30
  4776.4  235.69  4798.8  234.78  4807.2  235.09  4812.8  234.45  4835.1  234.09
  4843.5  232.30  4851.9  231.82  4924.6  229.07  4946.9  227.91  4969.3  227.60
  4985.2  226.32  5007.2  226.73  5021.5  226.39  5026.0  223.71  5026.3  223.21
  5029.8  223.21  5030.0  223.71  5035.8  226.34  5056.7  227.41  5064.5  228.24
  5078.1  228.84  5099.6  228.75  5184.2  230.84  5192.0  231.41  5220.7  232.15
  5248.0  233.56  5298.8  234.93  5362.6  238.09  5387.6  239.77  5390.5  239.77
#Mann=5,-1,0
  4776.4    0.05       0  4985.2    0.12       0  5026.0    0.05       0
  5030.0    0.12       0  5387.6    0.07       0
Bank Sta=5026,5030
Exp/Cntr=0.3,0.1

Type RM Length L Ch R = 1,1430,482,482,482
BEGIN DESCRIPTION:
Stream0504 3.0
END DESCRIPTION:
XS GIS Cut Line= 3
      2521175.00     13611674.97      2521175.00     13611975.00
      2521275.00     13612125.00
#Sta/Elev= 30
  4704.5  232.52  4733.1  231.03  4744.5  230.75  4764.5  229.60  4804.5  227.98
  4814.5  227.84  4824.5  227.24  4834.5  227.18  4844.5  226.66  4874.5  225.91
  4904.5  223.65  4924.5  223.83  4934.5  224.30  4944.5  222.68  4952.5  222.14
  4952.8  221.64  4956.3  221.64  4956.5  222.14  4964.5  224.07  5007.5  223.86
  5012.0  224.52  5018.0  224.98  5033.1  225.68  5043.1  226.45  5063.1  227.43
  5069.1  227.38  5076.6  227.97  5107.6  229.18  5148.8  230.94  5184.8  231.88
#Mann=6,-1,0
  4704.5    0.05       0  4733.1    0.12       0  4952.5    0.05       0
  4956.5    0.12       0  5043.1     0.1       0  5107.6    0.07       0
Bank Sta=4952.5,4956.5
Exp/Cntr=0.3,0.1

Type RM Length L Ch R = 1,948,419,419,419
BEGIN DESCRIPTION:
Stream0504 2.0
END DESCRIPTION:
XS GIS Cut Line= 3
      2520946.89     13611398.93      2520707.29     13612029.17
      2521129.19     13612206.26
#Sta/Elev= 30
  4331.0  240.73  4423.1  239.03  4455.2  237.80  4461.7  237.06  4491.9  236.66
  4540.8  234.87  4571.5  233.62  4583.6  232.43  4621.2  231.18  4711.4  228.62
  4818.9  224.33  4896.8  222.60  4996.5  219.60  4999.4  216.53  4999.7  216.03
  5003.2  216.03  5003.4  216.53  5005.2  218.66  5007.8  219.94  5031.6  219.98
  5037.0  220.74  5132.0  221.33  5166.6  222.17  5176.3  221.81  5214.2  223.06
  5267.1  223.60  5320.1  225.10  5367.6  228.41  5414.9  229.75  5462.8  228.72
#Mann=5,-1,0
  4331.0    0.05       0  4621.2   0.035       0  4896.8     0.1       0
  4999.4    0.05       0  5003.4     0.1       0
Bank Sta=4999.4,5003.4
Exp/Cntr=0.3,0.1

Type RM Length L Ch R = 1,529,334,334,334
BEGIN DESCRIPTION:
Stream0504 1.0
END DESCRIPTION:
XS GIS Cut Line= 3
      2520874.98     13611425.03      2520325.00     13612025.00
      2520175.01     13612324.99
#Sta/Elev= 30
  4186.2  238.27  4264.2  236.37  4370.2  232.25  4426.1  231.04  4475.2  230.78
  4563.0  230.31  4646.5  228.62  4713.6  225.79  4719.3  225.60  4766.7  223.23
  4871.7  219.79  4879.6  219.84  4893.7  218.40  4907.9  218.84  4936.3  217.96
  4957.9  218.41  5014.1  217.66  5020.5  211.01  5020.7  210.51  5024.5  211.01
  5030.9  215.27  5036.4  215.51  5044.8  218.41  5081.2  217.34  5103.5  217.78
  5270.4  228.20  5282.4  229.29  5304.8  229.49  5321.5  230.67  5335.5  230.17
#Mann=10,-1,0
  4186.2    0.05       0  4426.1   0.035       0  4475.2    0.05       0
  4563.0   0.035       0  4713.6    0.05       0  4719.3   0.035       0
  4871.7     0.1       0  5020.5    0.05       0  5024.5     0.1       0
  5270.4    0.12       0
Bank Sta=5020.5,5024.5
Exp/Cntr=0.3,0.1

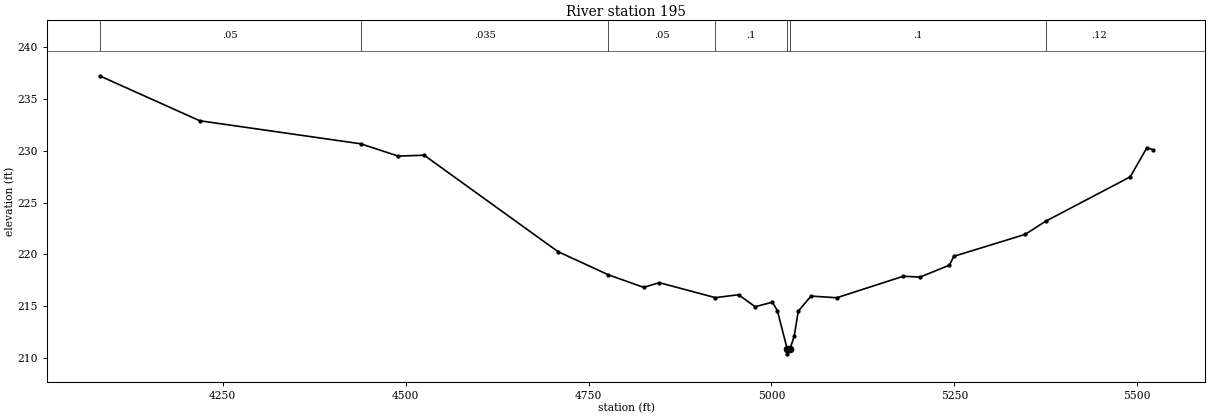
Type RM Length L Ch R = 1,195,0,0,0
BEGIN DESCRIPTION:
XS6950
END DESCRIPTION:
XS GIS Cut Line= 3
      2520827.10     13611419.78      2520051.04     13611878.13
      2519827.07     13612367.73
#Sta/Elev= 30
  4081.5  237.20  4218.5  232.87  4438.7  230.65  4489.7  229.47  4525.3  229.55
  4708.2  220.27  4777.0  218.04  4825.3  216.83  4846.7  217.28  4923.3  215.84
  4955.0  216.12  4977.6  214.97  5001.4  215.40  5008.1  214.58  5021.4  210.93
  5021.6  210.43  5025.4  210.93  5031.1  212.12  5036.6  214.54  5054.1  215.99
  5089.3  215.83  5180.2  217.90  5203.2  217.82  5243.3  218.97  5249.3  219.82
  5346.8  221.93  5374.7  223.19  5490.4  227.47  5513.4  230.29  5521.2  230.08
#Mann=7,-1,0
  4081.5    0.05       0  4438.7   0.035       0  4777.0    0.05       0
  4923.3     0.1       0  5021.4    0.05       0  5025.4     0.1       0
  5374.7    0.12       0
Bank Sta=5021.4,5025.4
Exp/Cntr=0.3,0.1

Chan Stop Cuts=-1