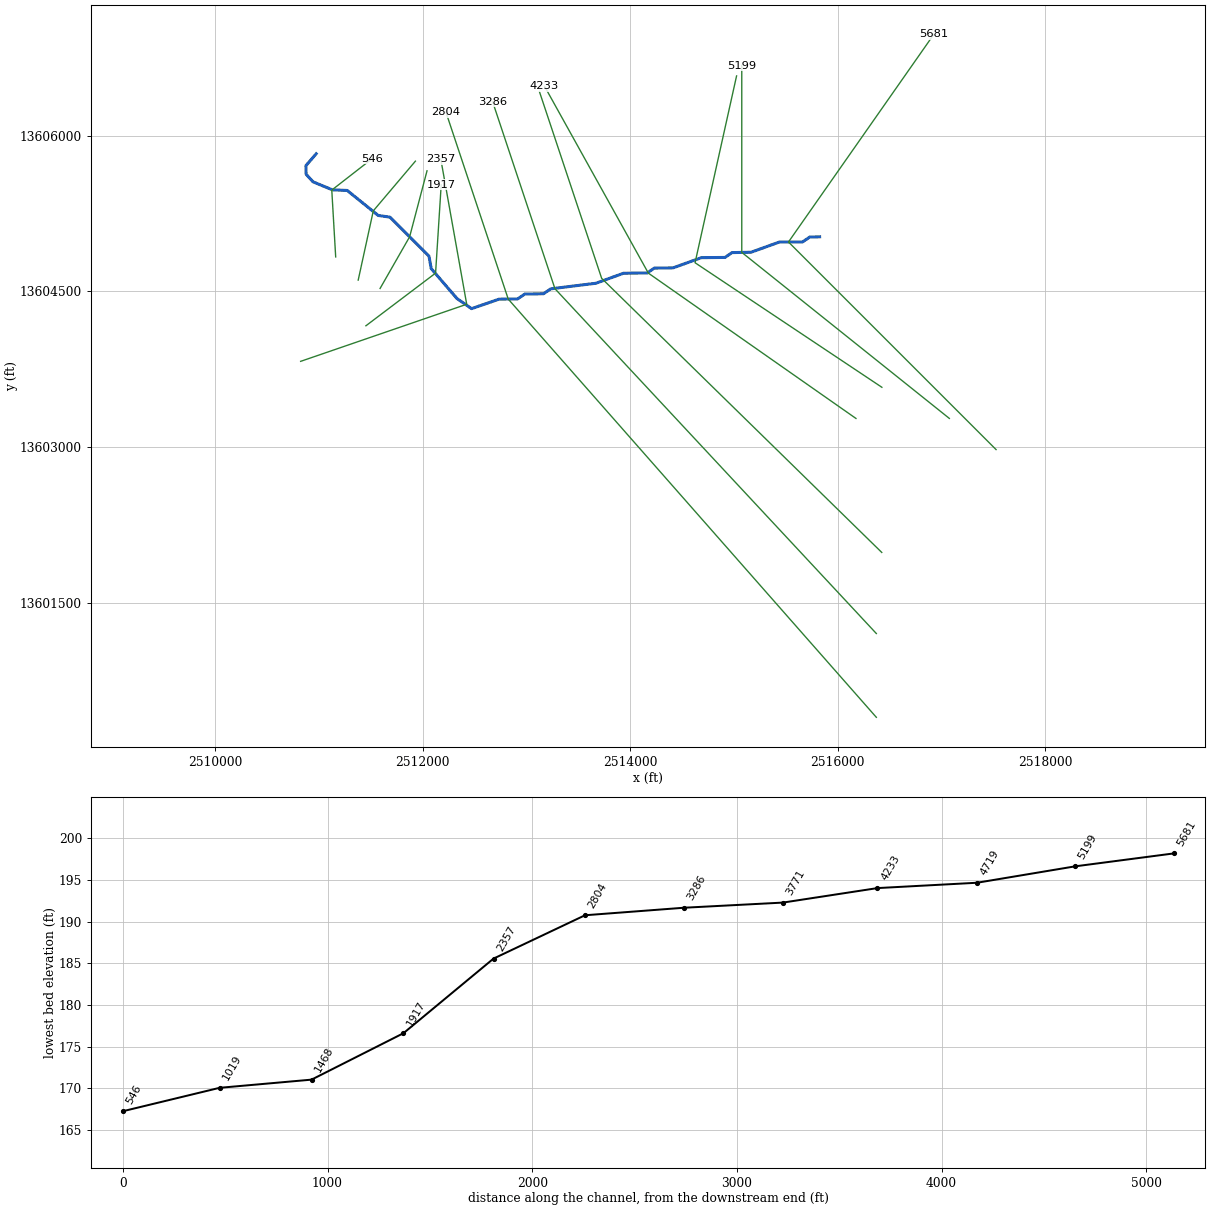
--- Stream0506.prj (project) ---

Proj Title=Stream0506 Base Level Engineering
Current Plan=p01
Default Exp/Contr=0.3,0.1
English Units
Geom File=g01
Flow File=f01
Plan File=p01
BEGIN DESCRIPTION:
Stream0506
END DESCRIPTION:

--- Stream0506.p01 (plan) ---

Plan Title=Multiple Run
Short Identifier=Multiple
Geom File=g01
Flow File=f01
Subcritical Flow
K Sum by GR= 0
Std Step Tol= 0.01
Critical Tol= 0.01
Num of Std Step Trials= 20
Max Error Tol= 0.3
Flow Tol Ratio= 0.001
Split Flow NTrial= 30
Split Flow Tol= 0.02
Split Flow Ratio= 0.02
Log Output Level= 0
Friction Slope Method= 1
Unsteady Friction Slope Method= 2
Unsteady Bridges Friction Slope Method= 1
Parabolic Critical Depth
Global Vel Dist=  1 , 1 , 1
Global Log Level= 0
CheckData=True
Encroach Param= -1, 0, 0, 0
BEGIN DESCRIPTION:
Multiple Run
END DESCRIPTION:

--- Stream0506.f01 (steady flow) ---

Flow Title=Multiple
Number of Profiles=7
Profile Names=10-year,25-year,50-year,1pct_min,100-year,1pct_plu,500-year
River Rch & RM= Stream0506,Reach-1,5681
     818    1331    1799    1177    2348    4686    3963
River Rch & RM= Stream0506,Reach-1,4233
    1007    1665    2274    1502    2996    5978    5156
Boundary for River Rch & Prof#=Stream0506,Reach-1,1
Up Type=0
Dn Type=3
Dn Slope=0.005
Boundary for River Rch & Prof#=Stream0506,Reach-1,2
Up Type=0
Dn Type=3
Dn Slope=0.005
Boundary for River Rch & Prof#=Stream0506,Reach-1,3
Up Type=0
Dn Type=3
Dn Slope=0.005
Boundary for River Rch & Prof#=Stream0506,Reach-1,4
Up Type=0
Dn Type=3
Dn Slope=0.005
Boundary for River Rch & Prof#=Stream0506,Reach-1,5
Up Type=0
Dn Type=3
Dn Slope=0.005
Boundary for River Rch & Prof#=Stream0506,Reach-1,6
Up Type=0
Dn Type=3
Dn Slope=0.005
Boundary for River Rch & Prof#=Stream0506,Reach-1,7
Up Type=0
Dn Type=3
Dn Slope=0.005

--- Stream0506.g01 (geometry) ---

Geom Title=Existing Conditions

River Reach=Stream0506,Reach-1
Reach XY= 30
      2515825.00     13605025.00      2515730.87     13605022.90
      2515659.79     13604975.51      2515435.50     13604973.78
      2515164.49     13604876.22      2514980.94     13604872.74
      2514914.50     13604826.22      2514685.50     13604823.78
      2514414.49     13604726.22      2514230.94     13604722.74
      2514164.50     13604676.22      2513935.50     13604673.78
      2513669.06     13604577.26      2513235.51     13604523.78
      2513164.49     13604476.22      2512985.51     13604473.78
      2512914.49     13604426.22      2512735.51     13604423.78
      2512471.59     13604332.81      2512330.62     13604430.62
      2512082.86     13604718.83      2512061.60     13604838.30
      2511684.79     13605214.48      2511572.58     13605230.54
      2511273.53     13605471.46      2511130.94     13605477.27
      2510944.72     13605554.48      2510878.45     13605626.48
      2510875.22     13605709.79      2510975.00     13605825.00

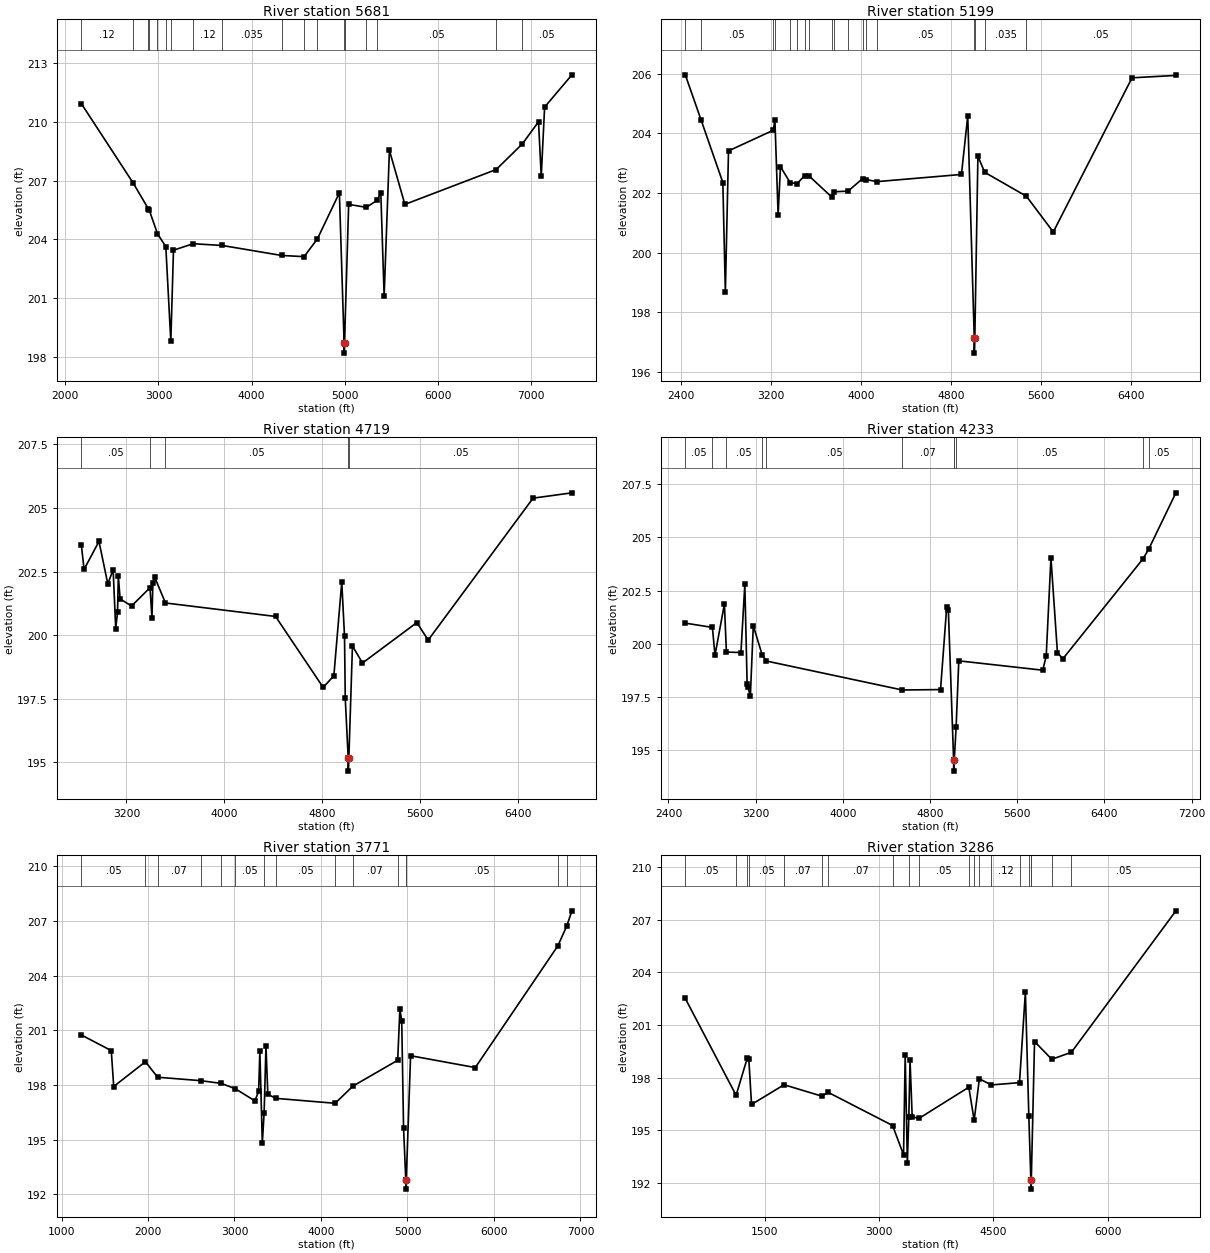
Type RM Length L Ch R = 1,5681,482,482,482
BEGIN DESCRIPTION:
Stream0506 12.0
END DESCRIPTION:
XS GIS Cut Line= 3
      2517524.99     13602975.01      2515525.00     13604975.00
      2516924.99     13606974.98
#Sta/Elev= 30
  2171.5  210.93  2728.6  206.87  2890.8  205.56  2901.0  205.49  2989.7  204.28
  3079.0  203.62  3132.8  198.79  3161.4  203.44  3373.0  203.77  3685.8  203.68
  4323.2  203.17  4564.4  203.11  4707.5  204.02  4943.3  206.37  4994.3  198.68
  4994.6  198.18  4998.4  198.68  5043.1  205.78  5232.7  205.63  5346.6  205.98
  5388.3  206.37  5424.1  201.10  5480.8  208.54  5646.9  205.78  6627.3  207.56
  6908.4  208.87  7082.4  210.00  7111.6  207.22  7147.8  210.75  7441.2  212.40
#Mann=18,-1,0
  2171.5    0.12       0  2728.6   0.035       0  2890.8    0.12       0
  2901.0   0.035       0  2989.7    0.05       0  3079.0    0.12       0
  3132.8    0.05       0  3373.0    0.12       0  3685.8   0.035       0
  4323.2    0.05       0  4564.4   0.035       0  4707.5    0.05       0
  4994.3    0.05       0  4998.4    0.05       0  5232.7   0.035       0
  5346.6    0.05       0  6627.3    0.07       0  6908.4    0.05       0
Bank Sta=4994.3,4998.4
Exp/Cntr=0.3,0.1

Type RM Length L Ch R = 1,5199,480,480,480
BEGIN DESCRIPTION:
Stream0506 11.0
END DESCRIPTION:
XS GIS Cut Line= 3
      2517074.97     13603275.03      2515075.00     13604875.00
      2515075.00     13606674.99
#Sta/Elev= 30
  2438.8  205.96  2577.9  204.46  2772.5  202.35  2794.9  198.67  2822.9  203.41
  3219.9  204.10  3235.5  204.44  3264.0  201.26  3284.8  202.88  3370.2  202.35
  3432.6  202.31  3499.1  202.58  3541.6  202.56  3744.5  201.85  3756.8  202.04
  3885.7  202.06  4014.6  202.48  4042.0  202.45  4143.5  202.38  4893.6  202.62
  4949.6  204.58  5007.5  197.13  5007.9  196.63  5012.5  197.13  5040.0  203.23
  5100.9  202.69  5471.1  201.89  5710.0  200.69  6410.0  205.86  6800.0  205.94
#Mann=18,-1,0
  2438.8    0.12       0  2577.9    0.05       0  3219.9    0.12       0
  3235.5    0.05       0  3370.2    0.12       0  3432.6   0.035       0
  3499.1    0.12       0  3541.6    0.05       0  3744.5   0.035       0
  3756.8    0.05       0  3885.7   0.035       0  4014.6    0.05       0
  4042.0   0.035       0  4143.5    0.05       0  5007.5    0.05       0
  5012.5    0.05       0  5100.9   0.035       0  5471.1    0.05       0
Bank Sta=5007.5,5012.5
Exp/Cntr=0.3,0.1

Type RM Length L Ch R = 1,4719,486,486,486
BEGIN DESCRIPTION:
Stream0506 10.0
END DESCRIPTION:
XS GIS Cut Line= 3
      2516424.99     13603575.01      2514625.00     13604775.00
      2515024.99     13606574.97
#Sta/Elev= 30
  2831.4  203.56  2853.9  202.59  2975.6  203.69  3047.7  202.02  3091.3  202.58
  3112.3  200.26  3127.3  200.91  3133.4  202.34  3148.4  201.43  3241.5  201.15
  3392.4  201.87  3408.3  200.69  3415.8  202.04  3430.8  202.28  3518.8  201.27
  4417.8  200.74  4806.9  197.95  4894.1  198.41  4958.7  202.09  4981.2  199.96
  4987.2  197.52  5011.4  195.16  5011.8  194.66  5016.5  195.16  5045.9  199.58
  5127.9  198.91  5572.2  200.50  5664.4  199.81  6521.1  205.39  6838.6  205.60
#Mann=5,-1,0
  2831.4    0.05       0  3392.4   0.035       0  3518.8    0.05       0
  5011.4    0.05       0  5016.5    0.05       0
Bank Sta=5011.4,5016.5
Exp/Cntr=0.3,0.1

Type RM Length L Ch R = 1,4233,462,462,462
BEGIN DESCRIPTION:
Stream0506 9.0
END DESCRIPTION:
XS GIS Cut Line= 3
      2516175.03     13603274.98      2514175.00     13604675.00
      2513174.99     13606475.02
#Sta/Elev= 30
  2554.5  200.97  2803.2  200.77  2827.0  199.46  2913.3  201.87  2931.6  199.61
  3065.0  199.59  3100.8  202.80  3121.7  198.10  3128.2  197.95  3151.4  197.56
  3178.4  200.85  3259.0  199.49  3299.1  199.19  4545.3  197.83  4896.0  197.85
  4952.7  201.74  4967.5  201.60  5016.0  194.52  5016.4  194.02  5021.5  194.52
  5038.8  196.07  5063.3  199.20  5833.2  198.76  5865.3  199.42  5908.7  204.04
  5968.2  199.59  6017.4  199.29  6753.1  203.99  6804.1  204.43  7055.0  207.09
#Mann=11,-1,0
  2554.5    0.05       0  2803.2   0.035       0  2931.6    0.05       0
  3259.0   0.035       0  3299.1    0.05       0  4545.3    0.07       0
  5016.0    0.05       0  5021.5    0.07       0  5038.8    0.05       0
  6753.1   0.035       0  6804.1    0.05       0
Bank Sta=5016,5021.5
Exp/Cntr=0.3,0.1

Type RM Length L Ch R = 1,3771,485,485,485
BEGIN DESCRIPTION:
Stream0506 8.0
END DESCRIPTION:
XS GIS Cut Line= 3
      2516423.60     13601984.02      2513725.00     13604625.00
      2513125.01     13606424.96
#Sta/Elev= 30
  1228.7  200.74  1575.0  199.88  1603.3  197.91  1969.8  199.27  2111.3  198.42
  2611.8  198.23  2847.9  198.08  3008.6  197.79  3236.7  197.12  3279.2  197.66
  3293.3  199.85  3321.6  194.80  3342.6  196.47  3364.0  200.14  3385.2  197.48
  3479.6  197.26  4164.2  196.99  4368.5  197.93  4887.0  199.35  4912.6  202.16
  4933.9  201.48  4955.1  195.62  4980.6  192.78  4981.0  192.28  4986.1  192.78
  5036.2  199.60  5784.6  198.95  6739.5  205.63  6842.4  206.72  6901.9  207.55
#Mann=15,-1,0
  1228.7    0.05       0  1969.8   0.035       0  2111.3    0.07       0
  2611.8    0.05       0  2847.9    0.07       0  3008.6    0.05       0
  3342.6   0.035       0  3479.6    0.05       0  4164.2    0.12       0
  4368.5    0.07       0  4887.0    0.05       0  4980.6    0.05       0
  4986.1    0.05       0  6739.5   0.035       0  6842.4    0.05       0
Bank Sta=4980.6,4986.1
Exp/Cntr=0.3,0.1

Type RM Length L Ch R = 1,3286,482,482,482
BEGIN DESCRIPTION:
Stream0506 7.0
END DESCRIPTION:
XS GIS Cut Line= 3
      2516371.47     13601202.81      2513275.00     13604525.00
      2512675.01     13606324.96
#Sta/Elev= 30
   458.1  202.51  1124.9  197.00  1273.7  199.15  1291.8  199.05  1327.4  196.48
  1754.8  197.60  2251.9  196.95  2332.3  197.17  3179.1  195.28  3322.6  193.61
  3344.1  199.31  3372.5  193.16  3391.7  195.75  3407.6  199.00  3436.0  195.78
  3522.9  195.68  4179.1  197.46  4249.2  195.58  4317.7  197.94  4474.2  197.59
  4844.3  197.72  4921.7  202.89  4966.5  195.84  4993.4  192.16  4993.8  191.66
  4999.0  192.16  5041.7  200.06  5268.3  199.05  5525.6  199.45  6896.9  207.50
#Mann=20,-1,0
   458.1    0.05       0  1124.9   0.035       0  1273.7    0.12       0
  1291.8    0.05       0  1754.8    0.07       0  2251.9    0.05       0
  2332.3    0.07       0  3179.1    0.05       0  3391.7   0.035       0
  3522.9    0.05       0  4179.1    0.07       0  4249.2    0.12       0
  4317.7    0.07       0  4474.2    0.12       0  4844.3    0.07       0
  4966.5    0.05       0  4993.4    0.05       0  4999.0    0.05       0
  5268.3   0.035       0  5525.6    0.05       0
Bank Sta=4993.4,4999
Exp/Cntr=0.3,0.1

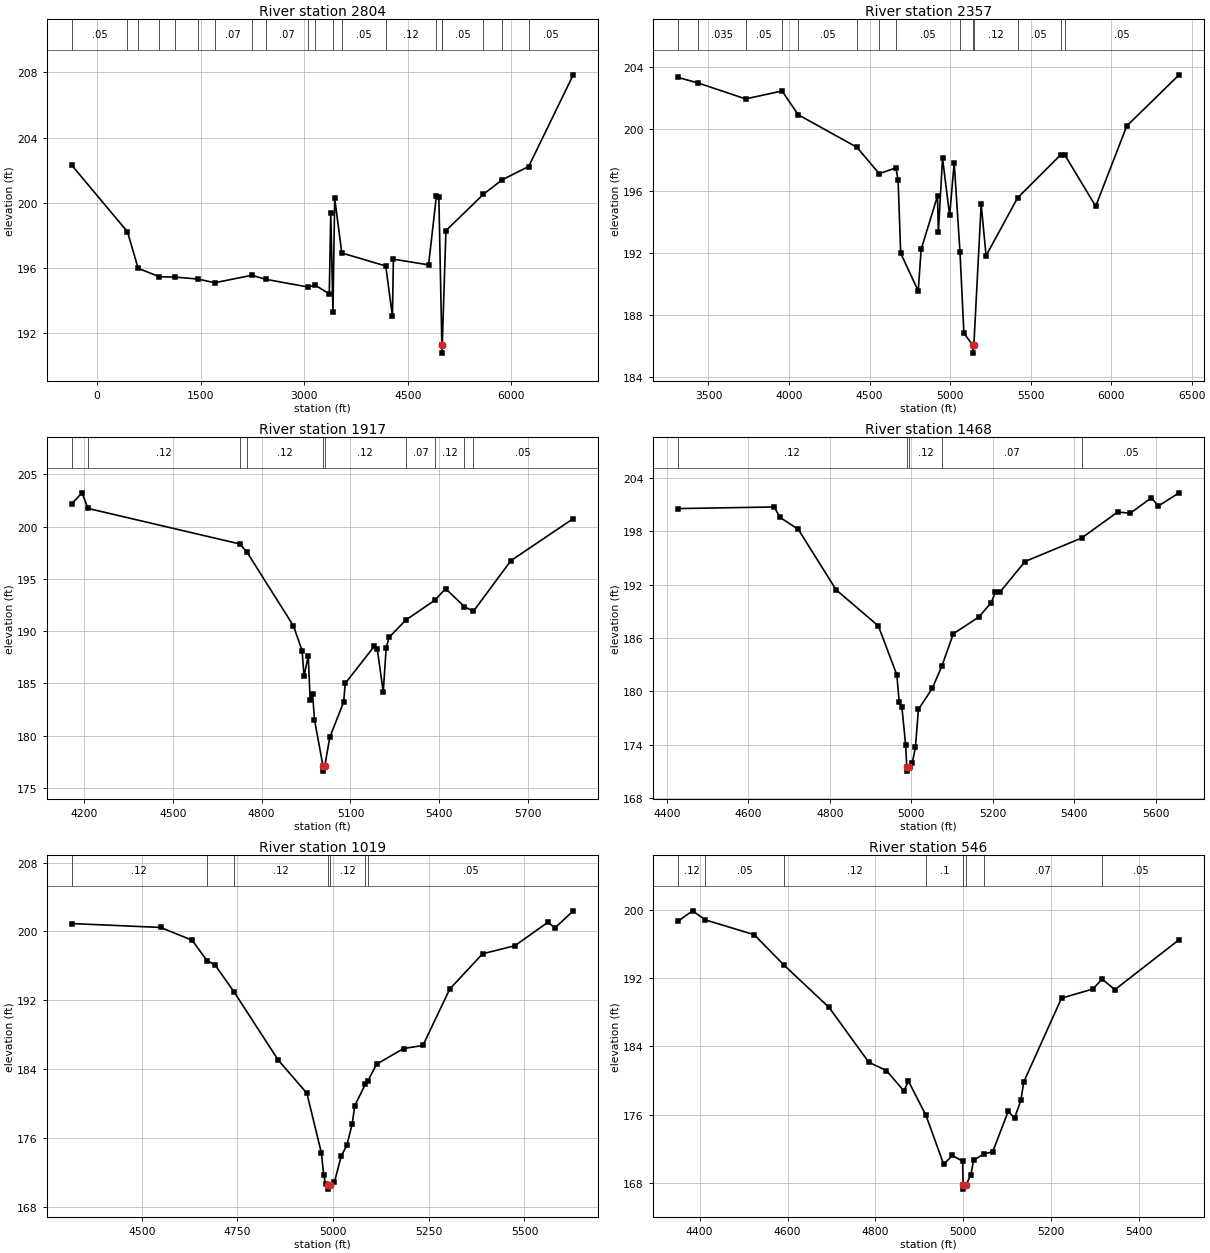
Type RM Length L Ch R = 1,2804,447,447,447
BEGIN DESCRIPTION:
Stream0506 6.0
END DESCRIPTION:
XS GIS Cut Line= 3
      2516371.48     13600395.51      2512825.00     13604425.00
      2512224.99     13606225.03
#Sta/Elev= 30
  -367.9  202.30   439.8  198.21   593.6  195.97   901.2  195.45  1123.8  195.43
  1460.1  195.31  1702.2  195.08  2238.8  195.54  2446.8  195.29  3054.7  194.82
  3160.1  194.93  3362.9  194.40  3384.7  199.34  3416.2  193.30  3441.4  200.27
  3544.3  196.91  4181.1  196.11  4277.5  193.04  4291.7  196.53  4801.3  196.18
  4915.2  200.42  4950.2  200.34  4993.9  191.26  4994.3  190.76  4999.5  191.26
  5052.7  198.28  5596.5  200.52  5870.3  201.41  6251.5  202.22  6897.4  207.85
#Mann=20,-1,0
  -367.9    0.05       0   439.8   0.035       0   593.6    0.07       0
   901.2    0.07       0  1123.8    0.05       0  1460.1    0.05       0
  1702.2    0.07       0  2238.8    0.05       0  2446.8    0.07       0
  3054.7    0.12       0  3160.1    0.05       0  3416.2   0.035       0
  3544.3    0.05       0  4181.1    0.12       0  4915.2    0.05       0
  4993.9    0.05       0  4999.5    0.05       0  5596.5   0.035       0
  5870.3    0.05       0  6251.5    0.05       0
Bank Sta=4993.9,4999.5
Exp/Cntr=0.3,0.1

Type RM Length L Ch R = 1,2357,440,440,440
BEGIN DESCRIPTION:
Stream0506 5.0
END DESCRIPTION:
XS GIS Cut Line= 3
      2510825.00     13603825.00      2512425.00     13604375.00
      2512175.01     13605774.96
#Sta/Elev= 30
  3308.3  203.31  3437.5  202.94  3730.5  201.92  3956.8  202.43  4057.4  200.90
  4421.5  198.81  4560.0  197.11  4663.5  197.48  4677.4  196.70  4693.5  191.99
  4802.4  189.56  4820.4  192.23  4922.1  195.67  4927.4  193.34  4953.3  198.10
  4997.5  194.42  5025.6  197.82  5061.5  192.10  5086.0  186.84  5142.1  186.06
  5142.6  185.56  5147.7  186.06  5193.2  195.14  5223.7  191.83  5419.2  195.55
  5688.7  198.34  5714.0  198.29  5904.3  195.01  6097.3  200.18  6422.3  203.47
#Mann=14,-1,0
  3308.3    0.05       0  3437.5   0.035       0  3730.5    0.05       0
  3956.8   0.035       0  4057.4    0.05       0  4421.5    0.12       0
  4560.0    0.07       0  4663.5    0.05       0  5061.5    0.12       0
  5142.1    0.05       0  5147.7    0.12       0  5419.2    0.05       0
  5688.7    0.07       0  5714.0    0.05       0
Bank Sta=5142.1,5147.7
Exp/Cntr=0.3,0.1

Type RM Length L Ch R = 1,1917,449,449,449
BEGIN DESCRIPTION:
Stream0506 4.0
END DESCRIPTION:
XS GIS Cut Line= 3
      2511453.96     13604167.76      2512125.00     13604675.00
      2512179.18     13605525.20
#Sta/Elev= 30
  4159.1  202.19  4193.9  203.24  4213.7  201.75  4725.9  198.35  4750.4  197.58
  4907.7  190.50  4936.8  188.13  4943.1  185.69  4957.6  187.63  4963.9  183.43
  4972.2  184.01  4978.4  181.55  5007.3  177.11  5007.8  176.61  5013.3  177.11
  5030.3  179.85  5077.2  183.23  5082.2  185.00  5180.6  188.56  5190.7  188.26
  5210.7  184.19  5220.7  188.43  5230.7  189.42  5286.7  191.06  5385.6  192.98
  5421.1  194.07  5484.6  192.36  5514.8  191.89  5641.6  196.75  5852.2  200.77
#Mann=10,-1,0
  4159.1    0.05       0  4213.7    0.12       0  4725.9    0.05       0
  4750.4    0.12       0  5007.3    0.05       0  5013.3    0.12       0
  5286.7    0.07       0  5385.6    0.12       0  5484.6    0.07       0
  5514.8    0.05       0
Bank Sta=5007.3,5013.3
Exp/Cntr=0.3,0.1

Type RM Length L Ch R = 1,1468,449,449,449
BEGIN DESCRIPTION:
Stream0506 3.0
END DESCRIPTION:
XS GIS Cut Line= 3
      2511590.34     13604527.25      2511875.00     13605025.00
      2512042.62     13605660.77
#Sta/Elev= 30
  4426.6  200.54  4663.9  200.72  4677.4  199.57  4722.9  198.20  4815.7  191.41
  4919.4  187.35  4964.7  181.85  4970.5  178.79  4977.0  178.24  4986.3  173.98
  4989.0  171.54  4989.5  171.04  4995.1  171.54  5002.6  171.98  5010.3  173.70
  5017.6  177.97  5051.7  180.35  5075.3  182.86  5103.4  186.48  5165.5  188.34
  5196.5  189.97  5206.8  191.19  5219.0  191.22  5279.2  194.59  5418.0  197.23
  5506.7  200.15  5537.8  200.02  5589.5  201.76  5606.5  200.83  5657.5  202.31
#Mann=5,-1,0
  4426.6    0.12       0  4989.0    0.05       0  4995.1    0.12       0
  5075.3    0.07       0  5418.0    0.05       0
Bank Sta=4989,4995.1
Exp/Cntr=0.3,0.1

Type RM Length L Ch R = 1,1019,473,473,473
BEGIN DESCRIPTION:
Stream0506 2.0
END DESCRIPTION:
XS GIS Cut Line= 3
      2511379.61     13604607.83      2511525.00     13605275.00
      2511930.61     13605753.75
#Sta/Elev= 30
  4317.2  200.91  4549.2  200.46  4631.6  198.98  4670.5  196.61  4691.3  196.12
  4740.8  193.00  4856.7  185.05  4931.5  181.20  4969.3  174.29  4975.5  171.71
  4980.6  170.62  4986.7  170.56  4987.2  170.06  4992.9  170.56  5003.3  170.85
  5021.5  173.93  5035.8  175.14  5050.0  177.64  5056.6  179.76  5084.0  182.22
  5091.0  182.65  5113.7  184.58  5184.0  186.39  5234.6  186.75  5304.9  193.31
  5390.6  197.40  5475.1  198.34  5560.9  201.05  5580.2  200.43  5627.5  202.39
#Mann=7,-1,0
  4317.2    0.12       0  4670.5    0.05       0  4740.8    0.12       0
  4986.7    0.05       0  4992.9    0.12       0  5084.0    0.07       0
  5091.0    0.05       0
Bank Sta=4986.7,4992.9
Exp/Cntr=0.3,0.1

Type RM Length L Ch R = 1,546,0,0,0
BEGIN DESCRIPTION:
Stream0506 1.0
END DESCRIPTION:
XS GIS Cut Line= 3
      2511162.68     13604830.98      2511125.00     13605475.00
      2511516.00     13605779.33
#Sta/Elev= 30
  4350.0  198.68  4384.1  199.93  4413.1  198.87  4524.3  197.12  4591.3  193.59
  4694.6  188.58  4784.8  182.15  4824.8  181.18  4864.9  178.77  4874.9  179.95
  4914.9  175.90  4955.1  170.18  4975.1  171.20  4998.3  170.52  4999.3  167.75
  4999.8  167.25  5005.5  167.75  5016.8  168.87  5023.2  170.65  5047.0  171.39
  5066.6  171.63  5101.9  176.39  5116.4  175.60  5130.8  177.68  5137.2  179.83
  5223.2  189.68  5294.6  190.75  5315.5  191.92  5344.4  190.67  5490.6  196.54
#Mann=8,-1,0
  4350.0    0.12       0  4413.1    0.05       0  4591.3    0.12       0
  4914.9     0.1       0  4999.3    0.05       0  5005.5     0.1       0
  5047.0    0.07       0  5315.5    0.05       0
Bank Sta=4999.3,5005.5
Exp/Cntr=0.3,0.1

Chan Stop Cuts=-1