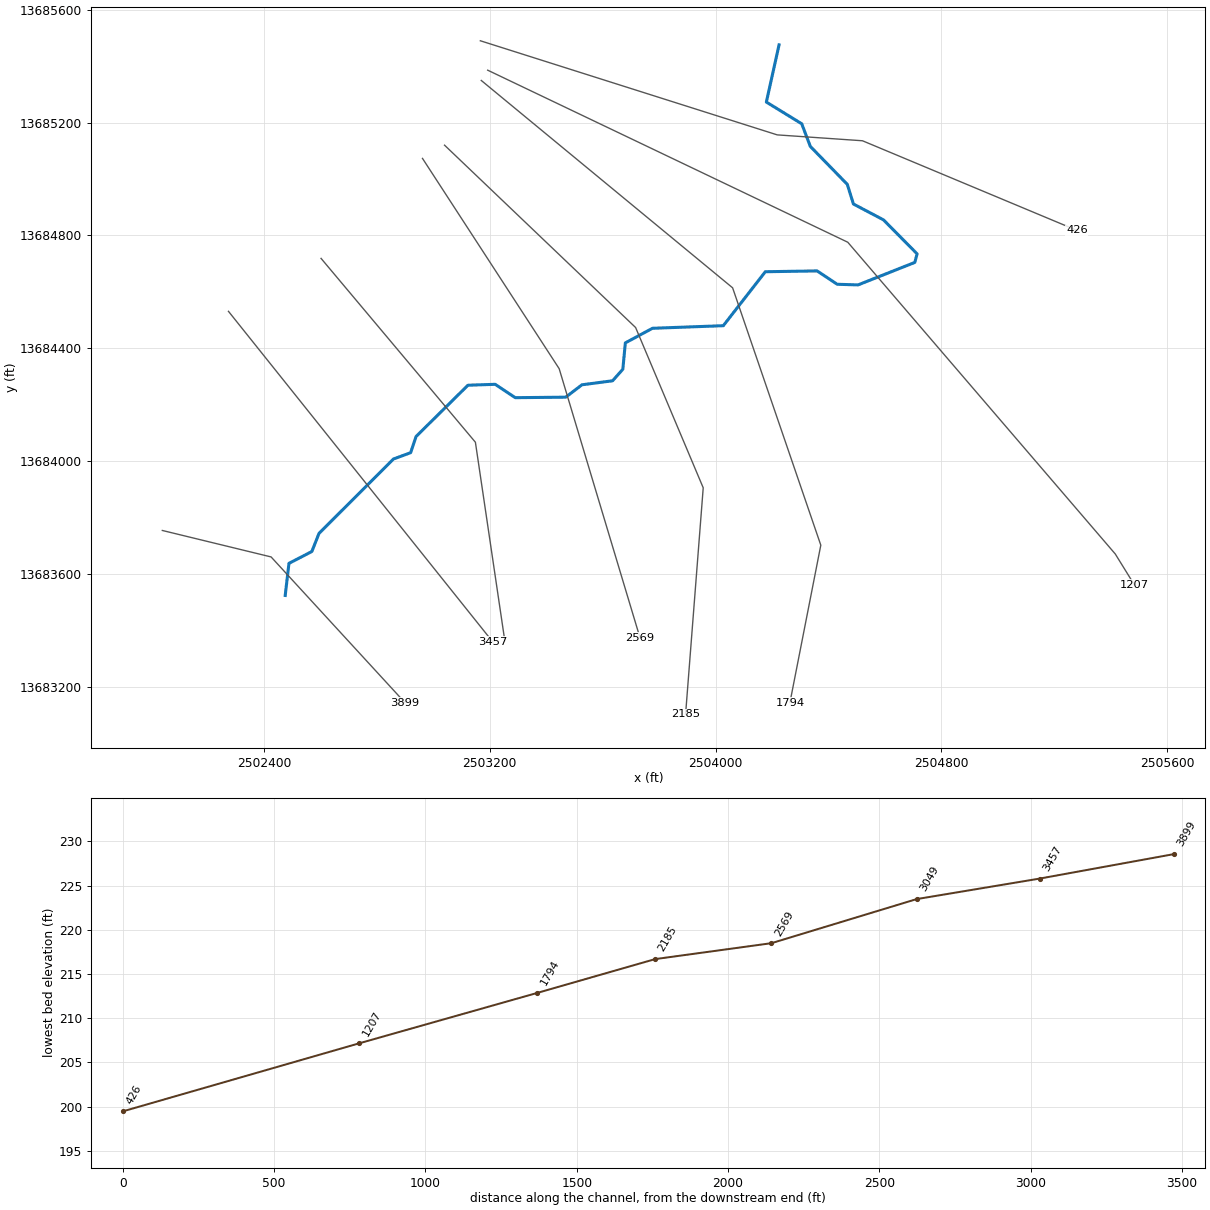
--- Stream0507.prj (project) ---

Proj Title=Stream0507 Base Level Engineering
Current Plan=p01
Default Exp/Contr=0.3,0.1
English Units
Geom File=g01
Flow File=f01
Plan File=p01
BEGIN DESCRIPTION:
Stream0507
END DESCRIPTION:

--- Stream0507.p01 (plan) ---

Plan Title=Multiple Run
Short Identifier=Multiple
Geom File=g01
Flow File=f01
Subcritical Flow
K Sum by GR= 0
Std Step Tol= 0.01
Critical Tol= 0.01
Num of Std Step Trials= 20
Max Error Tol= 0.3
Flow Tol Ratio= 0.001
Split Flow NTrial= 30
Split Flow Tol= 0.02
Split Flow Ratio= 0.02
Log Output Level= 0
Friction Slope Method= 1
Unsteady Friction Slope Method= 2
Unsteady Bridges Friction Slope Method= 1
Parabolic Critical Depth
Global Vel Dist=  1 , 1 , 1
Global Log Level= 0
CheckData=True
Encroach Param= -1, 0, 0, 0
BEGIN DESCRIPTION:
Multiple Run
END DESCRIPTION:

--- Stream0507.f01 (steady flow) ---

Flow Title=Multiple
Number of Profiles=7
Profile Names=10-year,25-year,50-year,1pct_min,100-year,1pct_plu,500-year
River Rch & RM= Stream0507,Reach-1,3899
     578     930    1247     812    1620    3232    2702
Boundary for River Rch & Prof#=Stream0507,Reach-1,1
Up Type=0
Dn Type=3
Dn Slope=0.005
Boundary for River Rch & Prof#=Stream0507,Reach-1,2
Up Type=0
Dn Type=3
Dn Slope=0.005
Boundary for River Rch & Prof#=Stream0507,Reach-1,3
Up Type=0
Dn Type=3
Dn Slope=0.005
Boundary for River Rch & Prof#=Stream0507,Reach-1,4
Up Type=0
Dn Type=3
Dn Slope=0.005
Boundary for River Rch & Prof#=Stream0507,Reach-1,5
Up Type=0
Dn Type=3
Dn Slope=0.005
Boundary for River Rch & Prof#=Stream0507,Reach-1,6
Up Type=0
Dn Type=3
Dn Slope=0.005
Boundary for River Rch & Prof#=Stream0507,Reach-1,7
Up Type=0
Dn Type=3
Dn Slope=0.005

--- Stream0507.g01 (geometry) ---

Geom Title=Existing Conditions

River Reach=Stream0507,Reach-1
Reach XY= 30
      2502475.00     13683525.00      2502488.26     13683638.69
      2502569.35     13683680.63      2502594.86     13683744.92
      2502858.52     13684008.27      2502919.38     13684030.62
      2502938.73     13684087.98      2503122.57     13684269.60
      2503219.02     13684272.84      2503290.22     13684225.52
      2503469.06     13684227.26      2503526.60     13684271.14
      2503635.16     13684285.37      2503671.46     13684326.33
      2503680.25     13684419.56      2503776.52     13684471.26
      2504027.47     13684480.45      2504176.25     13684671.55
      2504359.78     13684674.48      2504430.98     13684627.17
      2504504.90     13684624.90      2504705.99     13684704.52
      2504714.11     13684734.86      2504595.08     13684855.21
      2504488.49     13684911.44      2504466.83     13684981.03
      2504335.79     13685115.34      2504305.36     13685195.47
      2504179.99     13685272.45      2504225.00     13685475.00

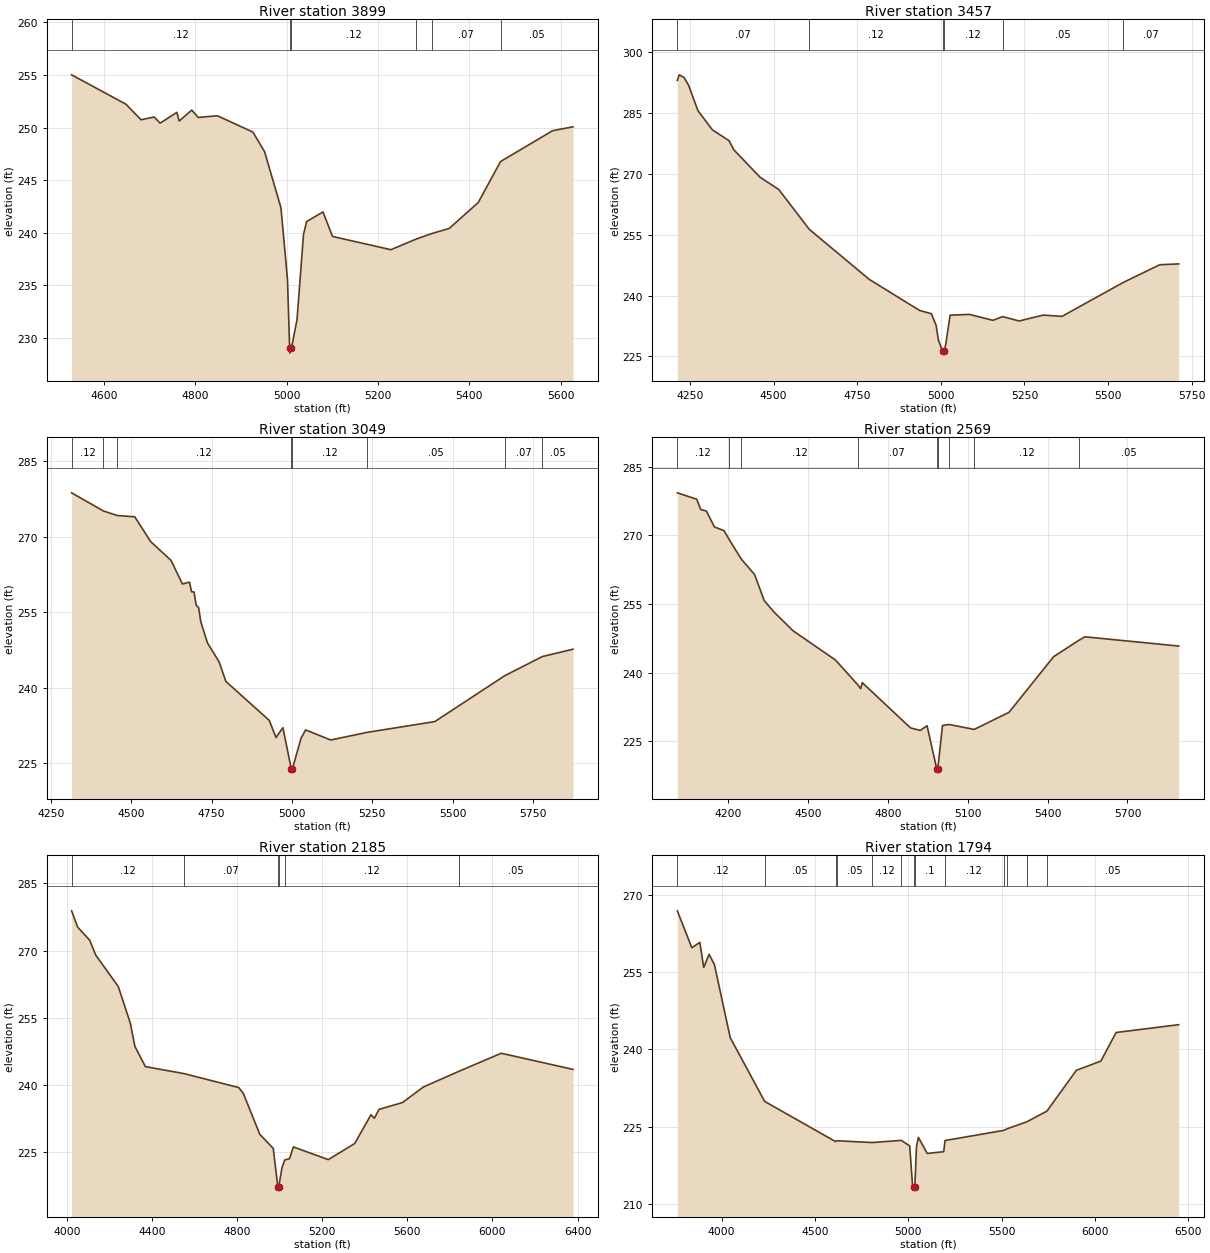
Type RM Length L Ch R = 1,3899,442,442,442
BEGIN DESCRIPTION:
XS6959
END DESCRIPTION:
XS GIS Cut Line= 3
      2502039.55     13683755.22      2502425.00     13683661.46
      2502898.99     13683145.80
#Sta/Elev= 30
  4529.7  255.01  4648.5  252.22  4681.6  250.74  4710.3  251.00  4723.4  250.42
  4760.0  251.44  4765.1  250.62  4792.6  251.66  4806.8  250.96  4848.6  251.12
  4926.4  249.57  4952.0  247.70  4987.8  242.37  5002.0  235.61  5006.8  229.06
  5007.0  228.56  5010.8  229.06  5022.9  231.73  5037.1  239.83  5043.9  241.06
  5079.7  241.98  5100.6  239.65  5228.3  238.39  5283.6  239.40  5318.2  239.93
  5355.9  240.41  5419.4  242.87  5468.3  246.77  5582.2  249.70  5626.8  250.07
#Mann=6,-1,0
  4529.7    0.12       0  5006.8    0.05       0  5010.8    0.12       0
  5283.6    0.05       0  5318.2    0.07       0  5468.3    0.05       0
Bank Sta=5006.8,5010.8
Exp/Cntr=0.3,0.1

Type RM Length L Ch R = 1,3457,408,408,408
BEGIN DESCRIPTION:
XS6958
END DESCRIPTION:
XS GIS Cut Line= 2
      2502273.94     13684531.28      2503210.48     13683360.60
#Sta/Elev= 30
  4212.2  293.04  4217.9  294.42  4232.3  293.76  4245.9  291.85  4273.9  285.58
  4317.1  280.84  4366.7  278.20  4381.1  275.94  4459.6  269.17  4515.6  266.14
  4606.7  256.33  4786.1  243.98  4936.6  236.32  4971.8  235.52  4986.2  232.60
  4992.6  229.10  5005.1  226.30  5005.3  225.80  5009.1  226.30  5014.2  227.71
  5027.9  235.15  5085.5  235.35  5155.9  233.89  5184.8  234.80  5234.4  233.73
  5306.4  235.18  5362.4  234.86  5545.6  243.23  5654.5  247.59  5711.4  247.80
#Mann=6,-1,0
  4212.2    0.07       0  4606.7    0.12       0  5005.1    0.05       0
  5009.1    0.12       0  5184.8    0.05       0  5545.6    0.07       0
Bank Sta=5005.1,5009.1
Exp/Cntr=0.3,0.1

Type RM Length L Ch R = 1,3049,480,480,480
BEGIN DESCRIPTION:
XS6957
END DESCRIPTION:
XS GIS Cut Line= 3
      2502602.06     13684718.78      2503148.96     13684067.71
      2503253.13     13683364.58
#Sta/Elev= 30
  4313.9  278.71  4412.5  275.12  4455.6  274.21  4510.5  273.95  4560.0  269.03
  4623.7  265.28  4658.8  260.62  4680.9  260.98  4687.4  259.07  4695.2  259.03
  4701.7  256.42  4709.5  255.89  4716.1  253.14  4736.9  248.92  4773.3  245.14
  4794.1  241.28  4929.4  233.53  4950.2  230.14  4971.8  232.09  4997.6  223.97
  4997.9  223.47  5001.6  223.97  5028.2  229.99  5042.5  231.65  5120.6  229.65
  5233.6  231.16  5444.6  233.30  5662.8  242.42  5779.5  246.21  5875.0  247.67
#Mann=8,-1,0
  4313.9    0.12       0  4412.5    0.07       0  4455.6    0.12       0
  4997.6    0.05       0  5001.6    0.12       0  5233.6    0.05       0
  5662.8    0.07       0  5779.5    0.05       0
Bank Sta=4997.6,5001.6
Exp/Cntr=0.3,0.1

Type RM Length L Ch R = 1,2569,384,384,384
BEGIN DESCRIPTION:
XS6956
END DESCRIPTION:
XS GIS Cut Line= 3
      2502961.43     13685072.96      2503445.83     13684328.13
      2503732.28     13683375.03
#Sta/Elev= 30
  4008.8  279.27  4081.7  277.87  4096.9  275.60  4118.0  275.30  4148.2  271.81
  4184.5  271.01  4204.0  269.02  4249.3  264.79  4299.1  261.41  4335.4  255.71
  4371.6  253.25  4444.1  249.11  4602.8  242.76  4686.8  237.34  4697.7  236.48
  4703.7  237.80  4884.9  227.92  4921.4  227.37  4947.0  228.40  4983.3  218.98
  4983.5  218.48  4987.3  218.98  5005.0  228.45  5030.0  228.67  5124.1  227.59
  5254.8  231.32  5422.7  243.49  5516.8  247.03  5539.9  247.82  5892.5  245.80
#Mann=9,-1,0
  4008.8    0.12       0  4204.0    0.07       0  4249.3    0.12       0
  4686.8    0.07       0  4983.3    0.05       0  4987.3    0.07       0
  5030.0    0.07       0  5124.1    0.12       0  5516.8    0.05       0
Bank Sta=4983.3,4987.3
Exp/Cntr=0.3,0.1

Type RM Length L Ch R = 1,2185,391,391,391
BEGIN DESCRIPTION:
XS6955
END DESCRIPTION:
XS GIS Cut Line= 4
      2503039.58     13685119.80      2503716.67     13684473.96
      2503956.25     13683906.25      2503893.75     13683104.18
#Sta/Elev= 30
  4022.4  278.87  4050.9  275.22  4107.5  272.30  4135.8  268.98  4241.8  261.95
  4298.4  253.76  4319.8  248.58  4369.1  244.06  4550.3  242.50  4807.6  239.38
  4829.0  238.12  4906.7  228.94  4970.0  225.78  4991.7  217.18  4991.9  216.68
  4995.7  217.18  5011.2  221.49  5023.8  223.19  5046.5  223.49  5064.8  226.11
  5228.8  223.27  5352.8  226.87  5429.4  233.30  5445.4  232.51  5467.1  234.50
  5577.4  236.03  5675.9  239.51  5843.2  243.02  6041.4  247.04  6378.8  243.44
#Mann=6,-1,0
  4022.4    0.12       0  4550.3    0.07       0  4991.7    0.05       0
  4995.7    0.07       0  5023.8    0.12       0  5843.2    0.05       0
Bank Sta=4991.7,4995.7
Exp/Cntr=0.3,0.1

Type RM Length L Ch R = 1,1794,587,587,587
BEGIN DESCRIPTION:
XS6954
END DESCRIPTION:
XS GIS Cut Line= 4
      2503169.76     13685348.98      2504060.42     13684614.58
      2504372.92     13683703.13      2504263.55     13683145.88
#Sta/Elev= 30
  3763.1  266.96  3840.6  259.79  3883.7  260.82  3904.5  255.96  3933.2  258.50
  3961.8  256.50  4046.5  242.30  4230.9  229.90  4610.5  222.09  4616.3  222.25
  4807.0  221.90  4962.9  222.32  5007.8  221.24  5022.8  213.74  5031.3  213.34
  5031.6  212.84  5035.3  213.34  5044.4  221.19  5054.5  222.89  5101.6  219.78
  5190.2  220.12  5197.0  222.29  5511.3  224.26  5530.9  224.59  5634.0  225.91
  5742.6  228.00  5900.4  235.94  6032.0  237.74  6113.5  243.30  6448.9  244.82
#Mann=13,-1,0
  3763.1    0.12       0  4230.9    0.05       0  4610.5    0.07       0
  4616.3    0.05       0  4807.0    0.12       0  4962.9     0.1       0
  5031.3    0.05       0  5035.3     0.1       0  5197.0    0.12       0
  5511.3    0.05       0  5530.9    0.12       0  5634.0    0.07       0
  5742.6    0.05       0
Bank Sta=5031.3,5035.3
Exp/Cntr=0.3,0.1

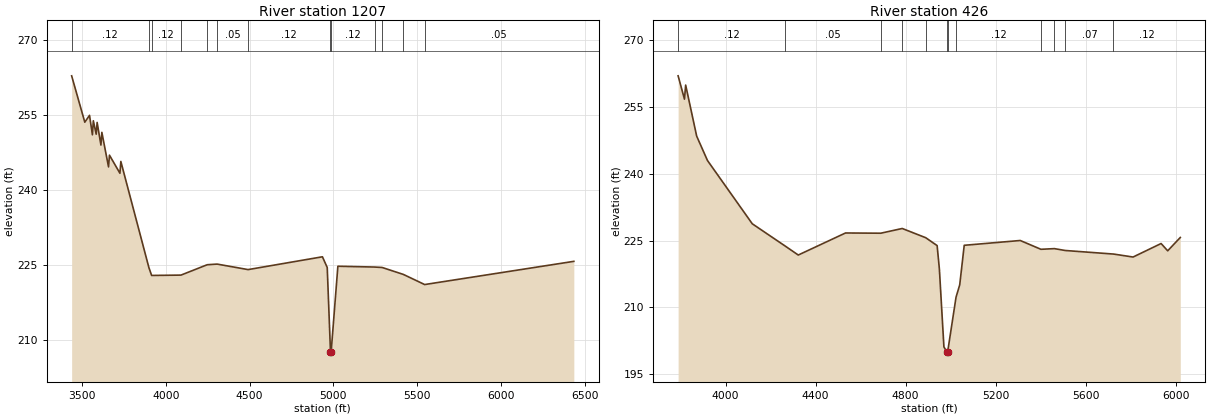
Type RM Length L Ch R = 1,1207,781,781,781
BEGIN DESCRIPTION:
E21118
END DESCRIPTION:
XS GIS Cut Line= 4
      2503192.47     13685385.41      2504468.50     13684776.04
      2505416.42     13683671.88      2505484.10     13683562.54
#Sta/Elev= 30
  3437.9  262.79  3516.4  253.52  3544.6  254.89  3561.8  251.00  3567.3  253.81
  3584.5  251.12  3590.0  253.47  3612.7  248.95  3618.2  251.49  3658.1  244.58
  3663.6  246.93  3726.1  243.31  3731.6  245.67  3899.2  224.43  3915.4  222.88
  4090.6  222.95  4247.1  225.02  4306.4  225.15  4491.2  224.05  4935.0  226.61
  4963.6  224.47  4983.1  207.65  4983.4  207.15  4987.1  207.65  5027.2  224.72
  5247.0  224.56  5291.8  224.47  5418.5  223.08  5545.3  221.06  6435.8  225.70
#Mann=13,-1,0
  3437.9    0.12       0  3899.2    0.05       0  3915.4    0.12       0
  4090.6    0.05       0  4247.1    0.12       0  4306.4    0.05       0
  4491.2    0.12       0  4983.1    0.05       0  4987.1    0.12       0
  5247.0    0.05       0  5291.8    0.12       0  5418.5    0.07       0
  5545.3    0.05       0
Bank Sta=4983.1,4987.1
Exp/Cntr=0.3,0.1

Type RM Length L Ch R = 1,426,0,0,0
BEGIN DESCRIPTION:
E21117
END DESCRIPTION:
XS GIS Cut Line= 4
      2503166.44     13685489.58      2504218.50     13685156.25
      2504520.58     13685135.42      2505280.52     13684817.91
#Sta/Elev= 30
  3789.5  262.05  3817.7  256.81  3823.0  259.97  3871.9  248.49  3919.8  243.01
  4118.8  228.77  4263.8  223.80  4323.0  221.74  4532.8  226.70  4689.5  226.65
  4784.7  227.71  4888.9  225.64  4939.7  223.86  4949.7  218.57  4969.8  201.09
  4982.4  199.95  4982.6  199.45  4986.4  199.95  5023.6  212.25  5040.0  215.04
  5060.0  223.93  5308.7  225.01  5400.6  223.03  5460.4  223.18  5508.5  222.76
  5722.7  221.96  5809.8  221.29  5934.2  224.33  5963.5  222.69  6019.5  225.69
#Mann=12,-1,0
  3789.5    0.12       0  4263.8    0.05       0  4689.5    0.12       0
  4784.7    0.05       0  4888.9     0.1       0  4982.4    0.05       0
  4986.4     0.1       0  5023.6    0.12       0  5400.6    0.07       0
  5460.4    0.12       0  5508.5    0.07       0  5722.7    0.12       0
Bank Sta=4982.4,4986.4
Exp/Cntr=0.3,0.1

Chan Stop Cuts=-1