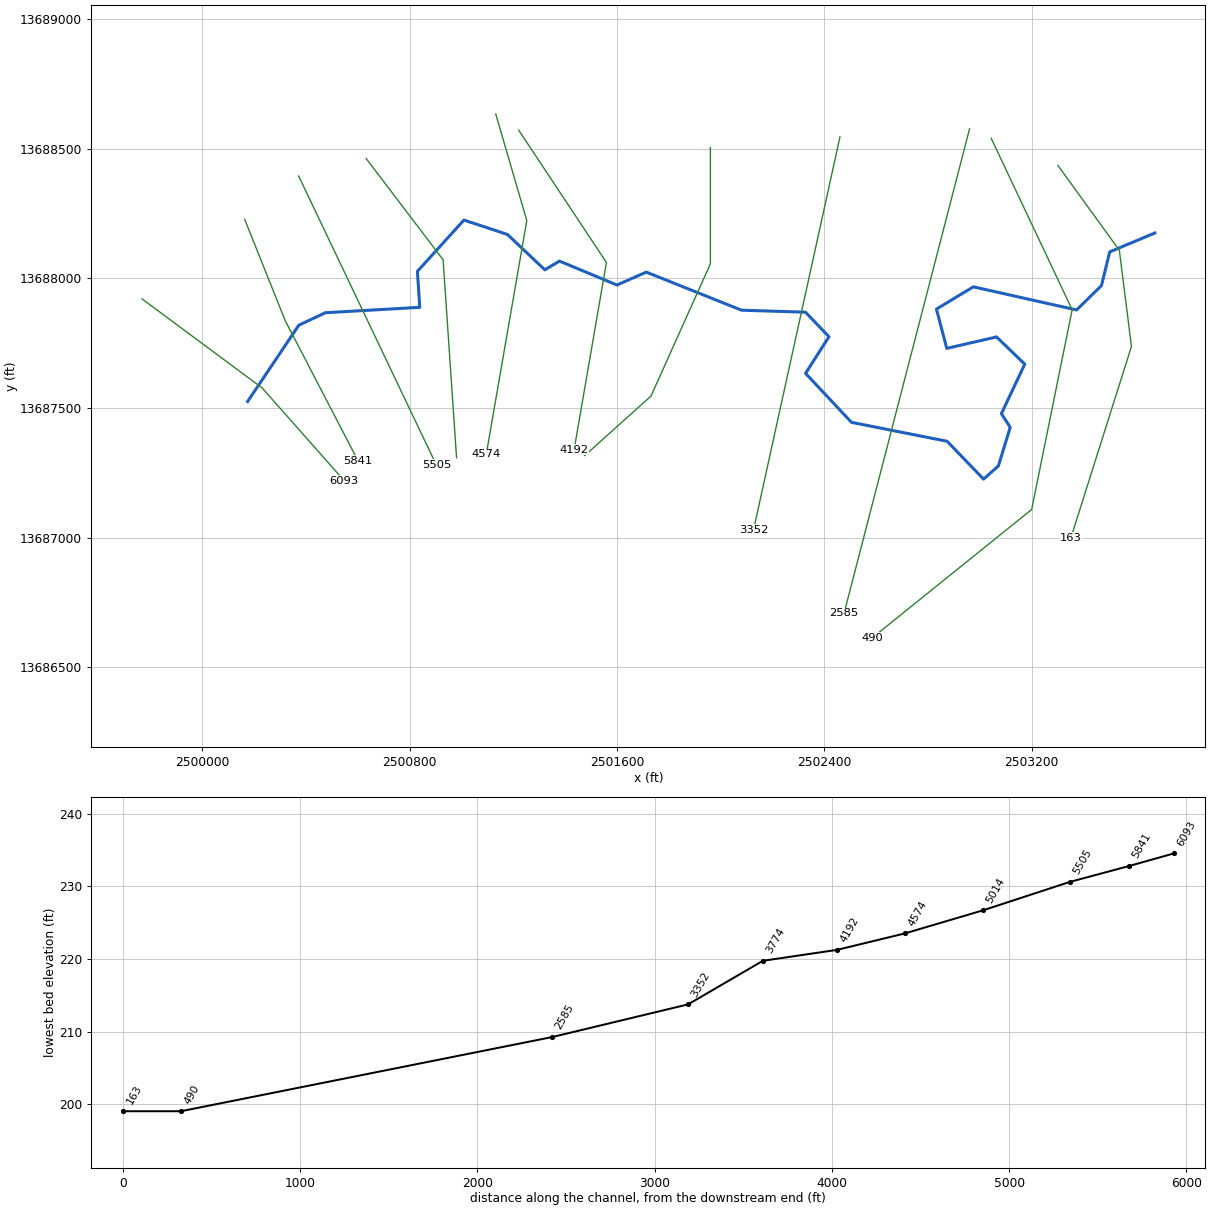
--- Stream0508.prj (project) ---

Proj Title=Stream0508 Base Level Engineering
Current Plan=p01
Default Exp/Contr=0.3,0.1
English Units
Geom File=g01
Flow File=f01
Plan File=p01
Y Axis Title=Elevation
X Axis Title(PF)=Main Channel Distance
X Axis Title(XS)=Station
BEGIN DESCRIPTION:
Stream0508
END DESCRIPTION:
DSS Export Rating Curves= 0
DSS Export Rating Curve Sorted= 0
DSS Export Volume Flow Curves= 0
DXF OffsetX= 0
DXF OffsetY= 0
DXF ScaleX= 1
DXF ScaleY= 10

--- Stream0508.p01 (plan) ---

Plan Title=Multiple Run
Short Identifier=Multiple
Geom File=g01
Flow File=f01
Subcritical Flow
K Sum by GR= 0
Std Step Tol= 0.01
Critical Tol= 0.01
Num of Std Step Trials= 20
Max Error Tol= 0.3
Flow Tol Ratio= 0.001
Split Flow NTrial= 30
Split Flow Tol= 0.02
Split Flow Ratio= 0.02
Log Output Level= 0
Friction Slope Method= 1
Unsteady Friction Slope Method= 2
Unsteady Bridges Friction Slope Method= 1
Parabolic Critical Depth
Global Vel Dist=  1 , 1 , 1
Global Log Level= 0
CheckData=True
Encroach Param= -1, 0, 0, 0
BEGIN DESCRIPTION:
Multiple Run
END DESCRIPTION:

--- Stream0508.f01 (steady flow) ---

Flow Title=Multiple
Number of Profiles=7
Profile Names=10-year,25-year,50-year,1pct_min,100-year,1pct_plu,500-year
River Rch & RM= Stream0508,Reach-1,6093
     985    1626    2220    1467    2927    5840    5037
River Rch & RM= Stream0508,Reach-1,5505
    1078    1783    2437    1612    3215    6416    5543
River Rch & RM= Stream0508,Reach-1,3774
    1236    2050    2807    1858    3707    7397    6404
Boundary for River Rch & Prof#=Stream0508,Reach-1,1
Up Type=0
Dn Type=3
Dn Slope=0.005
Boundary for River Rch & Prof#=Stream0508,Reach-1,2
Up Type=0
Dn Type=3
Dn Slope=0.005
Boundary for River Rch & Prof#=Stream0508,Reach-1,3
Up Type=0
Dn Type=3
Dn Slope=0.005
Boundary for River Rch & Prof#=Stream0508,Reach-1,4
Up Type=0
Dn Type=3
Dn Slope=0.005
Boundary for River Rch & Prof#=Stream0508,Reach-1,5
Up Type=0
Dn Type=3
Dn Slope=0.005
Boundary for River Rch & Prof#=Stream0508,Reach-1,6
Up Type=0
Dn Type=3
Dn Slope=0.005
Boundary for River Rch & Prof#=Stream0508,Reach-1,7
Up Type=0
Dn Type=3
Dn Slope=0.005

--- Stream0508.g01 (geometry) ---

Geom Title=Existing Conditions
Program Version=4.10

River Reach=Stream0508      ,Reach-1
Reach XY= 30
        2500175.       13687525.      2500372.46      13687819.3
      2500474.99     13687867.47      2500839.13     13687888.36
      2500830.13     13688027.28      2501009.53     13688224.99
      2501177.43     13688169.48      2501321.66     13688032.99
      2501378.22     13688066.71      2501599.95     13687974.39
      2501713.05     13688024.16      2502080.93     13687877.24
      2502327.48     13687869.54      2502417.92     13687775.02
      2502327.62     13687633.51       2502504.8     13687444.61
      2502873.75     13687371.55      2503014.48     13687225.46
      2503071.48     13687276.22      2503117.21      13687425.1
      2503083.24     13687478.23      2503173.39     13687668.97
      2503064.53     13687774.07      2502872.41     13687729.97
      2502832.64     13687881.46      2502974.99     13687967.47
      2503373.38     13687878.12      2503469.48     13687972.56
      2503501.04      13688102.2        2503675.       13688175.

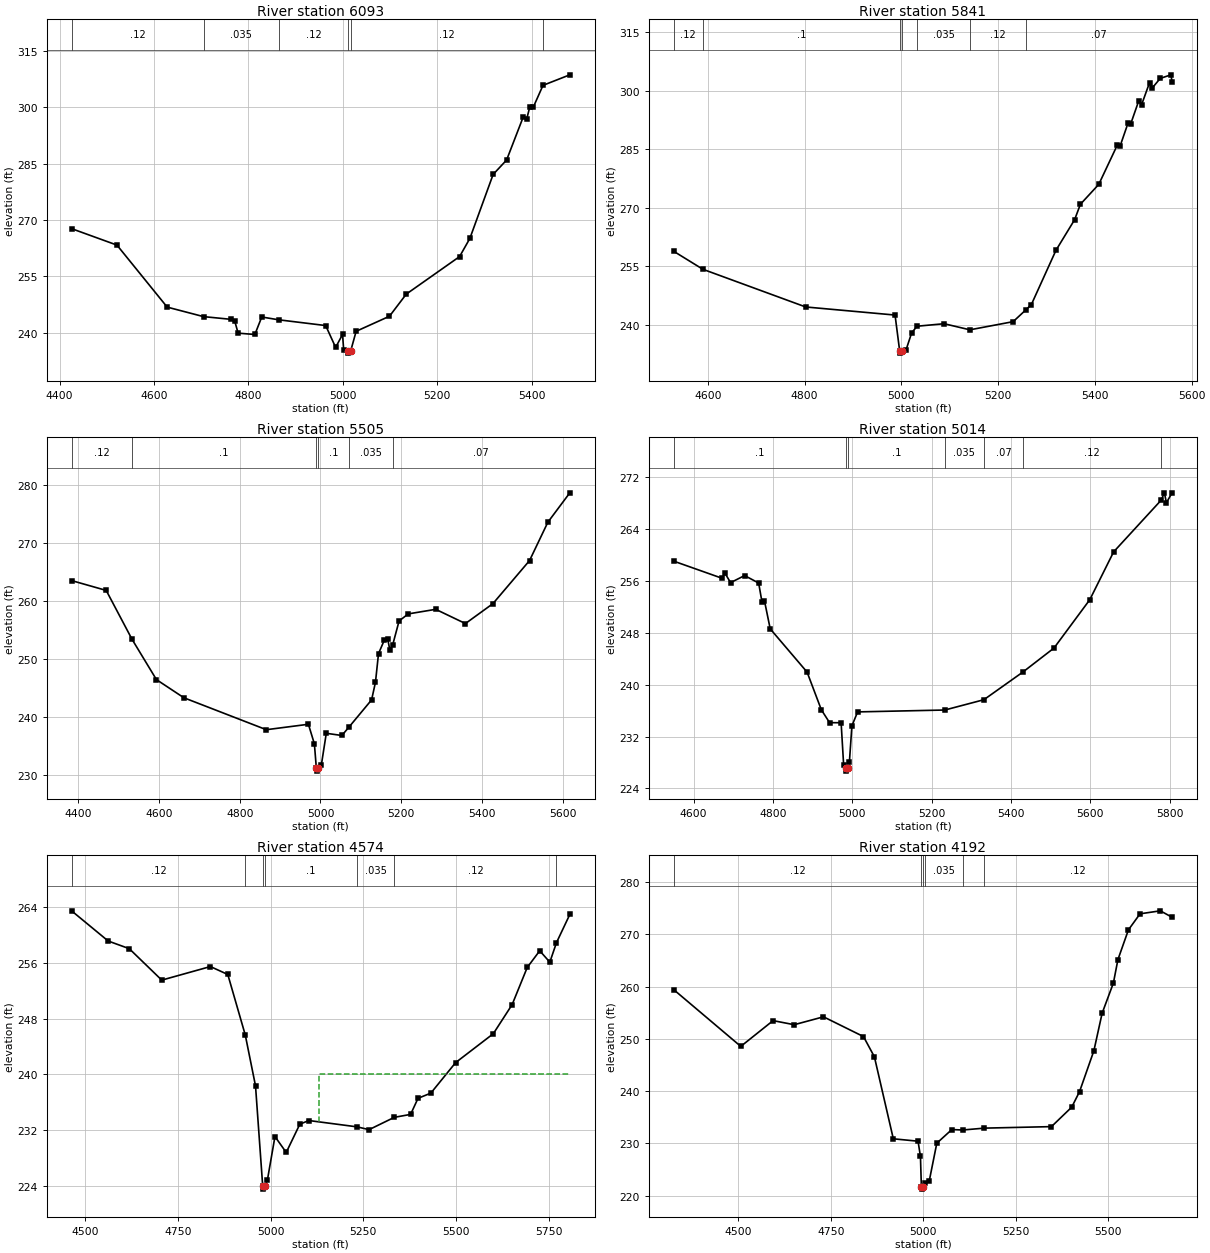
Type RM Length L Ch R = 1 ,6093    ,252,252,252
BEGIN DESCRIPTION:
XS6968
END DESCRIPTION:
XS GIS Cut Line= 3
      2499767.68     13687920.85      2500231.25     13687577.08
      2500547.96     13687218.83
#Sta/Elev= 30
  4425.5  267.66  4521.6  263.28    4628  246.77    4705  244.24  4763.6  243.51
  4770.8  243.18  4778.2  239.84  4813.7  239.48  4828.3  244.14  4864.2  243.39
  4963.7  241.86  4984.8  236.04  4999.4  239.49  5001.8  235.46  5011.5  235.02
  5011.9  234.52  5016.5  235.02  5028.2  240.33  5098.8  244.34  5134.4  250.23
  5247.3  260.22  5269.1  265.06  5318.4   282.1  5346.9  285.93    5382  297.35
  5389.5  296.89  5396.2  300.13  5403.8   300.1    5424  305.81  5480.8  308.61
#Mann= 6 ,-1 , 0
  4425.5     .12       0    4705    .035       0  4864.2     .12       0
  5011.5     .05       0  5016.5     .12       0    5424    .035       0
Bank Sta=5011.5,5016.5
XS Rating Curve= 0 ,0
Exp/Cntr=0.3,0.1

Type RM Length L Ch R = 1 ,5841    ,336,336,336
BEGIN DESCRIPTION:
XS6972
END DESCRIPTION:
XS GIS Cut Line= 3
      2500163.55      13688228.1      2500319.79      13687837.5
      2500600.53     13687296.83
#Sta/Elev= 30
  4529.6  258.85  4589.7  254.26  4802.2  244.61  4986.9  242.54  4996.5  233.29
  4996.9  232.79  5001.5  233.29  5009.4  233.53  5021.1  237.95  5032.3  239.68
  5088.3  240.32  5141.6  238.76    5231  240.85  5257.1  243.85  5268.6  245.21
  5319.5  259.12  5358.1  266.97    5370  270.91    5408  276.01  5446.6  286.15
  5452.2  285.86  5468.7  291.78  5474.3  291.59  5490.8  297.47  5496.4  296.37
  5512.9  302.04  5518.5  300.69    5535  303.14  5557.1  304.06  5559.5  302.33
#Mann= 7 ,-1 , 0
  4529.6     .12       0  4589.7      .1       0  4996.5     .05       0
  5001.5      .1       0  5032.3    .035       0  5141.6     .12       0
  5257.1     .07       0
Bank Sta=4996.5,5001.5
XS Rating Curve= 0 ,0
Exp/Cntr=0.3,0.1

Type RM Length L Ch R = 1 ,5505    ,491,491,491
BEGIN DESCRIPTION:
XS6967
END DESCRIPTION:
XS GIS Cut Line= 2
      2500371.87     13688394.81      2500903.11     13687280.24
#Sta/Elev= 30
  4383.2  263.53    4469  261.83    4533  253.38  4593.5  246.41  4661.6  243.27
  4865.9  237.75  4970.1  238.69  4984.9   235.3  4989.8  231.09  4990.2  230.59
  4994.8  231.09  5002.1  231.63  5014.4  237.13    5053  236.75  5071.5  238.28
  5126.7  242.91  5136.3  245.97  5143.8   250.9  5158.4  253.27  5166.5  253.45
  5172.1  251.47  5179.1  252.45  5194.8  256.55  5217.5  257.77  5285.6  258.56
  5359.2   256.1  5427.3  259.54  5518.1  266.99  5563.5  273.62  5617.9   278.7
#Mann= 6 ,-1 , 0
  4383.2     .12       0    4533      .1       0  4989.8     .05       0
  4994.8      .1       0  5071.5    .035       0  5179.1     .07       0
Bank Sta=4989.8,4994.8
XS Rating Curve= 0 ,0
Exp/Cntr=0.3,0.1

Type RM Length L Ch R = 1 ,5014    ,440,440,440
BEGIN DESCRIPTION:
XS6966
END DESCRIPTION:
XS GIS Cut Line= 3
      2500632.28     13688462.51      2500929.17     13688071.88
      2500981.13     13687308.09
#Sta/Elev= 30
  4550.1  259.07  4672.4  256.42  4678.7  257.25  4693.2  255.76  4728.6  256.85
    4764   255.7  4772.2  252.82  4778.5     253  4793.1  248.63  4886.1  241.95
    4922  236.14  4942.8  234.15  4971.9  234.14  4978.2  227.67  4983.9  227.17
  4984.3  226.67  4988.9  227.17  4992.7  228.03  4999.1  233.66  5013.5  235.81
  5233.3   236.1  5331.8  237.69  5430.4  241.97  5508.7  245.67  5598.9  253.13
    5659  260.51  5778.7  268.48    5787  269.62    5792  268.09  5806.3  269.62
#Mann= 7 ,-1 , 0
  4550.1      .1       0  4983.9     .05       0  4988.9      .1       0
  5233.3    .035       0  5331.8     .07       0  5430.4     .12       0
  5778.7     .07       0
Bank Sta=4983.9,4988.9
XS Rating Curve= 0 ,0
Exp/Cntr=0.3,0.1

Type RM Length L Ch R = 1 ,4574    ,382,382,382
BEGIN DESCRIPTION:
XS6965
END DESCRIPTION:
XS GIS Cut Line= 3
       2501132.3     13688634.33      2501252.08     13688222.92
      2501095.83     13687321.86
#Sta/Elev= 30
  4463.6   263.5  4562.3  259.16  4619.1  258.06  4706.7  253.54  4837.8  255.49
  4884.7  254.35  4931.8  245.65  4959.4  238.34  4978.7     224  4979.1   223.5
  4983.9     224  4991.5  224.82  5011.8  231.06  5042.2  228.77  5078.8  232.83
  5103.1  233.36  5233.2  232.45  5265.5  232.05  5333.6  233.82  5377.4  234.24
  5397.4  236.55    5432   237.3  5498.9  241.69  5600.4  245.84  5651.2  250.03
  5691.8  255.36  5725.5  257.76  5752.7  256.12  5770.6  258.92  5806.6  262.98
#Mann= 7 ,-1 , 0
  4463.6     .12       0  4931.8      .1       0  4978.7     .05       0
  4983.9      .1       0  5233.2    .035       0  5333.6     .12       0
  5770.6     .07       0
#XS Ineff= 2 , 0
       0                    5130       0     240
Permanent Ineff=
       F       F
Bank Sta=4978.7,4983.9
XS Rating Curve= 0 ,0
Exp/Cntr=0.3,0.1

Type RM Length L Ch R = 1 ,4192    ,418,418,418
BEGIN DESCRIPTION:
XS6964
END DESCRIPTION:
XS GIS Cut Line= 3
      2501220.81     13688571.91      2501559.38     13688061.46
       2501434.6     13687338.78
#Sta/Elev= 30
  4326.1  259.39    4507  248.55  4594.2  253.48  4651.3   252.7  4730.4  254.21
  4838.4  250.43  4867.9  246.56    4919  230.87  4985.8  230.41  4992.3   227.5
  4994.8  221.74  4995.2  221.24    5000  221.74  5005.7  222.47  5016.2  222.85
  5036.5  230.03  5077.1  232.64  5106.1  232.55  5164.7  232.91  5346.2   233.2
    5401  236.93  5422.1   239.9  5460.8  247.72    5483  254.88  5513.5  260.68
  5525.7  265.15  5554.1  270.85  5585.5  273.92  5640.3  274.49    5672  273.26
#Mann= 6 ,-1 , 0
  4326.1     .12       0  4994.8     .05       0    5000     .12       0
  5005.7    .035       0  5106.1      .1       0  5164.7     .12       0
Bank Sta=4994.8,5000
XS Rating Curve= 0 ,0
Exp/Cntr=0.3,0.1

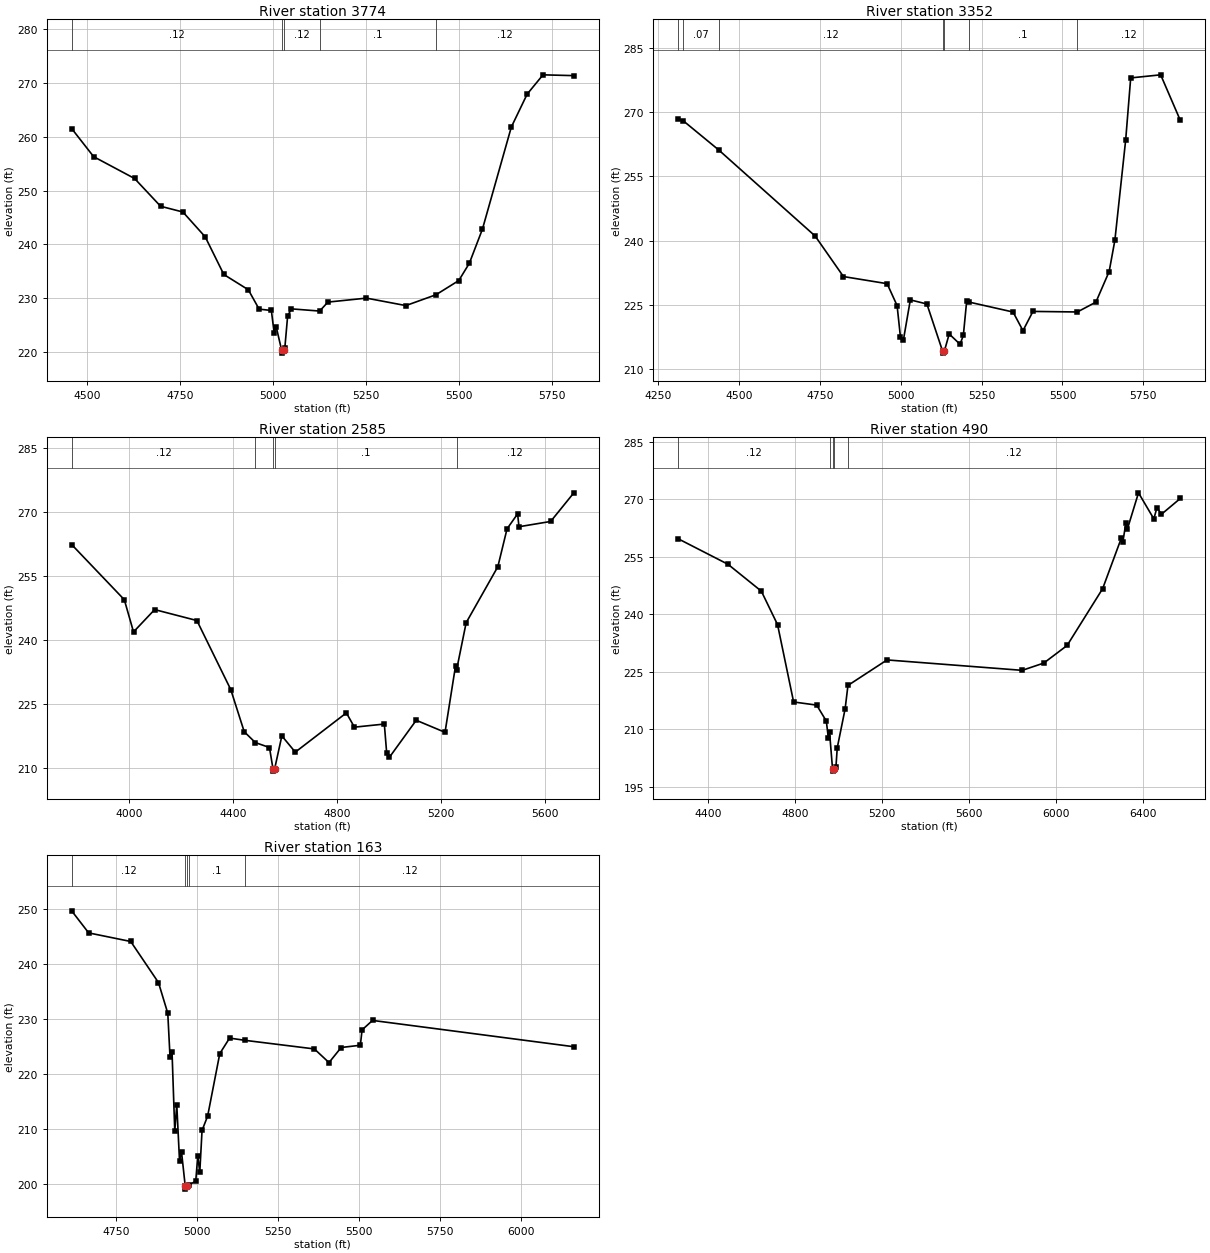
Type RM Length L Ch R = 1 ,3774    ,422,422,422
BEGIN DESCRIPTION:
XS6963
END DESCRIPTION:
XS GIS Cut Line= 4
      2501960.42     13688504.16      2501960.42     13688056.25
      2501731.25     13687545.83      2501476.05     13687316.67
#Sta/Elev= 30
  4459.3  261.55  4518.5  256.31  4628.5  252.25  4698.5  247.08  4758.5  246.01
  4818.5  241.38  4868.5  234.38  4934.3  231.54  4963.4  227.93  4996.3  227.68
  5003.8  223.54  5009.3  224.65  5024.1  220.24  5024.6  219.74  5029.9  220.24
  5032.5  220.67  5040.1  226.65  5050.2  227.98  5126.2  227.57  5148.3  229.24
    5252  229.98    5358  228.59  5439.1  230.61  5500.3  233.25  5528.7  236.47
  5563.9  242.82  5641.6  261.83  5684.2  267.96  5726.8  271.55  5809.7   271.4
#Mann= 5 ,-1 , 0
  4459.3     .12       0  5024.1     .05       0  5029.9     .12       0
  5126.2      .1       0  5439.1     .12       0
Bank Sta=5024.1,5029.9
XS Rating Curve= 0 ,0
Exp/Cntr=0.3,0.1

Type RM Length L Ch R = 1 ,3352    ,767,767,767
BEGIN DESCRIPTION:
XS6962
END DESCRIPTION:
XS GIS Cut Line= 2
      2502460.42     13688545.86      2502127.08     13687030.19
#Sta/Elev= 30
  4312.3  268.38  4328.6  267.91  4437.8  261.13  4735.7  241.06  4823.2   231.6
  4958.2  229.94    4989  224.83  4999.2  217.61  5008.5   216.8  5029.9  226.16
  5081.1   225.2  5129.4  214.24  5129.9  213.74  5135.2  214.24    5150  218.21
  5183.5  215.81  5193.7  217.86    5204  225.87  5210.1  225.67  5347.3  223.33
    5378  218.98  5408.8  223.47    5546  223.34  5603.3  225.63  5644.3  232.77
    5662  240.07  5695.4  263.48  5710.9  277.94  5803.5  278.66  5864.2  268.04
#Mann= 7 ,-1 , 0
  4312.3     .12       0  4328.6     .07       0  4437.8     .12       0
  5129.4     .05       0  5135.2     .12       0  5210.1      .1       0
    5546     .12       0
Bank Sta=5129.4,5135.2
XS Rating Curve= 0 ,0
Exp/Cntr=0.3,0.1

Type RM Length L Ch R = 1 ,2585    ,2095,2095,2095
BEGIN DESCRIPTION:
XS6961
END DESCRIPTION:
XS GIS Cut Line= 2
      2502960.43     13688577.12      2502476.38      13686708.6
#Sta/Elev= 30
  3779.6  262.43    3982  249.48  4017.4  241.92  4098.6  247.16    4261  244.59
  4391.3  228.36  4442.9  218.49  4485.7  215.94    4540  214.78  4553.5  209.74
    4554  209.24  4559.7  209.74  4587.5  217.51  4639.2   213.7  4835.5  222.91
  4866.5  219.56  4981.4  220.29  4990.4  213.53  5000.7  212.47    5104  221.18
  5214.7  218.35  5255.3  234.03  5259.1  232.99  5295.9  244.08  5417.7  257.23
  5453.1  266.12  5493.7  269.63  5498.9  266.61  5620.7  267.85  5709.8  274.57
#Mann= 5 ,-1 , 0
  3779.6     .12       0  4485.7      .1       0  4553.5     .05       0
  4559.7      .1       0  5259.1     .12       0
Bank Sta=4553.5,4559.7
XS Rating Curve= 0 ,0
Exp/Cntr=0.3,0.1

Type RM Length L Ch R = 1 ,490     ,327,327,327
BEGIN DESCRIPTION:
XS6960
END DESCRIPTION:
XS GIS Cut Line= 4
      2503043.75     13688540.64      2503356.25     13687879.17
        2503200.     13687108.33      2502585.41     13686613.54
#Sta/Elev= 30
  4263.8  259.72  4492.9  253.05  4646.1  246.03  4720.6  237.29  4794.4  217.09
  4900.4  216.27  4944.7   212.1  4953.8  207.75  4959.5  209.19  4973.3  199.53
  4973.8  199.03  4979.7  199.53  4988.9  200.16  4994.9  205.13  5031.1  215.31
    5044  221.41  5223.6  228.07  5844.5  225.35  5943.7  227.25  6050.9  231.85
  6214.1  246.68  6300.4  259.95  6306.8  258.82  6321.2  263.95  6327.7  262.23
  6378.8  271.71  6449.2  264.92  6463.6  267.82  6484.4  266.12  6570.9  270.24
#Mann= 5 ,-1 , 0
  4263.8     .12       0  4959.5      .1       0  4973.3     .05       0
  4979.7      .1       0    5044     .12       0
Bank Sta=4973.3,4979.7
XS Rating Curve= 0 ,0
Exp/Cntr=0.3,0.1

Type RM Length L Ch R = 1 ,163     ,0,0,0
BEGIN DESCRIPTION:
E21119
END DESCRIPTION:
XS GIS Cut Line= 4
      2503301.35     13688435.68      2503538.26     13688108.38
      2503585.02      13687737.4      2503351.45     13686999.33
#Sta/Elev= 30
  4612.6  249.59  4665.2  245.58  4795.2  244.02    4881  236.55  4909.7  230.98
  4916.6  223.06  4922.8  224.03  4931.3  209.57  4937.5  214.37    4946  204.15
  4952.2  205.79  4963.7  199.53  4964.2  199.03  4970.1  199.53  4974.8  199.83
  4996.1  200.44  5002.4  205.08  5008.6  202.08  5015.6  209.69  5032.9   212.3
  5070.4  223.65  5100.7  226.47  5149.9  226.05  5362.7   224.5    5408  222.02
  5445.6  224.76  5504.9  225.17  5510.2  227.96  5542.5  229.68  6164.7   224.9
#Mann= 5 ,-1 , 0
  4612.6     .12       0  4963.7     .05       0  4970.1     .12       0
  4974.8      .1       0  5149.9     .12       0
Bank Sta=4963.7,4970.1
XS Rating Curve= 0 ,0
Exp/Cntr=0.3,0.1

Chan Stop Cuts=-1
Use User Specified Reach Order=0
Composite Channel Slope=5