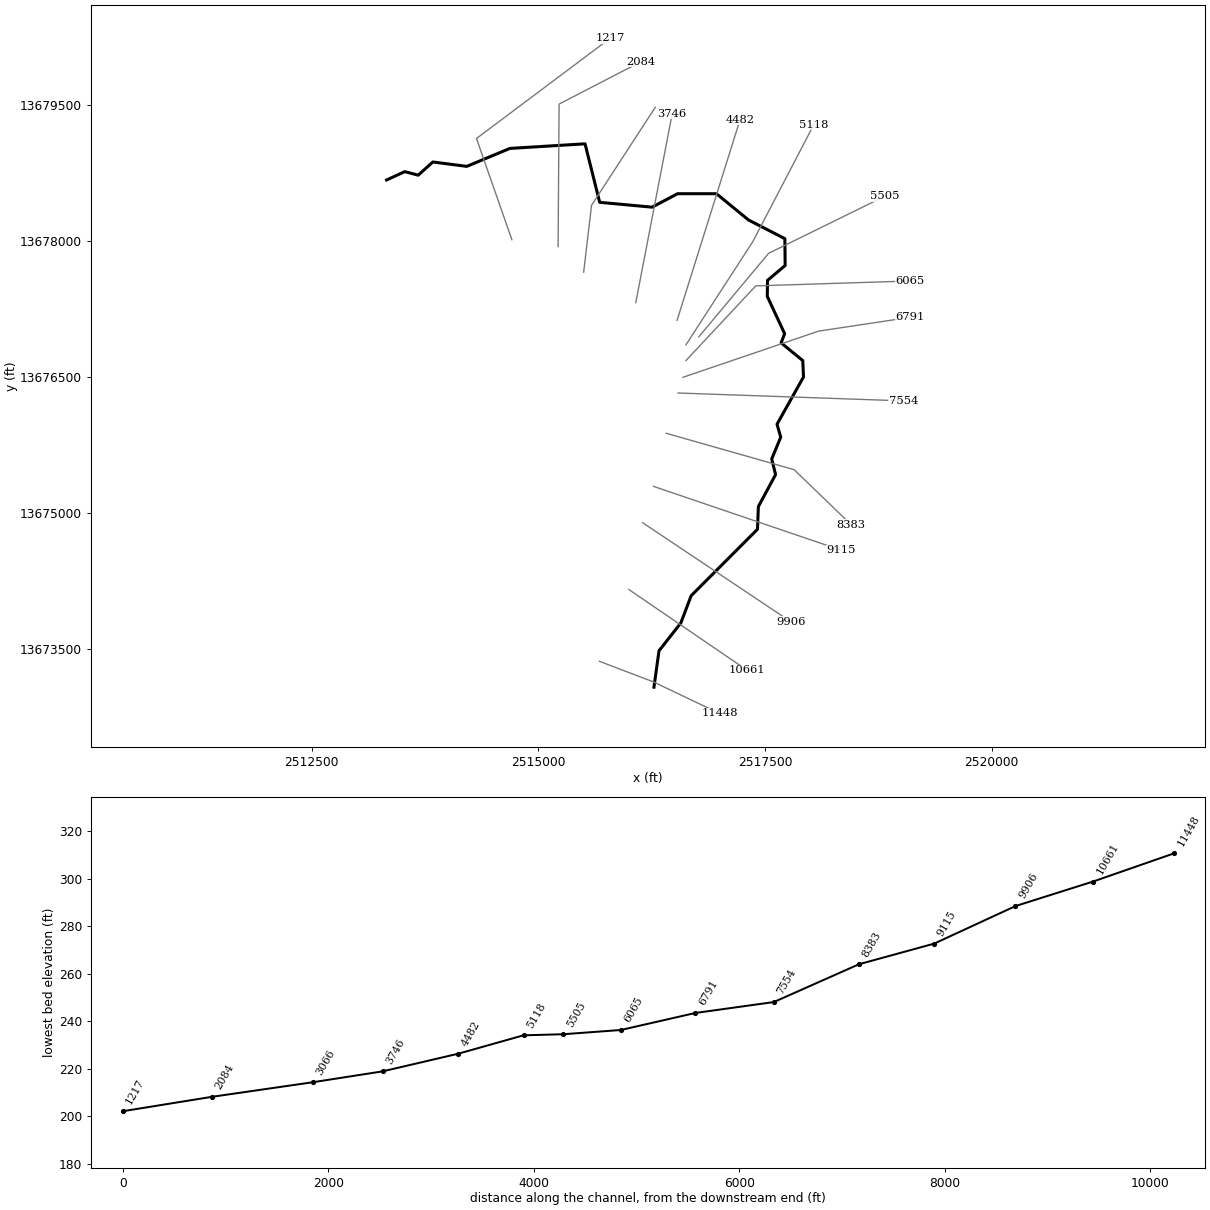
--- Stream0510.prj (project) ---

Proj Title=Stream0510 Base Level Engineering
Current Plan=p01
Default Exp/Contr=0.3,0.1
English Units
Geom File=g01
Flow File=f01
Plan File=p01
BEGIN DESCRIPTION:
Stream0510
END DESCRIPTION:

--- Stream0510.p01 (plan) ---

Plan Title=Multiple Run
Short Identifier=Multiple
Geom File=g01
Flow File=f01
Subcritical Flow
K Sum by GR= 0
Std Step Tol= 0.01
Critical Tol= 0.01
Num of Std Step Trials= 20
Max Error Tol= 0.3
Flow Tol Ratio= 0.001
Split Flow NTrial= 30
Split Flow Tol= 0.02
Split Flow Ratio= 0.02
Log Output Level= 0
Friction Slope Method= 1
Unsteady Friction Slope Method= 2
Unsteady Bridges Friction Slope Method= 1
Parabolic Critical Depth
Global Vel Dist=  1 , 1 , 1
Global Log Level= 0
CheckData=True
Encroach Param= -1, 0, 0, 0
BEGIN DESCRIPTION:
Multiple Run
END DESCRIPTION:

--- Stream0510.f01 (steady flow) ---

Flow Title=Multiple
Number of Profiles=7
Profile Names=10-year,25-year,50-year,1pct_min,100-year,1pct_plu,500-year
River Rch & RM= Stream0510,Reach-1,11448
     524     837    1119     727    1451    2895    2410
River Rch & RM= Stream0510,Reach-1,7554
    1392    2346    3248    2175    4340    8660    7676
Boundary for River Rch & Prof#=Stream0510,Reach-1,1
Up Type=0
Dn Type=3
Dn Slope=0.005
Boundary for River Rch & Prof#=Stream0510,Reach-1,2
Up Type=0
Dn Type=3
Dn Slope=0.005
Boundary for River Rch & Prof#=Stream0510,Reach-1,3
Up Type=0
Dn Type=3
Dn Slope=0.005
Boundary for River Rch & Prof#=Stream0510,Reach-1,4
Up Type=0
Dn Type=3
Dn Slope=0.005
Boundary for River Rch & Prof#=Stream0510,Reach-1,5
Up Type=0
Dn Type=3
Dn Slope=0.005
Boundary for River Rch & Prof#=Stream0510,Reach-1,6
Up Type=0
Dn Type=3
Dn Slope=0.005
Boundary for River Rch & Prof#=Stream0510,Reach-1,7
Up Type=0
Dn Type=3
Dn Slope=0.005

--- Stream0510.g01 (geometry) ---

Geom Title=Existing Conditions

River Reach=Stream0510,Reach-1
Reach XY= 30
      2516275.00     13673075.00      2516330.84     13673477.29
      2516571.46     13673783.49      2516685.51     13674084.81
      2517417.50     13674818.95      2517427.15     13675069.10
      2517616.92     13675421.70      2517574.61     13675595.13
      2517673.89     13675835.55      2517633.05     13675978.32
      2517925.21     13676499.91      2517917.20     13676681.21
      2517678.15     13676876.64      2517716.93     13676978.31
      2517525.52     13677390.22      2517528.06     13677566.72
      2517722.77     13677730.90      2517719.55     13678027.47
      2517318.93     13678233.14      2516964.50     13678523.80
      2516535.50     13678523.80      2516254.97     13678375.06
      2515676.22     13678428.44      2515514.53     13679074.43
      2514685.50     13679023.78      2514209.78     13678825.49
      2513835.43     13678873.95      2513673.50     13678728.46
      2513525.00     13678767.44      2513325.00     13678675.00

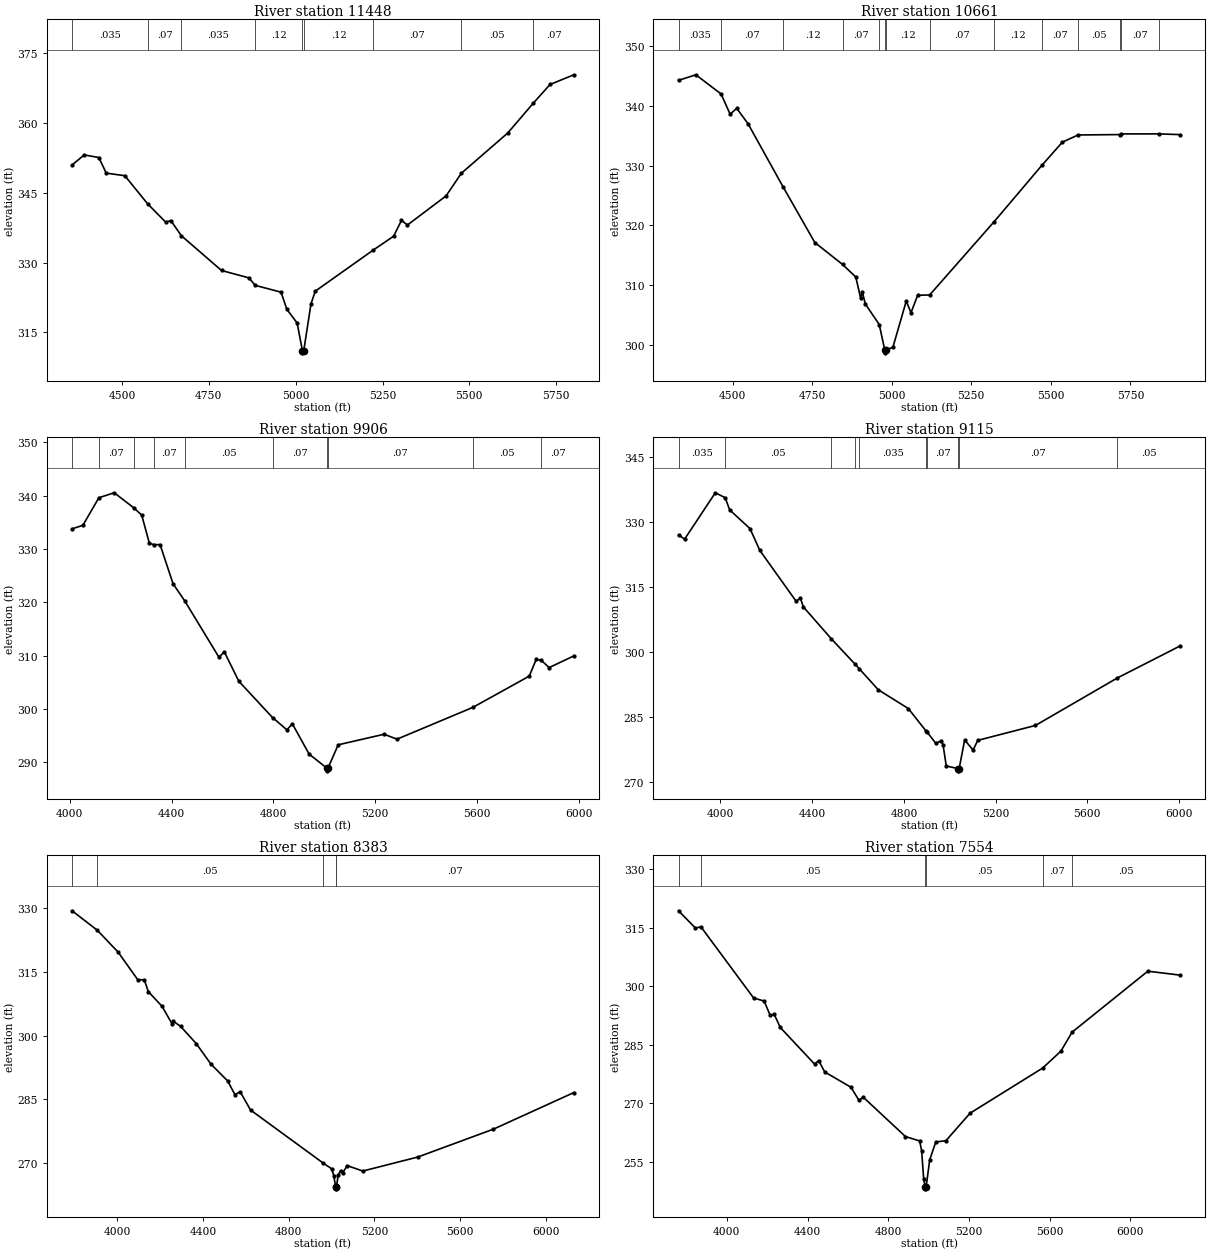
Type RM Length L Ch R = 1,11448,787,787,787
BEGIN DESCRIPTION:
XS6986
END DESCRIPTION:
XS GIS Cut Line= 3
      2515673.11     13673360.84      2516269.88     13673132.99
      2516996.92     13672785.74
#Sta/Elev= 30
  4356.3  351.02  4391.2  353.17  4433.3  352.62  4454.7  349.26  4508.2  348.70
  4573.5  342.68  4625.9  338.70  4640.5  339.06  4670.9  335.79  4786.5  328.31
  4865.0  326.73  4883.9  325.10  4957.8  323.65  4974.6  319.95  5004.2  317.01
  5019.3  311.09  5019.6  310.59  5023.3  311.09  5044.0  321.09  5056.2  323.85
  5223.4  332.71  5281.9  335.68  5304.6  339.10  5321.7  338.09  5433.0  344.36
  5476.8  349.22  5610.6  357.90  5683.9  364.30  5732.2  368.33  5800.8  370.42
#Mann=9,-1,0
  4356.3   0.035       0  4573.5    0.07       0  4670.9   0.035       0
  4883.9    0.12       0  5019.3    0.05       0  5023.3    0.12       0
  5223.4    0.07       0  5476.8    0.05       0  5683.9    0.07       0
Bank Sta=5019.3,5023.3
Exp/Cntr=0.3,0.1

Type RM Length L Ch R = 1,10661,755,755,755
BEGIN DESCRIPTION:
XS6985
END DESCRIPTION:
XS GIS Cut Line= 2
      2515998.61     13674152.96      2517299.99     13673263.68
#Sta/Elev= 30
  4330.4  344.23  4384.7  345.16  4464.1  341.95  4492.4  338.58  4513.3  339.56
  4549.2  336.94  4659.2  326.41  4758.5  317.16  4845.7  313.49  4887.2  311.40
  4902.1  307.95  4908.1  308.82  4917.0  306.91  4960.8  303.47  4978.1  299.24
  4978.3  298.74  4982.1  299.24  5003.7  299.65  5045.7  307.39  5060.6  305.43
  5081.5  308.35  5119.2  308.40  5320.2  320.54  5471.7  330.04  5536.0  333.91
  5585.4  335.11  5718.3  335.18  5721.7  335.29  5839.9  335.29  5906.6  335.17
#Mann=14,-1,0
  4330.4   0.035       0  4464.1    0.07       0  4659.2    0.12       0
  4845.7    0.07       0  4960.8    0.12       0  4978.1    0.05       0
  4982.1    0.12       0  5119.2    0.07       0  5320.2    0.12       0
  5471.7    0.07       0  5585.4    0.05       0  5718.3    0.12       0
  5721.7    0.07       0  5839.9    0.12       0
Bank Sta=4978.1,4982.1
Exp/Cntr=0.3,0.1

Type RM Length L Ch R = 1,9906,791,791,791
BEGIN DESCRIPTION:
XS6984
END DESCRIPTION:
XS GIS Cut Line= 2
      2516150.52     13674890.80      2517788.99     13673794.87
#Sta/Elev= 30
  4008.8  333.80  4051.3  334.46  4114.0  339.63  4174.4  340.56  4250.9  337.75
  4282.5  336.37  4312.5  331.08  4330.4  330.83  4354.5  330.84  4405.6  323.49
  4451.1  320.31  4585.7  309.73  4606.8  310.74  4663.9  305.22  4796.3  298.41
  4853.0  296.10  4874.0  297.25  4940.0  291.56  5010.1  288.92  5010.4  288.42
  5014.1  288.92  5054.2  293.30  5234.3  295.28  5285.4  294.36  5583.3  300.32
  5804.8  306.18  5831.9  309.30  5851.4  309.17  5882.9  307.78  5980.0  309.97
#Mann=10,-1,0
  4008.8   0.035       0  4114.0    0.07       0  4250.9   0.035       0
  4330.4    0.07       0  4451.1    0.05       0  4796.3    0.07       0
  5010.1    0.05       0  5014.1    0.07       0  5583.3    0.05       0
  5851.4    0.07       0
Bank Sta=5010.1,5014.1
Exp/Cntr=0.3,0.1

Type RM Length L Ch R = 1,9115,732,732,732
BEGIN DESCRIPTION:
XS6983
END DESCRIPTION:
XS GIS Cut Line= 2
      2516269.89     13675292.27      2518341.14     13674587.39
#Sta/Elev= 30
  3817.4  327.05  3843.9  326.06  3977.8  336.76  4020.7  335.63  4040.5  332.80
  4129.1  328.49  4171.4  323.50  4329.8  311.75  4348.9  312.45  4361.5  310.44
  4482.6  303.13  4587.5  297.19  4604.9  296.19  4688.6  291.30  4819.4  286.98
  4897.0  281.77  4902.4  281.47  4939.5  278.93  4963.6  279.59  4970.9  278.59
  4984.7  273.74  5036.9  273.11  5037.2  272.61  5040.9  273.11  5065.0  279.73
  5101.6  277.40  5122.1  279.64  5373.4  283.08  5731.2  294.05  6005.3  301.45
#Mann=10,-1,0
  3817.4   0.035       0  4020.7    0.05       0  4482.6   0.035       0
  4587.5    0.05       0  4604.9   0.035       0  4897.0    0.05       0
  4902.4    0.07       0  5036.9    0.05       0  5040.9    0.07       0
  5731.2    0.05       0
Bank Sta=5036.9,5040.9
Exp/Cntr=0.3,0.1

Type RM Length L Ch R = 1,8383,829,829,829
BEGIN DESCRIPTION:
XS6982
END DESCRIPTION:
XS GIS Cut Line= 3
      2516410.92     13675878.22      2517821.53     13675476.74
      2518449.97     13674869.96
#Sta/Elev= 30
  3790.1  329.41  3907.7  324.83  4005.1  319.66  4095.9  313.21  4127.1  313.12
  4145.8  310.37  4210.2  306.88  4257.8  302.66  4263.0  303.39  4296.8  302.16
  4369.7  298.11  4437.5  293.31  4515.6  289.35  4549.4  286.13  4574.1  286.79
  4622.4  282.49  4962.5  269.95  5000.4  268.67  5010.8  267.05  5018.8  264.43
  5019.1  263.93  5022.8  264.43  5031.6  267.16  5042.0  268.20  5052.4  267.69
  5073.2  269.40  5146.0  268.12  5401.8  271.41  5755.5  277.99  6130.3  286.60
#Mann=5,-1,0
  3790.1   0.035       0  3907.7    0.05       0  4962.5    0.07       0
  5018.8    0.05       0  5022.8    0.07       0
Bank Sta=5018.8,5022.8
Exp/Cntr=0.3,0.1

Type RM Length L Ch R = 1,7554,763,763,763
BEGIN DESCRIPTION:
XS6981
END DESCRIPTION:
XS GIS Cut Line= 2
      2516541.12     13676323.09      2519026.00     13676236.28
#Sta/Elev= 30
  3760.8  319.29  3844.5  314.86  3871.7  315.18  4132.8  296.93  4184.9  296.15
  4215.0  292.48  4235.0  292.75  4265.0  289.37  4435.1  279.98  4455.1  280.90
  4485.1  277.98  4615.2  274.05  4655.2  270.67  4675.2  271.54  4885.4  261.41
  4955.4  260.29  4965.4  257.81  4975.4  250.61  4983.2  248.51  4983.5  248.01
  4987.7  248.51  5005.4  255.44  5035.5  260.04  5085.5  260.34  5205.6  267.41
  5565.3  278.98  5655.8  283.32  5710.6  288.16  6086.1  303.80  6247.2  302.79
#Mann=6,-1,0
  3760.8   0.035       0  3871.7    0.05       0  4983.2    0.05       0
  4987.7    0.05       0  5565.3    0.07       0  5710.6    0.05       0
Bank Sta=4983.2,4987.7
Exp/Cntr=0.3,0.1

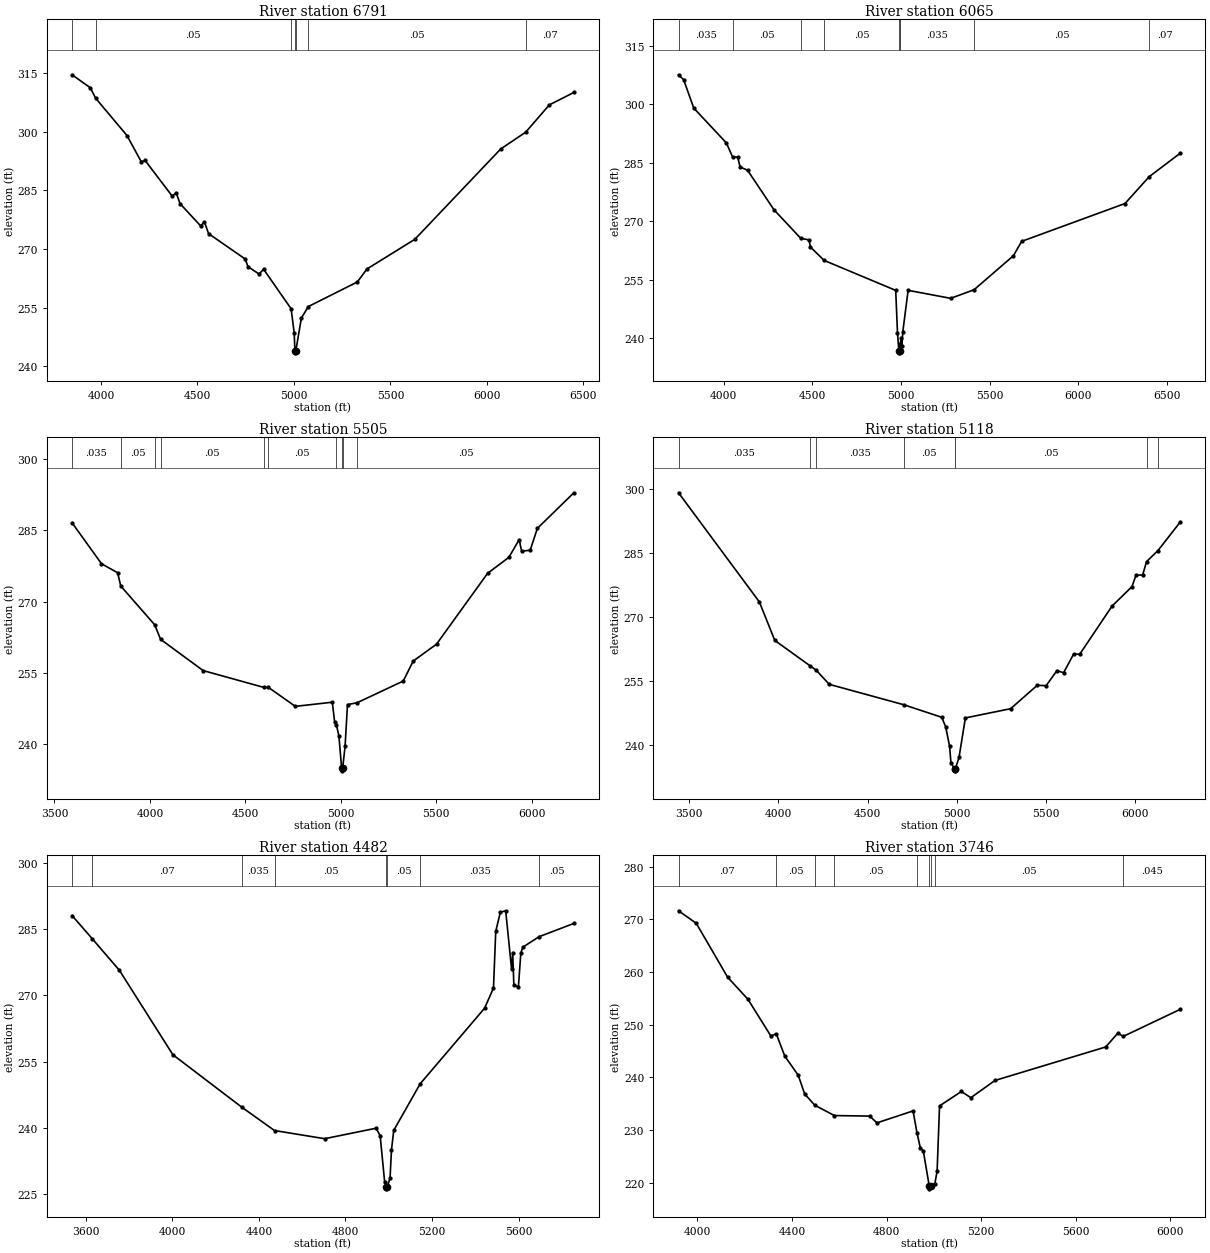
Type RM Length L Ch R = 1,6791,726,726,726
BEGIN DESCRIPTION:
XS6980
END DESCRIPTION:
XS GIS Cut Line= 3
      2516595.36     13676496.69      2518092.80     13677006.68
      2519100.05     13677158.31
#Sta/Elev= 30
  3850.3  314.56  3945.0  311.24  3972.0  308.59  4134.8  299.02  4209.1  292.29
  4228.9  292.64  4367.6  283.62  4390.9  284.23  4409.8  281.60  4516.3  275.91
  4536.6  276.89  4557.7  273.92  4747.9  267.41  4761.9  265.47  4819.3  263.59
  4842.9  264.80  4985.6  254.69  5001.4  248.51  5005.2  243.92  5005.5  243.42
  5009.8  243.92  5038.8  252.34  5074.8  255.26  5328.9  261.56  5378.4  264.87
  5626.6  272.46  6071.5  295.57  6201.4  299.88  6323.5  306.85  6450.8  310.04
#Mann=7,-1,0
  3850.3   0.035       0  3972.0    0.05       0  4985.6    0.07       0
  5005.2    0.05       0  5009.8    0.07       0  5074.8    0.05       0
  6201.4    0.07       0
Bank Sta=5005.2,5009.8
Exp/Cntr=0.3,0.1

Type RM Length L Ch R = 1,6065,560,560,560
BEGIN DESCRIPTION:
XS6979
END DESCRIPTION:
XS GIS Cut Line= 3
      2516627.96     13676681.18      2517398.35     13677505.82
      2519099.88     13677560.00
#Sta/Elev= 30
  3745.2  307.52  3774.2  306.24  3830.9  298.99  4014.6  290.08  4051.1  286.38
  4078.6  286.46  4092.6  283.89  4134.7  283.05  4283.7  272.92  4434.6  265.60
  4481.6  265.20  4488.9  263.39  4566.6  259.94  4970.4  252.26  4980.4  241.46
  4988.1  236.75  4988.4  236.25  4992.7  236.75  4996.8  238.48  5000.3  239.96
  5005.3  238.06  5010.4  241.64  5040.4  252.27  5280.6  250.22  5412.3  252.42
  5634.6  261.14  5680.8  264.82  6263.9  274.52  6400.6  281.40  6576.1  287.44
#Mann=9,-1,0
  3745.2   0.035       0  4051.1    0.05       0  4434.6   0.035       0
  4566.6    0.05       0  4988.1   0.035       0  4992.7    0.05       0
  4996.8   0.035       0  5412.3    0.05       0  6400.6    0.07       0
Bank Sta=4988.1,4992.7
Exp/Cntr=0.3,0.1

Type RM Length L Ch R = 1,5505,387,387,387
BEGIN DESCRIPTION:
E21121
END DESCRIPTION:
XS GIS Cut Line= 3
      2516769.98     13676943.25      2517540.40     13677865.59
      2518820.37     13678494.72
#Sta/Elev= 30
  3592.2  286.52  3746.3  277.93  3830.9  276.04  3847.1  273.26  4024.6  265.13
  4056.1  262.06  4278.6  255.51  4597.2  251.97  4619.8  252.00  4761.4  248.00
  4955.1  248.87  4967.2  244.75  4976.9  244.07  4989.7  241.78  5004.1  234.97
  5004.5  234.47  5009.1  234.97  5022.0  239.61  5034.7  248.37  5085.1  248.76
  5326.9  253.32  5378.5  257.49  5501.1  261.06  5768.5  275.92  5879.9  279.27
  5933.8  282.99  5946.8  280.56  5991.4  280.77  6029.2  285.36  6220.2  292.82
#Mann=10,-1,0
  3592.2   0.035       0  3847.1    0.05       0  4024.6   0.035       0
  4056.1    0.05       0  4597.2   0.035       0  4619.8    0.05       0
  4976.9    0.12       0  5004.1    0.05       0  5009.1    0.12       0
  5085.1    0.05       0
Bank Sta=5004.1,5009.1
Exp/Cntr=0.3,0.1

Type RM Length L Ch R = 1,5118,636,636,636
BEGIN DESCRIPTION:
XS6978
END DESCRIPTION:
XS GIS Cut Line= 3
      2516627.95     13676854.76      2517365.80     13677994.10
      2518038.56     13679285.36
#Sta/Elev= 30
  3439.7  299.01  3892.7  273.51  3979.5  264.49  4177.4  258.56  4210.3  257.59
  4284.8  254.23  4701.9  249.47  4915.4  246.53  4937.5  244.31  4959.6  239.70
  4967.2  235.79  4987.2  234.51  4987.6  234.01  4992.3  234.51  5012.3  237.15
  5048.0  246.38  5301.9  248.54  5451.0  254.01  5500.8  253.91  5561.4  257.45
  5598.7  256.94  5655.5  261.35  5688.4  261.23  5870.8  272.55  5982.1  277.07
  6004.6  279.74  6041.9  279.80  6063.6  282.91  6127.6  285.50  6253.1  292.20
#Mann=8,-1,0
  3439.7   0.035       0  4177.4    0.05       0  4210.3   0.035       0
  4701.9    0.05       0  4987.2    0.05       0  4992.3    0.05       0
  6063.6   0.035       0  6127.6    0.05       0
Bank Sta=4987.2,4992.3
Exp/Cntr=0.3,0.1

Type RM Length L Ch R = 1,4482,736,736,736
BEGIN DESCRIPTION:
XS6977
END DESCRIPTION:
XS GIS Cut Line= 2
      2516530.29     13677126.02      2517224.73     13679339.54
#Sta/Elev= 30
  3536.0  288.08  3629.4  282.83  3755.0  275.68  4002.0  256.60  4320.6  244.73
  4471.9  239.45  4703.9  237.60  4941.3  239.97  4960.3  238.31  4981.3  227.74
  4989.1  226.76  4989.5  226.26  4994.3  226.76  5006.2  228.80  5012.7  235.05
  5023.2  239.49  5145.5  250.03  5443.4  267.13  5484.3  271.70  5494.8  284.50
  5515.8  288.82  5540.7  289.16  5567.9  275.99  5573.1  279.72  5578.6  272.26
  5599.6  272.00  5610.8  279.65  5620.6  280.94  5694.7  283.29  5855.9  286.30
#Mann=8,-1,0
  3536.0    0.05       0  3629.4    0.07       0  4320.6   0.035       0
  4471.9    0.05       0  4989.1    0.05       0  4994.3    0.05       0
  5145.5   0.035       0  5694.7    0.05       0
Bank Sta=4989.1,4994.3
Exp/Cntr=0.3,0.1

Type RM Length L Ch R = 1,3746,680,680,680
BEGIN DESCRIPTION:
XS6976
END DESCRIPTION:
XS GIS Cut Line= 2
      2516074.56     13677321.31      2516476.04     13679404.68
#Sta/Elev= 30
  3920.1  271.61  3995.1  269.23  4127.5  259.01  4213.6  254.81  4310.8  247.82
  4333.2  248.30  4369.2  244.03  4426.2  240.40  4453.4  236.84  4496.6  234.69
  4579.2  232.74  4728.4  232.64  4758.9  231.35  4911.7  233.62  4928.3  229.47
  4942.3  226.64  4955.2  225.99  4980.3  219.33  4980.8  218.83  4985.6  219.33
  5004.1  219.84  5013.5  222.24  5023.7  234.57  5116.0  237.31  5156.1  236.13
  5258.0  239.40  5726.4  245.76  5777.3  248.37  5800.8  247.77  6041.8  252.91
#Mann=9,-1,0
  3920.1    0.07       0  4333.2    0.05       0  4496.6   0.035       0
  4579.2    0.05       0  4928.3    0.12       0  4980.3    0.05       0
  4985.6    0.12       0  5004.1    0.05       0  5800.8   0.045       0
Bank Sta=4980.3,4985.6
Exp/Cntr=0.3,0.1

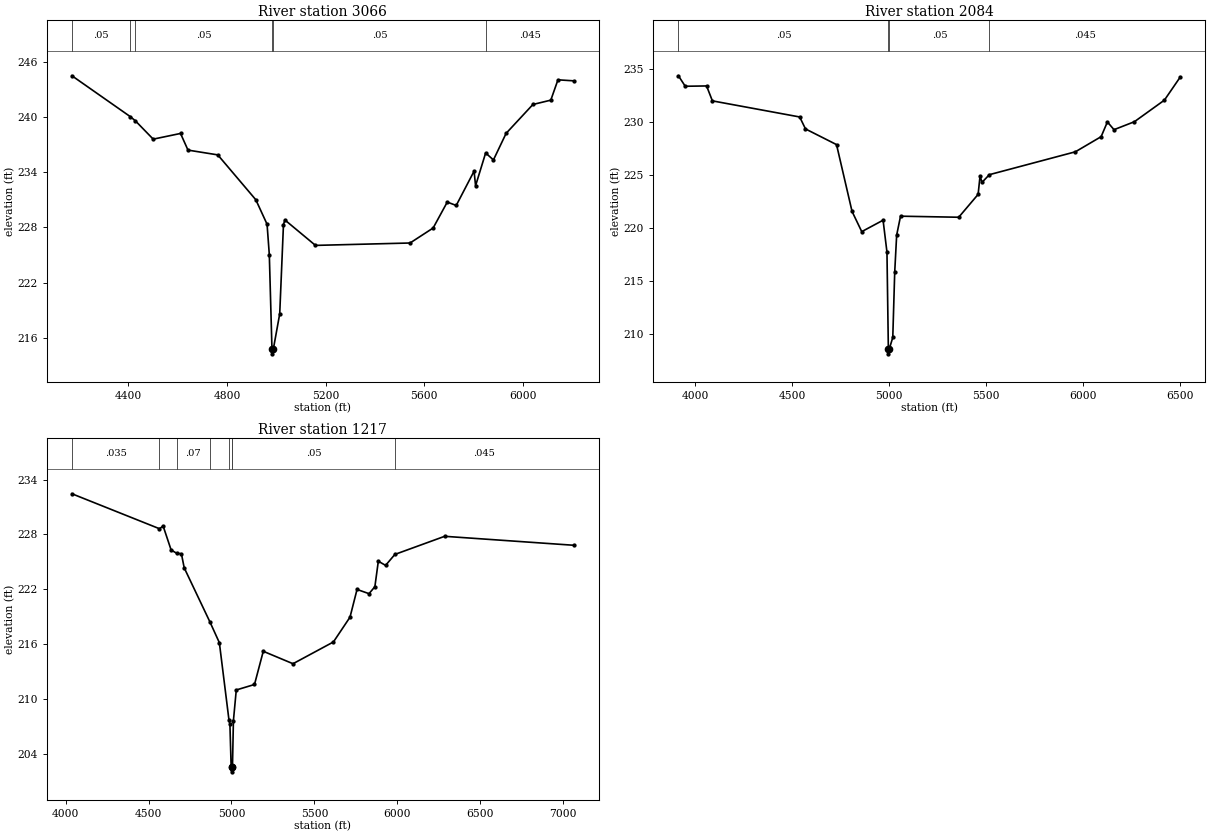
Type RM Length L Ch R = 1,3066,982,982,982
BEGIN DESCRIPTION:
XS6975
END DESCRIPTION:
XS GIS Cut Line= 3
      2515499.48     13677657.75      2515586.28     13678395.57
      2516290.56     13679479.08
#Sta/Elev= 30
  4171.0  244.48  4408.0  240.03  4428.3  239.58  4500.5  237.59  4611.3  238.21
  4641.5  236.40  4762.3  235.88  4916.6  231.00  4962.2  228.34  4971.3  225.03
  4982.1  214.75  4982.5  214.25  4987.5  214.75  5013.5  218.60  5028.7  228.31
  5034.6  228.80  5158.5  226.04  5542.0  226.30  5635.6  227.93  5692.9  230.75
  5729.2  230.38  5801.6  234.11  5807.7  232.53  5848.5  236.09  5880.1  235.33
  5931.5  238.22  6040.2  241.36  6112.7  241.83  6141.7  244.04  6206.2  243.93
#Mann=6,-1,0
  4171.0    0.05       0  4408.0   0.035       0  4428.3    0.05       0
  4982.1    0.05       0  4987.5    0.05       0  5848.5   0.045       0
Bank Sta=4982.1,4987.5
Exp/Cntr=0.3,0.1

Type RM Length L Ch R = 1,2084,867,867,867
BEGIN DESCRIPTION:
XS6974
END DESCRIPTION:
XS GIS Cut Line= 3
      2515217.36     13677939.84      2515228.21     13679513.19
      2516128.83     13679979.78
#Sta/Elev= 30
  3914.9  234.37  3950.1  233.38  4060.1  233.41  4090.1  232.00  4540.1  230.48
  4570.1  229.35  4730.1  227.87  4810.1  221.56  4860.1  219.65  4970.1  220.73
  4990.1  217.72  4997.3  208.61  4997.8  208.11  5002.8  208.61  5020.1  209.66
  5030.1  215.83  5040.1  219.32  5060.1  221.11  5360.1  221.01  5460.1  223.17
  5470.1  224.91  5480.1  224.30  5518.0  225.03  5961.5  227.19  6094.3  228.62
  6126.6  230.01  6160.7  229.28  6265.7  230.03  6420.6  232.07  6502.6  234.26
#Mann=4,-1,0
  3914.9    0.05       0  4997.3    0.05       0  5002.8    0.05       0
  5518.0   0.045       0
Bank Sta=4997.3,5002.8
Exp/Cntr=0.3,0.1

Type RM Length L Ch R = 1,1217,0,0,0
BEGIN DESCRIPTION:
XS6973
END DESCRIPTION:
XS GIS Cut Line= 3
      2514707.39     13678015.77      2514316.75     13679133.42
      2515791.12     13680239.19
#Sta/Elev= 30
  4037.9  232.45  4565.7  228.63  4587.9  228.92  4635.9  226.31  4669.0  225.95
  4698.0  225.89  4715.0  224.35  4870.5  218.42  4926.9  216.17  4985.1  207.68
  4990.5  207.30  4997.8  202.72  5000.3  202.55  5000.8  202.05  5005.9  202.55
  5011.7  207.65  5028.9  211.00  5138.8  211.60  5191.7  215.23  5371.0  213.87
  5614.8  216.25  5714.8  218.96  5757.2  221.99  5829.4  221.53  5864.8  222.29
  5885.6  225.08  5929.4  224.62  5985.4  225.82  6285.6  227.80  7064.8  226.82
#Mann=8,-1,0
  4037.9   0.035       0  4565.7    0.05       0  4669.0    0.07       0
  4870.5     0.1       0  4985.1    0.05       0  5000.3    0.05       0
  5005.9    0.05       0  5985.4   0.045       0
Bank Sta=5000.3,5005.9
Exp/Cntr=0.3,0.1

Chan Stop Cuts=-1