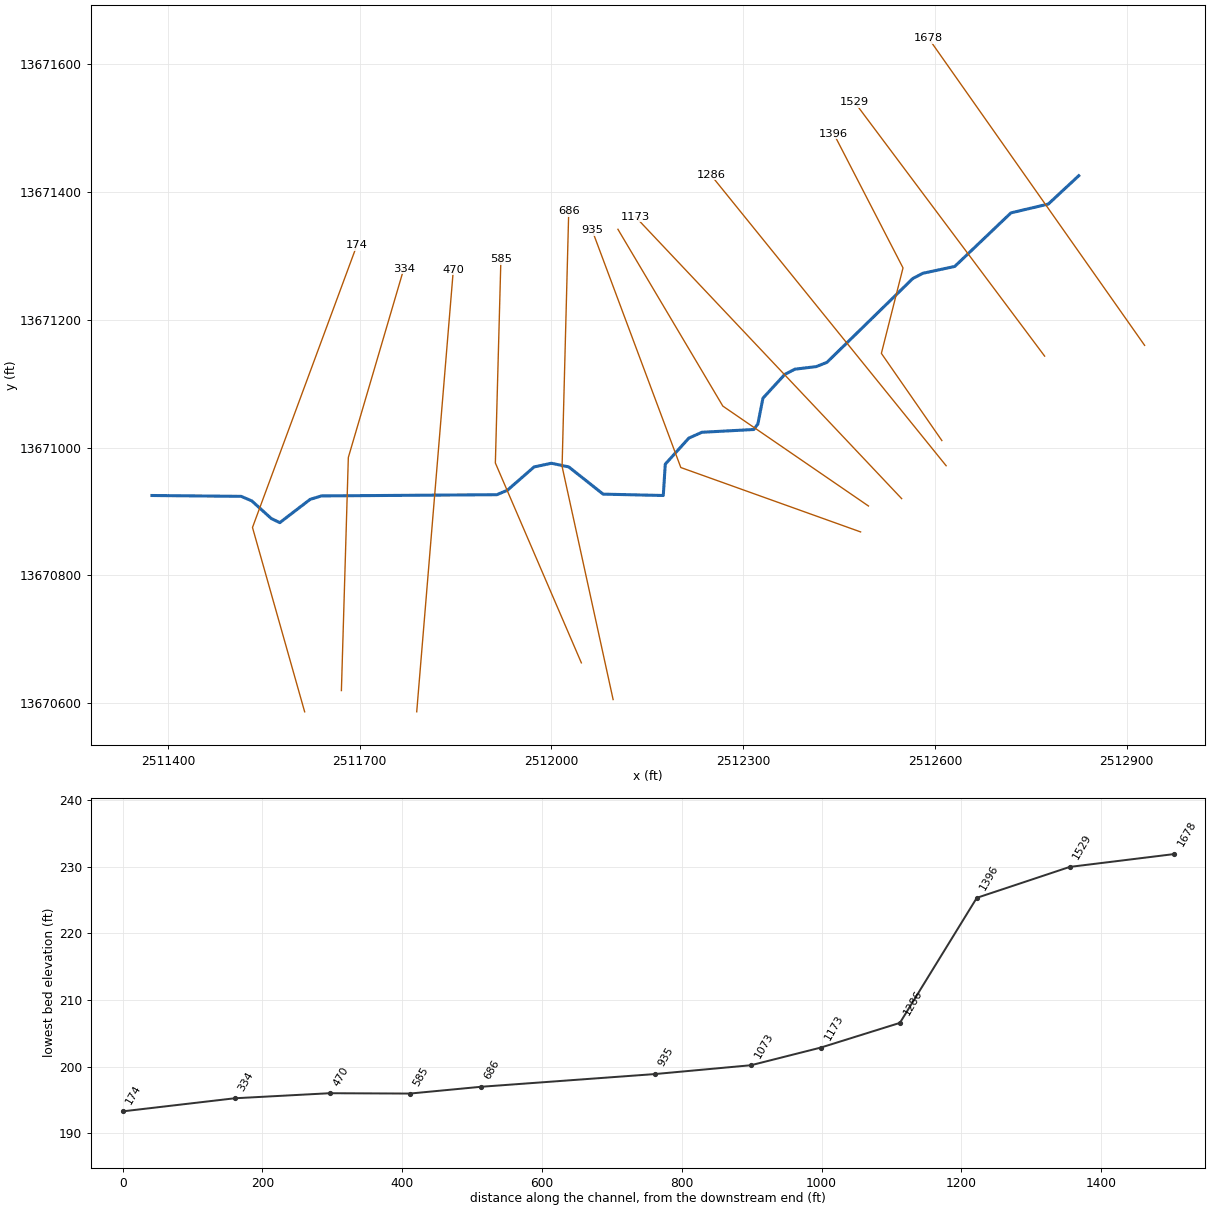
--- Stream0511.prj (project) ---

Proj Title=Stream0511 Base Level Engineering
Current Plan=p01
Default Exp/Contr=0.3,0.1
English Units
Geom File=g01
Flow File=f01
Plan File=p01
BEGIN DESCRIPTION:
Stream0511
END DESCRIPTION:

--- Stream0511.p01 (plan) ---

Plan Title=Multiple Run
Short Identifier=Multiple
Geom File=g01
Flow File=f01
Subcritical Flow
K Sum by GR= 0
Std Step Tol= 0.01
Critical Tol= 0.01
Num of Std Step Trials= 20
Max Error Tol= 0.3
Flow Tol Ratio= 0.001
Split Flow NTrial= 30
Split Flow Tol= 0.02
Split Flow Ratio= 0.02
Log Output Level= 0
Friction Slope Method= 1
Unsteady Friction Slope Method= 2
Unsteady Bridges Friction Slope Method= 1
Parabolic Critical Depth
Global Vel Dist=  1 , 1 , 1
Global Log Level= 0
CheckData=True
Encroach Param= -1, 0, 0, 0
BEGIN DESCRIPTION:
Multiple Run
END DESCRIPTION:

--- Stream0511.f01 (steady flow) ---

Flow Title=Multiple
Number of Profiles=7
Profile Names=10-year,25-year,50-year,1pct_min,100-year,1pct_plu,500-year
River Rch & RM= Stream0511,Reach-1,1678
     446     714     958     626    1249    2493    2096
River Rch & RM= Stream0511,Reach-1,686
     771    1281    1759    1174    2342    4674    4106
Boundary for River Rch & Prof#=Stream0511,Reach-1,1
Up Type=0
Dn Type=3
Dn Slope=0.005
Boundary for River Rch & Prof#=Stream0511,Reach-1,2
Up Type=0
Dn Type=3
Dn Slope=0.005
Boundary for River Rch & Prof#=Stream0511,Reach-1,3
Up Type=0
Dn Type=3
Dn Slope=0.005
Boundary for River Rch & Prof#=Stream0511,Reach-1,4
Up Type=0
Dn Type=3
Dn Slope=0.005
Boundary for River Rch & Prof#=Stream0511,Reach-1,5
Up Type=0
Dn Type=3
Dn Slope=0.005
Boundary for River Rch & Prof#=Stream0511,Reach-1,6
Up Type=0
Dn Type=3
Dn Slope=0.005
Boundary for River Rch & Prof#=Stream0511,Reach-1,7
Up Type=0
Dn Type=3
Dn Slope=0.005

--- Stream0511.g01 (geometry) ---

Geom Title=Existing Conditions

River Reach=Stream0511,Reach-1
Reach XY= 30
      2512825.00     13671425.00      2512777.35     13671380.70
      2512718.92     13671366.93      2512631.04     13671283.18
      2512581.05     13671272.47      2512565.32     13671264.22
      2512431.03     13671133.17      2512414.32     13671126.56
      2512380.88     13671122.51      2512365.03     13671114.29
      2512330.91     13671077.15      2512322.98     13671036.78
      2512316.65     13671028.19      2512235.47     13671023.87
      2512214.95     13671014.72      2512178.12     13670974.01
      2512175.00     13670925.00      2512080.86     13670927.13
      2512027.19     13670969.67      2512000.00     13670975.42
      2511972.82     13670969.63      2511931.08     13670933.19
      2511914.50     13670926.24      2511640.16     13670924.34
      2511622.55     13670918.98      2511575.00     13670882.56
      2511561.79     13670888.94      2511531.19     13670916.55
      2511514.59     13670923.66      2511375.00     13670925.00

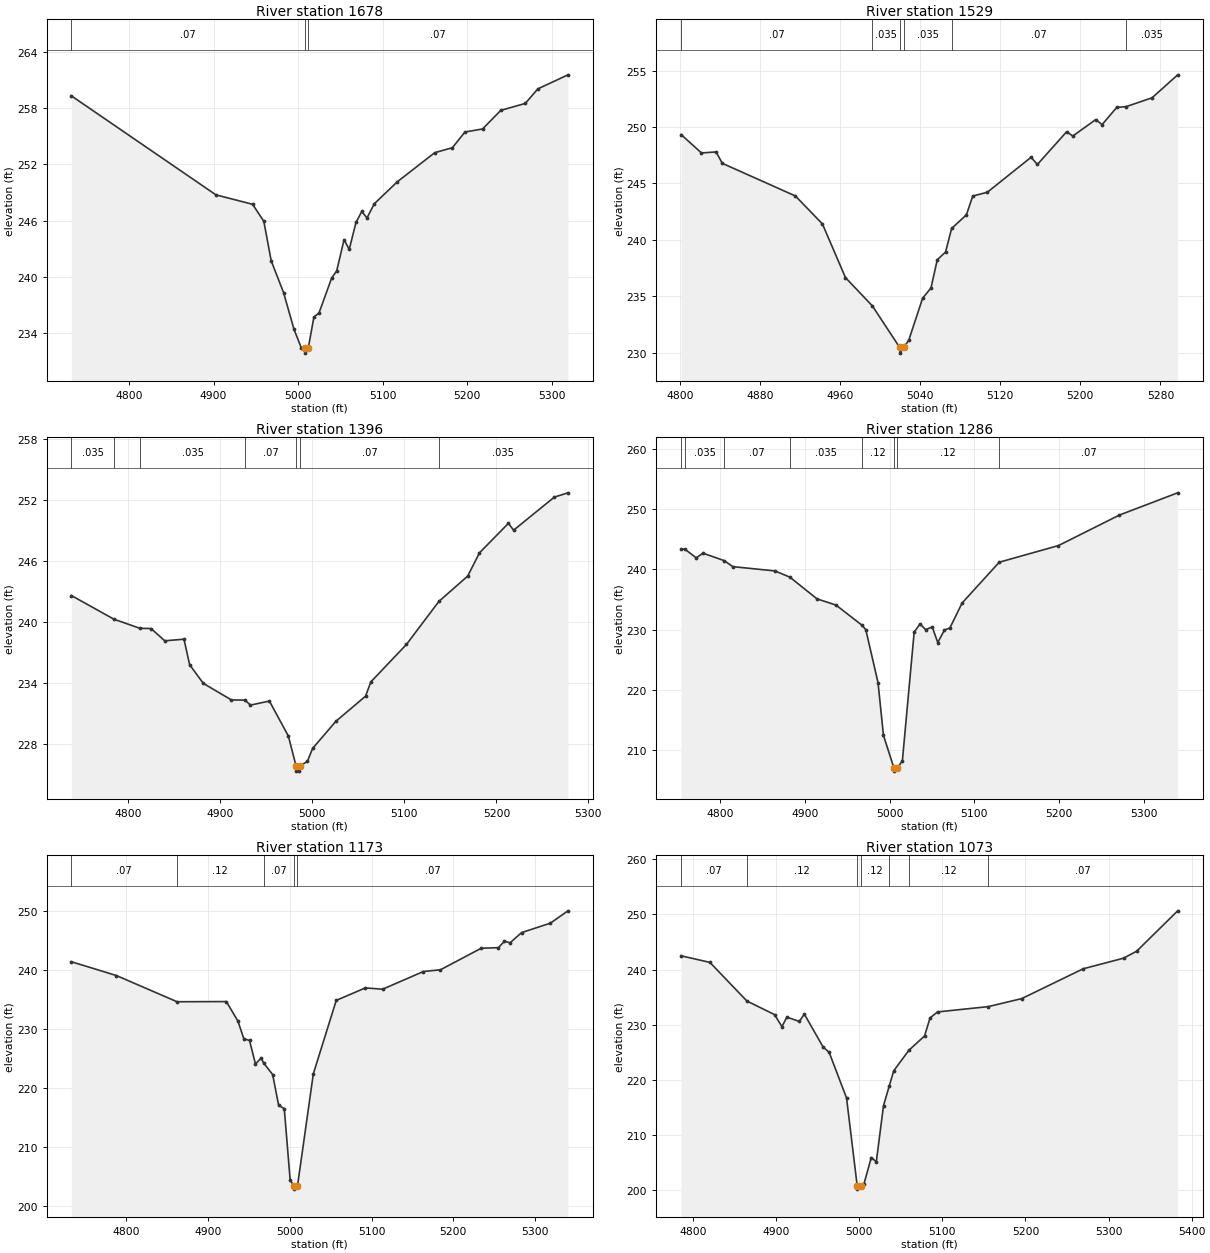
Type RM Length L Ch R = 1,1678,149,149,149
BEGIN DESCRIPTION:
XS6993
END DESCRIPTION:
XS GIS Cut Line= 2
      2512928.10     13671159.75      2512590.03     13671639.99
#Sta/Elev= 30
  4731.8  259.32  4902.8  248.76  4946.1  247.76  4959.4  245.94  4968.1  241.74
  4982.8  238.33  4995.1  234.42  5003.8  232.43  5007.9  232.39  5008.2  231.89
  5011.9  232.39  5018.6  235.73  5024.7  236.18  5039.5  239.87  5045.6  240.67
  5054.3  243.99  5060.4  242.95  5068.4  245.82  5075.2  246.99  5081.4  246.30
  5090.0  247.81  5117.3  250.16  5161.5  253.26  5182.4  253.79  5197.2  255.46
  5218.1  255.79  5239.6  257.77  5268.6  258.51  5283.4  260.06  5319.1  261.56
#Mann=3,-1,0
  4731.8    0.07       0  5007.9    0.05       0  5011.9    0.07       0
Bank Sta=5007.9,5011.9
Exp/Cntr=0.3,0.1

Type RM Length L Ch R = 1,1529,133,133,133
BEGIN DESCRIPTION:
E21126
END DESCRIPTION:
XS GIS Cut Line= 2
      2512771.65     13671142.93      2512474.40     13671539.99
#Sta/Elev= 30
  4801.2  249.33  4821.6  247.70  4836.2  247.79  4842.4  246.78  4915.4  243.89
  4942.4  241.41  4965.4  236.66  4992.3  234.15  5019.6  230.47  5019.9  229.97
  5023.6  230.47  5028.6  231.11  5042.5  234.84  5050.8  235.74  5057.1  238.24
  5065.4  238.93  5071.4  241.01  5086.2  242.22  5092.5  243.88  5107.1  244.22
  5150.8  247.32  5157.1  246.68  5186.3  249.58  5192.5  249.20  5215.4  250.66
  5221.7  250.21  5236.3  251.73  5246.0  251.81  5271.7  252.59  5297.2  254.62
#Mann=6,-1,0
  4801.2    0.07       0  4992.3   0.035       0  5019.6   0.035       0
  5023.6   0.035       0  5071.4    0.07       0  5246.0   0.035       0
Bank Sta=5019.6,5023.6
Exp/Cntr=0.3,0.1

Type RM Length L Ch R = 1,1396,110,110,110
BEGIN DESCRIPTION:
XS6992
END DESCRIPTION:
XS GIS Cut Line= 4
      2512610.85     13671010.93      2512516.22     13671147.22
      2512550.08     13671280.90      2512441.83     13671490.48
#Sta/Elev= 30
  4738.1  242.62  4784.3  240.29  4812.6  239.39  4824.7  239.37  4839.6  238.16
  4860.5  238.32  4866.6  235.81  4881.5  233.97  4912.0  232.34  4926.8  232.32
  4932.7  231.83  4953.3  232.23  4973.9  228.79  4982.3  225.83  4982.5  225.33
  4986.0  225.33  4986.3  225.83  4994.6  226.29  5000.3  227.57  5025.5  230.23
  5057.8  232.71  5063.6  234.12  5102.3  237.81  5137.5  242.04  5168.8  244.53
  5181.6  246.82  5213.1  249.73  5218.7  249.05  5263.0  252.31  5277.8  252.73
#Mann=7,-1,0
  4738.1   0.035       0  4784.3    0.07       0  4812.6   0.035       0
  4926.8    0.07       0  4982.3    0.05       0  4986.3    0.07       0
  5137.5   0.035       0
Bank Sta=4982.3,4986.3
Exp/Cntr=0.3,0.1

Type RM Length L Ch R = 1,1286,113,113,113
BEGIN DESCRIPTION:
E21125
END DESCRIPTION:
XS GIS Cut Line= 2
      2512617.55     13670971.52      2512249.34     13671426.36
#Sta/Elev= 30
  4754.3  243.36  4758.7  243.36  4772.2  241.92  4780.1  242.69  4805.1  241.46
  4815.3  240.46  4864.9  239.75  4882.6  238.71  4914.5  235.12  4936.8  234.10
  4967.2  230.79  4972.0  230.01  4986.4  221.24  4992.8  212.50  5005.2  207.08
  5005.4  206.58  5009.2  207.08  5015.1  208.31  5029.0  229.62  5035.9  230.97
  5042.4  230.03  5050.3  230.45  5056.8  227.89  5064.7  229.96  5071.1  230.31
  5085.5  234.44  5129.2  241.19  5199.0  243.95  5270.9  249.01  5339.5  252.69
#Mann=8,-1,0
  4754.3    0.07       0  4758.7   0.035       0  4805.1    0.07       0
  4882.6   0.035       0  4967.2    0.12       0  5005.2    0.05       0
  5009.2    0.12       0  5129.2    0.07       0
Bank Sta=5005.2,5009.2
Exp/Cntr=0.3,0.1

Type RM Length L Ch R = 1,1173,100,100,100
BEGIN DESCRIPTION:
XS6991
END DESCRIPTION:
XS GIS Cut Line= 2
      2512547.94     13670920.11      2512131.08     13671361.19
#Sta/Elev= 30
  4733.2  241.42  4788.3  239.08  4862.3  234.64  4922.6  234.67  4936.7  231.37
  4944.0  228.36  4950.9  228.08  4958.2  224.08  4965.0  225.09  4968.2  224.25
  4979.2  222.30  4986.5  217.09  4993.4  216.52  5000.6  204.35  5005.5  203.38
  5005.8  202.88  5009.5  203.38  5028.9  222.43  5056.9  234.87  5092.5  236.99
  5113.5  236.76  5163.3  239.76  5184.3  240.06  5234.1  243.71  5255.1  243.81
  5262.4  244.90  5269.3  244.63  5283.4  246.36  5318.6  247.96  5340.1  250.05
#Mann=5,-1,0
  4733.2    0.07       0  4862.3    0.12       0  4968.2    0.07       0
  5005.5    0.05       0  5009.5    0.07       0
Bank Sta=5005.5,5009.5
Exp/Cntr=0.3,0.1

Type RM Length L Ch R = 1,1073,138,138,138
BEGIN DESCRIPTION:
E21124
END DESCRIPTION:
XS GIS Cut Line= 3
      2512496.02     13670908.57      2512268.19     13671064.80
      2512104.03     13671341.28
#Sta/Elev= 30
  4785.4  242.51  4820.1  241.32  4864.6  234.32  4897.9  231.86  4906.8  229.68
  4912.8  231.40  4927.7  230.62  4933.8  231.94  4956.4  225.98  4963.6  225.04
  4984.6  216.75  4997.5  200.73  4997.7  200.23  5001.5  200.73  5005.5  201.15
  5014.4  205.96  5020.4  205.17  5029.1  215.36  5036.1  218.96  5041.4  221.68
  5059.7  225.40  5078.5  227.98  5085.1  231.25  5094.1  232.34  5155.1  233.30
  5195.4  234.75  5269.5  240.16  5318.1  242.08  5333.8  243.34  5383.2  250.66
#Mann=7,-1,0
  4785.4    0.07       0  4864.6    0.12       0  4997.5    0.05       0
  5001.5    0.12       0  5036.1     0.1       0  5059.7    0.12       0
  5155.1    0.07       0
Bank Sta=4997.5,5001.5
Exp/Cntr=0.3,0.1

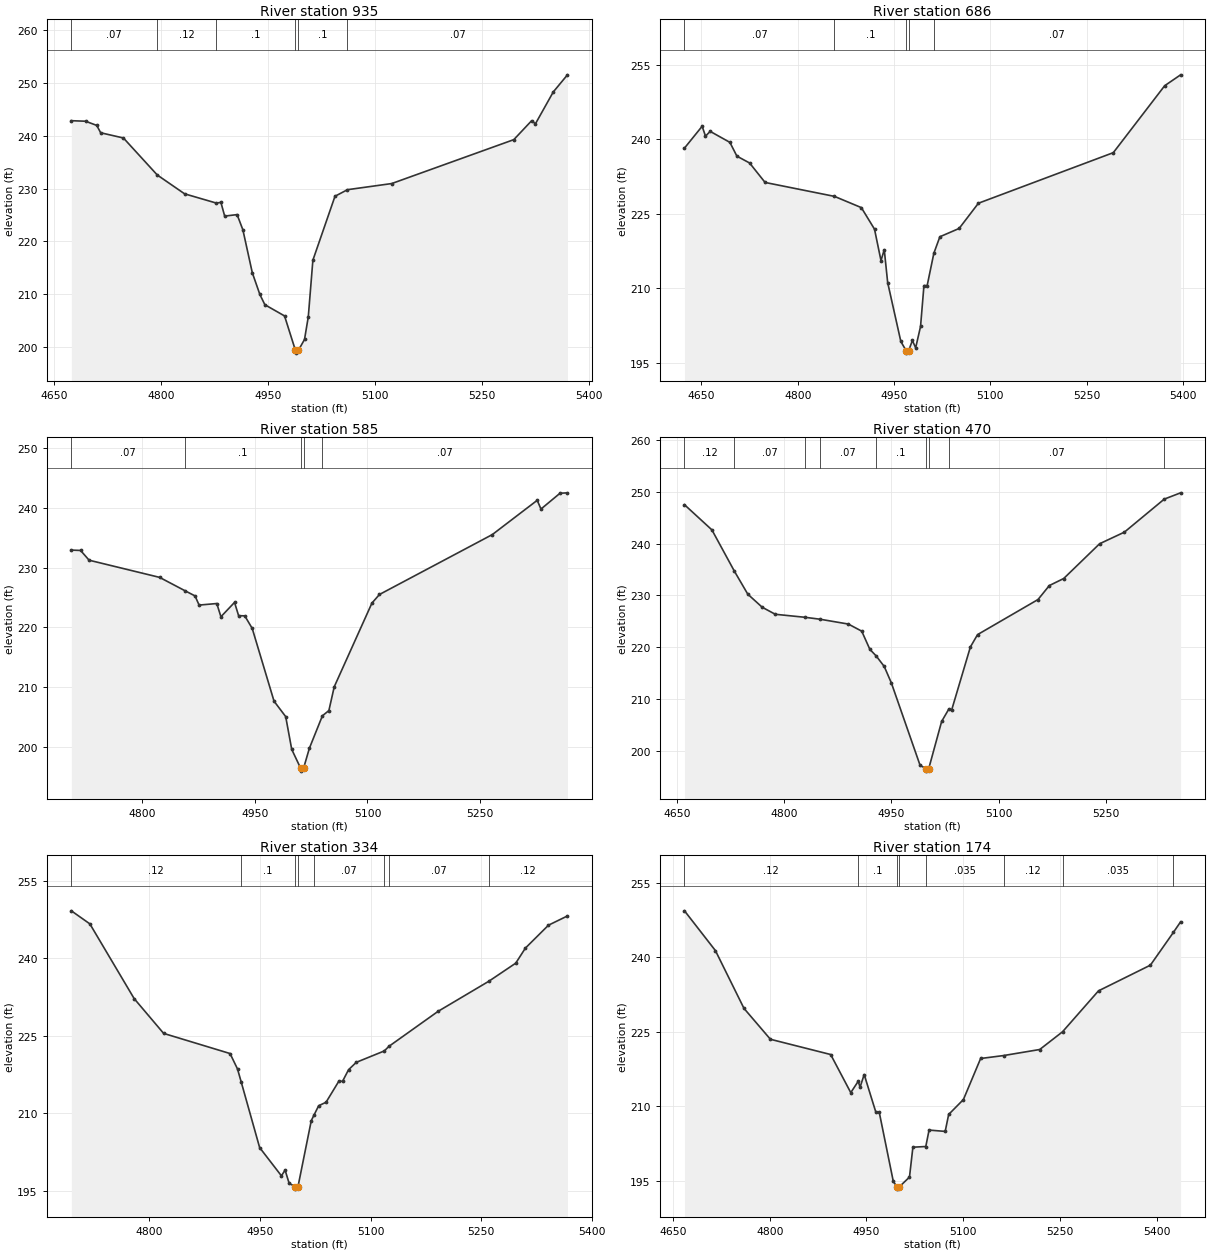
Type RM Length L Ch R = 1,935,249,249,249
BEGIN DESCRIPTION:
XS6990
END DESCRIPTION:
XS GIS Cut Line= 3
      2512483.72     13670868.04      2512202.43     13670968.75
      2512063.58     13671340.17
#Sta/Elev= 30
  4674.2  242.83  4694.1  242.73  4709.8  241.94  4715.3  240.55  4747.2  239.56
  4794.6  232.57  4832.9  229.01  4877.4  227.26  4883.8  227.39  4889.1  224.80
  4906.5  225.08  4914.6  222.21  4927.8  214.10  4938.4  209.99  4945.4  208.05
  4973.0  205.93  4988.3  199.40  4988.6  198.90  4992.3  199.40  5001.0  201.49
  5006.3  205.79  5012.7  216.46  5043.7  228.55  5061.2  229.79  5123.2  230.95
  5294.3  239.25  5319.3  242.83  5324.6  242.24  5349.6  248.26  5369.5  251.50
#Mann=6,-1,0
  4674.2    0.07       0  4794.6    0.12       0  4877.4     0.1       0
  4988.3    0.05       0  4992.3     0.1       0  5061.2    0.07       0
Bank Sta=4988.3,4992.3
Exp/Cntr=0.3,0.1

Type RM Length L Ch R = 1,686,101,101,101
BEGIN DESCRIPTION:
XS6989
END DESCRIPTION:
XS GIS Cut Line= 3
      2512096.52     13670605.94      2512016.67     13670970.49
      2512027.08     13671369.76
#Sta/Elev= 30
  4623.6  238.22  4651.1  242.61  4656.3  240.62  4663.6  241.58  4694.3  239.37
  4705.2  236.60  4725.0  235.22  4749.1  231.31  4857.1  228.51  4899.0  226.25
  4919.5  221.92  4929.6  215.60  4934.7  217.79  4940.0  211.18  4960.5  199.34
  4968.7  197.49  4968.9  196.99  4972.7  197.49  4978.5  199.53  4983.6  198.06
  4991.2  202.35  4996.5  210.57  5001.5  210.57  5011.9  217.06  5021.3  220.39
  5051.3  222.06  5081.3  227.13  5291.4  237.30  5371.4  250.76  5396.2  252.95
#Mann=5,-1,0
  4623.6    0.07       0  4857.1     0.1       0  4968.7    0.05       0
  4972.7     0.1       0  5011.9    0.07       0
Bank Sta=4968.7,4972.7
Exp/Cntr=0.3,0.1

Type RM Length L Ch R = 1,585,115,115,115
BEGIN DESCRIPTION:
E21123
END DESCRIPTION:
XS GIS Cut Line= 3
      2512046.84     13670663.30      2511912.28     13670975.83
      2511920.96     13671294.85
#Sta/Elev= 30
  4706.4  232.92  4718.7  232.86  4730.0  231.23  4823.7  228.36  4857.7  226.11
  4870.8  225.26  4876.2  223.73  4899.7  223.99  4905.2  221.78  4923.3  224.18
  4928.7  221.96  4936.9  221.93  4946.8  219.83  4975.8  207.67  4991.3  205.09
  4999.3  199.62  5011.1  196.48  5011.3  195.98  5015.1  196.48  5022.8  199.81
  5040.1  205.23  5048.7  206.10  5055.8  210.07  5105.9  224.06  5115.9  225.50
  5265.9  235.51  5325.6  241.24  5330.6  239.78  5355.9  242.42  5365.8  242.49
#Mann=5,-1,0
  4706.4    0.07       0  4857.7     0.1       0  5011.1    0.05       0
  5015.1     0.1       0  5040.1    0.07       0
Bank Sta=5011.1,5015.1
Exp/Cntr=0.3,0.1

Type RM Length L Ch R = 1,470,136,136,136
BEGIN DESCRIPTION:
XS6988
END DESCRIPTION:
XS GIS Cut Line= 2
      2511789.24     13670586.80      2511846.53     13671277.83
#Sta/Elev= 30
  4660.7  247.51  4699.0  242.65  4730.5  234.65  4749.2  230.22  4769.3  227.70
  4787.6  226.34  4829.6  225.75  4850.4  225.38  4889.7  224.45  4908.4  223.08
  4919.8  219.56  4928.6  218.29  4939.9  216.25  4949.9  213.05  4990.0  197.14
  4998.1  196.53  4998.3  196.03  5002.1  196.53  5020.1  205.63  5030.2  208.04
  5034.1  207.84  5060.3  220.03  5070.3  222.41  5154.8  229.19  5170.6  231.89
  5190.7  233.25  5240.9  239.97  5275.5  242.21  5331.2  248.59  5354.1  249.81
#Mann=9,-1,0
  4660.7    0.12       0  4730.5    0.07       0  4829.6    0.12       0
  4850.4    0.07       0  4928.6     0.1       0  4998.1    0.05       0
  5002.1     0.1       0  5030.2    0.07       0  5331.2    0.12       0
Bank Sta=4998.1,5002.1
Exp/Cntr=0.3,0.1

Type RM Length L Ch R = 1,334,160,160,160
BEGIN DESCRIPTION:
E21122
END DESCRIPTION:
XS GIS Cut Line= 3
      2511671.40     13670619.95      2511682.25     13670984.51
      2511769.07     13671279.68
#Sta/Elev= 30
  4694.5  249.19  4719.6  246.66  4779.6  232.19  4819.6  225.44  4909.6  221.54
  4919.7  218.55  4924.7  216.04  4949.7  203.32  4979.2  197.85  4984.2  198.95
  4989.7  196.39  4997.7  195.77  4997.9  195.27  5001.7  195.77  5019.7  208.55
  5023.3  209.59  5029.7  211.43  5039.7  212.10  5057.0  216.17  5062.1  216.17
  5070.2  218.40  5080.6  219.83  5118.6  222.04  5125.0  222.94  5191.5  229.71
  5260.4  235.55  5296.8  239.05  5309.9  241.97  5341.2  246.41  5366.9  248.20
#Mann=8,-1,0
  4694.5    0.12       0  4924.7     0.1       0  4997.7    0.05       0
  5001.7     0.1       0  5023.3    0.07       0  5118.6    0.12       0
  5125.0    0.07       0  5260.4    0.12       0
Bank Sta=4997.7,5001.7
Exp/Cntr=0.3,0.1

Type RM Length L Ch R = 1,174,0,0,0
BEGIN DESCRIPTION:
XS6987
END DESCRIPTION:
XS GIS Cut Line= 3
      2511613.90     13670586.77      2511532.29     13670875.00
      2511695.50     13671316.01
#Sta/Elev= 30
  4667.6  249.34  4715.6  241.33  4759.9  229.70  4800.9  223.48  4894.4  220.41
  4925.6  212.74  4937.2  215.03  4940.0  213.82  4946.4  216.38  4964.6  208.77
  4969.8  208.77  4991.6  194.86  4997.2  193.81  4997.4  193.31  5001.2  193.81
  5016.7  195.73  5022.0  201.75  5042.0  201.89  5047.1  205.20  5072.1  204.93
  5077.5  208.34  5100.4  211.35  5127.1  219.61  5162.6  220.20  5218.8  221.42
  5254.2  224.99  5310.0  233.23  5390.5  238.40  5426.1  244.98  5437.4  247.13
#Mann=8,-1,0
  4667.6    0.12       0  4937.2     0.1       0  4997.2    0.05       0
  5001.2     0.1       0  5042.0   0.035       0  5162.6    0.12       0
  5254.2   0.035       0  5426.1    0.12       0
Bank Sta=4997.2,5001.2
Exp/Cntr=0.3,0.1

Chan Stop Cuts=-1