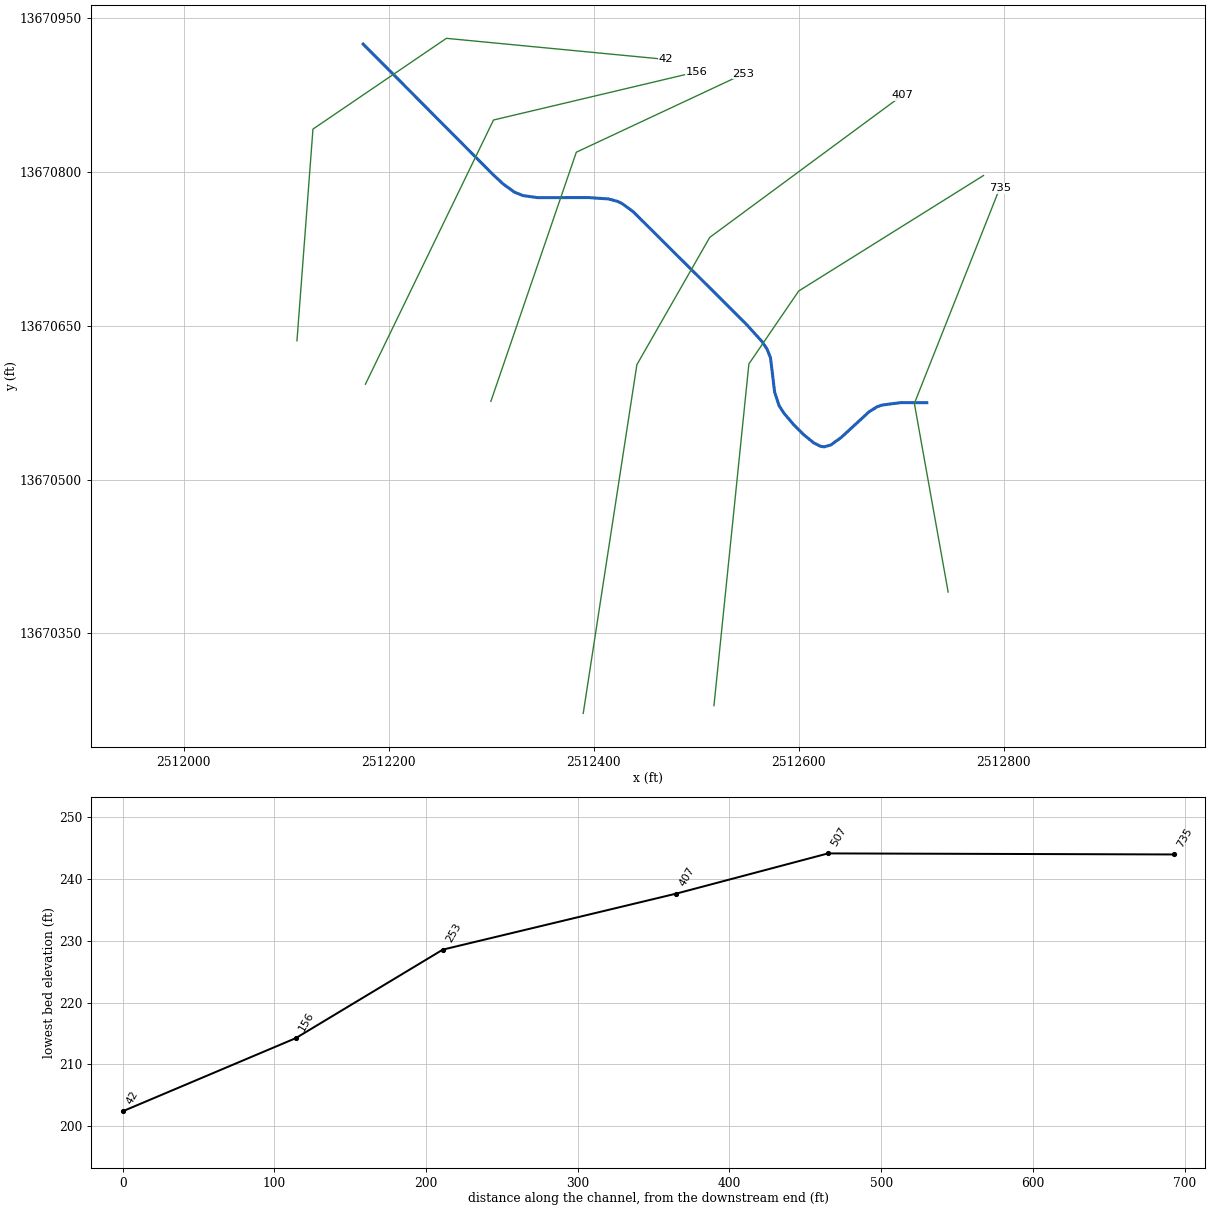
--- Stream0512.prj (project) ---

Proj Title=Stream0512 Base Level Engineering
Current Plan=p01
Default Exp/Contr=0.3,0.1
English Units
Geom File=g01
Flow File=f01
Plan File=p01
BEGIN DESCRIPTION:
Stream0512
END DESCRIPTION:

--- Stream0512.p01 (plan) ---

Plan Title=Multiple Run
Short Identifier=Multiple
Geom File=g01
Flow File=f01
Subcritical Flow
K Sum by GR= 0
Std Step Tol= 0.01
Critical Tol= 0.01
Num of Std Step Trials= 20
Max Error Tol= 0.3
Flow Tol Ratio= 0.001
Split Flow NTrial= 30
Split Flow Tol= 0.02
Split Flow Ratio= 0.02
Log Output Level= 0
Friction Slope Method= 1
Unsteady Friction Slope Method= 2
Unsteady Bridges Friction Slope Method= 1
Parabolic Critical Depth
Global Vel Dist=  1 , 1 , 1
Global Log Level= 0
CheckData=True
Encroach Param= -1, 0, 0, 0
BEGIN DESCRIPTION:
Multiple Run
END DESCRIPTION:

--- Stream0512.f01 (steady flow) ---

Flow Title=Multiple
Number of Profiles=7
Profile Names=10-year,25-year,50-year,1pct_min,100-year,1pct_plu,500-year
River Rch & RM= Stream0512,Reach-1,735
     264     404     526     335     668    1332    1057
Boundary for River Rch & Prof#=Stream0512,Reach-1,1
Up Type=0
Dn Type=3
Dn Slope=0.005
Boundary for River Rch & Prof#=Stream0512,Reach-1,2
Up Type=0
Dn Type=3
Dn Slope=0.005
Boundary for River Rch & Prof#=Stream0512,Reach-1,3
Up Type=0
Dn Type=3
Dn Slope=0.005
Boundary for River Rch & Prof#=Stream0512,Reach-1,4
Up Type=0
Dn Type=3
Dn Slope=0.005
Boundary for River Rch & Prof#=Stream0512,Reach-1,5
Up Type=0
Dn Type=3
Dn Slope=0.005
Boundary for River Rch & Prof#=Stream0512,Reach-1,6
Up Type=0
Dn Type=3
Dn Slope=0.005
Boundary for River Rch & Prof#=Stream0512,Reach-1,7
Up Type=0
Dn Type=3
Dn Slope=0.005

--- Stream0512.g01 (geometry) ---

Geom Title=Existing Conditions

River Reach=Stream0512,Reach-1
Reach XY= 30
      2512725.00     13670575.00      2512699.63     13670575.13
      2512681.13     13670572.69      2512676.34     13670570.97
      2512668.76     13670566.25      2512641.44     13670541.09
      2512631.40     13670533.82      2512624.70     13670531.95
      2512621.34     13670532.48      2512614.62     13670535.85
      2512604.57     13670544.10      2512594.76     13670553.97
      2512585.76     13670564.59      2512580.84     13670572.16
      2512576.54     13670585.31      2512572.47     13670618.87
      2512569.15     13670627.24      2512564.22     13670634.65
      2512548.70     13670651.81      2512438.30     13670761.60
      2512427.43     13670769.48      2512423.50     13670771.39
      2512414.52     13670773.83      2512395.08     13670775.18
      2512345.05     13670775.13      2512330.89     13670777.15
      2512322.57     13670780.52      2512311.69     13670788.40
      2512301.47     13670797.87      2512175.00     13670925.00

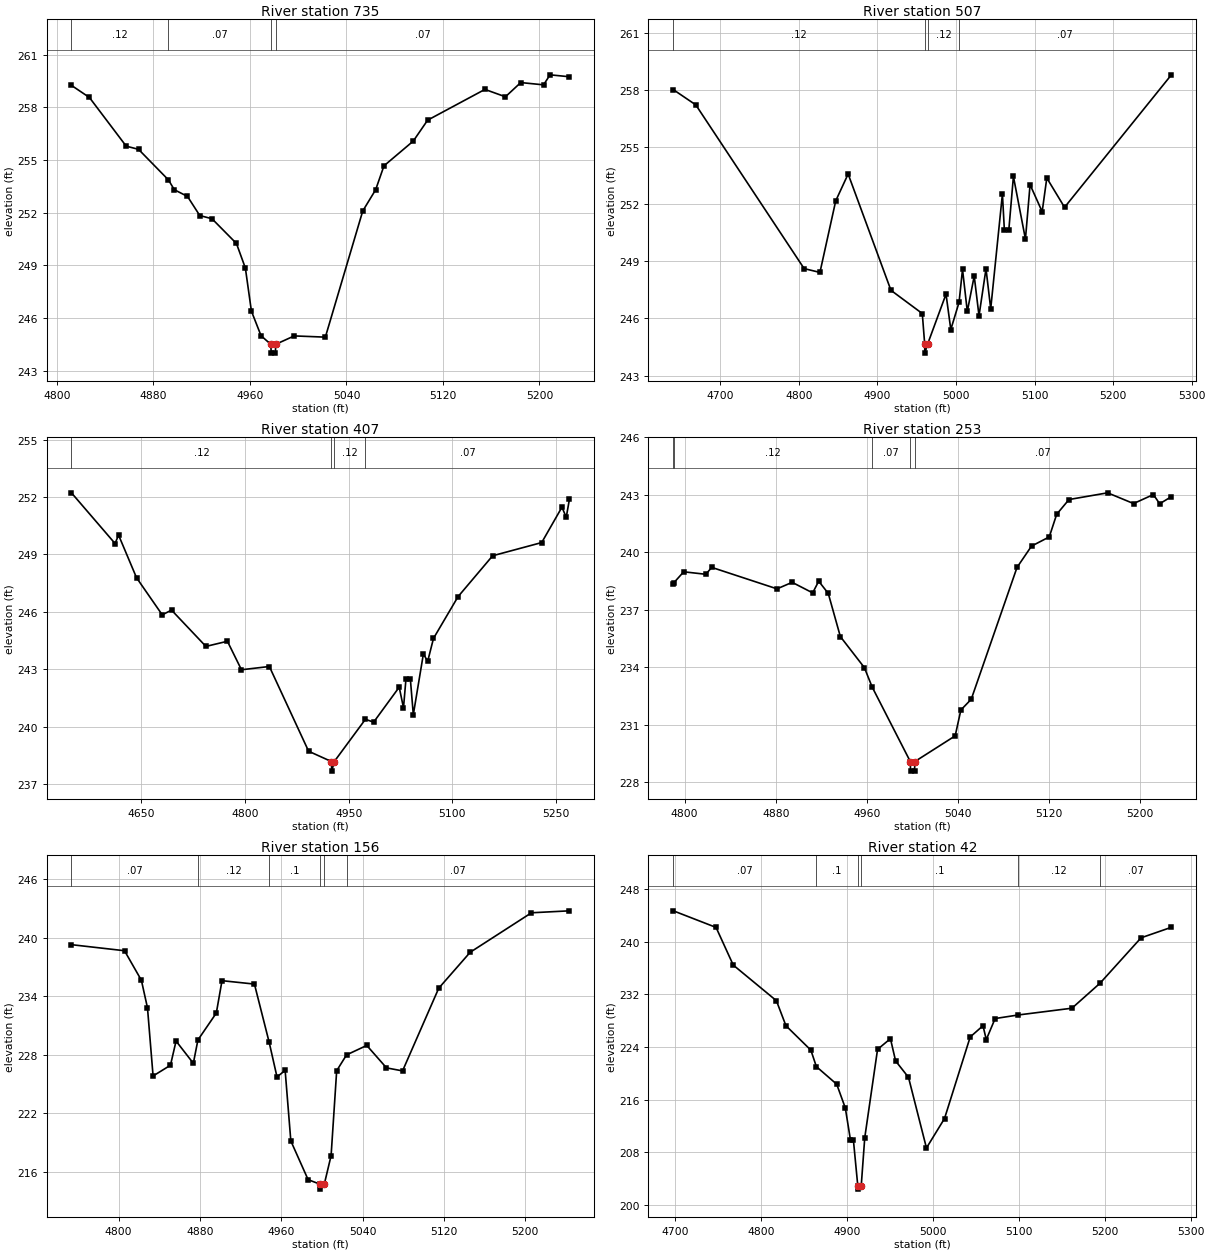
Type RM Length L Ch R = 1,735,228,228,228
BEGIN DESCRIPTION:
XS6997
END DESCRIPTION:
XS GIS Cut Line= 3
      2512745.83     13670390.30      2512712.85     13670574.31
      2512796.17     13670784.35
#Sta/Elev= 30
  4812.0  259.25  4826.9  258.56  4857.4  255.79  4867.6  255.61  4892.4  253.87
  4897.3  253.31  4908.2  252.93  4918.4  251.84  4928.5  251.66  4948.8  250.25
  4956.2  248.85  4961.2  246.40  4969.2  245.00  4977.3  244.51  4977.6  244.01
  4981.1  244.01  4981.3  244.51  4996.7  244.99  5022.5  244.92  5053.5  252.10
  5064.2  253.31  5071.1  254.67  5095.4  256.08  5107.3  257.27  5154.8  259.02
  5171.8  258.60  5184.5  259.41  5203.4  259.28  5208.8  259.85  5224.9  259.74
#Mann=4,-1,0
  4812.0    0.12       0  4892.4    0.07       0  4977.3    0.05       0
  4981.3    0.07       0
Bank Sta=4977.3,4981.3
Exp/Cntr=0.3,0.1

Type RM Length L Ch R = 1,507,100,100,100
BEGIN DESCRIPTION:
XS6996
END DESCRIPTION:
XS GIS Cut Line= 4
      2512517.31     13670279.41      2512551.39     13670612.85
      2512600.00     13670684.03      2512780.31     13670796.72
#Sta/Elev= 30
  4640.2  258.02  4668.8  257.22  4806.7  248.62  4826.8  248.42  4846.9  252.18
  4862.7  253.59  4917.2  247.48  4957.1  246.26  4960.1  244.68  4960.3  244.18
  4964.1  244.68  4987.3  247.28  4993.4  245.42  5003.9  246.85  5008.3  248.58
  5014.4  246.37  5023.2  248.23  5029.3  246.14  5038.2  248.61  5044.2  246.51
  5059.1  252.54  5061.6  250.63  5067.2  250.63  5073.1  253.46  5088.4  250.17
  5094.3  253.03  5109.7  251.61  5115.6  253.38  5138.2  251.84  5274.2  258.80
#Mann=4,-1,0
  4640.2    0.12       0  4960.1    0.05       0  4964.1    0.12       0
  5003.9    0.07       0
Bank Sta=4960.1,4964.1
Exp/Cntr=0.3,0.1

Type RM Length L Ch R = 1,407,154,154,154
BEGIN DESCRIPTION:
E21128
END DESCRIPTION:
XS GIS Cut Line= 4
      2512389.75     13670271.89      2512442.10     13670612.12
      2512513.15     13670736.29      2512700.96     13670874.88
#Sta/Elev= 30
  4548.8  252.22  4611.9  249.57  4617.0  250.01  4643.0  247.78  4680.2  245.84
  4693.6  246.09  4743.4  244.19  4774.5  244.46  4794.8  242.97  4835.2  243.14
  4892.0  238.71  4925.1  238.17  4925.4  237.67  4929.1  238.17  4974.2  240.38
  4986.1  240.23  5023.1  242.06  5029.3  240.98  5032.9  242.50  5039.2  242.50
  5043.5  240.62  5058.1  243.80  5064.3  243.41  5072.7  244.61  5108.2  246.79
  5158.3  248.93  5229.3  249.62  5258.6  251.47  5264.8  250.94  5269.5  251.90
#Mann=4,-1,0
  4548.8    0.12       0  4925.1    0.05       0  4929.1    0.12       0
  4974.2    0.07       0
Bank Sta=4925.1,4929.1
Exp/Cntr=0.3,0.1

Type RM Length L Ch R = 1,253,97,97,97
BEGIN DESCRIPTION:
XS6995
END DESCRIPTION:
XS GIS Cut Line= 3
      2512299.64     13670576.36      2512382.99     13670819.44
      2512546.21     13670895.85
#Sta/Elev= 30
  4790.1  238.35  4790.4  238.41  4799.2  238.99  4818.6  238.86  4823.8  239.22
  4881.1  238.10  4894.4  238.44  4912.4  237.89  4917.7  238.50  4926.1  237.86
  4936.7  235.61  4957.8  233.99  4964.6  232.98  4998.1  229.09  4998.3  228.59
  5001.8  228.59  5002.1  229.09  5037.5  230.43  5042.5  231.78  5051.6  232.34
  5091.8  239.22  5104.5  240.33  5120.1  240.81  5126.6  241.99  5137.4  242.76
  5171.3  243.11  5194.1  242.55  5211.5  243.02  5217.0  242.54  5227.3  242.91
#Mann=5,-1,0
  4790.1    0.07       0  4790.4    0.12       0  4964.6    0.07       0
  4998.1    0.05       0  5002.1    0.07       0
Bank Sta=4998.1,5002.1
Exp/Cntr=0.3,0.1

Type RM Length L Ch R = 1,156,114,114,114
BEGIN DESCRIPTION:
E21127
END DESCRIPTION:
XS GIS Cut Line= 3
      2512177.21     13670593.05      2512302.21     13670850.87
      2512500.11     13670897.74
#Sta/Elev= 30
  4753.6  239.30  4805.8  238.68  4822.4  235.65  4828.4  232.82  4833.9  225.84
  4851.0  226.94  4856.5  229.42  4873.5  227.14  4878.0  229.53  4896.1  232.29
  4901.7  235.61  4933.6  235.26  4948.1  229.29  4955.8  225.74  4963.8  226.41
  4969.4  219.18  4986.4  215.21  4998.3  214.74  4998.5  214.24  5002.3  214.74
  5009.0  217.67  5014.5  226.38  5024.2  228.00  5044.1  228.97  5063.5  226.67
  5079.3  226.36  5114.9  234.84  5145.8  238.52  5206.1  242.57  5243.5  242.77
#Mann=6,-1,0
  4753.6    0.07       0  4878.0    0.12       0  4948.1     0.1       0
  4998.3    0.05       0  5002.3     0.1       0  5024.2    0.07       0
Bank Sta=4998.3,5002.3
Exp/Cntr=0.3,0.1

Type RM Length L Ch R = 1,42,0,0,0
BEGIN DESCRIPTION:
XS6994
END DESCRIPTION:
XS GIS Cut Line= 4
      2512110.42     13670635.45      2512126.04     13670842.01
      2512256.25     13670930.56      2512470.16     13670910.02
#Sta/Elev= 30
  4697.9  244.67  4747.6  242.15  4767.6  236.43  4817.8  231.02  4828.9  227.22
  4857.9  223.51  4864.3  221.01  4888.0  218.33  4898.0  214.72  4904.0  209.85
  4907.4  209.85  4912.5  202.90  4912.8  202.40  4916.5  202.90  4920.6  210.20
  4935.5  223.63  4950.5  225.25  4956.5  221.87  4971.5  219.38  4992.4  208.65
  5013.4  213.12  5043.3  225.51  5058.2  227.22  5062.0  225.11  5072.3  228.31
  5099.1  228.85  5161.7  229.88  5194.4  233.68  5242.1  240.57  5277.4  242.17
#Mann=6,-1,0
  4697.9    0.07       0  4864.3     0.1       0  4912.5    0.05       0
  4916.5     0.1       0  5099.1    0.12       0  5194.4    0.07       0
Bank Sta=4912.5,4916.5
Exp/Cntr=0.3,0.1

Chan Stop Cuts=-1