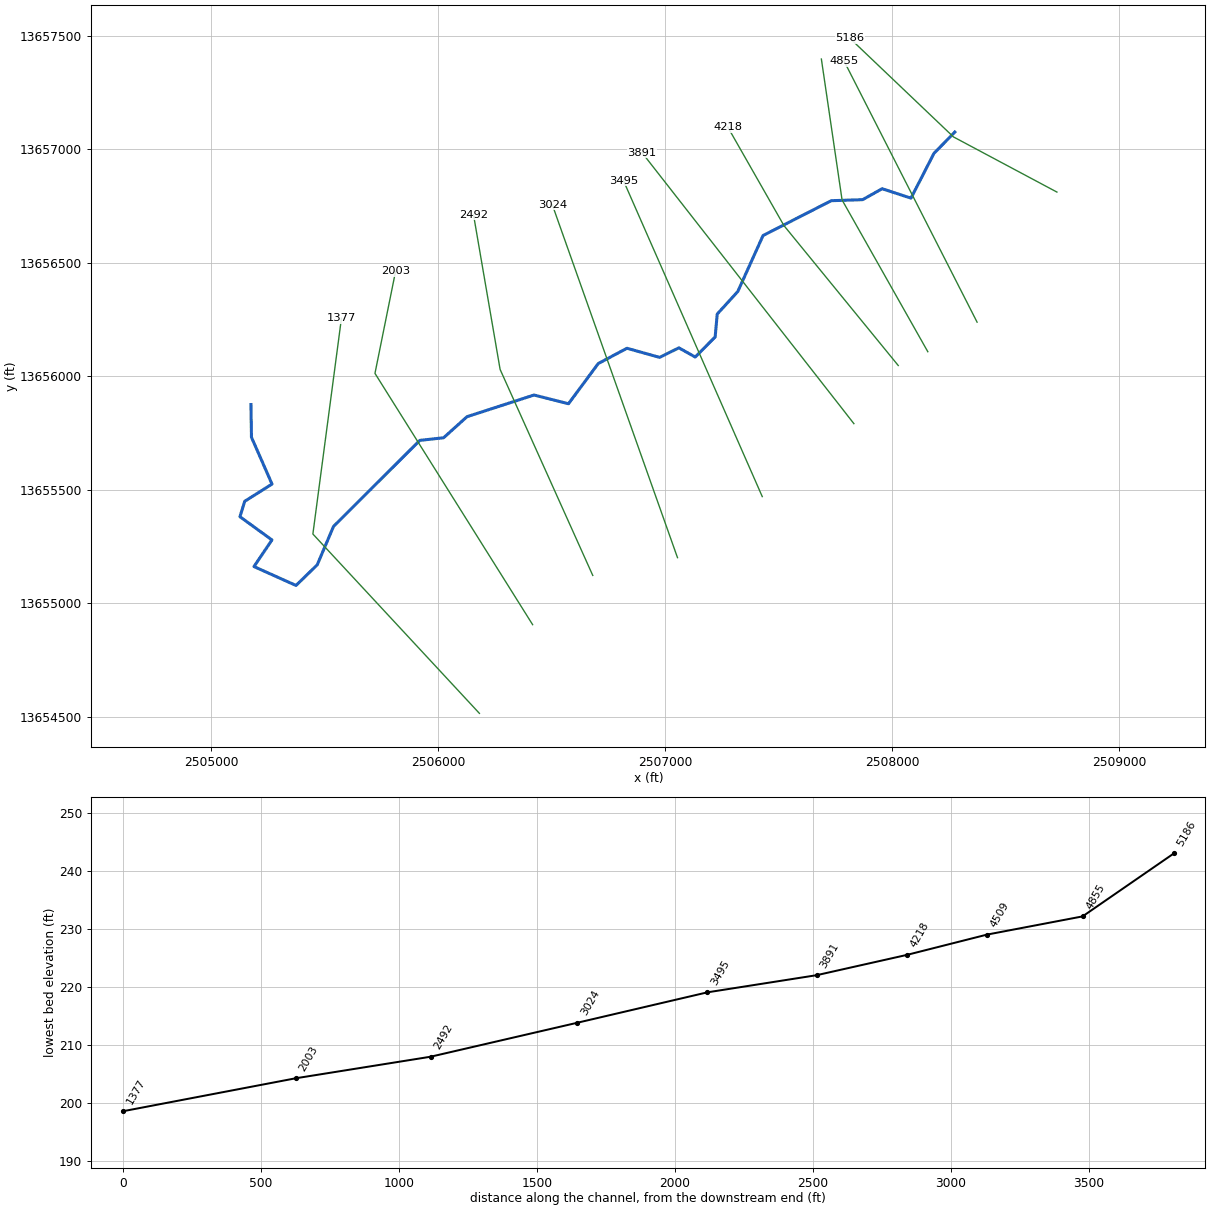
--- Stream0513.prj (project) ---

Proj Title=Stream0513 Base Level Engineering
Current Plan=p01
Default Exp/Contr=0.3,0.1
English Units
Geom File=g01
Flow File=f01
Plan File=p01
BEGIN DESCRIPTION:
Stream0513
END DESCRIPTION:

--- Stream0513.p01 (plan) ---

Plan Title=Multiple Run
Short Identifier=Multiple
Geom File=g01
Flow File=f01
Subcritical Flow
K Sum by GR= 0
Std Step Tol= 0.01
Critical Tol= 0.01
Num of Std Step Trials= 20
Max Error Tol= 0.3
Flow Tol Ratio= 0.001
Split Flow NTrial= 30
Split Flow Tol= 0.02
Split Flow Ratio= 0.02
Log Output Level= 0
Friction Slope Method= 1
Unsteady Friction Slope Method= 2
Unsteady Bridges Friction Slope Method= 1
Parabolic Critical Depth
Global Vel Dist=  1 , 1 , 1
Global Log Level= 0
CheckData=True
Encroach Param= -1, 0, 0, 0
BEGIN DESCRIPTION:
Multiple Run
END DESCRIPTION:

--- Stream0513.f01 (steady flow) ---

Flow Title=Multiple
Number of Profiles=7
Profile Names=10-year,25-year,50-year,1pct_min,100-year,1pct_plu,500-year
River Rch & RM= Stream0513,Reach-1,5186
     936    1552    2126    1412    2818    5622    4897
River Rch & RM= Stream0513,Reach-1,3024
     994    1656    2275    1514    3021    6027    5273
Boundary for River Rch & Prof#=Stream0513,Reach-1,1
Up Type=0
Dn Type=3
Dn Slope=0.005
Boundary for River Rch & Prof#=Stream0513,Reach-1,2
Up Type=0
Dn Type=3
Dn Slope=0.005
Boundary for River Rch & Prof#=Stream0513,Reach-1,3
Up Type=0
Dn Type=3
Dn Slope=0.005
Boundary for River Rch & Prof#=Stream0513,Reach-1,4
Up Type=0
Dn Type=3
Dn Slope=0.005
Boundary for River Rch & Prof#=Stream0513,Reach-1,5
Up Type=0
Dn Type=3
Dn Slope=0.005
Boundary for River Rch & Prof#=Stream0513,Reach-1,6
Up Type=0
Dn Type=3
Dn Slope=0.005
Boundary for River Rch & Prof#=Stream0513,Reach-1,7
Up Type=0
Dn Type=3
Dn Slope=0.005

--- Stream0513.g01 (geometry) ---

Geom Title=Existing Conditions

River Reach=Stream0513,Reach-1
Reach XY= 30
      2508275.00     13657075.00      2508183.09     13656981.08
      2508082.02     13656784.01      2507954.96     13656825.58
      2507869.06     13656777.27      2507730.93     13656772.75
      2507430.58     13656619.42      2507319.15     13656372.71
      2507228.63     13656273.50      2507219.48     13656172.54
      2507131.75     13656084.14      2507059.64     13656124.71
      2506975.01     13656082.59      2506830.97     13656122.85
      2506704.53     13656055.38      2506573.51     13655878.46
      2506421.70     13655916.92      2506126.50     13655821.38
      2506023.50     13655728.63      2505918.83     13655717.14
      2505538.62     13655338.21      2505466.87     13655168.92
      2505373.38     13655078.12      2505188.27     13655161.31
      2505267.50     13655278.58      2505126.49     13655380.91
      2505147.56     13655448.83      2505267.77     13655524.69
      2505177.22     13655730.92      2505175.00     13655875.00

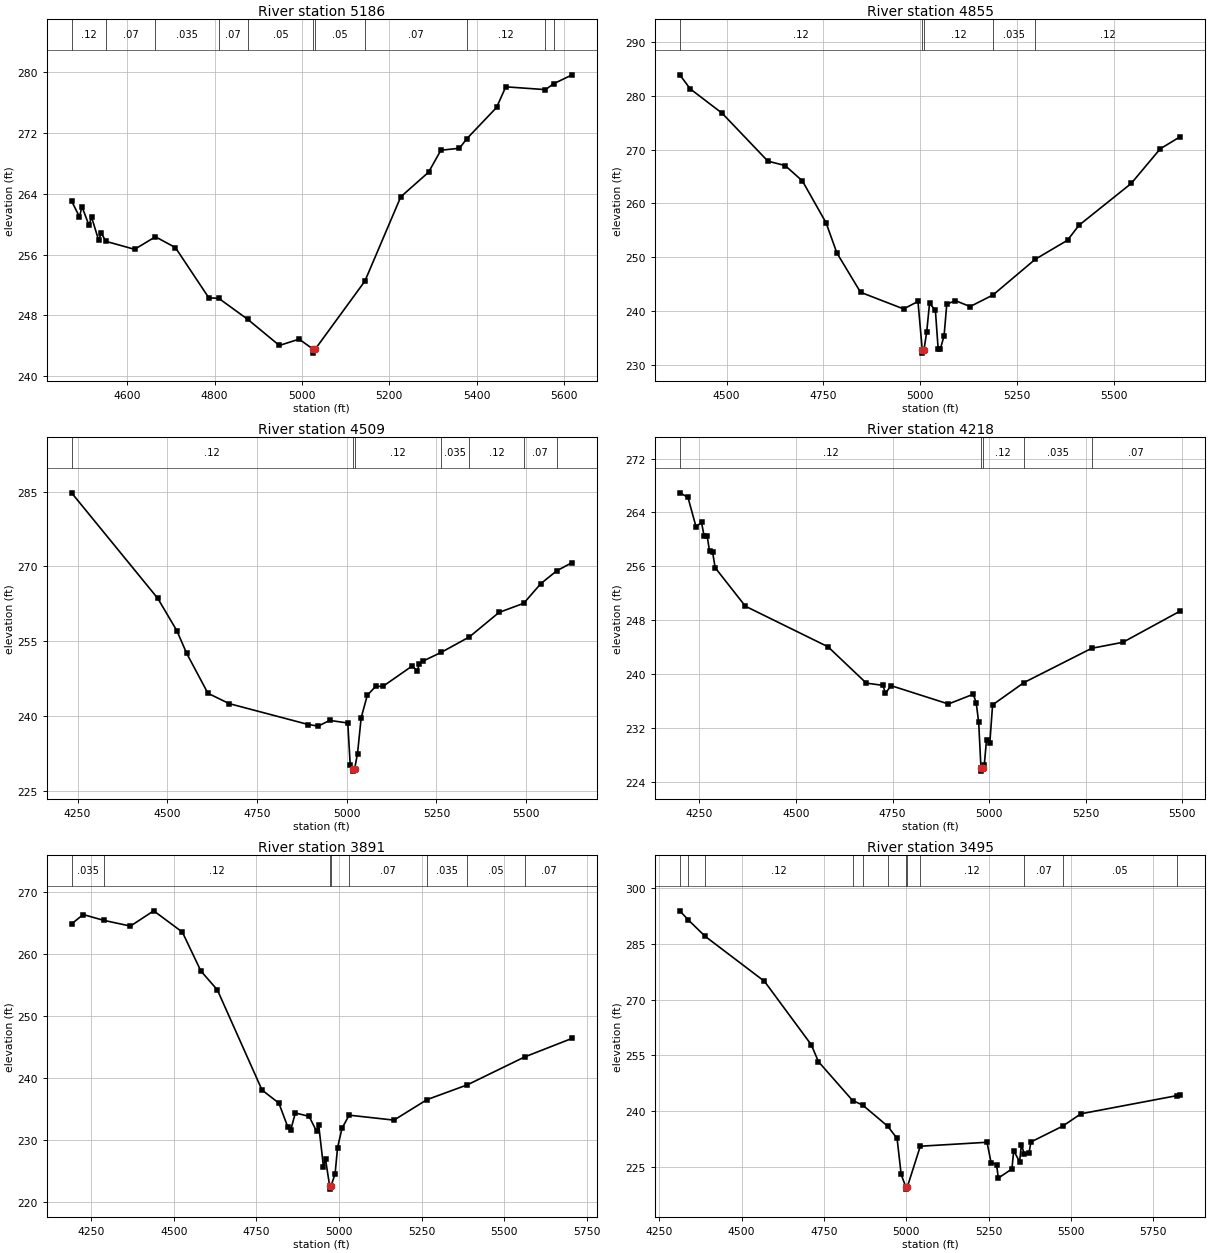
Type RM Length L Ch R = 1,5186,331,331,331
BEGIN DESCRIPTION:
XS7007
END DESCRIPTION:
XS GIS Cut Line= 3
      2508724.62     13656810.78      2508268.92     13657053.82
      2507813.19     13657487.85
#Sta/Elev= 30
  4472.8  263.05  4490.9  260.97  4496.6  262.32  4512.8  259.83  4518.5  260.95
  4534.8  257.88  4540.5  258.83  4551.6  257.74  4617.0  256.69  4664.8  258.34
  4710.5  256.92  4787.0  250.30  4809.6  250.24  4876.0  247.47  4948.4  244.03
  4993.7  244.86  5026.2  243.52  5026.5  243.02  5030.2  243.52  5144.2  252.50
  5226.4  263.61  5289.9  266.84  5318.2  269.74  5360.7  270.00  5377.4  271.25
  5445.6  275.37  5466.7  278.09  5557.5  277.72  5576.1  278.49  5618.6  279.67
#Mann=11,-1,0
  4472.8    0.12       0  4551.6    0.07       0  4664.8   0.035       0
  4809.6    0.07       0  4876.0    0.05       0  5026.2    0.05       0
  5030.2    0.05       0  5144.2    0.07       0  5377.4    0.12       0
  5557.5    0.05       0  5576.1    0.07       0
Bank Sta=5026.2,5030.2
Exp/Cntr=0.3,0.1

Type RM Length L Ch R = 1,4855,346,346,346
BEGIN DESCRIPTION:
XS7006
END DESCRIPTION:
XS GIS Cut Line= 2
      2508373.10     13656237.84      2507787.17     13657387.99
#Sta/Elev= 30
  4379.6  283.90  4406.5  281.28  4488.6  276.77  4606.6  267.86  4651.1  267.04
  4695.6  264.19  4756.7  256.40  4784.5  250.81  4845.6  243.49  4956.8  240.39
  4993.7  241.79  5004.9  232.68  5005.1  232.18  5008.9  232.68  5016.1  236.03
  5023.5  241.41  5038.6  240.16  5045.7  233.03  5051.4  232.95  5061.0  235.39
  5068.0  241.28  5090.2  241.93  5128.3  240.84  5187.2  242.99  5296.1  249.62
  5379.3  253.16  5408.9  255.94  5543.6  263.71  5618.3  270.14  5670.4  272.42
#Mann=5,-1,0
  4379.6    0.12       0  5004.9    0.05       0  5008.9    0.12       0
  5187.2   0.035       0  5296.1    0.12       0
Bank Sta=5004.9,5008.9
Exp/Cntr=0.3,0.1

Type RM Length L Ch R = 1,4509,291,291,291
BEGIN DESCRIPTION:
XS7005
END DESCRIPTION:
XS GIS Cut Line= 3
      2508156.07     13656107.65      2507778.47     13656776.04
      2507687.32     13657396.71
#Sta/Elev= 30
  4233.2  284.74  4473.1  263.65  4526.6  257.15  4554.0  252.61  4613.2  244.63
  4672.4  242.56  4893.3  238.37  4920.7  238.06  4952.5  239.20  5002.9  238.68
  5009.9  230.19  5018.0  229.55  5018.3  229.05  5022.0  229.55  5030.1  232.54
  5040.2  239.70  5057.3  244.22  5080.7  246.02  5100.9  246.01  5181.7  250.05
  5196.9  249.17  5202.0  250.47  5212.1  251.05  5264.0  252.84  5341.9  255.91
  5424.3  260.80  5493.4  262.64  5540.8  266.56  5585.6  269.15  5628.2  270.78
#Mann=7,-1,0
  4233.2    0.12       0  5018.0    0.05       0  5022.0    0.12       0
  5264.0   0.035       0  5341.9    0.12       0  5493.4    0.07       0
  5585.6    0.12       0
Bank Sta=5018,5022
Exp/Cntr=0.3,0.1

Type RM Length L Ch R = 1,4218,327,327,327
BEGIN DESCRIPTION:
XS7004
END DESCRIPTION:
XS GIS Cut Line= 3
      2508025.87     13656046.87      2507522.40     13656663.19
      2507275.00     13657097.22
#Sta/Elev= 30
  4199.5  266.92  4220.5  266.26  4241.3  261.90  4255.7  262.52  4262.1  260.55
  4270.1  260.56  4276.5  258.22  4284.4  258.08  4290.9  255.79  4369.1  250.07
  4583.1  244.03  4682.1  238.63  4725.2  238.30  4731.7  237.10  4746.0  238.26
  4894.6  235.53  4958.9  236.98  4966.4  235.74  4972.9  232.82  4978.8  226.05
  4979.0  225.55  4982.8  226.05  4987.3  226.40  4993.3  230.25  5001.7  229.72
  5008.9  235.40  5090.0  238.71  5265.4  243.81  5346.0  244.70  5494.9  249.36
#Mann=5,-1,0
  4199.5    0.12       0  4978.8    0.05       0  4982.8    0.12       0
  5090.0   0.035       0  5265.4    0.07       0
Bank Sta=4978.8,4982.8
Exp/Cntr=0.3,0.1

Type RM Length L Ch R = 1,3891,396,396,396
BEGIN DESCRIPTION:
XS7003
END DESCRIPTION:
XS GIS Cut Line= 2
      2507830.54     13655790.82      2506897.42     13656984.34
#Sta/Elev= 30
  4190.5  264.80  4225.7  266.31  4287.6  265.38  4368.6  264.45  4439.1  266.91
  4525.8  263.48  4582.0  257.20  4631.7  254.17  4767.0  238.02  4817.8  235.93
  4845.2  232.04  4853.3  231.51  4867.8  234.33  4909.4  233.79  4932.0  231.38
  4938.3  232.43  4952.8  225.70  4959.1  226.88  4971.6  222.56  4971.8  222.06
  4975.6  222.56  4988.0  224.49  4995.5  228.73  5008.9  231.85  5030.6  233.98
  5166.2  233.18  5266.2  236.48  5388.5  238.87  5562.1  243.37  5705.5  246.36
#Mann=8,-1,0
  4190.5   0.035       0  4287.6    0.12       0  4971.6    0.05       0
  4975.6    0.12       0  5030.6    0.07       0  5266.2   0.035       0
  5388.5    0.05       0  5562.1    0.07       0
Bank Sta=4971.6,4975.6
Exp/Cntr=0.3,0.1

Type RM Length L Ch R = 1,3495,471,471,471
BEGIN DESCRIPTION:
XS7002
END DESCRIPTION:
XS GIS Cut Line= 2
      2507426.92     13655469.58      2506815.55     13656861.43
#Sta/Elev= 30
  4312.2  293.83  4337.2  291.45  4389.2  286.98  4569.3  274.90  4711.3  257.89
  4733.2  253.33  4837.0  242.89  4867.5  241.68  4943.3  236.02  4972.0  232.74
  4984.4  223.06  4998.8  219.61  4999.0  219.11  5002.8  219.61  5042.5  230.63
  5245.2  231.69  5257.4  226.24  5274.1  225.70  5279.5  222.08  5320.8  224.53
  5326.2  229.44  5344.1  226.44  5349.6  231.04  5358.7  228.43  5372.9  228.88
  5378.4  231.77  5474.6  236.01  5530.5  239.34  5822.9  244.23  5832.4  244.37
#Mann=12,-1,0
  4312.2    0.12       0  4337.2    0.07       0  4389.2    0.12       0
  4837.0   0.035       0  4867.5    0.12       0  4943.3   0.035       0
  4998.8   0.035       0  5002.8   0.035       0  5042.5    0.12       0
  5358.7    0.07       0  5474.6    0.05       0  5822.9    0.07       0
Bank Sta=4998.8,5002.8
Exp/Cntr=0.3,0.1

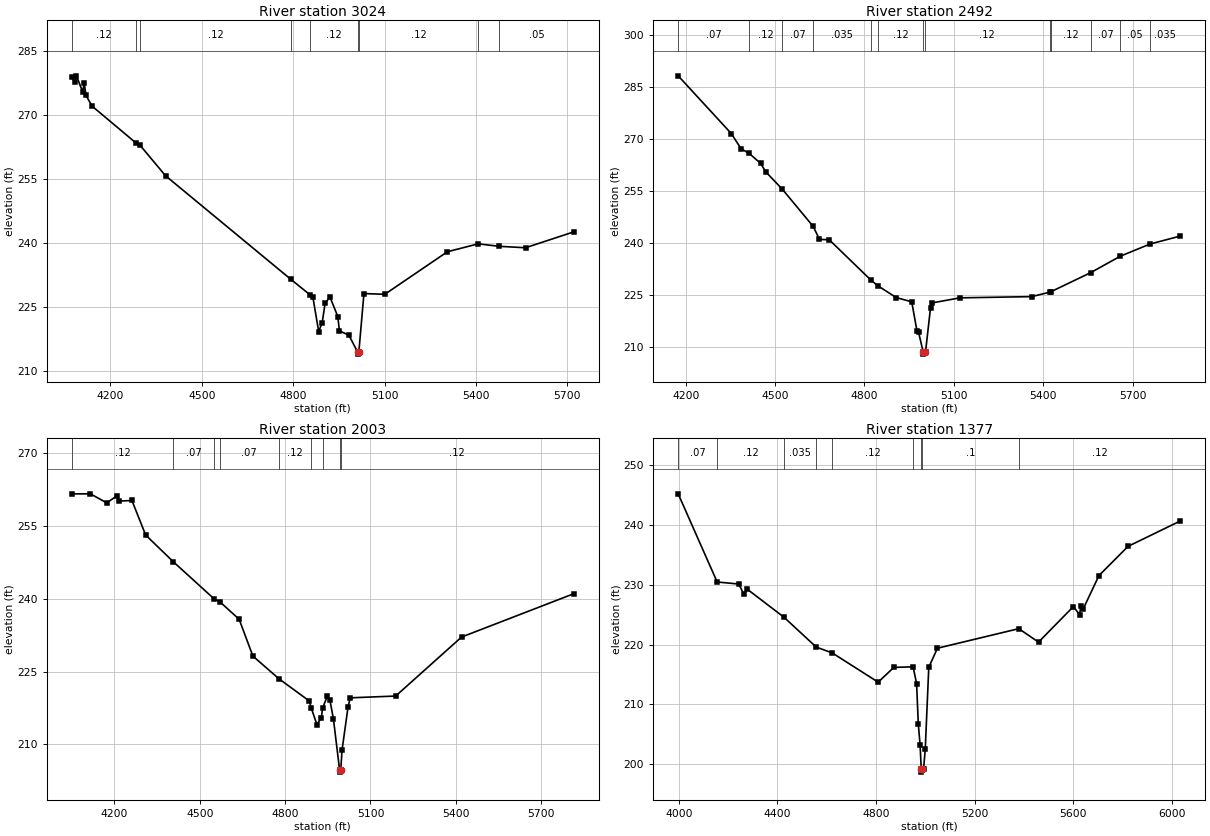
Type RM Length L Ch R = 1,3024,532,532,532
BEGIN DESCRIPTION:
XS7001
END DESCRIPTION:
XS GIS Cut Line= 2
      2507053.64     13655200.55      2506502.42     13656754.38
#Sta/Elev= 30
  4072.6  278.86  4083.1  277.54  4088.4  279.10  4108.6  275.37  4113.9  277.38
  4119.8  274.50  4139.5  272.01  4283.4  263.39  4296.3  262.90  4381.1  255.67
  4793.0  231.37  4855.2  227.78  4864.5  227.31  4883.7  219.18  4895.3  221.28
  4904.9  225.85  4920.9  227.25  4946.5  222.69  4951.8  219.32  4982.7  218.34
  5011.5  214.38  5011.7  213.88  5015.6  214.38  5032.3  228.07  5100.8  227.90
  5306.3  237.87  5407.5  239.73  5476.0  239.15  5562.8  238.81  5721.3  242.53
#Mann=9,-1,0
  4072.6    0.12       0  4283.4    0.07       0  4296.3    0.12       0
  4793.0   0.035       0  4855.2    0.12       0  5011.5    0.05       0
  5015.6    0.12       0  5407.5    0.07       0  5476.0    0.05       0
Bank Sta=5011.5,5015.6
Exp/Cntr=0.3,0.1

Type RM Length L Ch R = 1,2492,489,489,489
BEGIN DESCRIPTION:
XS7000
END DESCRIPTION:
XS GIS Cut Line= 3
      2506680.40     13655122.36      2506272.40     13656029.51
      2506155.30     13656710.43
#Sta/Elev= 30
  4174.8  288.13  4353.1  271.52  4386.0  267.14  4413.1  265.81  4451.8  262.91
  4468.3  260.55  4524.6  255.47  4628.0  244.79  4649.2  241.05  4682.1  240.93
  4822.0  229.32  4846.2  227.64  4907.0  224.30  4958.8  223.09  4976.5  214.69
  4982.0  214.26  4997.5  208.53  4997.8  208.03  5001.7  208.53  5005.1  208.65
  5022.0  221.44  5028.3  222.79  5120.7  224.23  5361.7  224.58  5422.9  225.88
  5427.2  226.04  5559.7  231.49  5659.1  236.22  5758.6  239.71  5860.4  242.02
#Mann=13,-1,0
  4174.8    0.07       0  4413.1    0.12       0  4524.6    0.07       0
  4628.0   0.035       0  4822.0    0.07       0  4846.2    0.12       0
  4997.5    0.05       0  5001.7    0.12       0  5422.9    0.07       0
  5427.2    0.12       0  5559.7    0.07       0  5659.1    0.05       0
  5758.6   0.035       0
Bank Sta=4997.5,5001.7
Exp/Cntr=0.3,0.1

Type RM Length L Ch R = 1,2003,626,626,626
BEGIN DESCRIPTION:
XS6999
END DESCRIPTION:
XS GIS Cut Line= 3
      2506415.64     13654905.36      2505721.18     13656012.15
      2505811.97     13656461.76
#Sta/Elev= 30
  4049.5  261.51  4115.3  261.52  4173.0  259.66  4209.5  261.14  4215.4  260.03
  4261.4  260.15  4309.7  253.05  4406.7  247.57  4549.6  239.97  4570.0  239.36
  4638.4  235.73  4686.7  228.17  4778.1  223.51  4884.7  218.96  4892.4  217.41
  4911.8  214.09  4927.1  215.47  4931.7  217.43  4948.3  219.97  4957.7  219.05
  4969.9  215.22  4991.4  204.82  4991.7  204.32  4995.6  204.82  5000.1  208.83
  5021.3  217.75  5028.9  219.59  5188.7  219.96  5420.2  232.08  5814.8  240.99
#Mann=9,-1,0
  4049.5    0.12       0  4406.7    0.07       0  4549.6   0.035       0
  4570.0    0.07       0  4778.1    0.12       0  4892.4    0.07       0
  4931.7    0.12       0  4991.4    0.05       0  4995.6    0.12       0
Bank Sta=4991.4,4995.6
Exp/Cntr=0.3,0.1

Type RM Length L Ch R = 1,1377,0,0,0
BEGIN DESCRIPTION:
XS6998
END DESCRIPTION:
XS GIS Cut Line= 3
      2506181.27     13654514.74      2505447.74     13655304.69
      2505573.61     13656255.19
#Sta/Elev= 30
  3997.7  245.21  4155.8  230.46  4243.1  230.12  4264.1  228.42  4278.3  229.24
  4426.7  224.57  4557.7  219.57  4622.8  218.59  4808.9  213.70  4872.4  216.17
  4950.6  216.27  4964.8  213.46  4971.6  206.77  4979.0  203.17  4983.7  199.15
  4984.0  198.65  4988.0  199.15  4993.2  199.23  5000.0  202.55  5014.2  216.18
  5049.3  219.38  5379.4  222.65  5459.3  220.40  5600.6  226.34  5626.0  225.00
  5631.0  226.49  5640.9  225.98  5704.4  231.53  5822.5  236.42  6034.5  240.67
#Mann=9,-1,0
  3997.7    0.07       0  4155.8    0.12       0  4426.7   0.035       0
  4557.7    0.07       0  4622.8    0.12       0  4950.6     0.1       0
  4983.7    0.05       0  4988.0     0.1       0  5379.4    0.12       0
Bank Sta=4983.7,4988
Exp/Cntr=0.3,0.1

Chan Stop Cuts=-1