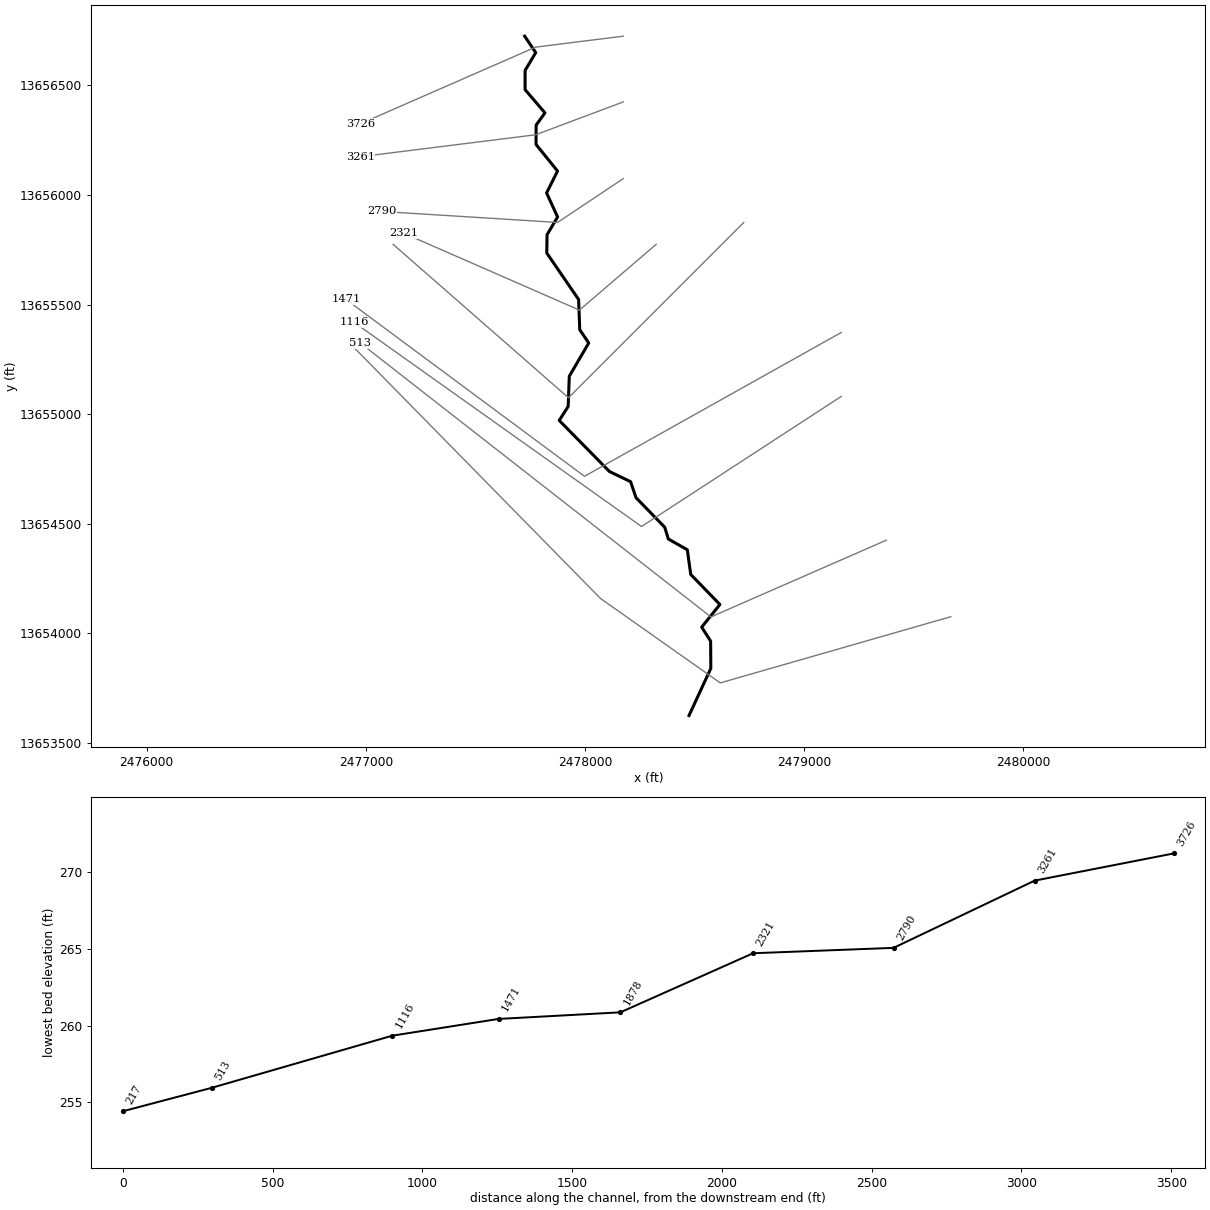
--- Stream0515.prj (project) ---

Proj Title=Stream0515 Base Level Engineering
Current Plan=p01
Default Exp/Contr=0.3,0.1
English Units
Geom File=g01
Flow File=f01
Plan File=p01
BEGIN DESCRIPTION:
Stream0515
END DESCRIPTION:

--- Stream0515.p01 (plan) ---

Plan Title=Multiple Run
Short Identifier=Multiple
Geom File=g01
Flow File=f01
Subcritical Flow
K Sum by GR= 0
Std Step Tol= 0.01
Critical Tol= 0.01
Num of Std Step Trials= 20
Max Error Tol= 0.3
Flow Tol Ratio= 0.001
Split Flow NTrial= 30
Split Flow Tol= 0.02
Split Flow Ratio= 0.02
Log Output Level= 0
Friction Slope Method= 1
Unsteady Friction Slope Method= 2
Unsteady Bridges Friction Slope Method= 1
Parabolic Critical Depth
Global Vel Dist=  1 , 1 , 1
Global Log Level= 0
CheckData=True
Encroach Param= -1, 0, 0, 0
BEGIN DESCRIPTION:
Multiple Run
END DESCRIPTION:

--- Stream0515.f01 (steady flow) ---

Flow Title=Multiple
Number of Profiles=7
Profile Names=10-year,25-year,50-year,1pct_min,100-year,1pct_plu,500-year
River Rch & RM= Stream0515,Reach-1,3726
     747    1209    1627    1061    2117    4224    3547
Boundary for River Rch & Prof#=Stream0515,Reach-1,1
Up Type=0
Dn Type=3
Dn Slope=0.005
Boundary for River Rch & Prof#=Stream0515,Reach-1,2
Up Type=0
Dn Type=3
Dn Slope=0.005
Boundary for River Rch & Prof#=Stream0515,Reach-1,3
Up Type=0
Dn Type=3
Dn Slope=0.005
Boundary for River Rch & Prof#=Stream0515,Reach-1,4
Up Type=0
Dn Type=3
Dn Slope=0.005
Boundary for River Rch & Prof#=Stream0515,Reach-1,5
Up Type=0
Dn Type=3
Dn Slope=0.005
Boundary for River Rch & Prof#=Stream0515,Reach-1,6
Up Type=0
Dn Type=3
Dn Slope=0.005
Boundary for River Rch & Prof#=Stream0515,Reach-1,7
Up Type=0
Dn Type=3
Dn Slope=0.005

--- Stream0515.g01 (geometry) ---

Geom Title=Existing Conditions

River Reach=Stream0515,Reach-1
Reach XY= 30
      2477725.00     13656725.00      2477775.61     13656649.95
      2477727.18     13656569.04      2477726.98     13656480.89
      2477817.67     13656375.10      2477777.37     13656319.11
      2477776.98     13656230.90      2477875.04     13656109.66
      2477825.11     13656009.61      2477875.39     13655900.00
      2477827.19     13655819.03      2477825.94     13655735.48
      2477971.24     13655523.44      2477976.40     13655385.44
      2478017.47     13655324.99      2477928.76     13655173.44
      2477923.60     13655035.44      2477882.79     13654971.58
      2478111.80     13654738.64      2478208.50     13654692.05
      2478233.17     13654618.97      2478364.11     13654484.42
      2478380.65     13654430.64      2478467.21     13654381.44
      2478482.86     13654268.83      2478616.03     13654131.67
      2478532.82     13654028.42      2478573.62     13653964.56
      2478574.51     13653840.22      2478475.00     13653625.00

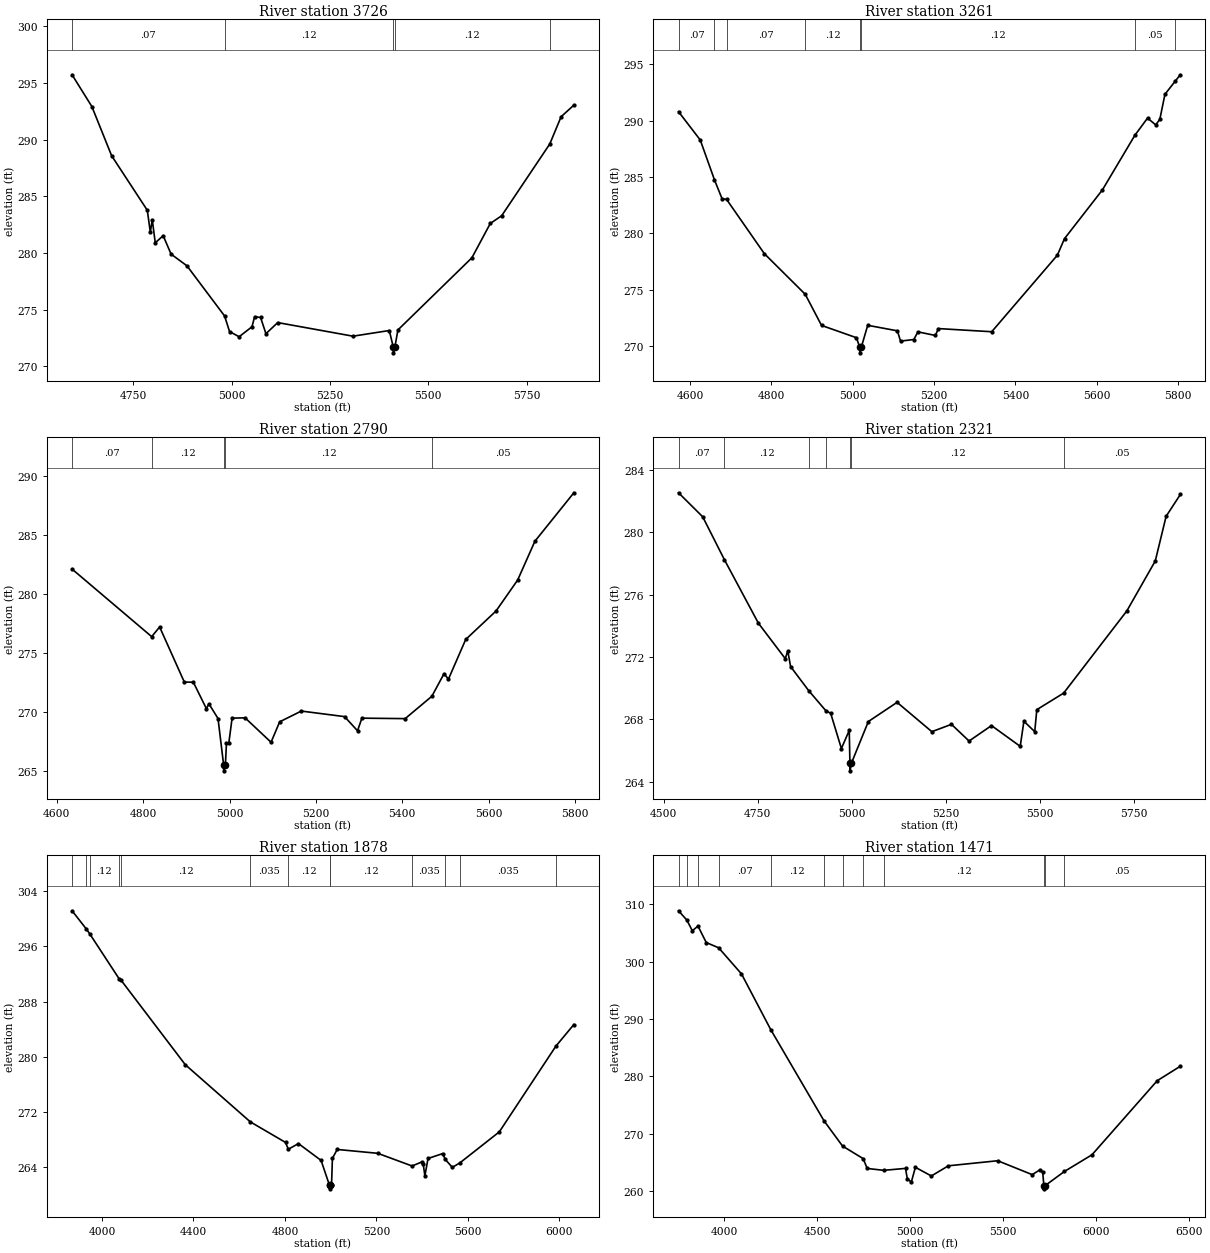
Type RM Length L Ch R = 1,3726,465,465,465
BEGIN DESCRIPTION:
Stream0515 6.0
END DESCRIPTION:
XS GIS Cut Line= 3
      2478174.95     13656724.99      2477775.00     13656675.00
      2476974.98     13656324.99
#Sta/Elev= 30
  4593.8  295.73  4644.1  292.93  4694.5  288.58  4785.2  283.77  4792.8  281.84
  4797.8  282.93  4805.4  280.90  4825.5  281.53  4845.7  279.90  4886.0  278.87
  4981.8  274.44  4994.3  273.07  5018.7  272.61  5051.4  273.49  5058.1  274.38
  5073.3  274.31  5086.9  272.88  5116.9  273.86  5308.3  272.66  5400.7  273.16
  5410.8  271.69  5411.1  271.19  5414.8  271.69  5422.6  273.21  5610.8  279.58
  5657.6  282.61  5686.5  283.29  5808.8  289.62  5837.7  292.03  5870.1  293.05
#Mann=5,-1,0
  4593.8    0.07       0  4981.8    0.12       0  5410.8    0.05       0
  5414.8    0.12       0  5808.8    0.05       0
Bank Sta=5410.8,5414.8
Exp/Cntr=0.3,0.1

Type RM Length L Ch R = 1,3261,471,471,471
BEGIN DESCRIPTION:
Stream0515 5.0
END DESCRIPTION:
XS GIS Cut Line= 3
      2478174.98     13656424.99      2477775.00     13656275.00
      2476975.00     13656175.00
#Sta/Elev= 30
  4572.0  290.79  4625.4  288.28  4660.3  284.75  4678.8  283.09  4690.2  283.01
  4782.9  278.21  4883.4  274.61  4923.5  271.85  5009.3  270.76  5017.3  269.92
  5017.6  269.42  5021.3  269.92  5037.0  271.86  5110.0  271.37  5117.6  270.46
  5150.3  270.60  5160.4  271.28  5203.3  270.96  5210.8  271.57  5341.8  271.29
  5503.1  278.07  5520.7  279.54  5613.9  283.86  5693.7  288.70  5724.8  290.22
  5744.9  289.62  5755.0  290.11  5767.6  292.33  5792.3  293.47  5805.4  294.06
#Mann=8,-1,0
  4572.0    0.07       0  4660.3    0.12       0  4690.2    0.07       0
  4883.4    0.12       0  5017.3    0.05       0  5021.3    0.12       0
  5693.7    0.05       0  5792.3    0.07       0
Bank Sta=5017.3,5021.3
Exp/Cntr=0.3,0.1

Type RM Length L Ch R = 1,2790,469,469,469
BEGIN DESCRIPTION:
Stream0515 4.0
END DESCRIPTION:
XS GIS Cut Line= 3
      2478175.00     13656075.00      2477875.00     13655875.00
      2477075.02     13655925.00
#Sta/Elev= 30
  4635.3  282.13  4819.7  276.41  4838.1  277.23  4895.2  272.57  4916.2  272.55
  4946.3  270.32  4952.3  270.72  4973.3  269.48  4986.3  265.55  4986.6  265.05
  4990.4  265.55  4992.9  267.42  4998.4  267.42  5005.9  269.51  5035.9  269.54
  5096.1  267.47  5116.1  269.20  5166.2  270.11  5266.4  269.64  5296.4  268.44
  5306.5  269.51  5406.7  269.47  5468.5  271.36  5496.8  273.28  5506.9  272.81
  5546.9  276.17  5617.1  278.58  5667.2  281.20  5707.2  284.49  5797.4  288.59
#Mann=5,-1,0
  4635.3    0.07       0  4819.7    0.12       0  4986.3    0.05       0
  4990.4    0.12       0  5468.5    0.05       0
Bank Sta=4986.3,4990.4
Exp/Cntr=0.3,0.1

Type RM Length L Ch R = 1,2321,443,443,443
BEGIN DESCRIPTION:
Stream0515 3.0
END DESCRIPTION:
XS GIS Cut Line= 3
      2478325.04     13655775.03      2477975.00     13655475.00
      2477175.03     13655824.98
#Sta/Elev= 30
  4539.4  282.52  4603.7  280.98  4661.6  278.22  4751.8  274.16  4823.2  271.89
  4829.8  272.39  4837.4  271.38  4885.8  269.83  4931.2  268.55  4943.9  268.39
  4972.4  266.13  4993.3  267.29  4995.1  265.20  4995.3  264.70  4999.2  265.20
  5044.1  267.86  5120.5  269.09  5212.9  267.21  5265.1  267.68  5311.9  266.61
  5371.5  267.60  5447.9  266.27  5457.7  267.88  5486.5  267.21  5492.0  268.62
  5563.3  269.68  5731.4  274.95  5807.0  278.15  5835.8  281.01  5873.6  282.41
#Mann=7,-1,0
  4539.4    0.07       0  4661.6    0.12       0  4885.8    0.07       0
  4931.2    0.12       0  4995.1    0.05       0  4999.2    0.12       0
  5563.3    0.05       0
Bank Sta=4995.1,4999.2
Exp/Cntr=0.3,0.1

Type RM Length L Ch R = 1,1878,407,407,407
BEGIN DESCRIPTION:
Stream0515 2.0
END DESCRIPTION:
XS GIS Cut Line= 3
      2478725.03     13655875.03      2477925.00     13655075.00
      2477125.02     13655774.98
#Sta/Elev= 30
  3869.0  301.17  3931.6  298.52  3945.8  297.85  4075.0  291.30  4081.1  291.20
  4364.0  278.86  4648.5  270.57  4802.4  267.59  4814.6  266.60  4859.0  267.42
  4958.0  264.98  4994.8  261.36  4995.1  260.86  4998.9  261.36  5003.7  261.36
  5007.5  265.27  5028.4  266.57  5205.9  266.01  5356.0  264.17  5397.6  264.75
  5404.3  264.53  5411.9  262.74  5425.6  265.26  5489.7  265.97  5500.9  265.13
  5531.9  263.97  5564.4  264.61  5737.4  269.12  5984.7  281.54  6063.4  284.68
#Mann=13,-1,0
  3869.0    0.07       0  3931.6   0.035       0  3945.8    0.12       0
  4075.0   0.035       0  4081.1    0.12       0  4648.5   0.035       0
  4814.6    0.12       0  4994.8    0.05       0  4998.9    0.12       0
  5356.0   0.035       0  5500.9    0.12       0  5564.4   0.035       0
  5984.7    0.05       0
Bank Sta=4994.8,4998.9
Exp/Cntr=0.3,0.1

Type RM Length L Ch R = 1,1471,355,355,355
BEGIN DESCRIPTION:
XS7010
END DESCRIPTION:
XS GIS Cut Line= 3
      2479169.78     13655372.91      2477997.92     13654716.67
      2476909.72     13655523.71
#Sta/Elev= 30
  3756.1  308.83  3800.8  307.21  3830.3  305.35  3860.7  306.17  3905.1  303.30
  3971.7  302.39  4094.6  297.84  4251.7  288.15  4538.3  272.27  4637.8  267.88
  4748.8  265.69  4770.4  263.98  4859.8  263.65  4976.5  263.99  4986.1  262.18
  5007.8  261.61  5029.5  264.18  5115.3  262.67  5207.1  264.44  5472.1  265.32
  5657.8  262.90  5700.4  263.77  5714.1  263.31  5720.5  260.93  5720.7  260.43
  5724.6  260.93  5830.6  263.45  5979.1  266.36  6329.7  279.25  6454.0  281.77
#Mann=12,-1,0
  3756.1   0.035       0  3800.8    0.07       0  3860.7   0.035       0
  3971.7    0.07       0  4251.7    0.12       0  4538.3    0.07       0
  4637.8   0.035       0  4748.8    0.07       0  4859.8    0.12       0
  5720.5    0.05       0  5724.6    0.12       0  5830.6    0.05       0
Bank Sta=5720.5,5724.6
Exp/Cntr=0.3,0.1

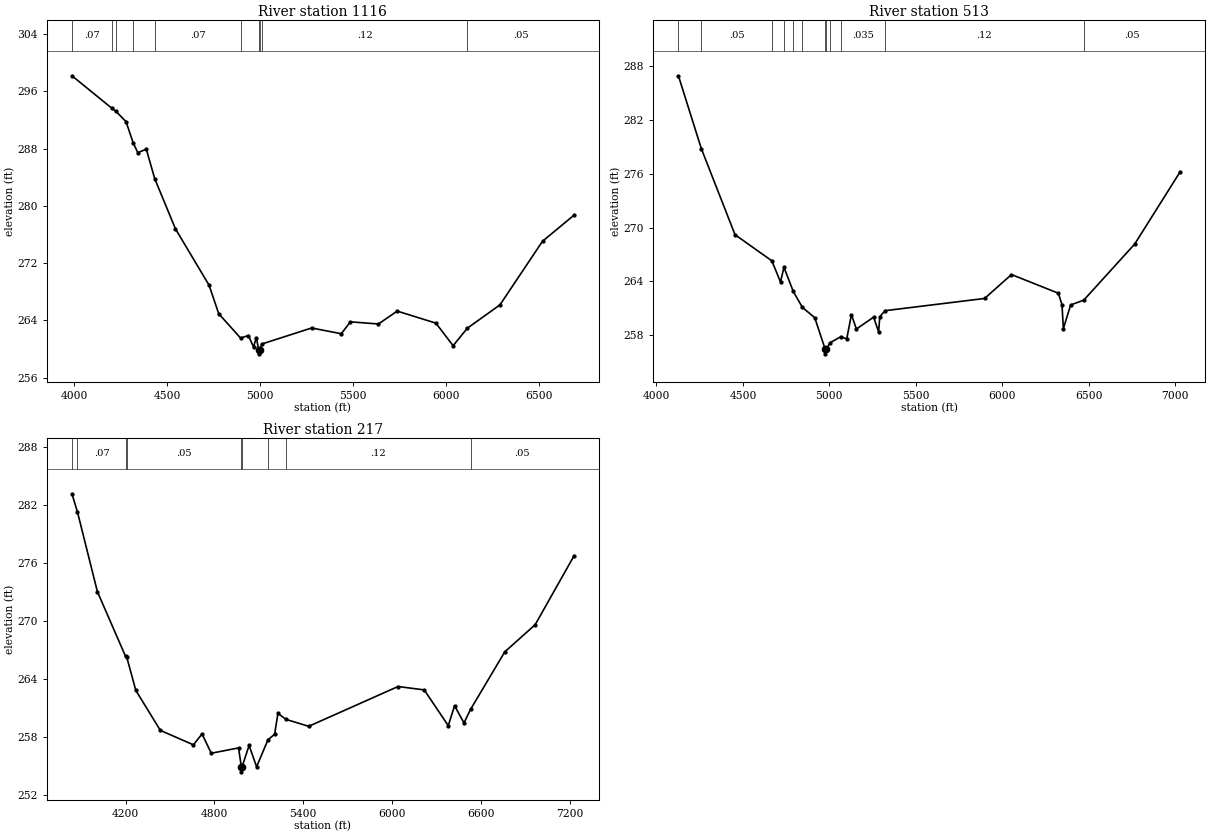
Type RM Length L Ch R = 1,1116,603,603,603
BEGIN DESCRIPTION:
XS7009
END DESCRIPTION:
XS GIS Cut Line= 3
      2479169.81     13655081.26      2478258.33     13654487.50
      2476945.86     13655419.77
#Sta/Elev= 30
  3987.6  298.18  4201.9  293.65  4223.4  293.23  4278.4  291.77  4317.2  288.77
  4341.7  287.44  4387.1  287.93  4432.5  283.81  4543.9  276.80  4725.0  268.91
  4776.4  264.95  4893.7  261.55  4936.2  261.90  4963.5  260.29  4978.6  261.62
  4991.6  259.84  4991.9  259.34  4995.8  259.84  5009.0  260.72  5275.8  262.95
  5435.2  262.15  5484.3  263.81  5635.0  263.51  5735.8  265.31  5943.7  263.63
  6036.3  260.48  6113.2  262.93  6288.1  266.18  6516.9  275.07  6685.3  278.69
#Mann=10,-1,0
  3987.6    0.07       0  4201.9   0.035       0  4223.4    0.07       0
  4317.2   0.035       0  4432.5    0.07       0  4893.7   0.035       0
  4991.6   0.035       0  4995.8   0.035       0  5009.0    0.12       0
  6113.2    0.05       0
Bank Sta=4991.6,4995.8
Exp/Cntr=0.3,0.1

Type RM Length L Ch R = 1,513,296,296,296
BEGIN DESCRIPTION:
Stream0515 1.0
END DESCRIPTION:
XS GIS Cut Line= 3
      2479375.03     13654425.01      2478575.00     13654075.00
      2476975.03     13655324.98
#Sta/Elev= 30
  4126.8  286.88  4259.1  278.79  4454.3  269.20  4667.2  266.30  4717.4  263.94
  4737.3  265.58  4791.1  262.90  4843.4  261.13  4915.5  259.97  4976.1  256.45
  4976.4  255.95  4980.4  256.45  5005.5  257.20  5066.8  257.86  5100.4  257.60
  5127.6  260.31  5156.5  258.71  5256.0  260.03  5284.9  258.40  5291.9  260.08
  5322.3  260.75  5898.1  262.11  6053.7  264.77  6325.0  262.69  6345.8  261.41
  6353.9  258.76  6395.9  261.39  6471.6  261.92  6766.4  268.16  7030.4  276.23
#Mann=12,-1,0
  4126.8    0.07       0  4259.1    0.05       0  4667.2    0.07       0
  4737.3    0.05       0  4791.1    0.07       0  4843.4     0.1       0
  4976.1    0.05       0  4980.4     0.1       0  5005.5    0.07       0
  5066.8   0.035       0  5322.3    0.12       0  6471.6    0.05       0
Bank Sta=4976.1,4980.4
Exp/Cntr=0.3,0.1

Type RM Length L Ch R = 1,217,0,0,0
BEGIN DESCRIPTION:
XS7008
END DESCRIPTION:
XS GIS Cut Line= 4
      2479669.79     13654076.04      2478617.71     13653773.96
      2478070.83     13654159.38      2476930.64     13655320.39
#Sta/Elev= 30
  3837.6  283.14  3875.0  281.25  4009.3  273.04  4200.2  266.34  4208.1  266.26
  4269.1  262.84  4434.8  258.71  4658.0  257.22  4716.5  258.34  4778.9  256.35
  4963.1  256.90  4982.3  254.93  4982.5  254.43  4986.6  254.93  5034.5  257.16
  5085.0  254.95  5161.9  257.74  5206.9  258.31  5229.1  260.46  5284.8  259.84
  5437.1  259.13  6040.7  263.24  6217.5  262.89  6380.0  259.20  6422.5  261.25
  6486.2  259.48  6530.3  260.87  6761.9  266.82  6967.1  269.62  7228.5  276.70
#Mann=9,-1,0
  3837.6    0.12       0  3875.0    0.07       0  4200.2   0.035       0
  4208.1    0.05       0  4982.3    0.05       0  4986.6    0.05       0
  5161.9   0.035       0  5284.8    0.12       0  6530.3    0.05       0
Bank Sta=4982.3,4986.6
Exp/Cntr=0.3,0.1

Chan Stop Cuts=-1