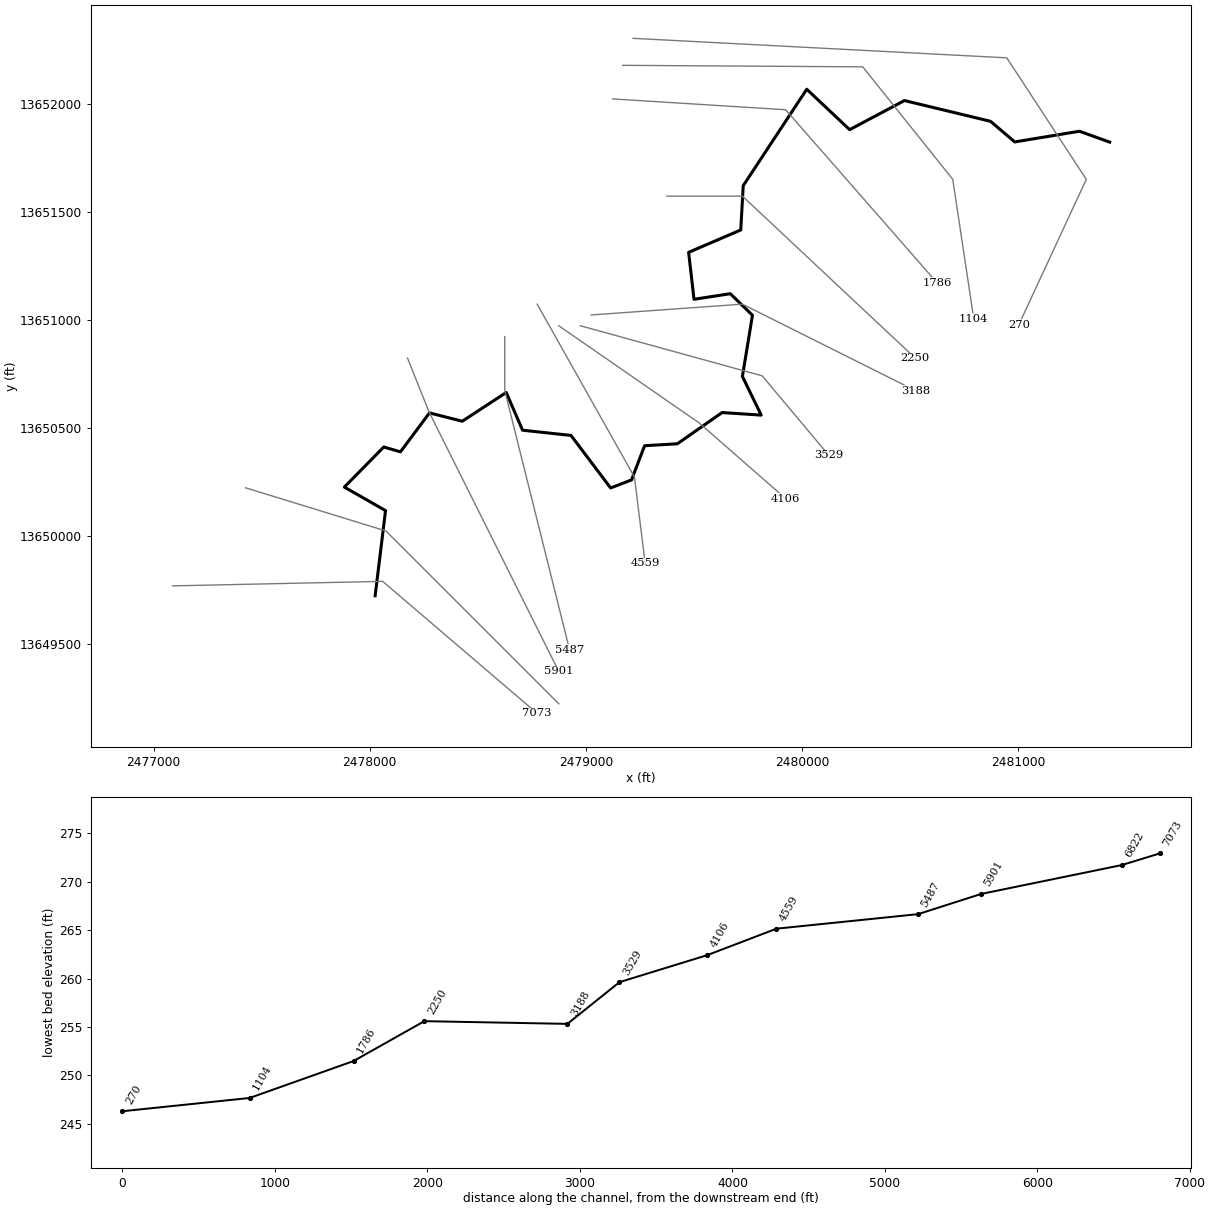
--- Stream0516.prj (project) ---

Proj Title=Stream0516 Base Level Engineering
Current Plan=p01
Default Exp/Contr=0.3,0.1
English Units
Geom File=g01
Flow File=f01
Plan File=p01
BEGIN DESCRIPTION:
Stream0516
END DESCRIPTION:

--- Stream0516.p01 (plan) ---

Plan Title=Multiple Run
Short Identifier=Multiple
Geom File=g01
Flow File=f01
Subcritical Flow
K Sum by GR= 0
Std Step Tol= 0.01
Critical Tol= 0.01
Num of Std Step Trials= 20
Max Error Tol= 0.3
Flow Tol Ratio= 0.001
Split Flow NTrial= 30
Split Flow Tol= 0.02
Split Flow Ratio= 0.02
Log Output Level= 0
Friction Slope Method= 1
Unsteady Friction Slope Method= 2
Unsteady Bridges Friction Slope Method= 1
Parabolic Critical Depth
Global Vel Dist=  1 , 1 , 1
Global Log Level= 0
CheckData=True
Encroach Param= -1, 0, 0, 0
BEGIN DESCRIPTION:
Multiple Run
END DESCRIPTION:

--- Stream0516.f01 (steady flow) ---

Flow Title=Multiple
Number of Profiles=7
Profile Names=10-year,25-year,50-year,1pct_min,100-year,1pct_plu,500-year
River Rch & RM= Stream0516,Reach-1,7073
     910    1494    2031    1337    2667    5322    4555
Boundary for River Rch & Prof#=Stream0516,Reach-1,1
Up Type=0
Dn Type=3
Dn Slope=0.005
Boundary for River Rch & Prof#=Stream0516,Reach-1,2
Up Type=0
Dn Type=3
Dn Slope=0.005
Boundary for River Rch & Prof#=Stream0516,Reach-1,3
Up Type=0
Dn Type=3
Dn Slope=0.005
Boundary for River Rch & Prof#=Stream0516,Reach-1,4
Up Type=0
Dn Type=3
Dn Slope=0.005
Boundary for River Rch & Prof#=Stream0516,Reach-1,5
Up Type=0
Dn Type=3
Dn Slope=0.005
Boundary for River Rch & Prof#=Stream0516,Reach-1,6
Up Type=0
Dn Type=3
Dn Slope=0.005
Boundary for River Rch & Prof#=Stream0516,Reach-1,7
Up Type=0
Dn Type=3
Dn Slope=0.005

--- Stream0516.g01 (geometry) ---

Geom Title=Existing Conditions

River Reach=Stream0516,Reach-1
Reach XY= 30
      2478025.00     13649725.00      2478073.12     13650119.31
      2477882.50     13650228.13      2478065.01     13650413.75
      2478142.04     13650391.24      2478276.49     13650571.54
      2478428.32     13650533.04      2478631.71     13650666.04
      2478707.38     13650491.43      2478931.48     13650467.31
      2479114.91     13650224.13      2479211.77     13650261.27
      2479272.27     13650419.65      2479423.53     13650428.55
      2479631.11     13650573.20      2479812.04     13650561.30
      2479724.96     13650740.34      2479771.47     13651023.55
      2479668.97     13651123.38      2479501.03     13651097.50
      2479475.98     13651314.74      2479717.33     13651418.48
      2479728.75     13651623.45      2480022.70     13652069.94
      2480221.34     13651882.67      2480474.99     13652017.47
      2480873.50     13651921.38      2480985.48     13651825.94
      2481285.19     13651875.46      2481425.00     13651825.00

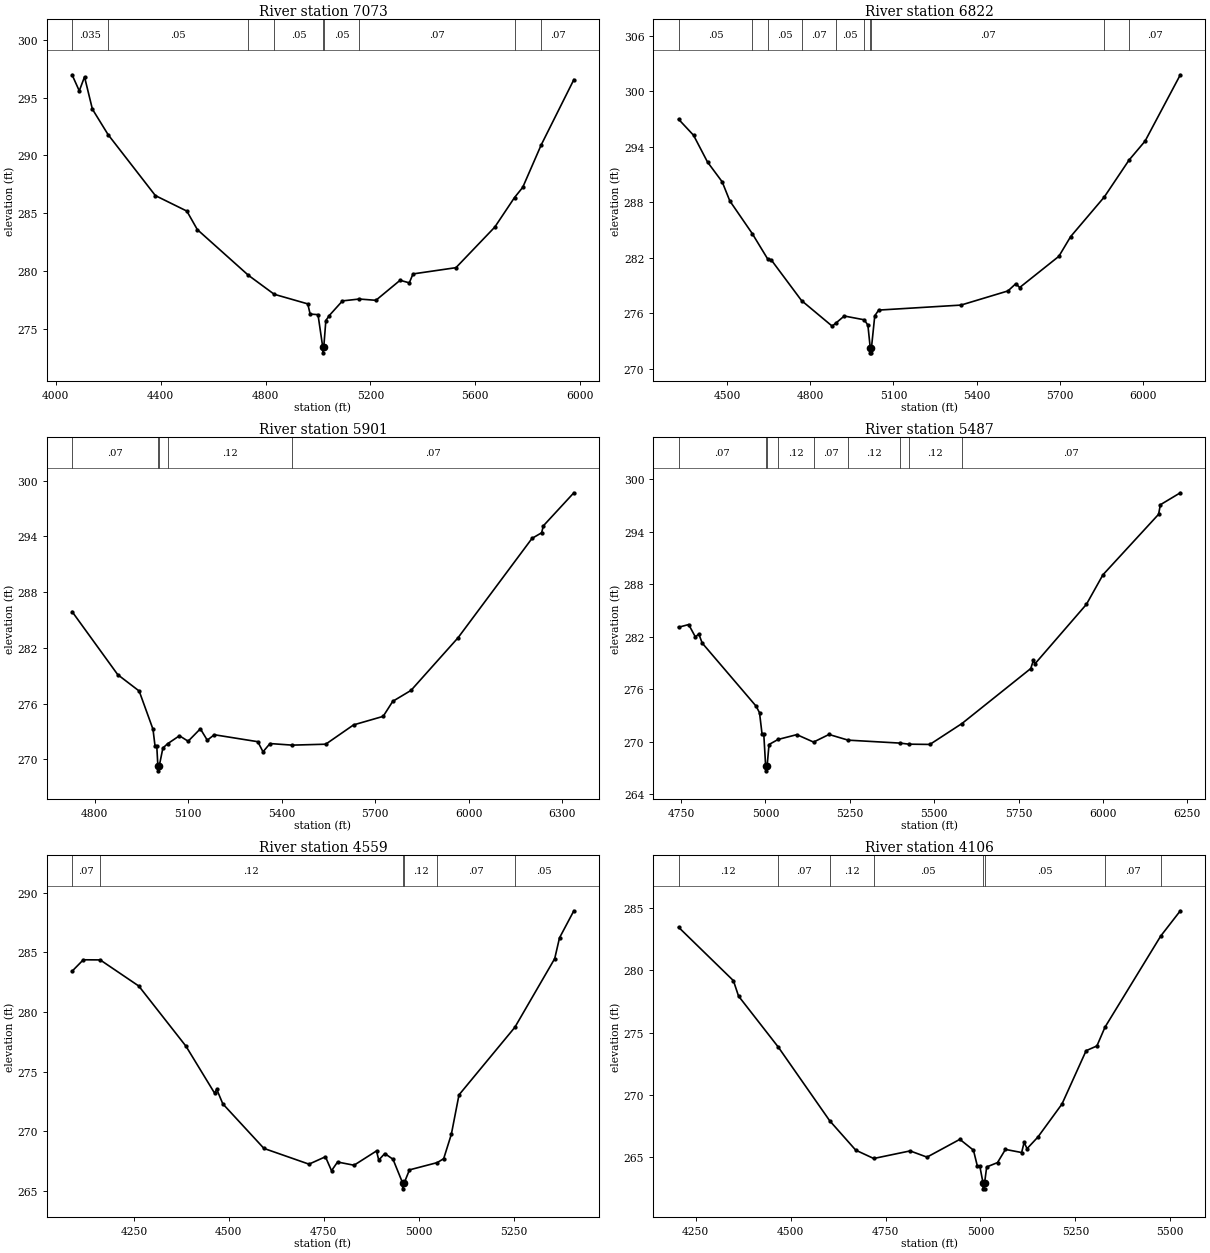
Type RM Length L Ch R = 1,7073,251,251,251
BEGIN DESCRIPTION:
XS7013
END DESCRIPTION:
XS GIS Cut Line= 3
      2477087.49     13649770.83      2478059.72     13649791.67
      2478774.97     13649180.58
#Sta/Elev= 30
  4062.3  296.97  4089.8  295.58  4109.8  296.79  4139.8  294.00  4199.6  291.80
  4379.9  286.53  4499.9  285.19  4539.9  283.59  4734.7  279.64  4833.1  278.00
  4961.0  277.17  4970.0  276.29  5000.0  276.24  5018.0  273.44  5018.3  272.94
  5022.0  273.44  5029.9  275.73  5042.8  276.16  5093.3  277.43  5157.4  277.59
  5220.7  277.48  5312.9  279.21  5348.0  278.99  5362.3  279.76  5525.9  280.30
  5674.1  283.81  5749.2  286.36  5780.5  287.24  5851.0  290.91  5975.5  296.55
#Mann=9,-1,0
  4062.3   0.035       0  4199.6    0.05       0  4734.7    0.07       0
  4833.1    0.05       0  5018.0    0.05       0  5022.0    0.05       0
  5157.4    0.07       0  5749.2    0.05       0  5851.0    0.07       0
Bank Sta=5018,5022
Exp/Cntr=0.3,0.1

Type RM Length L Ch R = 1,6822,921,921,921
BEGIN DESCRIPTION:
Stream0516 9.0
END DESCRIPTION:
XS GIS Cut Line= 3
      2477424.99     13650225.00      2478075.00     13650025.00
      2478875.03     13649224.97
#Sta/Elev= 30
  4324.0  296.98  4378.3  295.24  4428.6  292.35  4481.6  290.21  4509.1  288.15
  4590.1  284.62  4645.5  281.89  4658.8  281.77  4768.0  277.38  4878.5  274.62
  4892.2  274.95  4922.3  275.71  4994.5  275.30  5007.6  274.72  5016.2  272.23
  5016.5  271.73  5020.0  271.73  5020.3  272.23  5032.4  275.73  5046.5  276.35
  5343.5  276.89  5513.2  278.42  5541.5  279.20  5555.6  278.79  5697.0  282.16
  5739.5  284.29  5860.9  288.57  5950.3  292.56  6008.2  294.61  6135.5  301.78
#Mann=10,-1,0
  4324.0    0.05       0  4590.1    0.07       0  4645.5    0.05       0
  4768.0    0.07       0  4892.2    0.05       0  4994.5    0.07       0
  5016.2    0.05       0  5020.3    0.07       0  5860.9    0.05       0
  5950.3    0.07       0
Bank Sta=5016.2,5020.3
Exp/Cntr=0.3,0.1

Type RM Length L Ch R = 1,5901,414,414,414
BEGIN DESCRIPTION:
Stream0516 8.0
END DESCRIPTION:
XS GIS Cut Line= 3
      2478175.02     13650824.96      2478275.00     13650575.00
      2478875.02     13649374.96
#Sta/Elev= 30
  4727.0  285.91  4873.7  279.11  4942.4  277.35  4986.8  273.23  4993.5  271.38
  4999.0  271.38  5002.5  269.25  5002.7  268.75  5006.7  269.25  5018.6  271.21
  5033.7  271.67  5071.7  272.53  5099.6  271.94  5138.8  273.28  5161.1  272.05
  5183.5  272.64  5323.2  271.89  5340.0  270.80  5362.4  271.69  5433.5  271.52
  5541.3  271.62  5630.7  273.70  5725.7  274.62  5756.5  276.24  5815.2  277.42
  5966.1  283.09  6203.7  293.80  6234.4  294.40  6240.0  295.15  6337.9  298.71
#Mann=5,-1,0
  4727.0    0.07       0  5002.5    0.05       0  5006.7    0.07       0
  5033.7    0.12       0  5433.5    0.07       0
Bank Sta=5002.5,5006.7
Exp/Cntr=0.3,0.1

Type RM Length L Ch R = 1,5487,928,928,928
BEGIN DESCRIPTION:
Stream0516 7.0
END DESCRIPTION:
XS GIS Cut Line= 3
      2478625.00     13650925.01      2478625.00     13650675.00
      2478924.99     13649475.04
#Sta/Elev= 30
  4742.4  283.08  4772.4  283.39  4792.4  281.97  4802.4  282.32  4812.4  281.28
  4972.4  274.05  4982.4  273.30  4989.9  270.86  4995.0  270.86  5000.6  267.16
  5000.9  266.66  5004.8  267.16  5010.5  269.67  5037.4  270.25  5092.9  270.80
  5142.5  269.95  5188.3  270.82  5244.9  270.17  5399.7  269.83  5424.4  269.71
  5487.2  269.68  5582.2  272.07  5786.1  278.36  5793.8  279.28  5799.0  278.92
  5951.0  285.70  6000.0  289.08  6164.9  296.00  6170.1  297.09  6229.3  298.46
#Mann=9,-1,0
  4742.4    0.07       0  5000.6    0.05       0  5004.8    0.07       0
  5037.4    0.12       0  5142.5    0.07       0  5244.9    0.12       0
  5399.7    0.07       0  5424.4    0.12       0  5582.2    0.07       0
Bank Sta=5000.6,5004.8
Exp/Cntr=0.3,0.1

Type RM Length L Ch R = 1,4559,453,453,453
BEGIN DESCRIPTION:
Stream0516 6.0
END DESCRIPTION:
XS GIS Cut Line= 3
      2478775.01     13651074.99      2479225.00     13650275.00
      2479275.00     13649874.98
#Sta/Elev= 30
  4087.2  283.41  4116.8  284.37  4161.2  284.36  4262.8  282.17  4387.1  277.12
  4462.3  273.19  4468.0  273.51  4484.0  272.29  4592.3  268.55  4710.9  267.23
  4754.2  267.85  4770.2  266.68  4786.1  267.41  4829.5  267.14  4888.7  268.34
  4894.5  267.57  4910.4  268.12  4932.1  267.64  4957.3  265.66  4957.6  265.16
  4961.6  265.66  4975.4  266.75  5048.5  267.36  5065.5  267.69  5085.7  269.74
  5105.8  273.04  5252.9  278.71  5357.8  284.47  5370.4  286.21  5408.2  288.48
#Mann=6,-1,0
  4087.2    0.07       0  4161.2    0.12       0  4957.3    0.05       0
  4961.6    0.12       0  5048.5    0.07       0  5252.9    0.05       0
Bank Sta=4957.3,4961.6
Exp/Cntr=0.3,0.1

Type RM Length L Ch R = 1,4106,577,577,577
BEGIN DESCRIPTION:
Stream0516 5.0
END DESCRIPTION:
XS GIS Cut Line= 3
      2478875.02     13650974.99      2479525.00     13650525.00
      2479925.04     13650174.97
#Sta/Elev= 30
  4204.5  283.47  4349.1  279.17  4362.6  277.93  4467.3  273.83  4602.9  267.90
  4671.4  265.54  4718.8  264.87  4814.6  265.48  4859.2  264.98  4945.7  266.41
  4981.5  265.54  4992.0  264.24  4998.4  264.24  5006.6  262.93  5006.9  262.43
  5010.7  262.43  5011.0  262.93  5016.4  264.19  5044.9  264.54  5065.8  265.60
  5108.5  265.35  5115.1  266.17  5122.7  265.66  5151.2  266.59  5214.8  269.25
  5278.4  273.54  5306.8  273.92  5328.1  275.43  5475.2  282.77  5526.6  284.79
#Mann=8,-1,0
  4204.5    0.12       0  4467.3    0.07       0  4602.9    0.12       0
  4718.8    0.05       0  5006.6    0.05       0  5011.0    0.05       0
  5328.1    0.07       0  5475.2    0.05       0
Bank Sta=5006.6,5011
Exp/Cntr=0.3,0.1

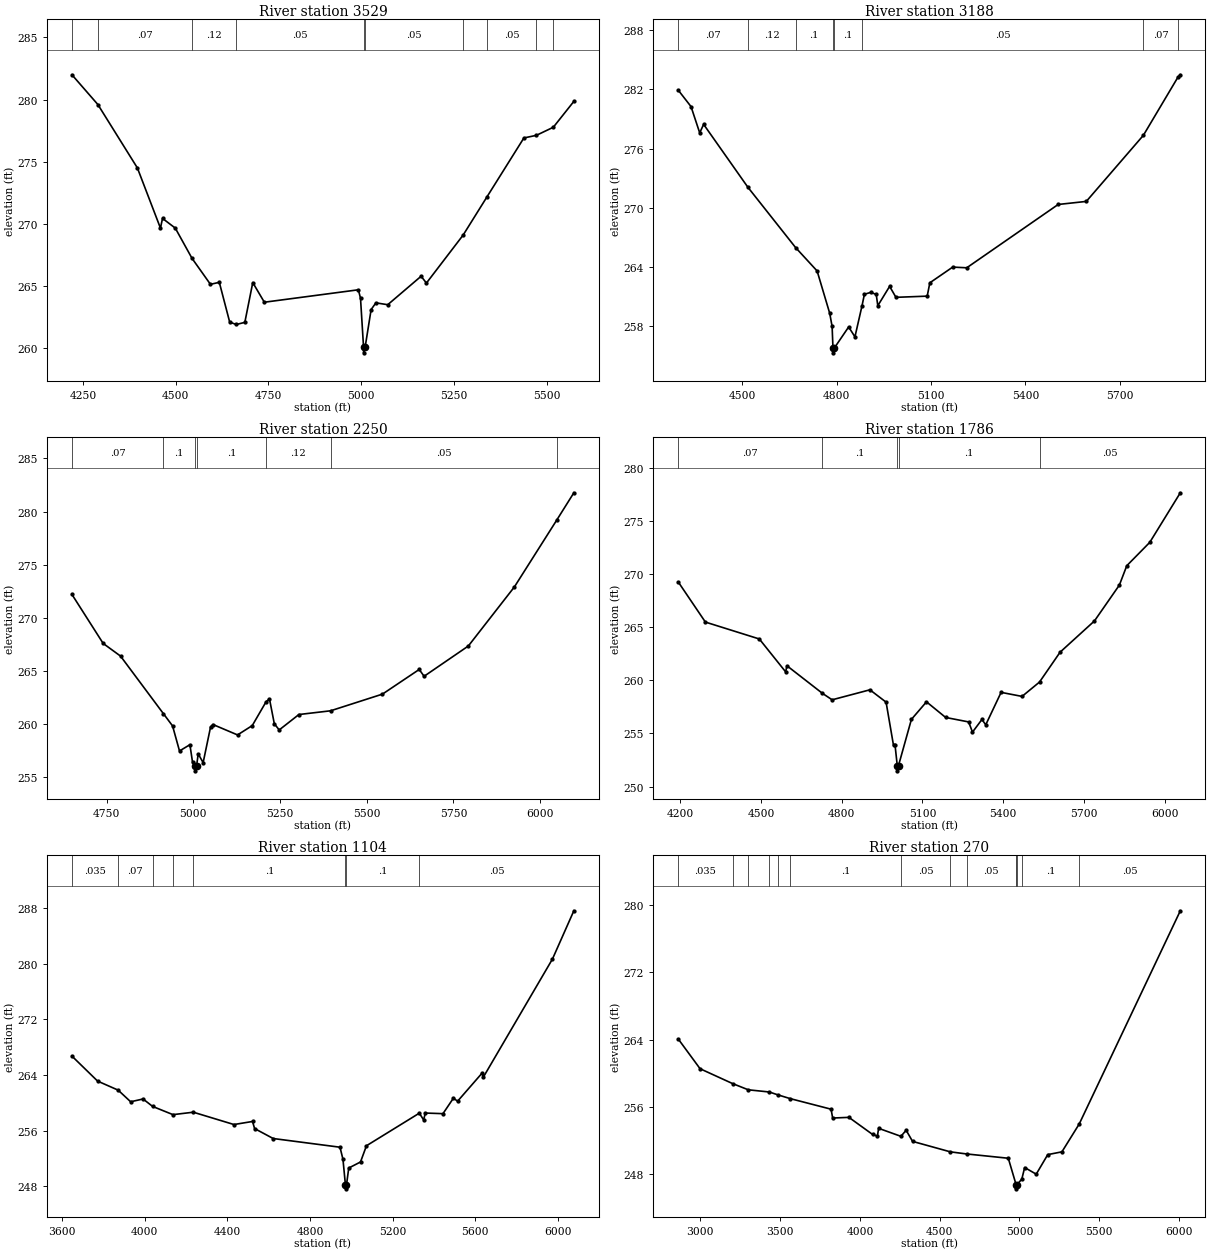
Type RM Length L Ch R = 1,3529,341,341,341
BEGIN DESCRIPTION:
Stream0516 4.0
END DESCRIPTION:
XS GIS Cut Line= 3
      2478974.97     13650975.01      2479816.67     13650743.06
      2480124.99     13650375.01
#Sta/Elev= 30
  4220.4  281.99  4290.2  279.60  4396.8  274.50  4459.0  269.66  4464.6  270.44
  4499.0  269.66  4544.1  267.23  4593.8  265.14  4617.7  265.30  4645.7  262.10
  4663.5  261.91  4686.5  262.08  4707.9  265.28  4739.1  263.70  4992.6  264.70
  4998.4  264.02  5006.5  260.13  5006.8  259.63  5011.1  260.13  5027.0  263.11
  5039.9  263.65  5071.8  263.50  5161.8  265.79  5176.1  265.24  5275.1  269.10
  5338.9  272.15  5438.9  276.91  5472.5  277.12  5518.2  277.77  5573.6  279.85
#Mann=10,-1,0
  4220.4    0.12       0  4290.2    0.07       0  4544.1    0.12       0
  4663.5    0.05       0  5006.5    0.05       0  5011.1    0.05       0
  5275.1    0.07       0  5338.9    0.05       0  5472.5    0.07       0
  5518.2    0.05       0
Bank Sta=5006.5,5011.1
Exp/Cntr=0.3,0.1

Type RM Length L Ch R = 1,3188,938,938,938
BEGIN DESCRIPTION:
Stream0516 3.0
END DESCRIPTION:
XS GIS Cut Line= 3
      2479024.98     13651025.00      2479725.00     13651075.00
      2480524.98     13650675.01
#Sta/Elev= 30
  4296.6  281.89  4336.7  280.25  4364.3  277.59  4376.8  278.45  4517.4  272.09
  4669.2  265.98  4737.7  263.61  4777.8  259.32  4785.4  257.99  4788.1  255.82
  4788.4  255.32  4792.7  255.82  4838.0  257.94  4858.0  256.94  4880.7  260.11
  4888.1  261.25  4908.2  261.44  4925.7  261.24  4930.7  260.09  4968.3  262.05
  4988.4  260.94  5087.8  261.06  5096.2  262.41  5168.9  264.00  5213.6  263.93
  5504.3  270.34  5593.8  270.65  5775.3  277.34  5884.7  283.20  5892.8  283.47
#Mann=8,-1,0
  4296.6    0.07       0  4517.4    0.12       0  4669.2     0.1       0
  4788.1    0.05       0  4792.7     0.1       0  4880.7    0.05       0
  5775.3    0.07       0  5884.7    0.05       0
Bank Sta=4788.1,4792.7
Exp/Cntr=0.3,0.1

Type RM Length L Ch R = 1,2250,464,464,464
BEGIN DESCRIPTION:
Stream0516 2.0
END DESCRIPTION:
XS GIS Cut Line= 3
      2479375.00     13651575.00      2479725.00     13651575.00
      2480525.01     13650824.99
#Sta/Elev= 30
  4650.4  272.20  4740.4  267.59  4790.4  266.40  4913.8  260.99  4940.4  259.83
  4960.4  257.47  4990.4  258.06  4997.9  256.42  5005.1  256.10  5005.5  255.60
  5009.8  256.10  5014.3  257.20  5028.5  256.37  5050.0  259.74  5056.8  259.96
  5127.7  258.98  5170.1  259.86  5209.9  262.10  5219.7  262.37  5233.7  260.03
  5247.8  259.45  5304.5  260.90  5395.7  261.25  5545.3  262.82  5651.3  265.14
  5665.4  264.50  5792.9  267.35  5925.6  272.91  6047.5  279.19  6097.0  281.77
#Mann=7,-1,0
  4650.4    0.07       0  4913.8     0.1       0  5005.1    0.05       0
  5009.8     0.1       0  5209.9    0.12       0  5395.7    0.05       0
  6047.5    0.07       0
Bank Sta=5005.1,5009.8
Exp/Cntr=0.3,0.1

Type RM Length L Ch R = 1,1786,682,682,682
BEGIN DESCRIPTION:
Stream0516 1.0
END DESCRIPTION:
XS GIS Cut Line= 3
      2479125.00     13652025.00      2479925.00     13651975.00
      2480625.02     13651174.98
#Sta/Elev= 30
  4193.5  269.22  4293.7  265.47  4494.1  263.88  4591.8  260.79  4596.8  261.36
  4728.4  258.77  4764.6  258.16  4904.9  259.10  4965.0  257.94  4992.6  253.87
  4998.4  253.87  5006.5  251.98  5006.8  251.48  5011.2  251.98  5059.1  256.32
  5115.1  257.97  5186.3  256.50  5271.7  256.08  5286.0  255.12  5321.1  256.31
  5335.3  255.81  5392.3  258.86  5470.1  258.48  5535.0  259.83  5611.5  262.64
  5739.2  265.58  5831.7  268.95  5859.2  270.77  5944.7  272.97  6058.1  277.63
#Mann=5,-1,0
  4193.5    0.07       0  4728.4     0.1       0  5006.5    0.05       0
  5011.2     0.1       0  5535.0    0.05       0
Bank Sta=5006.5,5011.2
Exp/Cntr=0.3,0.1

Type RM Length L Ch R = 1,1104,834,834,834
BEGIN DESCRIPTION:
XS7012
END DESCRIPTION:
XS GIS Cut Line= 4
      2479170.81     13652180.56      2480281.94     13652173.61
      2480698.61     13651652.78      2480795.60     13651008.49
#Sta/Elev= 30
  3647.4  266.73  3771.6  263.14  3871.1  261.84  3931.6  260.17  3991.6  260.57
  4038.0  259.50  4136.5  258.32  4234.9  258.67  4431.6  256.90  4521.6  257.34
  4531.6  256.32  4621.6  254.89  4945.0  253.64  4959.4  251.90  4971.5  248.16
  4971.8  247.66  4976.2  248.16  4987.3  250.65  5044.3  251.52  5073.1  253.85
  5328.9  258.53  5350.0  257.56  5358.0  258.55  5443.5  258.46  5494.1  260.69
  5514.3  260.25  5633.5  264.31  5638.6  263.69  5973.4  280.67  6077.1  287.61
#Mann=8,-1,0
  3647.4   0.035       0  3871.1    0.07       0  4038.0    0.12       0
  4136.5    0.07       0  4234.9     0.1       0  4971.5    0.05       0
  4976.2     0.1       0  5328.9    0.05       0
Bank Sta=4971.5,4976.2
Exp/Cntr=0.3,0.1

Type RM Length L Ch R = 1,270,0,0,0
BEGIN DESCRIPTION:
XS7011
END DESCRIPTION:
XS GIS Cut Line= 4
      2479219.49     13652305.55      2480948.61     13652215.28
      2481316.67     13651652.78      2481004.36     13650979.58
#Sta/Elev= 30
  2862.4  264.04  2998.1  260.54  3201.7  258.78  3300.4  258.04  3432.2  257.78
  3485.9  257.44  3563.9  256.99  3819.2  255.74  3829.2  254.69  3931.1  254.77
  4079.6  252.74  4109.6  252.55  4117.2  253.47  4257.0  252.52  4289.8  253.24
  4329.9  251.92  4566.5  250.68  4668.1  250.43  4930.0  249.92  4978.6  246.80
  4978.9  246.79  4979.2  246.29  4983.7  246.79  5014.5  247.43  5032.6  248.82
  5105.0  248.03  5177.3  250.35  5266.1  250.68  5374.4  253.98  6008.2  279.28
#Mann=14,-1,0
  2862.4   0.035       0  3201.7    0.07       0  3300.4    0.12       0
  3432.2     0.1       0  3485.9    0.12       0  3563.9     0.1       0
  4257.0    0.05       0  4566.5   0.035       0  4668.1    0.05       0
  4978.6    0.07       0  4978.9    0.05       0  4983.7    0.07       0
  5014.5     0.1       0  5374.4    0.05       0
Bank Sta=4978.9,4983.7
Exp/Cntr=0.3,0.1

Chan Stop Cuts=-1