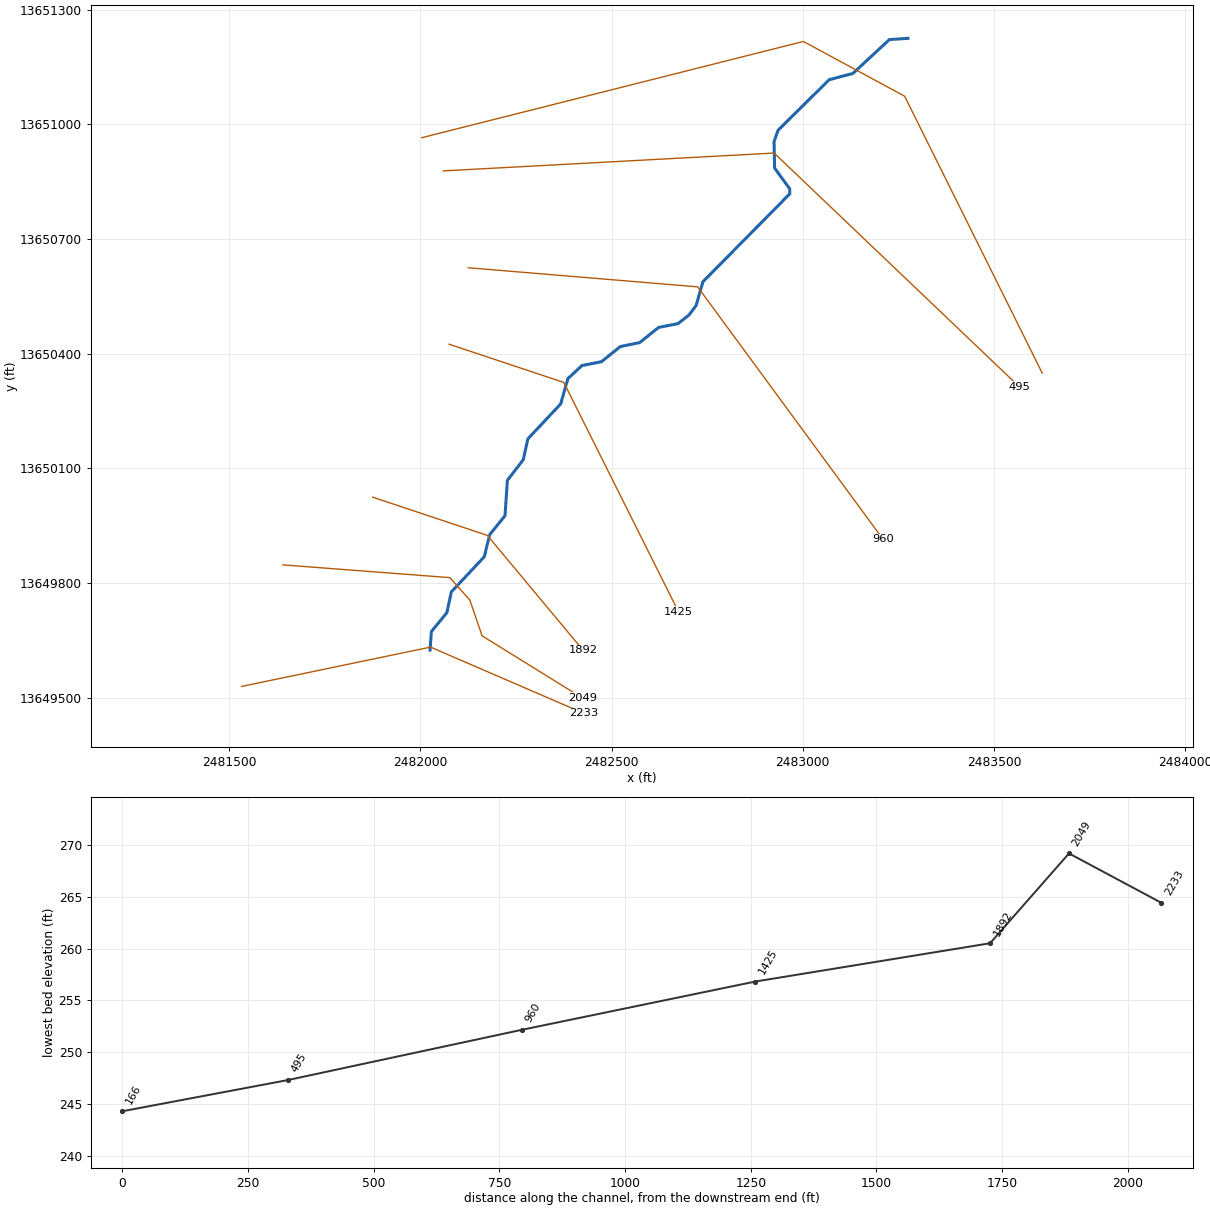
--- Stream0517.prj (project) ---

Proj Title=Stream0517 Base Level Engineering
Current Plan=p01
Default Exp/Contr=0.3,0.1
English Units
Geom File=g01
Flow File=f01
Plan File=p01
BEGIN DESCRIPTION:
Stream0517
END DESCRIPTION:

--- Stream0517.p01 (plan) ---

Plan Title=Multiple Run
Short Identifier=Multiple
Geom File=g01
Flow File=f01
Subcritical Flow
K Sum by GR= 0
Std Step Tol= 0.01
Critical Tol= 0.01
Num of Std Step Trials= 20
Max Error Tol= 0.3
Flow Tol Ratio= 0.001
Split Flow NTrial= 30
Split Flow Tol= 0.02
Split Flow Ratio= 0.02
Log Output Level= 0
Friction Slope Method= 1
Unsteady Friction Slope Method= 2
Unsteady Bridges Friction Slope Method= 1
Parabolic Critical Depth
Global Vel Dist=  1 , 1 , 1
Global Log Level= 0
CheckData=True
Encroach Param= -1, 0, 0, 0
BEGIN DESCRIPTION:
Multiple Run
END DESCRIPTION:

--- Stream0517.f01 (steady flow) ---

Flow Title=Multiple
Number of Profiles=7
Profile Names=10-year,25-year,50-year,1pct_min,100-year,1pct_plu,500-year
River Rch & RM= Stream0517,Reach-1,2233
     334     518     679     432     863    1722    1377
Boundary for River Rch & Prof#=Stream0517,Reach-1,1
Up Type=0
Dn Type=3
Dn Slope=0.005
Boundary for River Rch & Prof#=Stream0517,Reach-1,2
Up Type=0
Dn Type=3
Dn Slope=0.005
Boundary for River Rch & Prof#=Stream0517,Reach-1,3
Up Type=0
Dn Type=3
Dn Slope=0.005
Boundary for River Rch & Prof#=Stream0517,Reach-1,4
Up Type=0
Dn Type=3
Dn Slope=0.005
Boundary for River Rch & Prof#=Stream0517,Reach-1,5
Up Type=0
Dn Type=3
Dn Slope=0.005
Boundary for River Rch & Prof#=Stream0517,Reach-1,6
Up Type=0
Dn Type=3
Dn Slope=0.005
Boundary for River Rch & Prof#=Stream0517,Reach-1,7
Up Type=0
Dn Type=3
Dn Slope=0.005

--- Stream0517.g01 (geometry) ---

Geom Title=Existing Conditions

River Reach=Stream0517,Reach-1
Reach XY= 30
      2482025.00     13649625.00      2482028.60     13649673.51
      2482069.03     13649722.76      2482080.83     13649777.30
      2482166.84     13649868.95      2482181.14     13649927.17
      2482221.17     13649976.58      2482227.33     13650069.03
      2482268.86     13650122.83      2482280.84     13650177.29
      2482366.81     13650268.98      2482385.65     13650335.00
      2482422.45     13650369.27      2482473.24     13650379.20
      2482522.80     13650418.92      2482573.28     13650429.16
      2482622.84     13650468.89      2482673.58     13650478.86
      2482702.14     13650501.16      2482721.11     13650526.43
      2482738.64     13650588.20      2482965.87     13650818.26
      2482965.71     13650831.53      2482926.27     13650885.48
      2482924.80     13650954.94      2482935.44     13650984.79
      2483068.95     13651116.84      2483131.05     13651133.16
      2483226.36     13651221.71      2483275.00     13651225.00

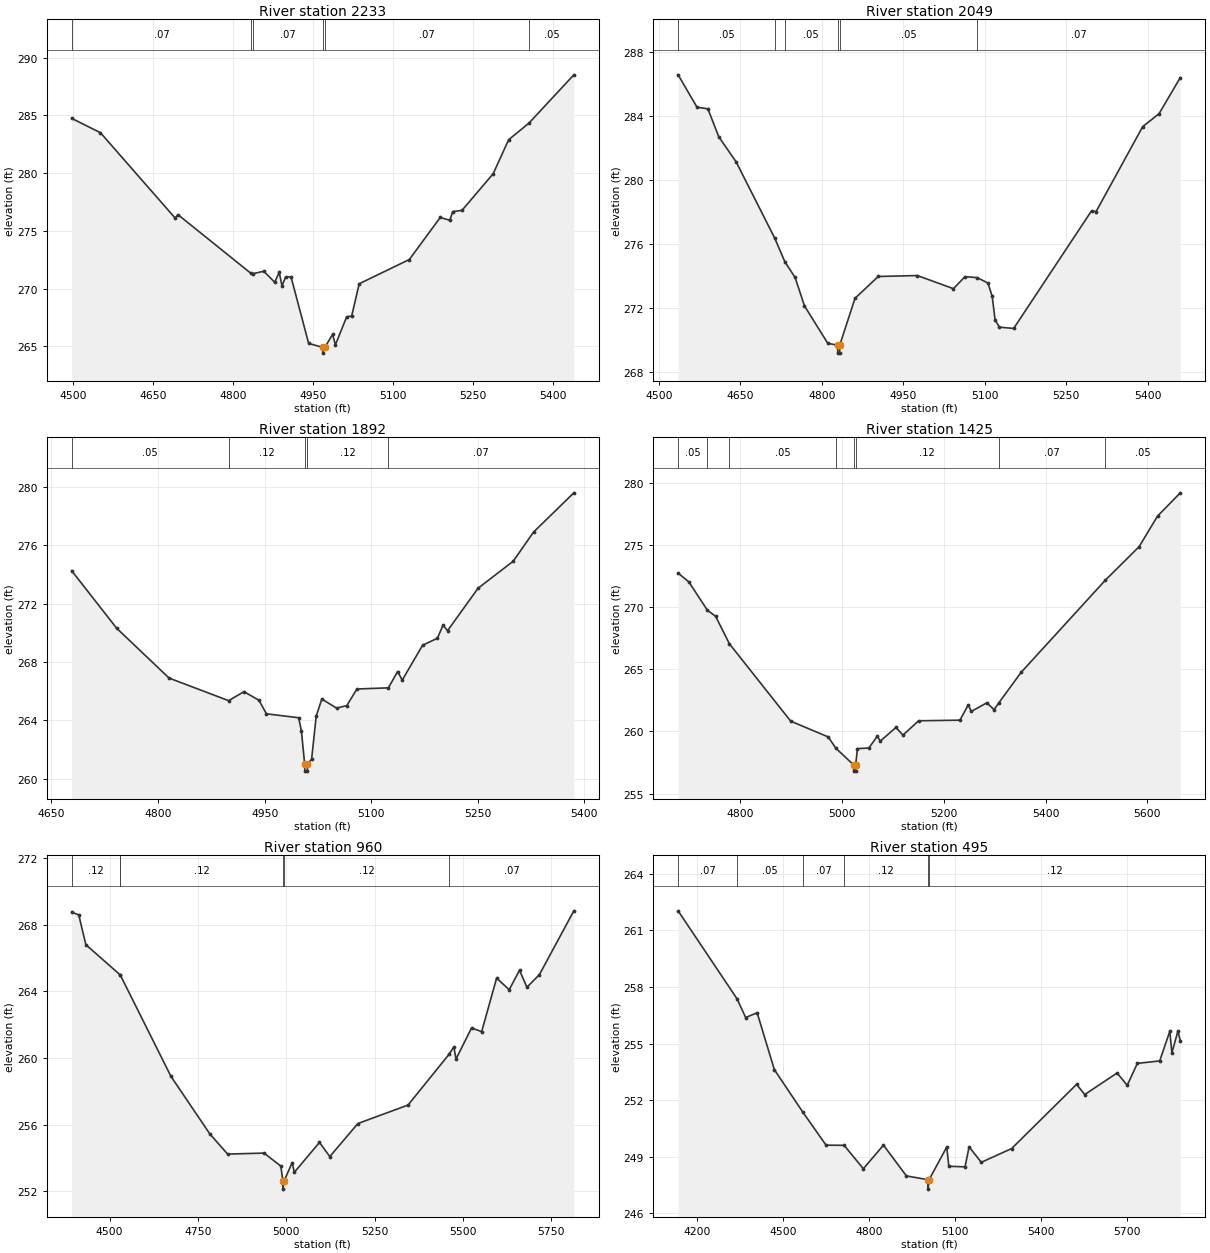
Type RM Length L Ch R = 1,2233,184,184,184
BEGIN DESCRIPTION:
XS7015
END DESCRIPTION:
XS GIS Cut Line= 3
      2481532.16     13649529.98      2482026.37     13649632.83
      2482427.53     13649459.51
#Sta/Elev= 30
  4496.8  284.75  4550.9  283.50  4690.9  276.11  4696.1  276.41  4833.1  271.32
  4837.0  271.30  4857.2  271.50  4877.6  270.55  4886.1  271.41  4891.3  270.23
  4898.1  271.02  4908.3  271.00  4941.3  265.25  4967.6  264.91  4967.8  264.41
  4971.6  264.91  4986.3  266.04  4991.4  265.12  5012.6  267.56  5021.9  267.62
  5036.1  270.42  5130.1  272.52  5188.0  276.16  5206.0  275.92  5211.5  276.67
  5228.9  276.78  5287.4  279.96  5316.4  282.90  5354.3  284.33  5438.6  288.52
#Mann=6,-1,0
  4496.8    0.07       0  4833.1    0.05       0  4837.0    0.07       0
  4967.6    0.05       0  4971.6    0.07       0  5354.3    0.05       0
Bank Sta=4967.6,4971.6
Exp/Cntr=0.3,0.1

Type RM Length L Ch R = 1,2049,157,157,157
BEGIN DESCRIPTION:
E21129
END DESCRIPTION:
XS GIS Cut Line= 5
      2481640.31     13649847.89      2482077.13     13649814.50
      2482129.23     13649755.72      2482161.29     13649662.22
      2482423.83     13649499.62
#Sta/Elev= 30
  4535.6  286.55  4570.4  284.53  4590.4  284.43  4610.5  282.68  4642.4  281.12
  4713.3  276.37  4732.2  274.88  4750.9  273.91  4768.1  272.14  4811.1  269.80
  4829.1  269.69  4829.4  269.19  4832.9  269.19  4833.1  269.69  4861.2  272.61
  4903.9  273.97  4975.9  274.03  5042.4  273.21  5063.6  273.96  5086.2  273.90
  5105.9  273.56  5113.7  272.73  5119.0  271.26  5127.0  270.81  5153.2  270.73
  5296.6  278.07  5304.9  278.02  5390.7  283.32  5420.7  284.12  5459.9  286.38
#Mann=6,-1,0
  4535.6    0.05       0  4713.3    0.07       0  4732.2    0.05       0
  4829.1    0.05       0  4833.1    0.05       0  5086.2    0.07       0
Bank Sta=4829.1,4833.1
Exp/Cntr=0.3,0.1

Type RM Length L Ch R = 1,1892,467,467,467
BEGIN DESCRIPTION:
Stream0517 4.0
END DESCRIPTION:
XS GIS Cut Line= 3
      2481874.97     13650025.01      2482175.00     13649925.00
      2482425.02     13649624.98
#Sta/Elev= 30
  4678.4  274.25  4741.7  270.31  4815.5  266.89  4899.4  265.34  4920.9  265.96
  4942.0  265.37  4952.5  264.44  4997.9  264.17  5001.8  263.25  5006.3  261.01
  5006.6  260.51  5010.1  260.51  5010.3  261.01  5016.1  261.32  5022.6  264.28
  5030.5  265.45  5051.3  264.83  5065.6  265.00  5079.9  266.14  5124.2  266.22
  5137.2  267.34  5143.7  266.75  5172.3  269.14  5193.2  269.62  5201.0  270.51
  5207.5  270.14  5250.4  273.05  5299.9  274.90  5328.5  276.90  5385.2  279.59
#Mann=5,-1,0
  4678.4    0.05       0  4899.4    0.12       0  5006.3    0.05       0
  5010.3    0.12       0  5124.2    0.07       0
Bank Sta=5006.3,5010.3
Exp/Cntr=0.3,0.1

Type RM Length L Ch R = 1,1425,465,465,465
BEGIN DESCRIPTION:
Stream0517 3.0
END DESCRIPTION:
XS GIS Cut Line= 3
      2482075.04     13650424.99      2482375.00     13650325.00
      2482675.00     13649725.01
#Sta/Elev= 30
  4677.9  272.74  4698.9  272.04  4735.5  269.75  4751.6  269.27  4778.6  267.06
  4899.2  260.83  4973.0  259.56  4988.0  258.65  5022.8  257.31  5023.1  256.81
  5026.6  256.81  5026.8  257.31  5030.4  258.62  5052.8  258.67  5069.6  259.63
  5075.1  259.22  5105.9  260.32  5119.9  259.71  5150.6  260.86  5231.7  260.91
  5248.4  262.15  5254.0  261.61  5284.8  262.31  5298.8  261.75  5308.7  262.33
  5351.9  264.75  5517.3  272.16  5583.8  274.86  5620.2  277.33  5664.9  279.20
#Mann=8,-1,0
  4677.9    0.05       0  4735.5    0.07       0  4778.6    0.05       0
  4988.0    0.12       0  5022.8    0.05       0  5026.8    0.12       0
  5308.7    0.07       0  5517.3    0.05       0
Bank Sta=5022.8,5026.8
Exp/Cntr=0.3,0.1

Type RM Length L Ch R = 1,960,465,465,465
BEGIN DESCRIPTION:
Stream0517 2.0
END DESCRIPTION:
XS GIS Cut Line= 3
      2482124.98     13650625.00      2482725.00     13650575.00
      2483209.91     13649914.73
#Sta/Elev= 30
  4392.6  268.74  4412.7  268.58  4432.8  266.79  4530.0  264.98  4530.8  264.95
  4673.6  258.90  4784.0  255.44  4834.1  254.24  4937.0  254.30  4984.7  253.52
  4990.2  252.64  4990.4  252.14  4994.2  252.64  5016.7  253.73  5022.9  253.15
  5094.0  254.94  5123.2  254.09  5202.6  256.07  5344.7  257.18  5460.3  260.21
  5474.3  260.66  5480.5  259.94  5524.4  261.80  5553.0  261.58  5595.4  264.79
  5630.9  264.09  5660.2  265.26  5681.1  264.24  5716.6  265.00  5813.9  268.82
#Mann=6,-1,0
  4392.6    0.12       0  4530.0    0.05       0  4530.8    0.12       0
  4990.2    0.05       0  4994.2    0.12       0  5460.3    0.07       0
Bank Sta=4990.2,4994.2
Exp/Cntr=0.3,0.1

Type RM Length L Ch R = 1,495,329,329,329
BEGIN DESCRIPTION:
Stream0517 1.0
END DESCRIPTION:
XS GIS Cut Line= 3
      2482059.74     13650878.30      2482925.00     13650925.00
      2483565.81     13650314.05
#Sta/Elev= 30
  4134.3  262.03  4339.8  257.37  4369.9  256.38  4410.0  256.63  4470.0  253.62
  4569.3  251.37  4650.3  249.62  4713.4  249.61  4780.5  248.37  4850.6  249.62
  4930.7  247.99  5005.9  247.79  5006.1  247.29  5009.9  247.79  5071.4  249.52
  5078.7  248.50  5135.3  248.47  5149.4  249.53  5191.9  248.71  5297.9  249.44
  5524.4  252.84  5552.7  252.30  5665.6  253.44  5701.1  252.79  5736.3  253.95
  5814.3  254.08  5849.6  255.65  5856.8  254.51  5877.9  255.66  5886.2  255.15
#Mann=6,-1,0
  4134.3    0.07       0  4339.8    0.05       0  4569.3    0.07       0
  4713.4    0.12       0  5005.9    0.05       0  5009.9    0.12       0
Bank Sta=5005.9,5009.9
Exp/Cntr=0.3,0.1

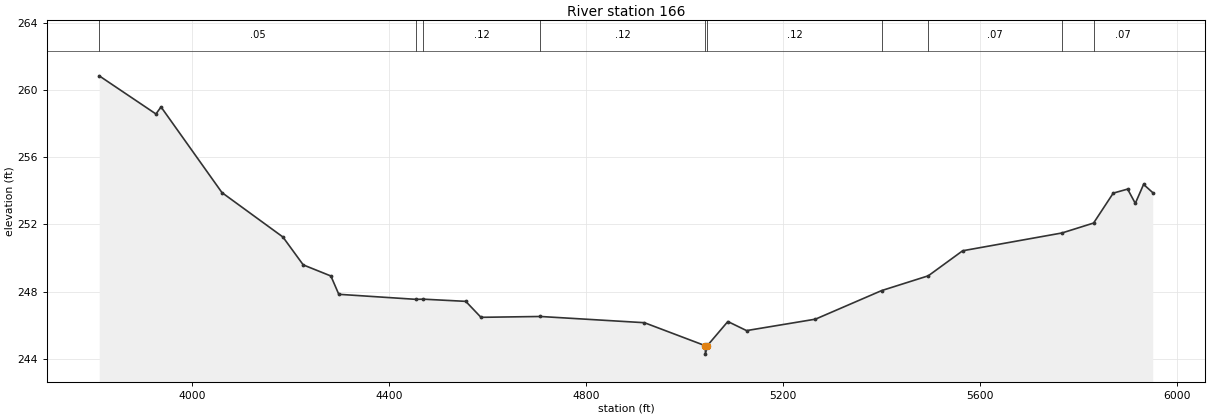
Type RM Length L Ch R = 1,166,0,0,0
BEGIN DESCRIPTION:
XS7014
END DESCRIPTION:
XS GIS Cut Line= 4
      2482003.31     13650965.11      2483001.56     13651216.84
      2483266.32     13651073.61      2483626.28     13650349.35
#Sta/Elev= 30
  3811.7  260.84  3926.9  258.57  3937.2  258.99  4061.0  253.89  4184.7  251.25
  4226.0  249.59  4282.1  248.93  4298.2  247.84  4454.7  247.54  4470.1  247.55
  4556.0  247.42  4586.9  246.47  4707.5  246.52  4918.8  246.15  5042.4  244.78
  5042.7  244.28  5046.4  244.78  5088.2  246.22  5126.2  245.68  5266.0  246.36
  5400.4  248.06  5495.2  248.94  5565.0  250.43  5766.8  251.49  5830.9  252.08
  5870.8  253.86  5900.0  254.10  5915.6  253.25  5932.4  254.38  5951.0  253.89
#Mann=10,-1,0
  3811.7    0.05       0  4454.7    0.07       0  4470.1    0.12       0
  4707.5    0.12       0  5042.4    0.05       0  5046.4    0.12       0
  5400.4    0.12       0  5495.2    0.07       0  5766.8    0.12       0
  5830.9    0.07       0
Bank Sta=5042.4,5046.4
Exp/Cntr=0.3,0.1

Chan Stop Cuts=-1