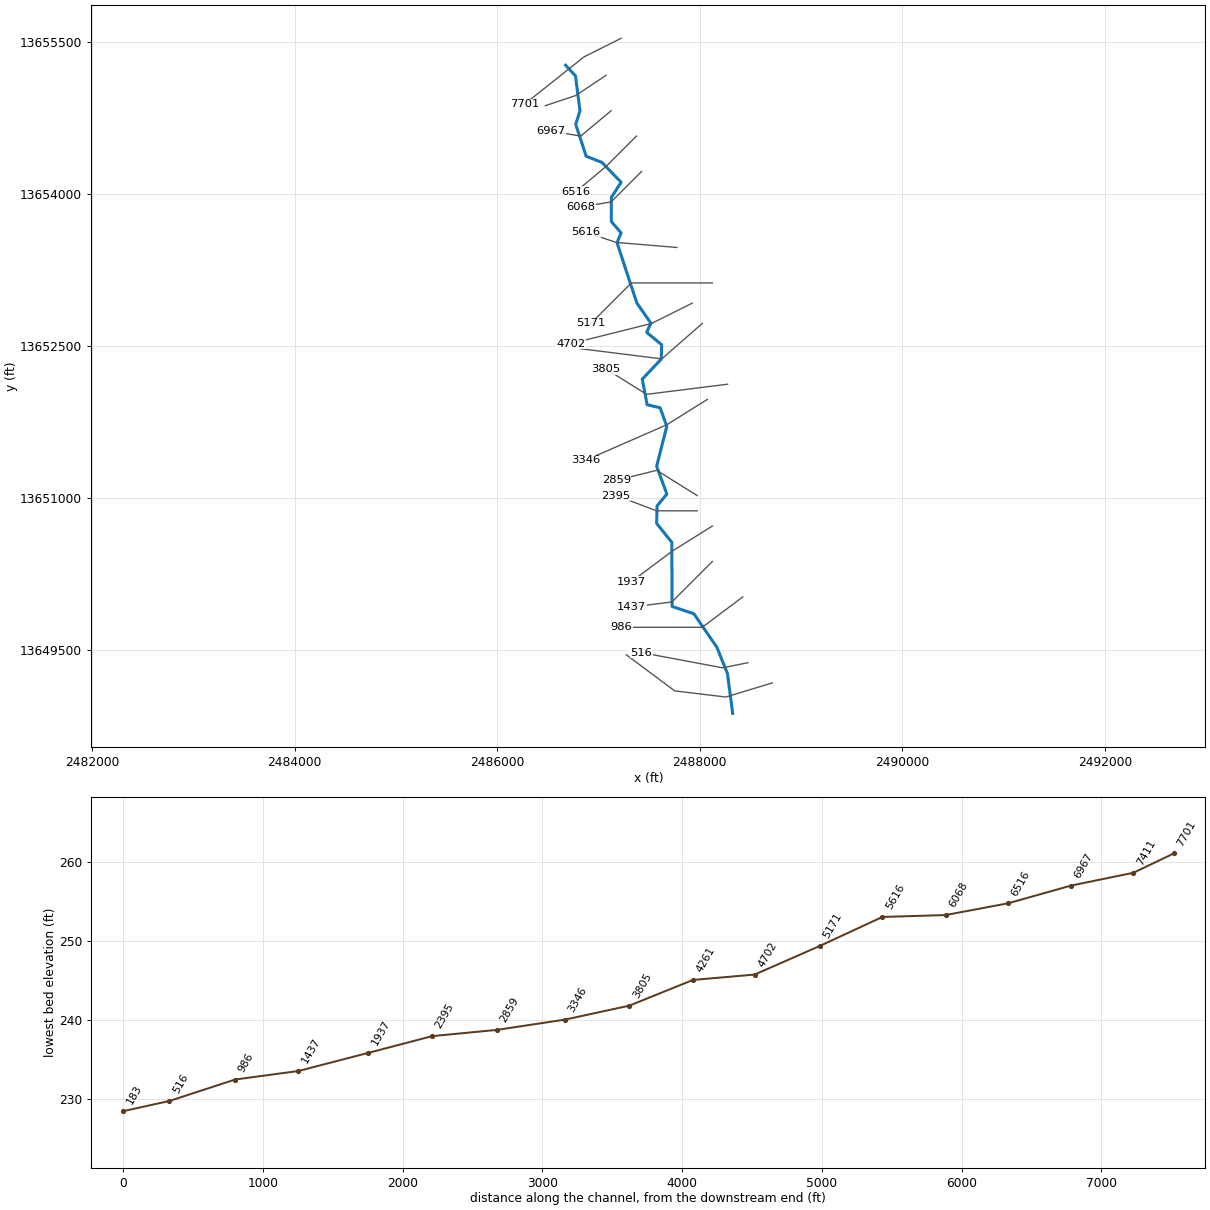
--- Stream0518.prj (project) ---

Proj Title=Stream0518 Base Level Engineering
Current Plan=p01
Default Exp/Contr=0.3,0.1
English Units
Geom File=g01
Flow File=f01
Plan File=p01
BEGIN DESCRIPTION:
Stream0518
END DESCRIPTION:

--- Stream0518.p01 (plan) ---

Plan Title=Multiple Run
Short Identifier=Multiple
Geom File=g01
Flow File=f01
Subcritical Flow
K Sum by GR= 0
Std Step Tol= 0.01
Critical Tol= 0.01
Num of Std Step Trials= 20
Max Error Tol= 0.3
Flow Tol Ratio= 0.001
Split Flow NTrial= 30
Split Flow Tol= 0.02
Split Flow Ratio= 0.02
Log Output Level= 0
Friction Slope Method= 1
Unsteady Friction Slope Method= 2
Unsteady Bridges Friction Slope Method= 1
Parabolic Critical Depth
Global Vel Dist=  1 , 1 , 1
Global Log Level= 0
CheckData=True
Encroach Param= -1, 0, 0, 0
BEGIN DESCRIPTION:
Multiple Run
END DESCRIPTION:

--- Stream0518.f01 (steady flow) ---

Flow Title=Multiple
Number of Profiles=7
Profile Names=10-year,25-year,50-year,1pct_min,100-year,1pct_plu,500-year
River Rch & RM= Stream0518,Reach-1,7701
     763    1243    1682    1103    2200    4390    3727
River Rch & RM= Stream0518,Reach-1,5171
     817    1325    1787    1166    2326    4641    3904
Boundary for River Rch & Prof#=Stream0518,Reach-1,1
Up Type=0
Dn Type=3
Dn Slope=0.005
Boundary for River Rch & Prof#=Stream0518,Reach-1,2
Up Type=0
Dn Type=3
Dn Slope=0.005
Boundary for River Rch & Prof#=Stream0518,Reach-1,3
Up Type=0
Dn Type=3
Dn Slope=0.005
Boundary for River Rch & Prof#=Stream0518,Reach-1,4
Up Type=0
Dn Type=3
Dn Slope=0.005
Boundary for River Rch & Prof#=Stream0518,Reach-1,5
Up Type=0
Dn Type=3
Dn Slope=0.005
Boundary for River Rch & Prof#=Stream0518,Reach-1,6
Up Type=0
Dn Type=3
Dn Slope=0.005
Boundary for River Rch & Prof#=Stream0518,Reach-1,7
Up Type=0
Dn Type=3
Dn Slope=0.005

--- Stream0518.g01 (geometry) ---

Geom Title=Existing Conditions

River Reach=Stream0518,Reach-1
Reach XY= 30
      2486675.00     13655275.00      2486772.98     13655169.16
      2486817.44     13654825.00      2486775.39     13654690.28
      2486878.51     13654376.25      2487034.78     13654314.48
      2487223.42     13654118.95      2487127.07     13653969.14
      2487127.07     13653730.86      2487223.33     13653618.95
      2487183.07     13653521.69      2487378.83     13652926.58
      2487517.16     13652728.38      2487476.22     13652637.03
      2487623.97     13652514.57      2487619.61     13652372.32
      2487432.33     13652175.10      2487480.46     13651922.00
      2487608.54     13651892.61      2487674.50     13651709.78
      2487574.50     13651314.83      2487675.04     13651040.34
      2487578.55     13650923.53      2487574.70     13650749.88
      2487723.95     13650564.57      2487726.97     13649930.65
      2487941.80     13649858.58      2488169.16     13649527.29
      2488273.18     13649268.88      2488325.00     13648875.00

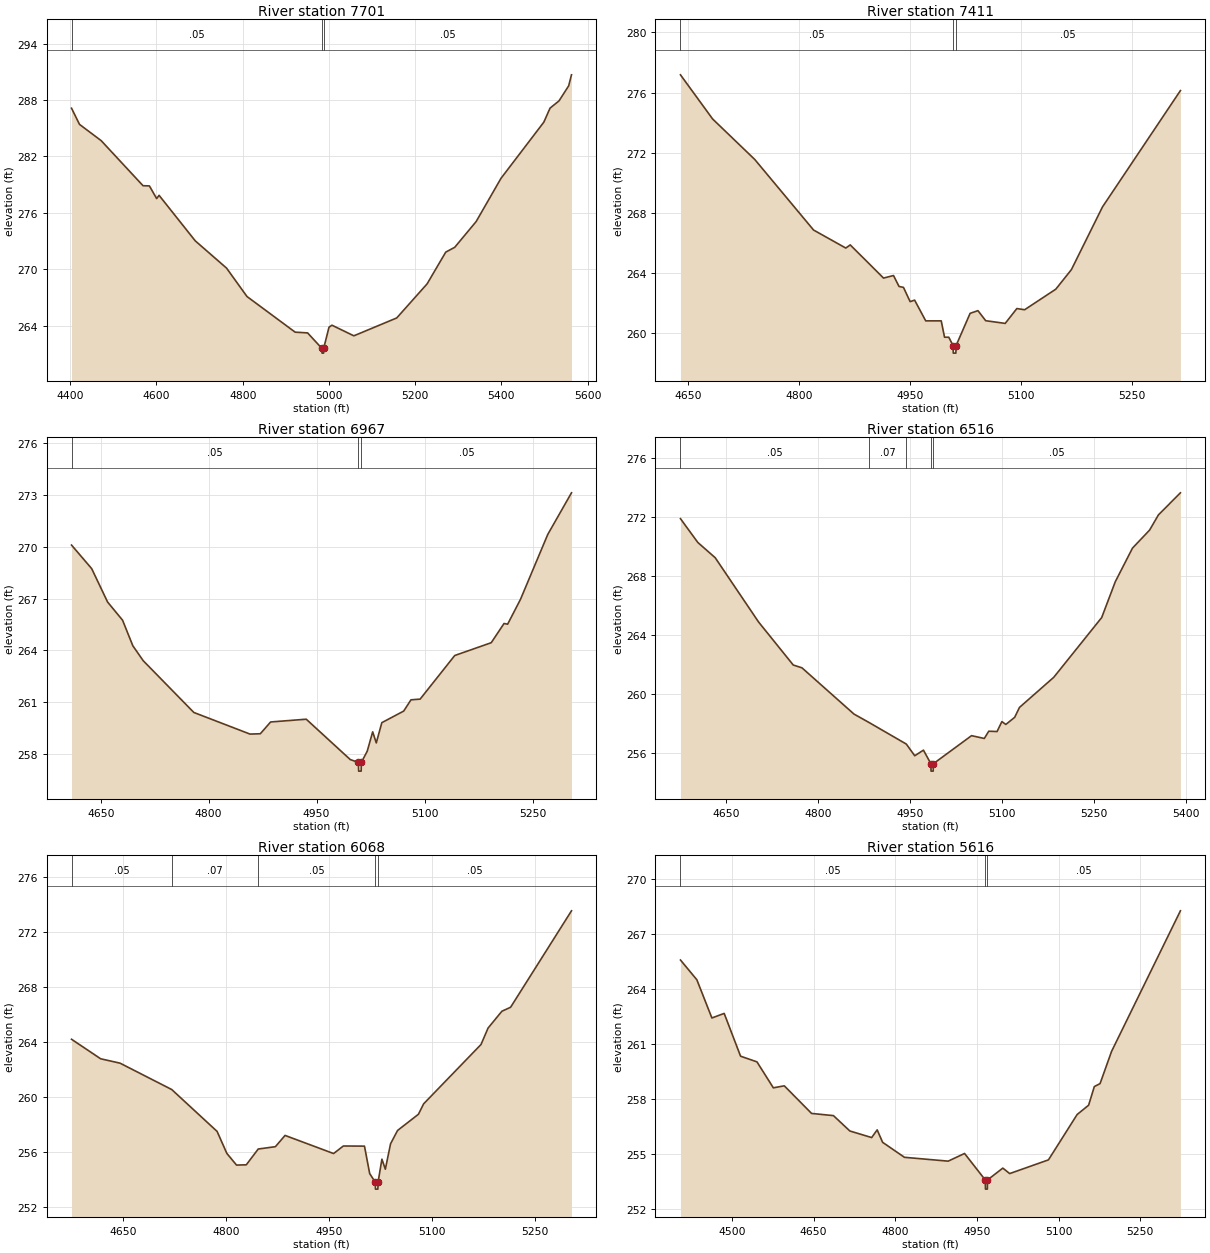
Type RM Length L Ch R = 1,7701,290,290,290
BEGIN DESCRIPTION:
XS7016
END DESCRIPTION:
XS GIS Cut Line= 3
      2487223.27     13655539.93      2486858.68     13655357.64
      2486269.88     13654890.06
#Sta/Elev= 30
  4403.0  287.13  4421.5  285.41  4471.8  283.68  4568.8  278.89  4583.6  278.87
  4600.4  277.52  4606.0  277.87  4689.9  273.03  4762.5  270.13  4809.9  267.11
  4921.6  263.32  4950.5  263.24  4983.7  261.59  4984.0  261.09  4987.5  261.09
  4987.7  261.59  5000.1  263.84  5006.9  264.06  5057.8  262.93  5157.2  264.83
  5227.6  268.45  5270.9  271.83  5291.7  272.34  5341.4  275.08  5399.1  279.68
  5498.4  285.65  5512.8  287.14  5533.6  287.91  5556.0  289.51  5562.5  290.68
#Mann=3,-1,0
  4403.0    0.05       0  4983.7    0.05       0  4987.7    0.05       0
Bank Sta=4983.7,4987.7
Exp/Cntr=0.3,0.1

Type RM Length L Ch R = 1,7411,444,444,444
BEGIN DESCRIPTION:
Stream0518 16.0
END DESCRIPTION:
XS GIS Cut Line= 3
      2487074.97     13655174.98      2486775.00     13654975.00
      2486474.95     13654874.98
#Sta/Elev= 30
  4639.4  277.18  4682.9  274.24  4740.0  271.54  4819.6  266.84  4863.2  265.64
  4869.2  265.85  4914.3  263.64  4927.8  263.81  4935.3  263.08  4941.3  263.02
  4950.3  262.07  4956.4  262.17  4971.4  260.79  4992.4  260.79  4996.9  259.70
  5002.6  259.70  5008.5  259.14  5008.7  258.64  5012.2  258.64  5012.5  259.14
  5031.5  261.29  5042.1  261.47  5052.6  260.80  5079.0  260.62  5094.8  261.61
  5105.3  261.53  5147.5  262.90  5168.6  264.20  5210.7  268.38  5316.2  276.13
#Mann=3,-1,0
  4639.4    0.05       0  5008.5    0.05       0  5012.5    0.05       0
Bank Sta=5008.5,5012.5
Exp/Cntr=0.3,0.1

Type RM Length L Ch R = 1,6967,451,451,451
BEGIN DESCRIPTION:
Stream0518 15.0
END DESCRIPTION:
XS GIS Cut Line= 3
      2487124.99     13654824.99      2486825.00     13654575.00
      2486525.04     13654624.99
#Sta/Elev= 30
  4609.5  270.09  4637.5  268.73  4659.6  266.80  4680.4  265.75  4694.7  264.27
  4709.1  263.41  4779.4  260.42  4857.5  259.17  4871.8  259.19  4886.1  259.87
  4935.6  260.03  4996.7  257.70  5008.1  257.53  5008.4  257.03  5011.9  257.03
  5012.1  257.53  5020.3  258.18  5027.9  259.30  5032.9  258.66  5040.6  259.83
  5071.0  260.50  5081.1  261.15  5093.8  261.19  5141.9  263.71  5192.6  264.45
  5210.4  265.56  5215.4  265.52  5233.2  266.95  5271.2  270.71  5304.1  273.11
#Mann=3,-1,0
  4609.5    0.05       0  5008.1    0.05       0  5012.1    0.05       0
Bank Sta=5008.1,5012.1
Exp/Cntr=0.3,0.1

Type RM Length L Ch R = 1,6516,448,448,448
BEGIN DESCRIPTION:
Stream0518 14.0
END DESCRIPTION:
XS GIS Cut Line= 3
      2487374.99     13654574.99      2487075.00     13654275.00
      2486774.97     13654024.98
#Sta/Elev= 30
  4576.0  271.87  4604.3  270.26  4632.6  269.23  4703.3  264.88  4759.8  261.97
  4774.0  261.78  4858.8  258.65  4882.5  258.10  4944.1  256.62  4957.8  255.83
  4972.0  256.21  4984.1  255.29  4984.4  254.79  4987.9  254.79  4988.1  255.29
  5050.4  257.19  5071.2  257.00  5078.4  257.49  5092.0  257.47  5099.8  258.14
  5106.3  257.95  5120.7  258.43  5128.5  259.10  5184.4  261.14  5262.5  265.18
  5284.7  267.61  5312.7  269.88  5340.6  271.10  5355.0  272.13  5390.8  273.62
#Mann=5,-1,0
  4576.0    0.05       0  4882.5    0.07       0  4944.1    0.05       0
  4984.1    0.05       0  4988.1    0.05       0
Bank Sta=4984.1,4988.1
Exp/Cntr=0.3,0.1

Type RM Length L Ch R = 1,6068,452,452,452
BEGIN DESCRIPTION:
Stream0518 13.0
END DESCRIPTION:
XS GIS Cut Line= 3
      2487425.01     13654225.01      2487125.00     13653925.00
      2486825.01     13653875.00
#Sta/Elev= 30
  4575.3  264.21  4617.7  262.79  4646.0  262.47  4721.3  260.55  4787.4  257.50
  4801.6  255.90  4815.7  255.05  4829.9  255.07  4847.3  256.22  4872.3  256.39
  4886.4  257.21  4957.1  255.89  4971.3  256.44  5002.1  256.43  5009.7  254.43
  5017.9  253.80  5018.1  253.30  5021.6  253.30  5021.9  253.80  5027.5  255.48
  5032.5  254.75  5040.1  256.60  5050.3  257.57  5080.7  258.75  5088.3  259.51
  5171.9  263.83  5182.1  265.02  5202.3  266.25  5215.0  266.54  5303.7  273.56
#Mann=5,-1,0
  4575.3    0.05       0  4721.3    0.07       0  4847.3    0.05       0
  5017.9    0.05       0  5021.9    0.05       0
Bank Sta=5017.9,5021.9
Exp/Cntr=0.3,0.1

Type RM Length L Ch R = 1,5616,445,445,445
BEGIN DESCRIPTION:
Stream0518 12.0
END DESCRIPTION:
XS GIS Cut Line= 3
      2487775.01     13653475.00      2487175.00     13653525.00
      2486875.01     13653625.00
#Sta/Elev= 30
  4405.6  265.59  4435.7  264.51  4463.3  262.42  4485.9  262.67  4516.0  260.33
  4546.1  260.02  4576.2  258.60  4596.3  258.71  4646.4  257.20  4686.6  257.08
  4716.7  256.24  4756.8  255.88  4766.9  256.30  4776.9  255.62  4817.0  254.80
  4897.3  254.59  4927.4  255.01  4965.5  253.56  4965.8  253.06  4969.3  253.06
  4969.5  253.56  4997.7  254.21  5010.3  253.91  5081.5  254.66  5134.2  257.14
  5155.3  257.65  5165.8  258.67  5176.3  258.83  5197.4  260.59  5323.9  268.28
#Mann=3,-1,0
  4405.6    0.05       0  4965.5    0.05       0  4969.5    0.05       0
Bank Sta=4965.5,4969.5
Exp/Cntr=0.3,0.1

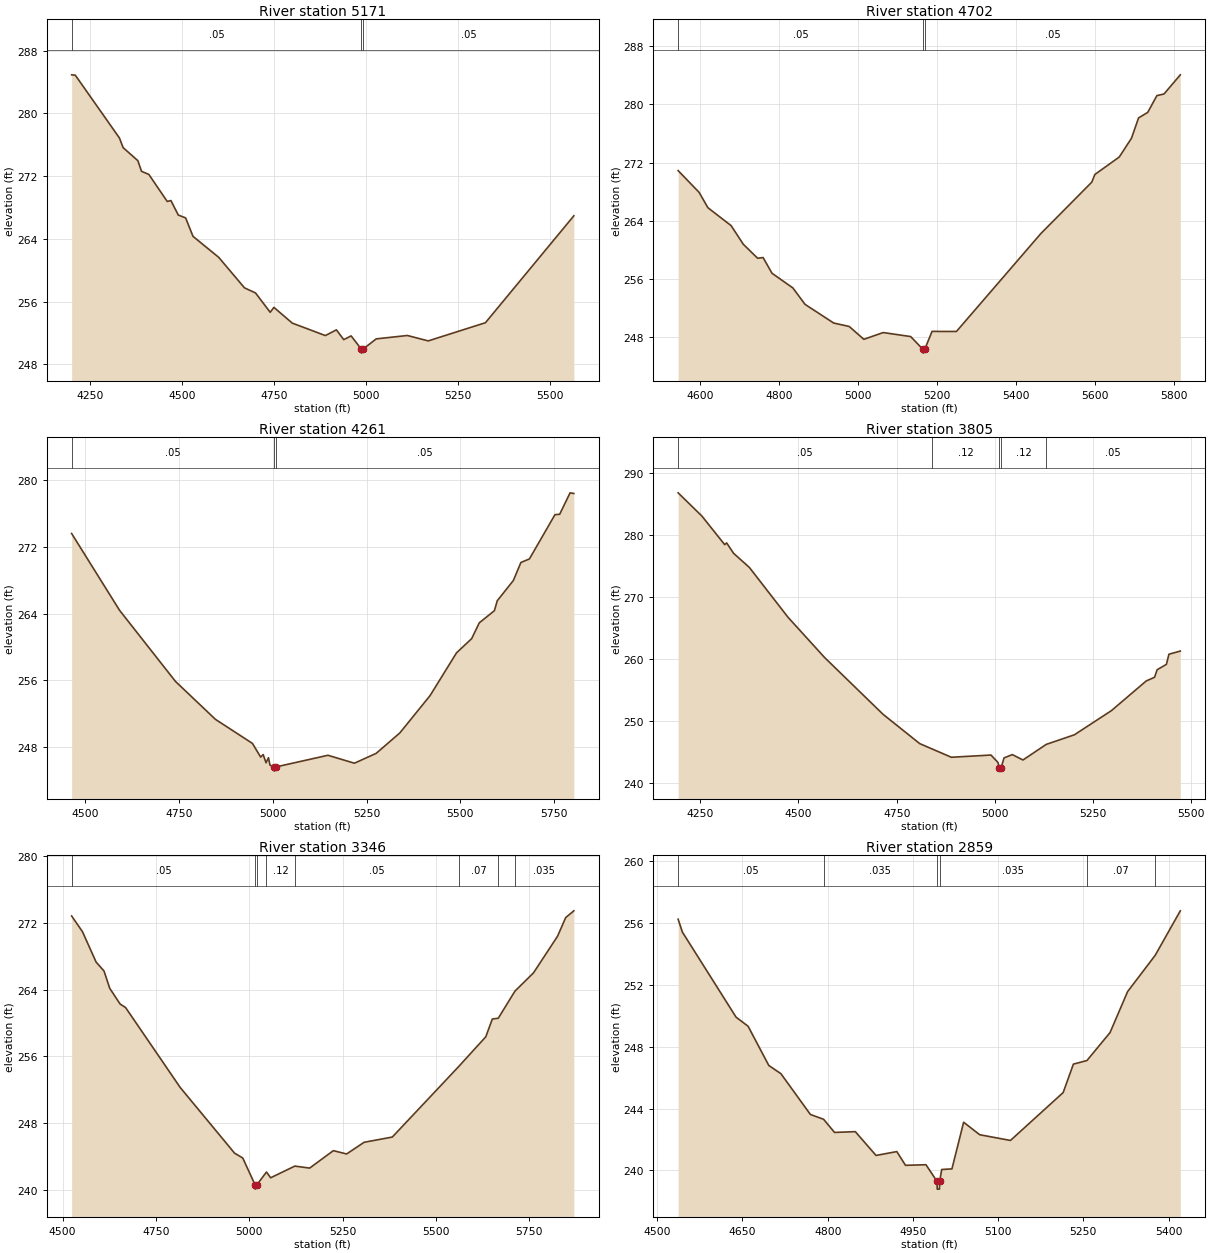
Type RM Length L Ch R = 1,5171,469,469,469
BEGIN DESCRIPTION:
Stream0518 11.0
END DESCRIPTION:
XS GIS Cut Line= 3
      2488125.00     13653125.00      2487325.00     13653125.00
      2486924.99     13652724.99
#Sta/Elev= 30
  4200.0  284.93  4210.0  284.88  4330.0  276.87  4340.0  275.64  4380.0  273.98
  4390.0  272.62  4410.0  272.22  4460.0  268.77  4470.0  268.89  4490.0  267.04
  4510.0  266.67  4530.0  264.32  4600.0  261.64  4670.0  257.75  4700.0  257.10
  4740.0  254.63  4750.0  255.26  4800.0  253.25  4890.0  251.66  4920.0  252.39
  4940.0  251.14  4960.0  251.62  4987.9  249.92  4988.2  249.42  4992.0  249.92
  5028.3  251.24  5113.1  251.67  5169.7  250.98  5325.3  253.30  5565.7  266.94
#Mann=3,-1,0
  4200.0    0.05       0  4987.9    0.05       0  4992.0    0.05       0
Bank Sta=4987.9,4992
Exp/Cntr=0.3,0.1

Type RM Length L Ch R = 1,4702,441,441,441
BEGIN DESCRIPTION:
Stream0518 10.0
END DESCRIPTION:
XS GIS Cut Line= 3
      2487925.04     13652925.02      2487525.00     13652725.00
      2486724.98     13652524.99
#Sta/Elev= 30
  4544.8  270.90  4597.9  267.91  4620.3  265.79  4679.0  263.33  4709.8  260.77
  4746.1  258.84  4760.1  258.93  4782.4  256.78  4835.5  254.75  4866.3  252.49
  4938.9  249.92  4978.1  249.45  5015.2  247.68  5064.2  248.61  5133.8  248.06
  5165.2  246.28  5165.5  245.78  5169.3  246.28  5187.9  248.77  5249.7  248.76
  5463.6  262.24  5592.5  269.31  5600.2  270.36  5662.1  272.77  5693.0  275.35
  5711.0  278.15  5734.2  278.91  5757.4  281.22  5775.4  281.44  5816.7  284.08
#Mann=3,-1,0
  4544.8    0.05       0  5165.2    0.05       0  5169.3    0.05       0
Bank Sta=5165.2,5169.3
Exp/Cntr=0.3,0.1

Type RM Length L Ch R = 1,4261,456,456,456
BEGIN DESCRIPTION:
Stream0518 9.0
END DESCRIPTION:
XS GIS Cut Line= 3
      2488025.01     13652725.01      2487625.00     13652375.00
      2486825.05     13652474.99
#Sta/Elev= 30
  4464.6  273.59  4592.3  264.38  4741.3  255.85  4847.6  251.31  4946.3  248.42
  4968.1  246.78  4974.8  247.09  4982.4  246.10  4989.0  246.71  4992.8  245.82
  5004.1  245.60  5004.4  245.10  5008.3  245.60  5147.3  247.00  5217.8  246.05
  5275.8  247.23  5338.8  249.68  5419.4  254.16  5489.9  259.29  5530.2  260.99
  5550.4  262.88  5590.7  264.34  5598.3  265.53  5641.1  267.95  5661.3  270.12
  5683.9  270.54  5752.0  275.85  5764.6  275.90  5792.3  278.47  5802.3  278.39
#Mann=3,-1,0
  4464.6    0.05       0  5004.1    0.05       0  5008.3    0.05       0
Bank Sta=5004.1,5008.3
Exp/Cntr=0.3,0.1

Type RM Length L Ch R = 1,3805,459,459,459
BEGIN DESCRIPTION:
Stream0518 8.0
END DESCRIPTION:
XS GIS Cut Line= 3
      2488275.04     13652125.00      2487475.00     13652025.00
      2487074.97     13652275.02
#Sta/Elev= 30
  4193.7  286.82  4254.2  283.07  4312.2  278.45  4317.2  278.73  4334.8  277.05
  4375.1  274.76  4473.4  266.71  4566.6  260.20  4715.3  251.03  4808.5  246.30
  4839.8  245.44  4889.1  244.09  4989.9  244.45  5007.6  243.26  5011.4  242.35
  5011.7  241.85  5015.4  241.85  5015.6  242.35  5023.0  243.98  5044.2  244.52
  5071.3  243.65  5130.5  246.17  5202.2  247.72  5296.5  251.63  5385.0  256.42
  5406.2  257.02  5412.7  258.23  5436.3  259.10  5442.8  260.74  5471.7  261.25
#Mann=5,-1,0
  4193.7    0.05       0  4839.8    0.12       0  5011.4    0.05       0
  5015.6    0.12       0  5130.5    0.05       0
Bank Sta=5011.4,5015.6
Exp/Cntr=0.3,0.1

Type RM Length L Ch R = 1,3346,487,487,487
BEGIN DESCRIPTION:
Stream0518 7.0
END DESCRIPTION:
XS GIS Cut Line= 3
      2488075.01     13651975.01      2487675.00     13651725.00
      2486875.02     13651375.01
#Sta/Elev= 30
  4524.2  272.81  4553.1  270.94  4589.7  267.29  4610.9  266.22  4626.2  264.15
  4653.9  262.27  4668.7  261.84  4814.9  252.27  4960.5  244.40  4982.4  243.82
  5015.6  240.59  5015.9  240.09  5019.9  240.59  5046.0  242.14  5057.1  241.45
  5122.0  242.85  5161.6  242.61  5225.1  244.70  5260.6  244.30  5307.4  245.70
  5383.0  246.33  5560.6  254.77  5633.3  258.34  5650.8  260.47  5666.7  260.56
  5711.4  263.81  5761.1  266.00  5825.5  270.39  5847.3  272.62  5869.1  273.43
#Mann=8,-1,0
  4524.2    0.05       0  5015.6    0.05       0  5019.9    0.05       0
  5046.0    0.12       0  5122.0    0.05       0  5560.6    0.07       0
  5666.7    0.05       0  5711.4   0.035       0
Bank Sta=5015.6,5019.9
Exp/Cntr=0.3,0.1

Type RM Length L Ch R = 1,2859,464,464,464
BEGIN DESCRIPTION:
Stream0518 6.0
END DESCRIPTION:
XS GIS Cut Line= 3
      2487974.96     13651025.02      2487575.00     13651275.00
      2487174.97     13651174.99
#Sta/Elev= 30
  4536.7  256.26  4544.3  255.42  4638.7  249.92  4659.9  249.33  4696.4  246.79
  4717.7  246.26  4769.6  243.62  4792.8  243.31  4812.0  242.46  4848.6  242.51
  4885.1  240.97  4921.7  241.22  4937.0  240.33  4973.0  240.37  4992.5  239.29
  4992.8  238.79  4996.7  238.79  4997.1  239.29  5000.7  240.06  5018.7  240.10
  5039.3  243.12  5067.6  242.31  5121.7  241.94  5214.5  245.04  5232.5  246.88
  5256.3  247.11  5297.0  248.92  5327.9  251.57  5376.5  253.92  5420.7  256.80
#Mann=6,-1,0
  4536.7    0.05       0  4792.8   0.035       0  4992.5   0.035       0
  4997.1   0.035       0  5256.3    0.07       0  5376.5   0.035       0
Bank Sta=4992.5,4997.1
Exp/Cntr=0.3,0.1

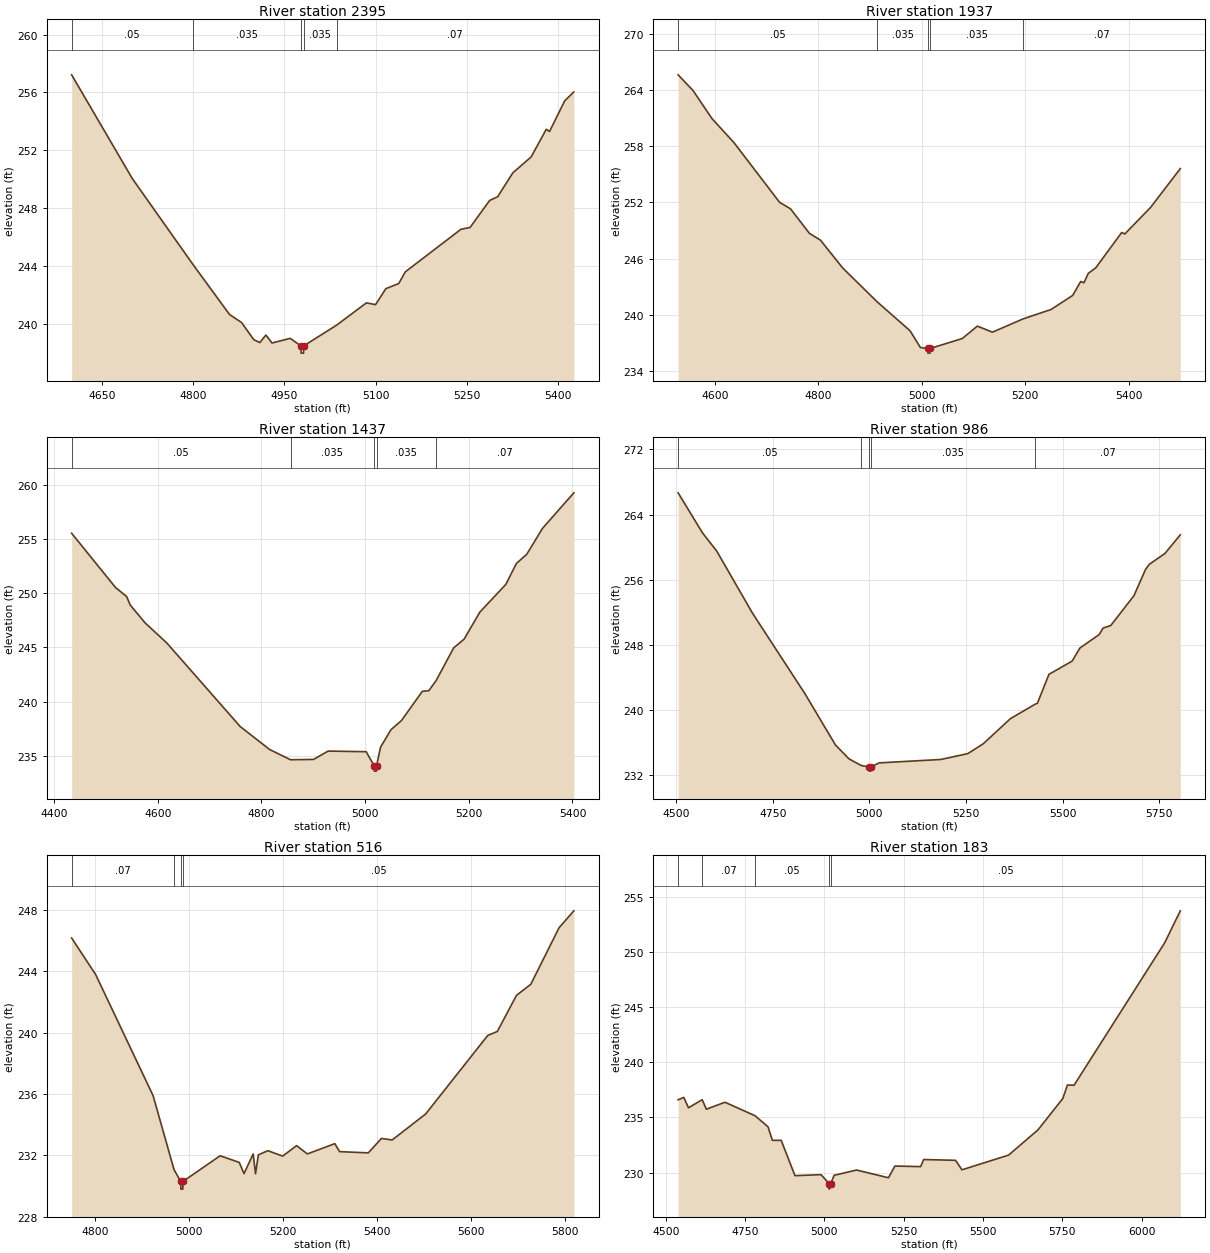
Type RM Length L Ch R = 1,2395,458,458,458
BEGIN DESCRIPTION:
Stream0518 5.0
END DESCRIPTION:
XS GIS Cut Line= 3
      2487975.03     13650875.00      2487575.00     13650875.00
      2487175.03     13651024.99
#Sta/Elev= 30
  4599.5  257.22  4699.5  250.05  4798.7  244.16  4859.5  240.67  4879.5  240.11
  4899.5  238.93  4909.5  238.73  4919.5  239.25  4929.5  238.70  4959.5  239.02
  4977.2  238.50  4977.5  238.00  4981.5  238.00  4981.8  238.50  5035.9  239.93
  5085.0  241.47  5100.1  241.35  5117.0  242.45  5138.4  242.81  5149.0  243.61
  5240.7  246.55  5255.8  246.68  5287.9  248.54  5301.2  248.80  5326.2  250.45
  5356.4  251.55  5381.3  253.46  5386.7  253.31  5411.6  255.42  5426.7  256.04
#Mann=5,-1,0
  4599.5    0.05       0  4798.7   0.035       0  4977.2   0.035       0
  4981.8   0.035       0  5035.9    0.07       0
Bank Sta=4977.2,4981.8
Exp/Cntr=0.3,0.1

Type RM Length L Ch R = 1,1937,500,500,500
BEGIN DESCRIPTION:
Stream0518 4.0
END DESCRIPTION:
XS GIS Cut Line= 3
      2488125.02     13650725.01      2487725.00     13650475.00
      2487325.01     13650175.01
#Sta/Elev= 30
  4528.4  265.65  4557.3  263.97  4593.9  260.97  4636.3  258.41  4724.8  252.01
  4746.0  251.31  4782.5  248.69  4803.8  247.97  4846.8  244.99  4913.7  241.36
  4977.1  238.28  4997.2  236.48  5011.3  236.38  5011.7  235.88  5015.7  235.88
  5016.0  236.38  5078.2  237.44  5107.4  238.77  5136.6  238.12  5196.2  239.55
  5250.1  240.55  5291.8  242.05  5307.4  243.54  5313.7  243.41  5322.0  244.41
  5336.6  245.01  5386.6  248.78  5392.8  248.63  5442.8  251.48  5500.1  255.62
#Mann=5,-1,0
  4528.4    0.05       0  4913.7   0.035       0  5011.3   0.035       0
  5016.0   0.035       0  5196.2    0.07       0
Bank Sta=5011.3,5016
Exp/Cntr=0.3,0.1

Type RM Length L Ch R = 1,1437,451,451,451
BEGIN DESCRIPTION:
Stream0518 3.0
END DESCRIPTION:
XS GIS Cut Line= 3
      2488124.97     13650374.97      2487725.00     13649975.00
      2487324.96     13649924.99
#Sta/Elev= 30
  4433.9  255.53  4518.7  250.52  4539.9  249.70  4547.0  248.91  4575.3  247.28
  4617.7  245.40  4759.1  237.70  4815.7  235.59  4856.2  234.64  4900.6  234.67
  4928.8  235.44  5002.1  235.38  5017.4  234.09  5017.7  233.59  5021.8  233.59
  5022.1  234.09  5029.8  235.80  5049.9  237.41  5070.1  238.25  5110.4  240.95
  5123.0  241.01  5137.0  241.94  5170.9  244.96  5191.0  245.76  5221.3  248.25
  5271.6  250.82  5291.8  252.74  5312.0  253.60  5342.2  255.98  5402.7  259.26
#Mann=5,-1,0
  4433.9    0.05       0  4856.2   0.035       0  5017.4   0.035       0
  5022.1   0.035       0  5137.0    0.07       0
Bank Sta=5017.4,5022.1
Exp/Cntr=0.3,0.1

Type RM Length L Ch R = 1,986,470,470,470
BEGIN DESCRIPTION:
Stream0518 2.0
END DESCRIPTION:
XS GIS Cut Line= 3
      2488424.97     13650024.98      2488025.00     13649725.00
      2487224.97     13649725.00
#Sta/Elev= 30
  4504.8  266.67  4568.3  261.73  4604.8  259.52  4697.5  251.89  4832.9  242.04
  4912.1  235.73  4947.5  234.01  4979.0  233.21  4999.2  233.02  4999.6  232.52
  5003.7  232.52  5004.0  233.02  5024.8  233.53  5184.8  233.95  5254.8  234.67
  5294.8  235.88  5364.8  238.95  5429.2  240.74  5434.8  240.84  5464.8  244.40
  5524.8  246.02  5544.8  247.62  5594.8  249.28  5604.8  250.07  5624.8  250.39
  5684.8  254.05  5714.8  257.27  5724.8  257.91  5764.8  259.22  5804.8  261.52
#Mann=5,-1,0
  4504.8    0.05       0  4979.0   0.035       0  4999.2   0.035       0
  5004.0   0.035       0  5429.2    0.07       0
Bank Sta=4999.2,5004
Exp/Cntr=0.3,0.1

Type RM Length L Ch R = 1,516,333,333,333
BEGIN DESCRIPTION:
Stream0518 1.0
END DESCRIPTION:
XS GIS Cut Line= 3
      2488474.99     13649375.00      2488225.00     13649325.00
      2487424.98     13649475.00
#Sta/Elev= 30
  4749.4  246.15  4800.4  243.78  4922.8  235.89  4967.3  231.08  4981.5  230.31
  4981.9  229.81  4986.0  229.81  4986.3  230.31  5065.4  231.98  5106.1  231.55
  5116.3  230.82  5135.8  232.10  5140.8  230.81  5146.8  232.04  5167.1  232.31
  5198.5  231.96  5228.2  232.64  5251.1  232.10  5309.6  232.77  5319.7  232.25
  5380.8  232.17  5408.8  233.11  5431.7  233.01  5502.9  234.70  5635.1  239.81
  5655.5  240.07  5696.2  242.42  5726.7  243.14  5786.9  246.82  5818.3  247.92
#Mann=4,-1,0
  4749.4    0.07       0  4967.3    0.05       0  4981.5    0.05       0
  4986.3    0.05       0
Bank Sta=4981.5,4986.3
Exp/Cntr=0.3,0.1

Type RM Length L Ch R = 1,183,0,0,0
BEGIN DESCRIPTION:
XS7017
END DESCRIPTION:
XS GIS Cut Line= 4
      2488716.35     13649175.36      2488256.25     13649036.46
      2487752.78     13649097.22      2487275.37     13649453.11
#Sta/Elev= 30
  4539.1  236.60  4556.9  236.82  4571.8  235.88  4615.0  236.61  4628.1  235.75
  4686.8  236.38  4781.5  235.16  4822.5  234.16  4836.3  232.93  4864.1  232.93
  4907.5  229.73  4989.7  229.82  5015.4  229.01  5015.7  228.51  5020.2  229.01
  5031.0  229.76  5101.6  230.24  5202.3  229.54  5222.4  230.60  5303.8  230.55
  5313.1  231.19  5413.8  231.12  5433.9  230.26  5580.9  231.59  5673.7  233.88
  5751.9  236.72  5766.5  237.94  5787.3  237.92  6073.0  250.82  6122.3  253.72
#Mann=5,-1,0
  4539.1    0.05       0  4615.0    0.07       0  4781.5    0.05       0
  5015.4    0.05       0  5020.2    0.05       0
Bank Sta=5015.4,5020.2
Exp/Cntr=0.3,0.1

Chan Stop Cuts=-1