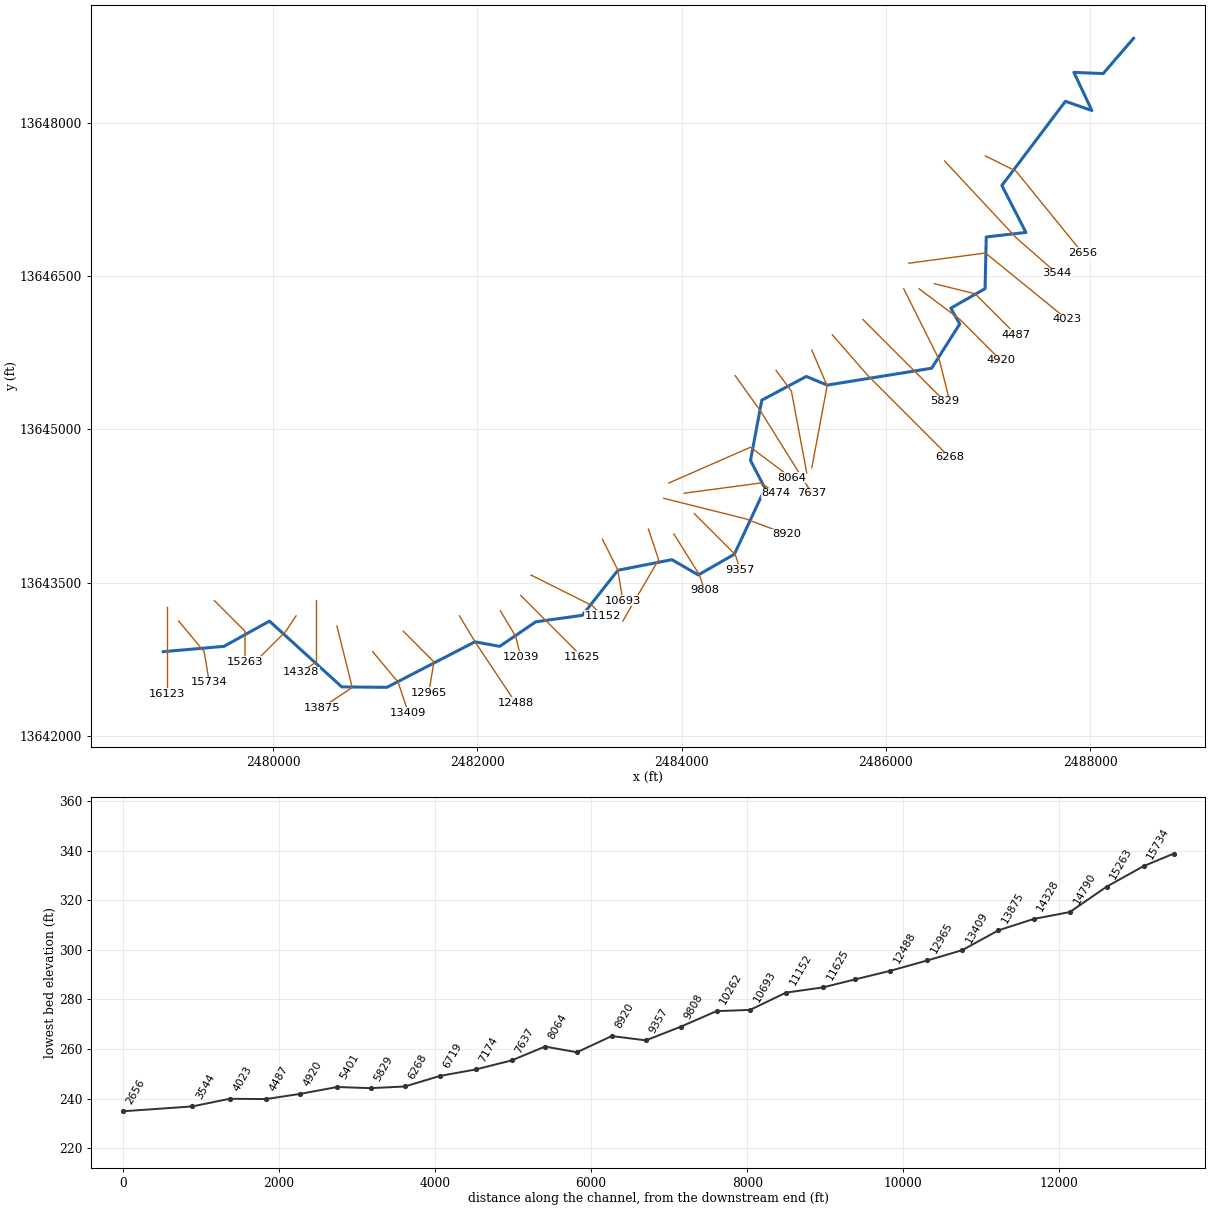
--- Stream0519.prj (project) ---

Proj Title=Stream0519 Base Level Engineering
Current Plan=p01
Default Exp/Contr=0.3,0.1
English Units
Geom File=g01
Flow File=f01
Plan File=p01
BEGIN DESCRIPTION:
Stream0519
END DESCRIPTION:

--- Stream0519.p01 (plan) ---

Plan Title=Multiple Run
Short Identifier=Multiple
Geom File=g01
Flow File=f01
Subcritical Flow
K Sum by GR= 0
Std Step Tol= 0.01
Critical Tol= 0.01
Num of Std Step Trials= 20
Max Error Tol= 0.3
Flow Tol Ratio= 0.001
Split Flow NTrial= 30
Split Flow Tol= 0.02
Split Flow Ratio= 0.02
Log Output Level= 0
Friction Slope Method= 1
Unsteady Friction Slope Method= 2
Unsteady Bridges Friction Slope Method= 1
Parabolic Critical Depth
Global Vel Dist=  1 , 1 , 1
Global Log Level= 0
CheckData=True
Encroach Param= -1, 0, 0, 0
BEGIN DESCRIPTION:
Multiple Run
END DESCRIPTION:

--- Stream0519.f01 (steady flow) ---

Flow Title=Multiple
Number of Profiles=7
Profile Names=10-year,25-year,50-year,1pct_min,100-year,1pct_plu,500-year
River Rch & RM= Stream0519,Reach-1,16123
     388     610     807     520    1037    2069    1689
River Rch & RM= Stream0519,Reach-1,13409
     833    1374    1874    1240    2473    4935    4263
River Rch & RM= Stream0519,Reach-1,9808
     911    1506    2057    1361    2716    5419    4688
River Rch & RM= Stream0519,Reach-1,7637
    1166    1952    2690    1794    3579    7141    6275
River Rch & RM= Stream0519,Reach-1,5401
    1374    2307    3184    2124    4238    8455    7439
Boundary for River Rch & Prof#=Stream0519,Reach-1,1
Up Type=0
Dn Type=3
Dn Slope=0.005
Boundary for River Rch & Prof#=Stream0519,Reach-1,2
Up Type=0
Dn Type=3
Dn Slope=0.005
Boundary for River Rch & Prof#=Stream0519,Reach-1,3
Up Type=0
Dn Type=3
Dn Slope=0.005
Boundary for River Rch & Prof#=Stream0519,Reach-1,4
Up Type=0
Dn Type=3
Dn Slope=0.005
Boundary for River Rch & Prof#=Stream0519,Reach-1,5
Up Type=0
Dn Type=3
Dn Slope=0.005
Boundary for River Rch & Prof#=Stream0519,Reach-1,6
Up Type=0
Dn Type=3
Dn Slope=0.005
Boundary for River Rch & Prof#=Stream0519,Reach-1,7
Up Type=0
Dn Type=3
Dn Slope=0.005

--- Stream0519.g01 (geometry) ---

Geom Title=Existing Conditions

River Reach=Stream0519,Reach-1
Reach XY= 30
      2478925.00     13642825.00      2479519.14     13642877.07
      2479964.45     13643123.92      2480672.55     13642480.46
      2481114.50     13642476.22      2481976.47     13642921.47
      2482218.89     13642876.80      2482571.68     13643116.96
      2483027.44     13643180.52      2483376.47     13643621.46
      2483905.02     13643725.04      2484163.17     13643575.59
      2484516.75     13643778.07      2484816.98     13644421.69
      2484674.78     13644695.20      2484785.35     13645285.18
      2485221.33     13645517.31      2485425.01     13645432.53
      2486448.53     13645597.71      2486723.42     13646031.05
      2486635.95     13646185.03      2486971.55     13646376.25
      2486982.80     13646881.84      2487371.65     13646926.25
      2487136.08     13647385.05      2487757.88     13648209.00
      2488017.36     13648118.45      2487841.19     13648491.70
      2488127.83     13648480.07      2488425.00     13648825.00

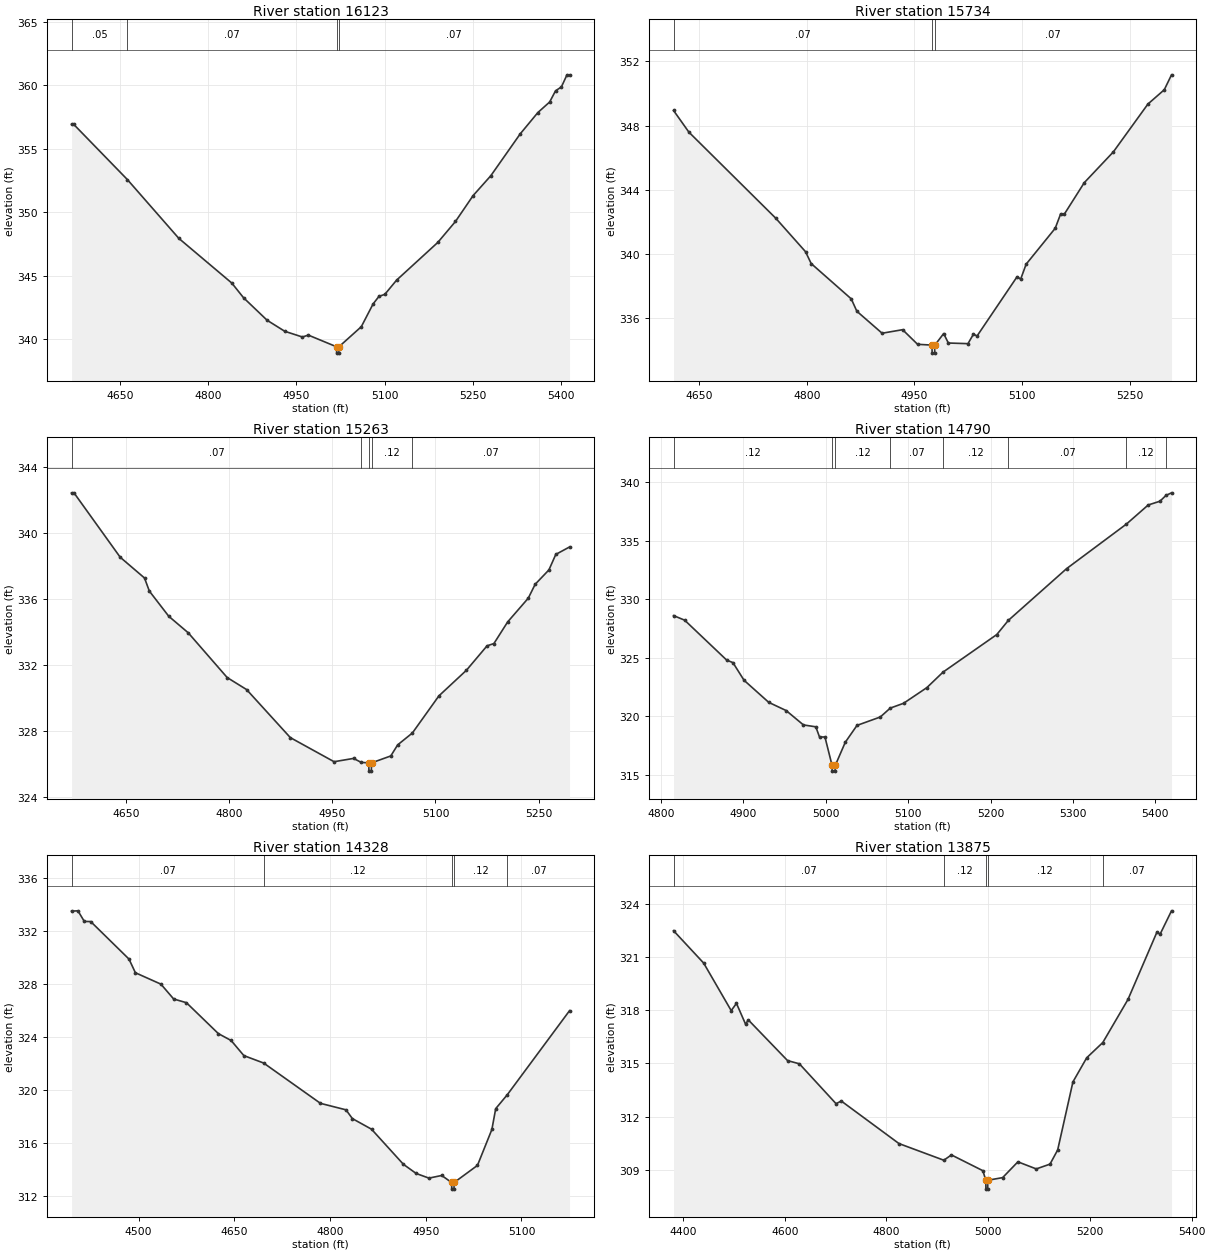
Type RM Length L Ch R = 1,16123,389,389,389
BEGIN DESCRIPTION:
XS7023
END DESCRIPTION:
XS GIS Cut Line= 2
      2478960.91     13643257.20      2478960.91     13642411.20
#Sta/Elev= 30
  4568.2  356.92  4571.8  356.92  4663.0  352.57  4750.4  347.94  4840.4  344.42
  4860.4  343.26  4900.4  341.49  4930.4  340.62  4960.4  340.17  4970.4  340.32
  5018.4  339.40  5018.6  338.90  5022.1  338.90  5022.4  339.40  5060.4  340.98
  5080.4  342.77  5090.4  343.37  5100.4  343.53  5120.4  344.65  5190.4  347.62
  5220.4  349.27  5250.4  351.31  5280.4  352.87  5330.4  356.17  5360.4  357.85
  5380.4  358.68  5390.4  359.56  5400.4  359.87  5409.8  360.82  5414.2  360.82
#Mann=4,-1,0
  4568.2    0.05       0  4663.0    0.07       0  5018.4    0.05       0
  5022.4    0.07       0
Bank Sta=5018.4,5022.4
Exp/Cntr=0.3,0.1

Type RM Length L Ch R = 1,15734,471,471,471
BEGIN DESCRIPTION:
Stream0519 31.0
END DESCRIPTION:
XS GIS Cut Line= 3
      2479075.03     13643124.96      2479325.00     13642825.00
      2479375.00     13642525.00
#Sta/Elev= 30
  4613.9  348.94  4635.3  347.59  4756.4  342.23  4798.0  340.14  4805.9  339.40
  4861.8  337.20  4869.6  336.43  4904.8  335.06  4933.4  335.28  4954.3  334.37
  4974.4  334.32  4974.6  333.82  4978.1  333.82  4978.4  334.32  4990.7  335.04
  4997.2  334.45  5024.6  334.41  5032.2  335.00  5037.3  334.89  5093.1  338.58
  5098.1  338.43  5105.7  339.36  5146.3  341.60  5153.9  342.50  5159.0  342.48
  5186.8  344.44  5227.4  346.36  5275.6  349.34  5298.4  350.23  5308.5  351.16
#Mann=3,-1,0
  4613.9    0.07       0  4974.4    0.05       0  4978.4    0.07       0
Bank Sta=4974.4,4978.4
Exp/Cntr=0.3,0.1

Type RM Length L Ch R = 1,15263,473,473,473
BEGIN DESCRIPTION:
Stream0519 30.0
END DESCRIPTION:
XS GIS Cut Line= 3
      2479425.00     13643325.00      2479725.00     13643025.00
      2479725.00     13642724.96
#Sta/Elev= 30
  4570.7  342.42  4574.2  342.42  4641.4  338.52  4676.8  337.26  4683.8  336.47
  4712.1  334.94  4740.4  333.94  4797.0  331.23  4825.3  330.50  4888.9  327.59
  4952.5  326.13  4980.8  326.33  4992.0  326.09  5003.0  326.06  5003.2  325.56
  5006.7  325.56  5007.0  326.06  5035.0  326.48  5045.0  327.15  5066.4  327.87
  5105.0  330.12  5145.0  331.67  5175.0  333.15  5185.0  333.29  5205.0  334.60
  5235.0  336.04  5245.0  336.88  5265.0  337.75  5275.0  338.69  5295.0  339.14
#Mann=5,-1,0
  4570.7    0.07       0  4992.0    0.12       0  5003.0    0.05       0
  5007.0    0.12       0  5066.4    0.07       0
Bank Sta=5003,5007
Exp/Cntr=0.3,0.1

Type RM Length L Ch R = 1,14790,462,462,462
BEGIN DESCRIPTION:
Stream0519 29.0
END DESCRIPTION:
XS GIS Cut Line= 3
      2480224.98     13643174.98      2480125.00     13643025.00
      2479825.01     13642725.01
#Sta/Elev= 30
  4815.1  328.59  4828.6  328.20  4879.7  324.78  4887.2  324.57  4900.7  323.06
  4930.7  321.17  4951.8  320.47  4972.8  319.24  4987.8  319.08  4992.3  318.21
  4998.9  318.21  5007.5  315.79  5007.7  315.29  5011.2  315.29  5011.5  315.79
  5023.6  317.76  5037.8  319.20  5066.1  319.92  5078.2  320.68  5094.3  321.09
  5122.6  322.43  5142.3  323.76  5207.5  326.97  5221.5  328.18  5292.3  332.61
  5364.9  336.42  5391.3  338.05  5405.5  338.37  5412.9  338.87  5419.6  339.09
#Mann=8,-1,0
  4815.1    0.12       0  5007.5    0.05       0  5011.5    0.12       0
  5078.2    0.07       0  5142.3    0.12       0  5221.5    0.07       0
  5364.9    0.12       0  5412.9    0.07       0
Bank Sta=5007.5,5011.5
Exp/Cntr=0.3,0.1

Type RM Length L Ch R = 1,14328,453,453,453
BEGIN DESCRIPTION:
Stream0519 28.0
END DESCRIPTION:
XS GIS Cut Line= 3
      2480425.00     13643324.98      2480425.00     13642725.00
      2480274.97     13642624.98
#Sta/Elev= 30
  4395.0  333.48  4405.0  333.50  4415.0  332.70  4425.0  332.69  4485.0  329.86
  4495.0  328.83  4535.0  327.97  4555.0  326.85  4575.0  326.57  4625.0  324.24
  4645.0  323.72  4665.0  322.58  4696.0  322.02  4785.0  318.98  4825.0  318.49
  4835.0  317.83  4865.0  317.03  4915.0  314.38  4935.0  313.69  4955.0  313.34
  4975.0  313.54  4990.5  313.01  4990.7  312.51  4994.2  312.51  4994.5  313.01
  5031.0  314.30  5053.6  317.01  5059.6  318.58  5077.6  319.62  5175.3  325.97
#Mann=5,-1,0
  4395.0    0.07       0  4696.0    0.12       0  4990.5    0.05       0
  4994.5    0.12       0  5077.6    0.07       0
Bank Sta=4990.5,4994.5
Exp/Cntr=0.3,0.1

Type RM Length L Ch R = 1,13875,466,466,466
BEGIN DESCRIPTION:
Stream0519 27.0
END DESCRIPTION:
XS GIS Cut Line= 3
      2480625.00     13643074.99      2480775.00     13642475.00
      2480475.01     13642275.01
#Sta/Elev= 30
  4381.4  322.49  4440.7  320.66  4494.8  317.98  4505.1  318.39  4523.1  317.21
  4528.3  317.46  4605.6  315.16  4628.8  314.98  4700.9  312.73  4711.2  312.88
  4824.6  310.48  4912.8  309.54  4927.7  309.84  4989.5  308.95  4995.3  308.41
  4995.5  307.91  4999.0  307.91  4999.3  308.41  5028.4  308.56  5058.4  309.45
  5094.5  309.05  5121.5  309.32  5136.6  310.12  5166.6  313.96  5193.7  315.32
  5225.3  316.18  5274.8  318.61  5331.9  322.42  5337.9  322.29  5360.4  323.61
#Mann=5,-1,0
  4381.4    0.07       0  4912.8    0.12       0  4995.3    0.05       0
  4999.3    0.12       0  5225.3    0.07       0
Bank Sta=4995.3,4999.3
Exp/Cntr=0.3,0.1

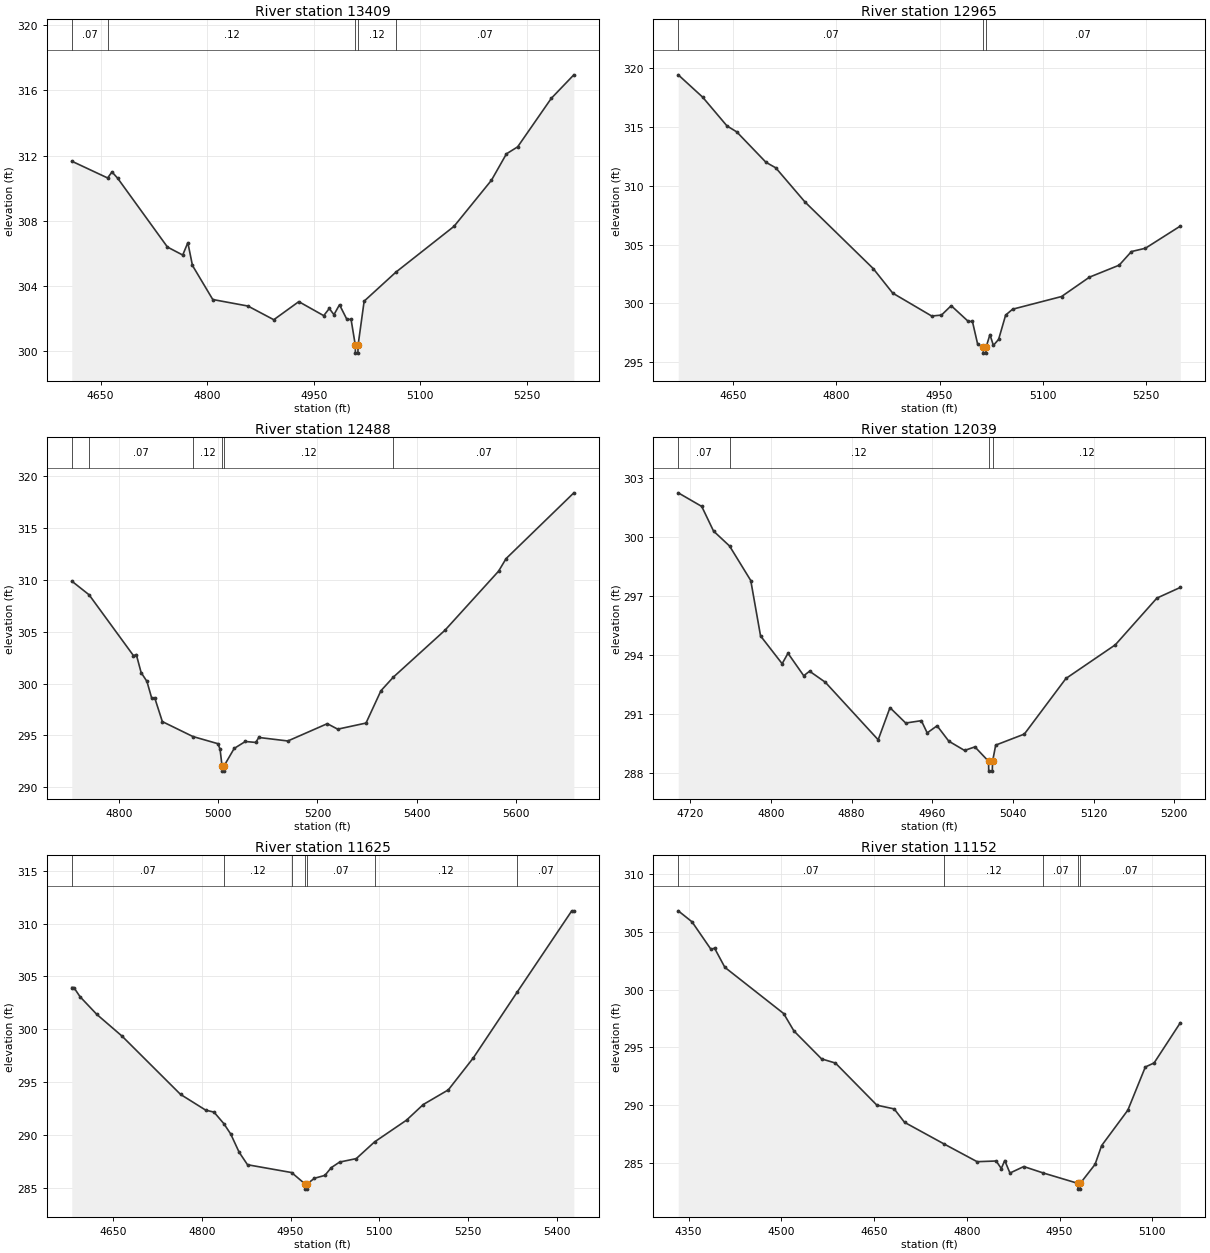
Type RM Length L Ch R = 1,13409,444,444,444
BEGIN DESCRIPTION:
Stream0519 26.0
END DESCRIPTION:
XS GIS Cut Line= 3
      2480974.99     13642825.02      2481225.00     13642525.00
      2481325.01     13642224.96
#Sta/Elev= 30
  4609.3  311.66  4659.8  310.63  4665.9  311.00  4673.8  310.62  4744.0  306.39
  4765.5  305.90  4772.7  306.66  4779.2  305.26  4807.8  303.17  4857.3  302.77
  4893.7  301.93  4928.9  303.04  4964.0  302.18  4971.8  302.62  4978.4  302.24
  4986.2  302.85  4996.6  301.95  5002.5  301.95  5008.4  300.38  5008.6  299.88
  5012.1  299.88  5012.4  300.38  5020.9  303.07  5065.6  304.85  5147.4  307.66
  5200.1  310.49  5221.2  312.11  5237.0  312.54  5284.4  315.52  5316.1  316.96
#Mann=5,-1,0
  4609.3    0.07       0  4659.8    0.12       0  5008.4    0.05       0
  5012.4    0.12       0  5065.6    0.07       0
Bank Sta=5008.4,5012.4
Exp/Cntr=0.3,0.1

Type RM Length L Ch R = 1,12965,477,477,477
BEGIN DESCRIPTION:
Stream0519 25.0
END DESCRIPTION:
XS GIS Cut Line= 3
      2481274.98     13643025.02      2481575.00     13642725.00
      2481525.01     13642425.03
#Sta/Elev= 30
  4570.9  319.46  4606.3  317.56  4641.6  315.11  4655.8  314.60  4698.2  312.01
  4712.4  311.54  4754.8  308.63  4853.8  302.96  4882.1  300.87  4938.6  298.92
  4952.8  299.00  4966.9  299.80  4991.7  298.46  4997.7  298.46  5005.3  296.52
  5013.5  296.26  5013.7  295.76  5017.2  295.76  5017.5  296.26  5023.1  297.34
  5028.1  296.42  5035.7  296.93  5045.9  299.00  5056.0  299.50  5127.0  300.58
  5167.5  302.23  5210.6  303.25  5228.4  304.41  5248.6  304.69  5299.3  306.58
#Mann=3,-1,0
  4570.9    0.07       0  5013.5    0.05       0  5017.5    0.07       0
Bank Sta=5013.5,5017.5
Exp/Cntr=0.3,0.1

Type RM Length L Ch R = 1,12488,449,449,449
BEGIN DESCRIPTION:
Stream0519 24.0
END DESCRIPTION:
XS GIS Cut Line= 3
      2481825.00     13643175.00      2481975.00     13642925.00
      2482375.02     13642324.97
#Sta/Elev= 30
  4704.5  309.90  4739.4  308.58  4828.9  302.71  4834.7  302.81  4844.4  301.07
  4856.1  300.22  4865.8  298.59  4871.7  298.65  4887.2  296.34  4948.8  294.90
  4999.1  294.21  5003.6  293.68  5007.6  292.06  5007.8  291.56  5011.3  291.56
  5011.6  292.06  5032.1  293.75  5054.6  294.42  5075.7  294.33  5081.7  294.81
  5140.3  294.47  5219.9  296.14  5240.9  295.61  5298.0  296.20  5328.1  299.32
  5353.1  300.63  5457.3  305.16  5565.4  310.86  5580.5  312.07  5717.2  318.42
#Mann=6,-1,0
  4704.5    0.12       0  4739.4    0.07       0  4948.8    0.12       0
  5007.6    0.05       0  5011.6    0.12       0  5353.1    0.07       0
Bank Sta=5007.6,5011.6
Exp/Cntr=0.3,0.1

Type RM Length L Ch R = 1,12039,414,414,414
BEGIN DESCRIPTION:
Stream0519 23.0
END DESCRIPTION:
XS GIS Cut Line= 3
      2482225.00     13643224.99      2482375.00     13642975.00
      2482425.00     13642774.99
#Sta/Elev= 30
  4708.2  302.23  4731.5  301.54  4743.2  300.29  4759.1  299.53  4780.1  297.78
  4789.8  294.97  4811.2  293.56  4817.0  294.09  4832.6  292.95  4838.4  293.18
  4854.0  292.62  4906.4  289.70  4918.1  291.33  4933.7  290.55  4949.2  290.67
  4955.0  290.05  4964.8  290.41  4976.4  289.63  4992.0  289.16  5002.3  289.34
  5015.8  288.61  5016.0  288.11  5019.5  288.11  5019.8  288.61  5022.9  289.43
  5051.3  289.99  5092.5  292.81  5141.5  294.52  5182.7  296.89  5205.9  297.43
#Mann=4,-1,0
  4708.2    0.07       0  4759.1    0.12       0  5015.8    0.05       0
  5019.8    0.12       0
Bank Sta=5015.8,5019.8
Exp/Cntr=0.3,0.1

Type RM Length L Ch R = 1,11625,473,473,473
BEGIN DESCRIPTION:
Stream0519 22.0
END DESCRIPTION:
XS GIS Cut Line= 3
      2482425.00     13643375.00      2482725.00     13643075.00
      2483024.98     13642775.02
#Sta/Elev= 30
  4580.2  303.95  4583.7  303.95  4594.3  303.07  4622.6  301.40  4665.1  299.35
  4764.0  293.83  4806.5  292.34  4820.6  292.15  4837.2  291.06  4848.9  290.07
  4863.0  288.36  4877.2  287.17  4951.7  286.43  4974.2  285.36  4974.4  284.86
  4977.9  284.86  4978.2  285.36  4990.3  285.89  5008.0  286.16  5018.6  286.89
  5032.8  287.42  5061.0  287.75  5091.9  289.33  5145.9  291.39  5174.2  292.87
  5216.6  294.26  5259.0  297.30  5333.0  303.52  5425.2  311.21  5428.7  311.21
#Mann=7,-1,0
  4580.2    0.07       0  4837.2    0.12       0  4951.7    0.07       0
  4974.2    0.05       0  4978.2    0.07       0  5091.9    0.12       0
  5333.0    0.07       0
Bank Sta=4974.2,4978.2
Exp/Cntr=0.3,0.1

Type RM Length L Ch R = 1,11152,459,459,459
BEGIN DESCRIPTION:
Stream0519 21.0
END DESCRIPTION:
XS GIS Cut Line= 3
      2482525.04     13643574.98      2483125.00     13643275.00
      2483225.00     13643175.00
#Sta/Elev= 30
  4333.2  306.80  4355.5  305.85  4386.3  303.46  4391.9  303.58  4408.6  301.92
  4503.7  297.93  4520.4  296.42  4565.1  294.01  4587.5  293.65  4654.6  290.01
  4682.5  289.69  4699.3  288.53  4762.6  286.68  4816.7  285.13  4847.5  285.19
  4855.8  284.54  4861.4  285.23  4869.8  284.15  4892.2  284.71  4924.0  284.15
  4979.6  283.26  4979.9  282.76  4983.4  282.76  4983.6  283.26  5007.5  284.90
  5018.1  286.52  5060.5  289.58  5088.8  293.31  5103.0  293.66  5145.4  297.13
#Mann=5,-1,0
  4333.2    0.07       0  4762.6    0.12       0  4924.0    0.07       0
  4979.6    0.05       0  4983.6    0.07       0
Bank Sta=4979.6,4983.6
Exp/Cntr=0.3,0.1

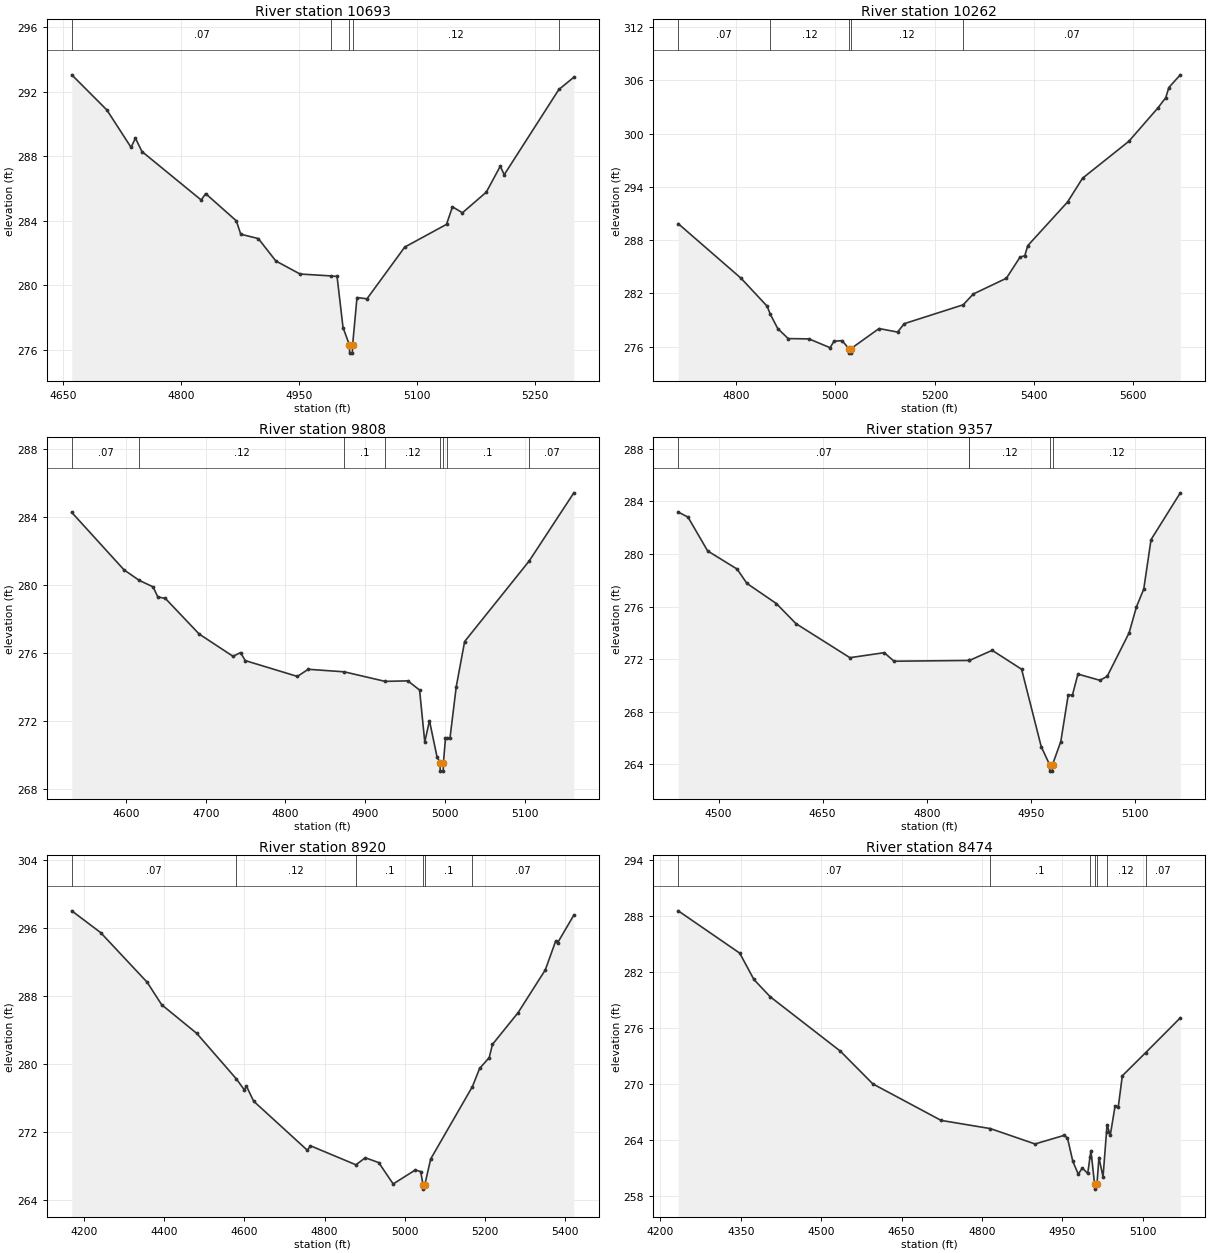
Type RM Length L Ch R = 1,10693,431,431,431
BEGIN DESCRIPTION:
Stream0519 20.0
END DESCRIPTION:
XS GIS Cut Line= 3
      2483225.00     13643924.99      2483375.00     13643625.00
      2483424.99     13643325.04
#Sta/Elev= 30
  4660.6  293.06  4705.3  290.88  4736.1  288.56  4741.7  289.13  4750.0  288.30
  4825.5  285.29  4831.1  285.69  4870.2  284.00  4875.8  283.17  4898.2  282.90
  4920.5  281.51  4951.3  280.70  4991.1  280.58  4998.5  280.55  5006.1  277.38
  5014.3  276.29  5014.5  275.79  5018.0  275.79  5018.3  276.29  5023.9  279.24
  5036.6  279.16  5084.7  282.37  5137.9  283.78  5145.5  284.87  5158.2  284.50
  5188.6  285.78  5206.4  287.39  5211.4  286.86  5281.0  292.15  5300.1  292.91
#Mann=5,-1,0
  4660.6    0.07       0  4991.1    0.12       0  5014.3    0.05       0
  5018.3    0.12       0  5281.0    0.07       0
Bank Sta=5014.3,5018.3
Exp/Cntr=0.3,0.1

Type RM Length L Ch R = 1,10262,454,454,454
BEGIN DESCRIPTION:
Stream0519 19.0
END DESCRIPTION:
XS GIS Cut Line= 3
      2483675.01     13644024.98      2483775.00     13643725.00
      2483425.02     13643125.03
#Sta/Elev= 30
  4683.9  289.86  4810.4  283.71  4863.1  280.55  4868.9  279.70  4884.2  278.05
  4905.2  276.92  4947.4  276.88  4989.6  275.89  4997.5  276.62  5013.8  276.69
  5027.5  275.78  5027.7  275.28  5031.2  275.28  5031.5  275.78  5088.2  278.05
  5125.4  277.65  5139.0  278.60  5257.5  280.72  5278.0  281.94  5344.5  283.71
  5371.8  286.07  5381.7  286.26  5387.5  287.38  5467.7  292.30  5497.9  294.98
  5591.0  299.13  5649.7  302.90  5665.4  304.05  5671.6  305.19  5694.7  306.62
#Mann=5,-1,0
  4683.9    0.07       0  4868.9    0.12       0  5027.5    0.05       0
  5031.5    0.12       0  5257.5    0.07       0
Bank Sta=5027.5,5031.5
Exp/Cntr=0.3,0.1

Type RM Length L Ch R = 1,9808,451,451,451
BEGIN DESCRIPTION:
Stream0519 18.0
END DESCRIPTION:
XS GIS Cut Line= 3
      2483924.99     13643975.02      2484175.00     13643575.00
      2484224.99     13643425.03
#Sta/Elev= 30
  4531.9  284.25  4597.4  280.88  4616.5  280.26  4633.9  279.88  4639.8  279.29
  4649.3  279.20  4691.7  277.11  4734.2  275.80  4743.6  276.02  4749.5  275.55
  4814.9  274.62  4828.5  275.04  4873.7  274.89  4925.0  274.33  4953.5  274.36
  4968.2  273.82  4974.7  270.77  4980.6  272.02  4990.1  269.89  4993.9  269.56
  4994.1  269.06  4997.8  269.06  4998.1  269.56  5000.7  270.99  5002.8  270.99
  5006.3  270.99  5014.2  274.02  5024.7  276.67  5105.7  281.40  5161.7  285.40
#Mann=8,-1,0
  4531.9    0.07       0  4616.5    0.12       0  4873.7     0.1       0
  4925.0    0.12       0  4993.9    0.05       0  4998.1    0.12       0
  5002.8     0.1       0  5105.7    0.07       0
Bank Sta=4993.9,4998.1
Exp/Cntr=0.3,0.1

Type RM Length L Ch R = 1,9357,437,437,437
BEGIN DESCRIPTION:
Stream0519 17.0
END DESCRIPTION:
XS GIS Cut Line= 3
      2484125.00     13644175.00      2484525.00     13643775.00
      2484575.00     13643625.01
#Sta/Elev= 30
  4441.8  283.19  4455.9  282.80  4484.2  280.23  4526.7  278.85  4540.8  277.76
  4583.2  276.23  4611.5  274.70  4689.3  272.11  4738.8  272.49  4752.9  271.84
  4861.5  271.90  4861.6  271.90  4894.4  272.67  4936.8  271.23  4965.1  265.34
  4977.1  263.98  4977.4  263.48  4981.1  263.48  4981.4  263.98  4993.3  265.73
  5004.0  269.27  5010.1  269.27  5018.0  270.86  5049.7  270.39  5060.2  270.69
  5091.8  274.00  5102.4  275.98  5112.9  277.33  5123.4  281.09  5165.6  284.65
#Mann=5,-1,0
  4441.8    0.07       0  4861.5     0.1       0  4861.6    0.12       0
  4977.1    0.05       0  4981.4    0.12       0
Bank Sta=4977.1,4981.4
Exp/Cntr=0.3,0.1

Type RM Length L Ch R = 1,8920,446,446,446
BEGIN DESCRIPTION:
Stream0519 16.0
END DESCRIPTION:
XS GIS Cut Line= 3
      2483825.04     13644324.99      2484625.00     13644125.00
      2485025.02     13643974.99
#Sta/Elev= 30
  4169.5  298.05  4241.6  295.48  4357.6  289.62  4393.6  286.98  4481.3  283.59
  4580.2  278.21  4599.8  276.93  4605.0  277.38  4623.0  275.60  4757.0  269.81
  4764.7  270.34  4878.0  268.10  4901.3  268.93  4934.8  268.36  4970.9  265.84
  5026.1  267.49  5039.5  267.30  5045.3  265.73  5045.6  265.23  5049.6  265.73
  5064.4  268.79  5168.5  277.33  5186.3  279.46  5210.3  280.74  5218.4  282.30
  5282.4  286.05  5350.1  291.08  5375.9  294.47  5381.2  294.31  5421.3  297.55
#Mann=6,-1,0
  4169.5    0.07       0  4580.2    0.12       0  4878.0     0.1       0
  5045.3    0.05       0  5049.6     0.1       0  5168.5    0.07       0
Bank Sta=5045.3,5049.6
Exp/Cntr=0.3,0.1

Type RM Length L Ch R = 1,8474,410,410,410
BEGIN DESCRIPTION:
Stream0519 15.0
END DESCRIPTION:
XS GIS Cut Line= 3
      2484025.04     13644375.01      2484775.00     13644475.00
      2484925.02     13644374.98
#Sta/Elev= 30
  4233.1  288.57  4347.8  284.03  4374.3  281.20  4404.6  279.35  4535.7  273.50
  4596.2  269.99  4723.6  266.07  4815.5  265.19  4898.9  263.54  4953.1  264.46
  4959.4  264.19  4969.5  261.66  4979.6  260.30  4987.2  260.96  4997.2  260.37
  5001.5  262.13  5003.2  262.82  5010.1  259.19  5010.4  258.69  5014.4  259.19
  5018.2  262.08  5025.8  260.00  5032.3  264.86  5033.3  265.61  5039.3  264.47
  5048.3  267.63  5054.3  267.55  5061.8  270.86  5105.1  273.33  5170.0  277.08
#Mann=7,-1,0
  4233.1    0.07       0  4815.5     0.1       0  5001.5    0.07       0
  5010.1    0.05       0  5014.4    0.07       0  5032.3    0.12       0
  5105.1    0.07       0
Bank Sta=5010.1,5014.4
Exp/Cntr=0.3,0.1

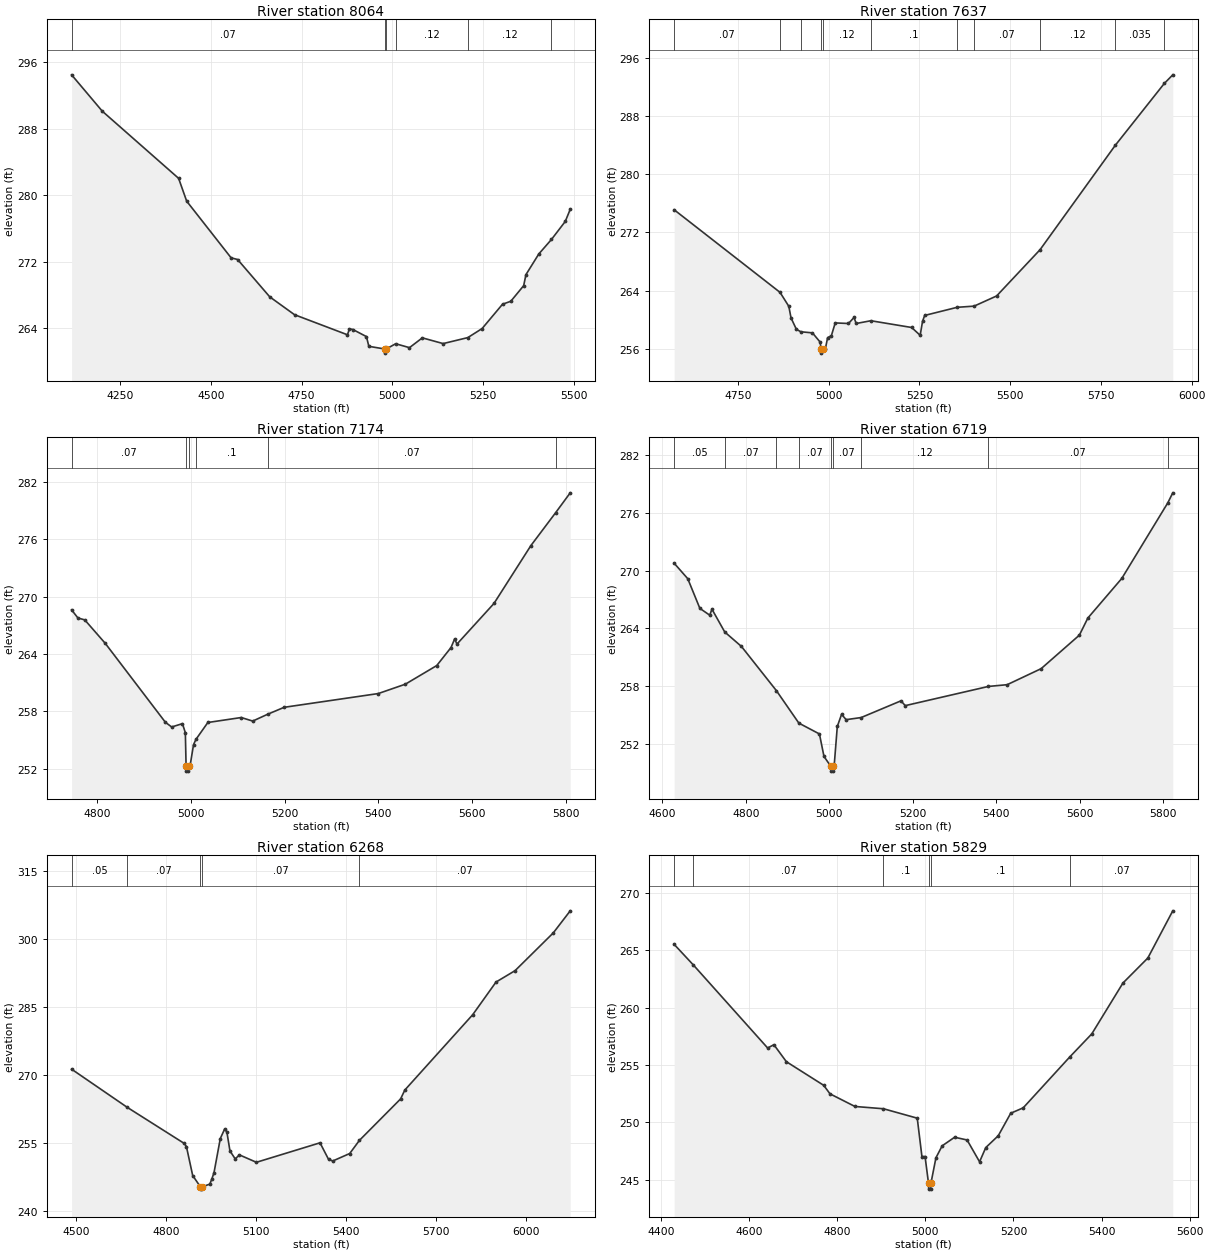
Type RM Length L Ch R = 1,8064,427,427,427
BEGIN DESCRIPTION:
Stream0519 14.0
END DESCRIPTION:
XS GIS Cut Line= 3
      2483875.04     13644475.02      2484675.00     13644825.00
      2485075.02     13644524.98
#Sta/Elev= 30
  4116.5  294.51  4201.0  290.13  4411.2  282.04  4433.4  279.29  4555.8  272.46
  4573.7  272.26  4662.2  267.76  4730.4  265.61  4876.2  263.19  4881.7  263.91
  4891.4  263.82  4928.5  262.97  4935.1  261.80  4978.5  261.48  4978.8  260.98
  4982.9  261.48  5009.0  262.11  5047.0  261.64  5082.4  262.82  5139.7  262.13
  5207.6  262.85  5247.0  263.94  5303.2  266.87  5326.1  267.23  5361.5  269.11
  5367.8  270.44  5403.2  272.93  5438.1  274.68  5476.1  276.85  5489.7  278.31
#Mann=6,-1,0
  4116.5    0.07       0  4978.5    0.05       0  4982.9    0.07       0
  5009.0    0.12       0  5207.6    0.12       0  5438.1    0.07       0
Bank Sta=4978.5,4982.9
Exp/Cntr=0.3,0.1

Type RM Length L Ch R = 1,7637,463,463,463
BEGIN DESCRIPTION:
Stream0519 13.0
END DESCRIPTION:
XS GIS Cut Line= 3
      2484525.01     13645524.98      2484775.00     13645175.00
      2485275.00     13644375.00
#Sta/Elev= 30
  4574.5  275.13  4866.1  263.76  4890.3  261.84  4896.5  260.23  4911.2  258.67
  4923.6  258.33  4955.4  258.18  4976.3  256.93  4979.9  255.89  4980.3  255.39
  4985.0  255.89  4991.1  255.99  4997.2  257.52  5007.5  257.78  5018.2  259.55
  5054.7  259.47  5070.0  260.30  5075.9  259.47  5116.4  259.85  5228.7  258.92
  5252.2  257.84  5258.7  259.77  5264.6  260.58  5354.2  261.70  5400.7  261.86
  5462.7  263.26  5582.4  269.63  5789.7  284.01  5924.8  292.53  5948.0  293.71
#Mann=11,-1,0
  4574.5    0.07       0  4866.1     0.1       0  4923.6    0.12       0
  4979.9    0.05       0  4985.0    0.12       0  5116.4     0.1       0
  5354.2    0.12       0  5400.7    0.07       0  5582.4    0.12       0
  5789.7   0.035       0  5924.8    0.05       0
Bank Sta=4979.9,4985
Exp/Cntr=0.3,0.1

Type RM Length L Ch R = 1,7174,455,455,455
BEGIN DESCRIPTION:
Stream0519 12.0
END DESCRIPTION:
XS GIS Cut Line= 3
      2484925.00     13645575.01      2485075.00     13645375.00
      2485224.99     13644575.05
#Sta/Elev= 30
  4745.5  268.61  4759.0  267.76  4773.6  267.56  4817.4  265.10  4945.5  256.85
  4959.0  256.35  4982.0  256.70  4988.2  255.75  4989.8  252.23  4990.2  251.73
  4994.6  251.73  4995.0  252.23  4998.1  252.23  5005.7  254.51  5010.9  255.06
  5036.2  256.82  5107.4  257.34  5132.0  256.97  5163.7  257.68  5199.0  258.41
  5399.9  259.85  5457.6  260.83  5524.6  262.78  5555.1  264.67  5562.7  265.56
  5567.8  265.03  5646.7  269.28  5725.5  275.34  5778.1  278.77  5809.4  280.86
#Mann=6,-1,0
  4745.5    0.07       0  4989.8    0.05       0  4995.0    0.07       0
  5010.9     0.1       0  5163.7    0.07       0  5778.1   0.035       0
Bank Sta=4989.8,4995
Exp/Cntr=0.3,0.1

Type RM Length L Ch R = 1,6719,451,451,451
BEGIN DESCRIPTION:
Stream0519 11.0
END DESCRIPTION:
XS GIS Cut Line= 3
      2485275.02     13645774.96      2485425.00     13645425.00
      2485275.00     13644624.99
#Sta/Elev= 30
  4628.1  270.78  4660.7  269.17  4689.7  266.08  4713.3  265.37  4718.7  265.99
  4749.3  263.62  4789.4  262.11  4873.1  257.51  4926.9  254.13  4976.2  253.00
  4987.1  250.66  5003.5  249.63  5003.9  249.13  5008.3  249.13  5008.7  249.63
  5011.4  249.63  5019.0  253.78  5029.2  255.04  5040.2  254.49  5076.2  254.71
  5171.6  256.45  5181.8  255.95  5381.2  257.95  5426.0  258.13  5507.4  259.80
  5599.0  263.29  5619.3  265.07  5700.7  269.20  5810.9  277.07  5822.8  278.11
#Mann=9,-1,0
  4628.1    0.05       0  4749.3    0.07       0  4873.1     0.1       0
  4926.9    0.07       0  5003.5    0.05       0  5008.7    0.07       0
  5076.2    0.12       0  5381.2    0.07       0  5810.9   0.035       0
Bank Sta=5003.5,5008.7
Exp/Cntr=0.3,0.1

Type RM Length L Ch R = 1,6268,439,439,439
BEGIN DESCRIPTION:
Stream0519 10.0
END DESCRIPTION:
XS GIS Cut Line= 3
      2485475.03     13645924.97      2485825.00     13645525.00
      2486624.98     13644725.02
#Sta/Elev= 30
  4485.0  271.28  4670.2  262.89  4860.3  254.94  4867.9  254.24  4888.8  247.86
  4914.6  245.36  4915.0  244.86  4919.9  245.36  4945.8  245.96  4952.4  247.04
  4960.0  248.52  4980.9  256.01  4995.1  258.06  5002.7  257.50  5013.1  253.27
  5030.6  251.52  5044.7  252.40  5101.3  250.77  5313.4  255.06  5341.7  251.44
  5355.9  251.06  5412.4  252.70  5444.8  255.60  5582.1  264.73  5596.3  266.69
  5822.6  283.28  5900.3  290.47  5964.0  292.99  6091.3  301.30  6147.8  306.16
#Mann=5,-1,0
  4485.0    0.05       0  4670.2    0.07       0  4914.6    0.05       0
  4919.9    0.07       0  5444.8    0.07       0
Bank Sta=4914.6,4919.9
Exp/Cntr=0.3,0.1

Type RM Length L Ch R = 1,5829,428,428,428
BEGIN DESCRIPTION:
Stream0519 9.0
END DESCRIPTION:
XS GIS Cut Line= 3
      2485774.98     13646075.02      2486175.00     13645675.00
      2486575.00     13645275.00
#Sta/Elev= 30
  4430.1  265.51  4474.0  263.70  4642.3  256.48  4656.4  256.77  4684.7  255.29
  4769.5  253.23  4783.7  252.49  4840.3  251.39  4905.1  251.19  4981.7  250.37
  4992.3  247.03  4999.4  247.03  5007.3  244.69  5007.7  244.19  5012.2  244.19
  5012.7  244.69  5024.1  246.92  5038.2  247.96  5066.5  248.71  5094.8  248.47
  5123.1  246.57  5137.2  247.81  5165.5  248.84  5193.8  250.80  5222.1  251.27
  5328.2  255.72  5377.7  257.71  5448.4  262.14  5504.9  264.32  5561.5  268.43
#Mann=6,-1,0
  4430.1    0.05       0  4474.0    0.07       0  4905.1     0.1       0
  5007.3    0.05       0  5012.7     0.1       0  5328.2    0.07       0
Bank Sta=5007.3,5012.7
Exp/Cntr=0.3,0.1

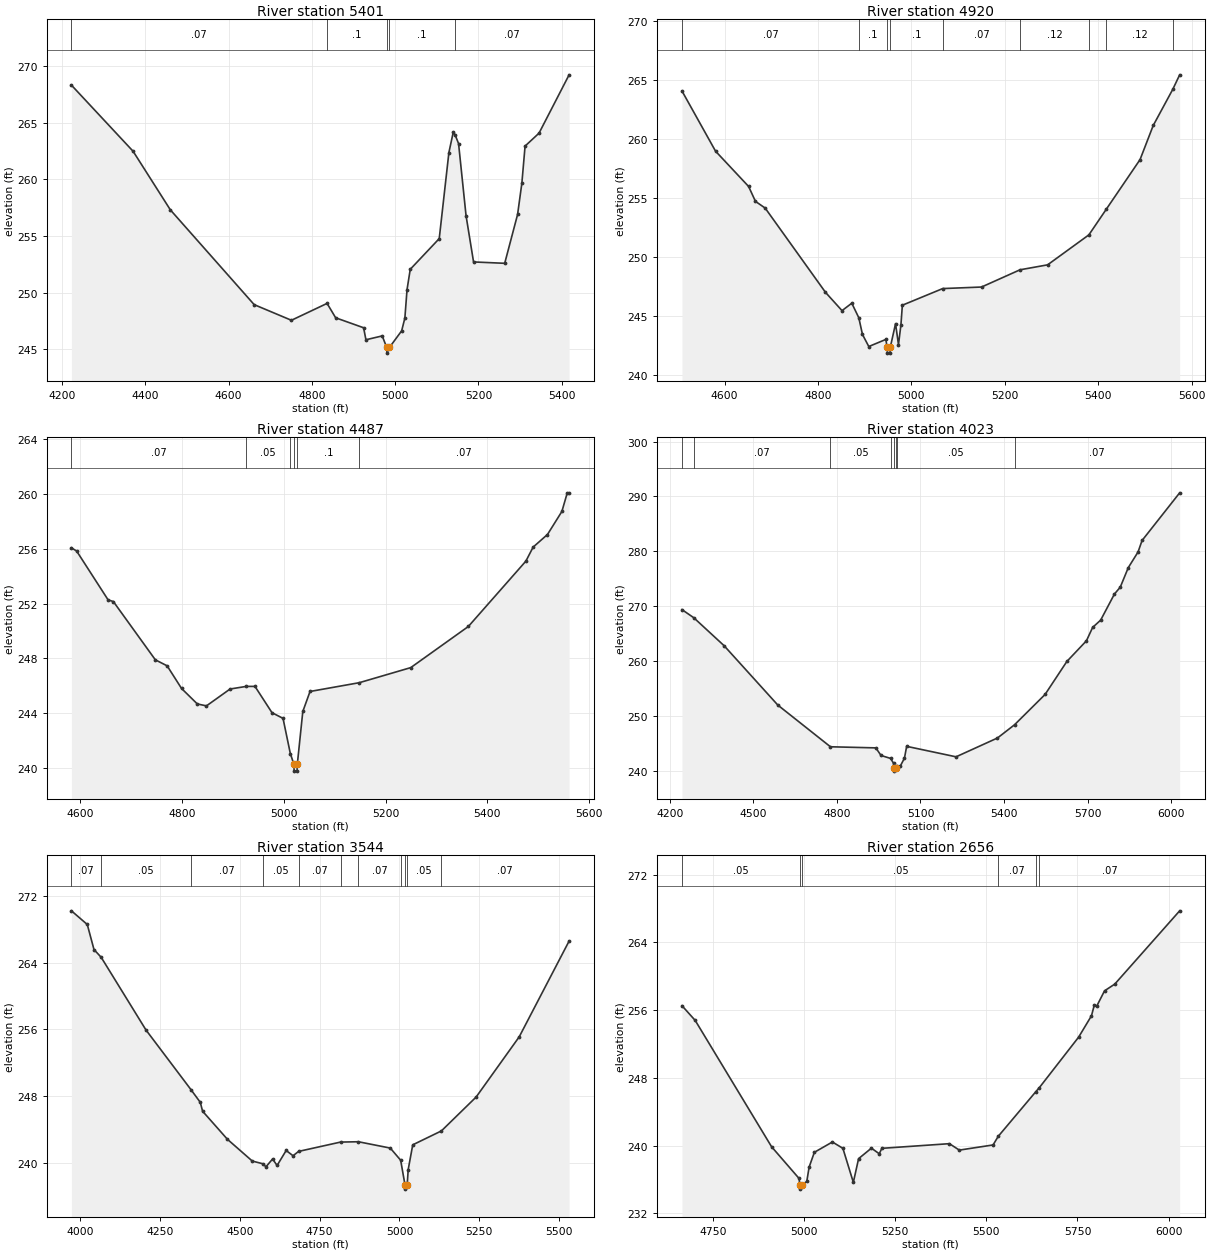
Type RM Length L Ch R = 1,5401,481,481,481
BEGIN DESCRIPTION:
Stream0519 8.0
END DESCRIPTION:
XS GIS Cut Line= 3
      2486175.02     13646374.97      2486525.00     13645675.00
      2486625.00     13645275.00
#Sta/Elev= 30
  4222.8  268.31  4370.9  262.47  4460.3  257.30  4661.6  248.93  4751.0  247.55
  4836.6  249.04  4857.2  247.77  4924.3  246.89  4929.9  245.83  4969.0  246.17
  4979.8  245.15  4980.3  244.65  4986.3  245.15  5015.7  246.62  5023.4  247.75
  5028.6  250.26  5036.3  252.05  5105.9  254.76  5129.1  262.36  5139.4  264.13
  5143.9  263.93  5152.3  263.15  5170.3  256.78  5188.3  252.70  5263.1  252.58
  5294.0  256.89  5304.3  259.66  5312.0  262.93  5345.5  264.07  5417.7  269.22
#Mann=5,-1,0
  4222.8    0.07       0  4836.6     0.1       0  4979.8    0.05       0
  4986.3     0.1       0  5143.9    0.07       0
Bank Sta=4979.8,4986.3
Exp/Cntr=0.3,0.1

Type RM Length L Ch R = 1,4920,433,433,433
BEGIN DESCRIPTION:
Stream0519 7.0
END DESCRIPTION:
XS GIS Cut Line= 3
      2486324.98     13646375.01      2486725.00     13646075.00
      2487124.99     13645675.01
#Sta/Elev= 30
  4508.7  264.05  4580.6  258.95  4651.4  255.96  4666.0  254.70  4686.8  254.13
  4816.0  246.99  4851.4  245.44  4872.3  246.07  4887.3  244.84  4895.2  243.42
  4908.7  242.40  4945.2  243.00  4948.1  242.34  4948.6  241.84  4954.3  241.84
  4954.8  242.34  4966.0  244.34  4972.3  242.56  4977.5  244.23  4980.6  245.90
  5067.0  247.31  5150.1  247.44  5232.5  248.90  5291.6  249.32  5380.0  251.86
  5417.4  254.04  5489.6  258.24  5517.8  261.13  5559.9  264.21  5574.4  265.42
#Mann=9,-1,0
  4508.7    0.07       0  4887.3     0.1       0  4948.1    0.05       0
  4954.8     0.1       0  5067.0    0.07       0  5232.5    0.12       0
  5380.0    0.07       0  5417.4    0.12       0  5559.9    0.07       0
Bank Sta=4948.1,4954.8
Exp/Cntr=0.3,0.1

Type RM Length L Ch R = 1,4487,464,464,464
BEGIN DESCRIPTION:
Stream0519 6.0
END DESCRIPTION:
XS GIS Cut Line= 3
      2486475.02     13646424.99      2486875.00     13646325.00
      2487275.02     13645924.98
#Sta/Elev= 30
  4582.6  256.07  4592.9  255.83  4654.7  252.27  4665.0  252.15  4747.5  247.90
  4770.7  247.46  4799.0  245.81  4830.0  244.68  4848.0  244.54  4894.4  245.77
  4926.2  245.96  4943.3  245.96  4976.8  244.04  4998.4  243.63  5012.8  241.06
  5019.8  240.28  5020.3  239.78  5026.0  239.78  5026.5  240.28  5037.3  244.13
  5051.5  245.59  5148.2  246.23  5249.4  247.33  5362.6  250.33  5475.7  255.10
  5489.9  256.12  5518.1  257.04  5546.4  258.72  5557.0  260.08  5560.6  260.08
#Mann=6,-1,0
  4582.6    0.07       0  4926.2    0.05       0  5012.8     0.1       0
  5019.8    0.05       0  5026.5     0.1       0  5148.2    0.07       0
Bank Sta=5019.8,5026.5
Exp/Cntr=0.3,0.1

Type RM Length L Ch R = 1,4023,479,479,479
BEGIN DESCRIPTION:
Stream0519 5.0
END DESCRIPTION:
XS GIS Cut Line= 3
      2486225.01     13646625.00      2486975.00     13646725.00
      2487775.00     13646075.00
#Sta/Elev= 30
  4243.4  269.35  4285.8  267.87  4394.7  262.77  4587.7  251.94  4776.6  244.34
  4939.5  244.14  4958.4  242.75  4992.5  242.22  5003.2  241.34  5003.8  240.40
  5004.3  239.90  5010.6  240.40  5017.1  240.78  5028.0  240.87  5042.4  242.27
  5050.3  244.42  5227.7  242.51  5376.4  245.94  5437.7  248.35  5547.4  253.88
  5625.7  259.90  5696.0  263.67  5718.3  266.11  5747.1  267.44  5796.6  272.20
  5817.5  273.45  5846.2  277.00  5881.4  279.87  5895.8  281.96  6030.8  290.65
#Mann=8,-1,0
  4243.4    0.05       0  4285.8    0.07       0  4776.6    0.05       0
  4992.5     0.1       0  5003.8    0.05       0  5010.6     0.1       0
  5017.1    0.05       0  5437.7    0.07       0
Bank Sta=5003.8,5010.6
Exp/Cntr=0.3,0.1

Type RM Length L Ch R = 1,3544,888,888,888
BEGIN DESCRIPTION:
Stream0519 4.0
END DESCRIPTION:
XS GIS Cut Line= 3
      2486575.00     13647625.00      2487275.00     13646875.00
      2487674.99     13646525.01
#Sta/Elev= 30
  3973.4  270.23  4023.0  268.59  4044.0  265.58  4066.5  264.65  4206.7  255.92
  4347.6  248.75  4376.7  247.23  4383.8  246.17  4461.7  242.79  4539.4  240.18
  4574.0  239.84  4581.9  239.48  4602.9  240.43  4617.0  239.65  4645.4  241.45
  4666.9  240.82  4684.3  241.34  4815.6  242.46  4871.4  242.50  4971.2  241.74
  5003.7  240.28  5017.3  237.31  5017.8  236.81  5024.1  237.31  5027.3  239.16
  5041.5  242.13  5131.2  243.80  5239.9  247.87  5374.7  255.10  5530.8  266.60
#Mann=11,-1,0
  3973.4    0.07       0  4066.5    0.05       0  4347.6    0.07       0
  4574.0    0.05       0  4684.3    0.07       0  4815.6     0.1       0
  4871.4    0.07       0  5003.7    0.05       0  5017.3    0.05       0
  5024.1    0.05       0  5131.2    0.07       0
Bank Sta=5017.3,5024.1
Exp/Cntr=0.3,0.1

Type RM Length L Ch R = 1,2656,466,466,466
BEGIN DESCRIPTION:
Stream0519 2.0
END DESCRIPTION:
XS GIS Cut Line= 3
      2486975.03     13647674.99      2487275.00     13647525.00
      2487925.03     13646724.96
#Sta/Elev= 30
  4664.4  256.53  4700.7  254.79  4910.3  239.87  4985.8  236.12  4987.9  235.36
  4988.4  234.86  4994.9  235.36  5007.0  235.77  5013.4  237.46  5027.8  239.21
  5077.3  240.43  5106.1  239.68  5134.8  235.66  5149.2  238.46  5184.4  239.70
  5205.9  239.04  5213.1  239.68  5398.5  240.23  5425.7  239.47  5518.4  240.08
  5532.6  241.10  5635.5  246.36  5645.4  246.85  5753.3  252.82  5788.5  255.34
  5796.4  256.63  5802.8  256.47  5824.4  258.29  5852.4  259.08  6030.6  267.74
#Mann=6,-1,0
  4664.4    0.05       0  4987.9    0.05       0  4994.9    0.05       0
  5532.6    0.07       0  5635.5    0.05       0  5645.4    0.07       0
Bank Sta=4987.9,4994.9
Exp/Cntr=0.3,0.1