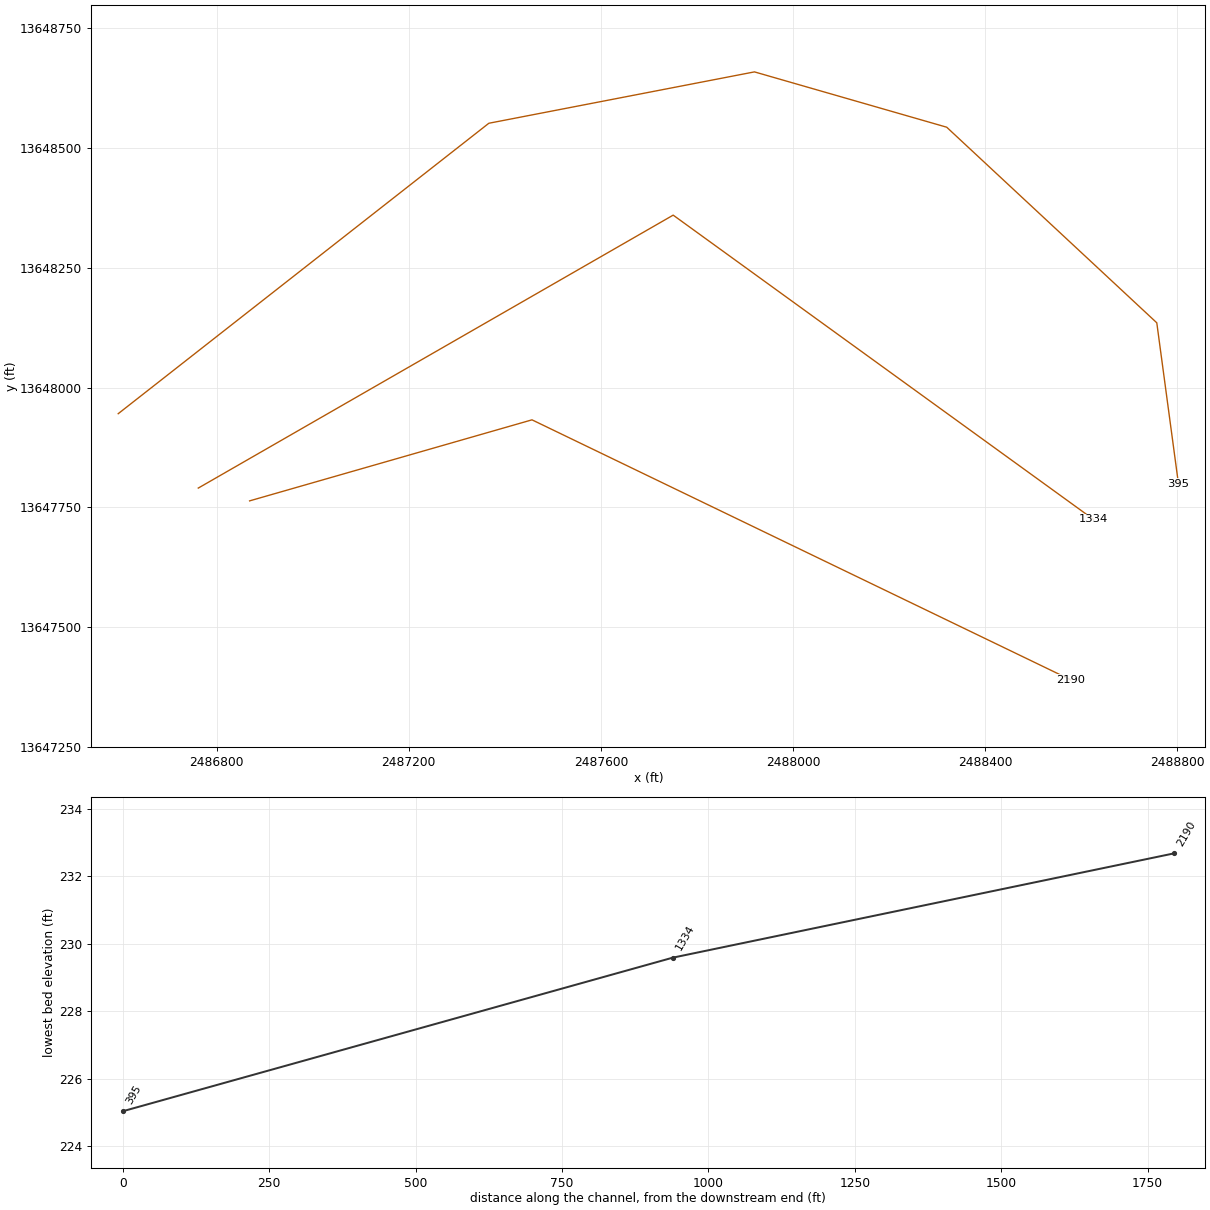
HEC-RAS study Stream0519.prj: Stream0519 Base Level Engineering

--- Stream0519.g01 (geometry) --- (continued)

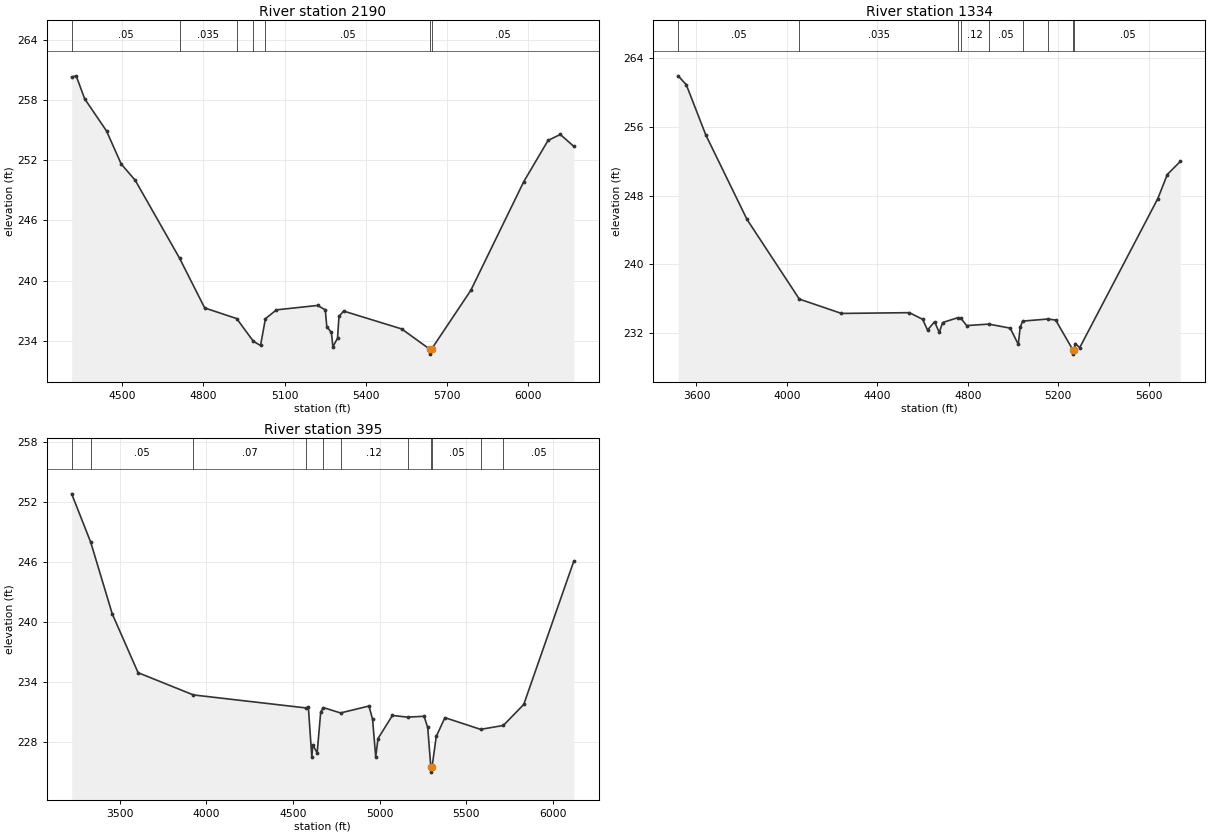
Type RM Length L Ch R = 1,2190,856,856,856
BEGIN DESCRIPTION:
XS7018
END DESCRIPTION:
XS GIS Cut Line= 3
      2486868.90     13647763.36      2487456.70     13647932.58
      2488578.13     13647389.67
#Sta/Elev= 30
  4312.5  260.27  4329.3  260.39  4360.5  258.11  4441.7  254.89  4495.7  251.61
  4547.8  249.98  4711.5  242.23  4804.6  237.27  4923.0  236.21  4984.9  233.94
  5011.2  233.53  5029.3  236.20  5070.0  237.08  5222.3  237.52  5250.7  237.08
  5256.3  235.40  5273.3  234.83  5278.8  233.41  5295.9  234.24  5301.4  236.43
  5318.5  236.96  5533.3  235.18  5636.7  233.17  5637.2  232.67  5643.7  233.17
  5788.9  239.02  5984.5  249.83  6074.9  253.96  6120.0  254.55  6170.1  253.36
#Mann=7,-1,0
  4312.5    0.05       0  4711.5   0.035       0  4923.0     0.1       0
  4984.9    0.07       0  5029.3    0.05       0  5636.7    0.05       0
  5643.7    0.05       0
Bank Sta=5636.7,5643.7
Exp/Cntr=0.3,0.1

Type RM Length L Ch R = 1,1334,939,939,939
BEGIN DESCRIPTION:
Stream0519 1.0
END DESCRIPTION:
XS GIS Cut Line= 3
      2486762.04     13647790.07      2487750.58     13648360.04
      2488625.02     13647724.98
#Sta/Elev= 30
  3518.8  261.93  3554.9  260.90  3641.1  255.07  3823.5  245.24  4055.0  235.98
  4241.5  234.31  4541.7  234.40  4600.6  233.63  4622.2  232.38  4653.4  233.34
  4674.3  232.10  4688.9  233.25  4755.6  233.81  4769.0  233.77  4795.6  232.90
  4893.2  233.07  4988.1  232.60  5023.8  230.72  5032.1  232.68  5042.9  233.42
  5154.6  233.66  5189.1  233.54  5265.2  230.08  5265.7  229.58  5272.2  230.08
  5274.9  230.81  5295.7  230.34  5641.3  247.67  5683.0  250.46  5740.6  251.98
#Mann=9,-1,0
  3518.8    0.05       0  4055.0   0.035       0  4755.6     0.1       0
  4769.0    0.12       0  4893.2    0.05       0  5042.9    0.07       0
  5154.6    0.05       0  5265.2    0.05       0  5272.2    0.05       0
Bank Sta=5265.2,5272.2
Exp/Cntr=0.3,0.1

Type RM Length L Ch R = 1,395,0,0,0
BEGIN DESCRIPTION:
E21130
END DESCRIPTION:
XS GIS Cut Line= 6
      2486595.38     13647945.42      2487366.90     13648551.90
      2487919.73     13648659.17      2488319.92     13648543.65
      2488757.23     13648135.21      2488802.41     13647798.44
#Sta/Elev= 30
  3222.6  252.82  3333.0  247.97  3457.0  240.83  3606.1  234.96  3925.2  232.74
  4575.1  231.44  4589.1  231.53  4609.2  226.51  4614.3  227.75  4640.0  226.96
  4660.4  231.02  4674.8  231.48  4774.7  230.94  4939.1  231.63  4959.9  230.30
  4978.0  226.54  4991.2  228.38  5074.4  230.69  5162.0  230.52  5257.2  230.61
  5278.2  229.49  5296.2  225.53  5296.7  225.03  5303.2  225.53  5327.5  228.59
  5377.4  230.47  5583.7  229.30  5714.7  229.69  5832.7  231.79  6121.8  246.11
#Mann=11,-1,0
  3222.6    0.07       0  3333.0    0.05       0  3925.2    0.07       0
  4575.1    0.12       0  4674.8     0.1       0  4774.7    0.12       0
  5162.0    0.05       0  5296.2    0.05       0  5303.2    0.05       0
  5583.7   0.035       0  5714.7    0.05       0
Bank Sta=5296.2,5303.2
Exp/Cntr=0.3,0.1

Chan Stop Cuts=-1