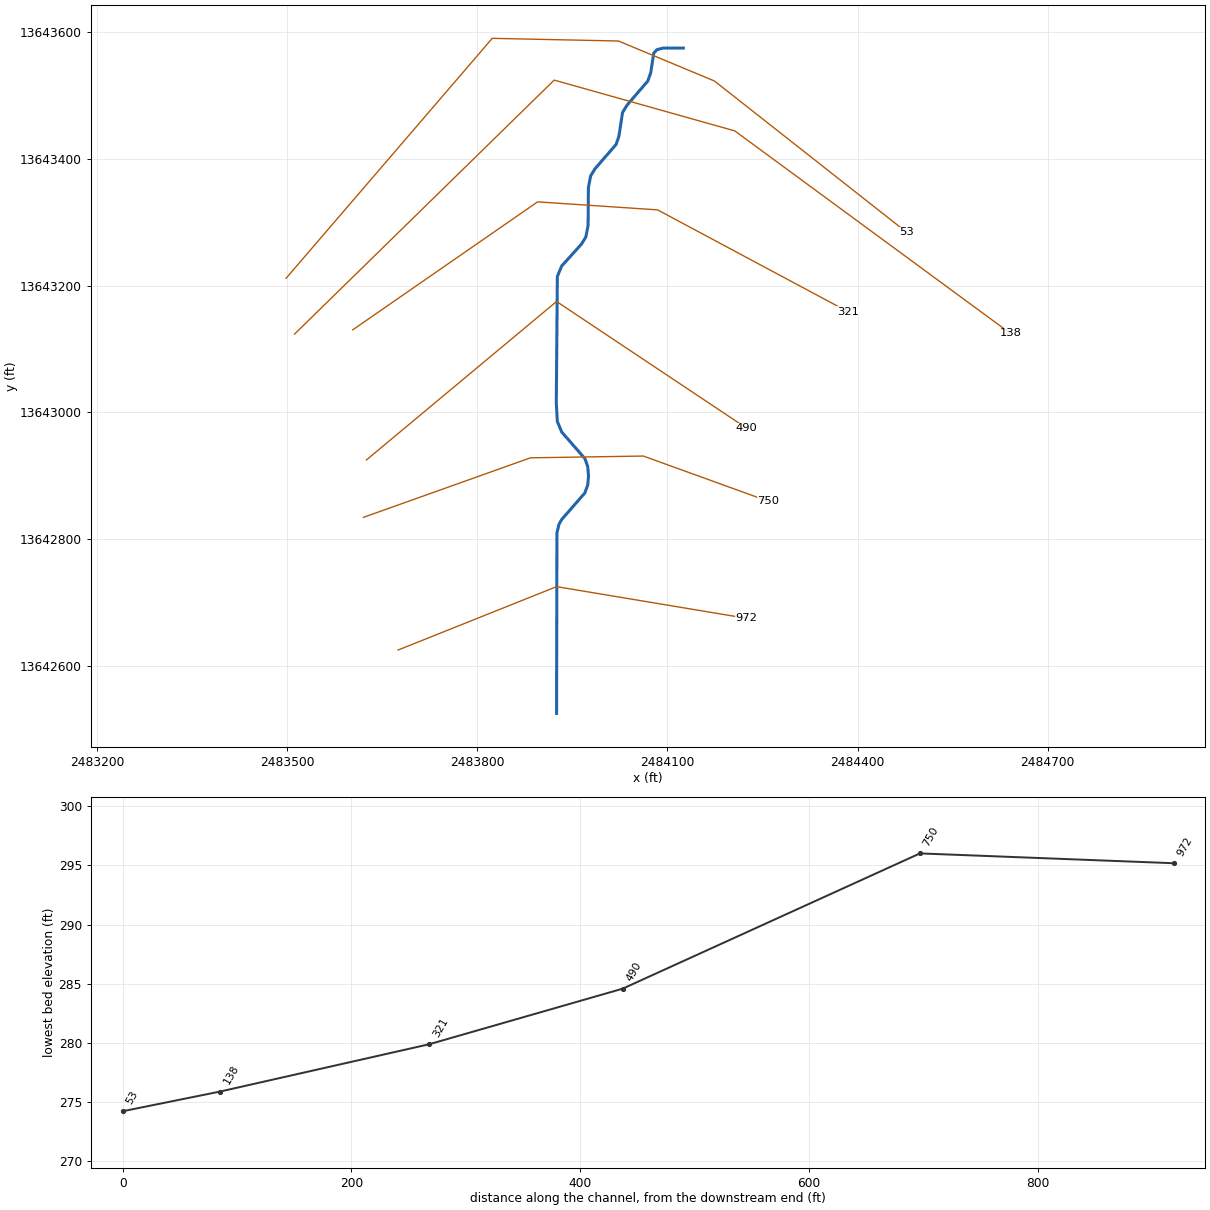
--- Stream0520.prj (project) ---

Proj Title=Stream0520 Base Level Engineering
Current Plan=p01
Default Exp/Contr=0.3,0.1
English Units
Geom File=g01
Flow File=f01
Plan File=p01
BEGIN DESCRIPTION:
Stream0520
END DESCRIPTION:

--- Stream0520.p01 (plan) ---

Plan Title=Multiple Run
Short Identifier=Multiple
Geom File=g01
Flow File=f01
Subcritical Flow
K Sum by GR= 0
Std Step Tol= 0.01
Critical Tol= 0.01
Num of Std Step Trials= 20
Max Error Tol= 0.3
Flow Tol Ratio= 0.001
Split Flow NTrial= 30
Split Flow Tol= 0.02
Split Flow Ratio= 0.02
Log Output Level= 0
Friction Slope Method= 1
Unsteady Friction Slope Method= 2
Unsteady Bridges Friction Slope Method= 1
Parabolic Critical Depth
Global Vel Dist=  1 , 1 , 1
Global Log Level= 0
CheckData=True
Encroach Param= -1, 0, 0, 0
BEGIN DESCRIPTION:
Multiple Run
END DESCRIPTION:

--- Stream0520.f01 (steady flow) ---

Flow Title=Multiple
Number of Profiles=7
Profile Names=10-year,25-year,50-year,1pct_min,100-year,1pct_plu,500-year
River Rch & RM= Stream0520,Reach-1,972
     229     348     450     285     568    1133     888
Boundary for River Rch & Prof#=Stream0520,Reach-1,1
Up Type=0
Dn Type=3
Dn Slope=0.005
Boundary for River Rch & Prof#=Stream0520,Reach-1,2
Up Type=0
Dn Type=3
Dn Slope=0.005
Boundary for River Rch & Prof#=Stream0520,Reach-1,3
Up Type=0
Dn Type=3
Dn Slope=0.005
Boundary for River Rch & Prof#=Stream0520,Reach-1,4
Up Type=0
Dn Type=3
Dn Slope=0.005
Boundary for River Rch & Prof#=Stream0520,Reach-1,5
Up Type=0
Dn Type=3
Dn Slope=0.005
Boundary for River Rch & Prof#=Stream0520,Reach-1,6
Up Type=0
Dn Type=3
Dn Slope=0.005
Boundary for River Rch & Prof#=Stream0520,Reach-1,7
Up Type=0
Dn Type=3
Dn Slope=0.005

--- Stream0520.g01 (geometry) ---

Geom Title=Existing Conditions

River Reach=Stream0520,Reach-1
Reach XY= 30
      2483925.00     13642525.00      2483925.54     13642809.79
      2483928.81     13642823.45      2483933.19     13642831.08
      2483969.62     13642872.82      2483974.23     13642885.69
      2483975.40     13642900.00      2483974.23     13642914.31
      2483969.62     13642927.18      2483933.19     13642968.92
      2483926.24     13642985.50      2483924.55     13643014.81
      2483926.22     13643214.50      2483933.14     13643231.06
      2483964.11     13643265.37      2483971.14     13643276.60
      2483974.76     13643295.10      2483975.23     13643354.91
      2483978.83     13643373.42      2483985.84     13643384.65
      2484018.89     13643422.82      2484023.33     13643435.69
      2484029.13     13643473.31      2484036.04     13643484.60
      2484069.00     13643522.99      2484073.55     13643535.87
      2484078.41     13643567.01      2484083.40     13643572.39
      2484093.44     13643574.94      2484125.00     13643575.00

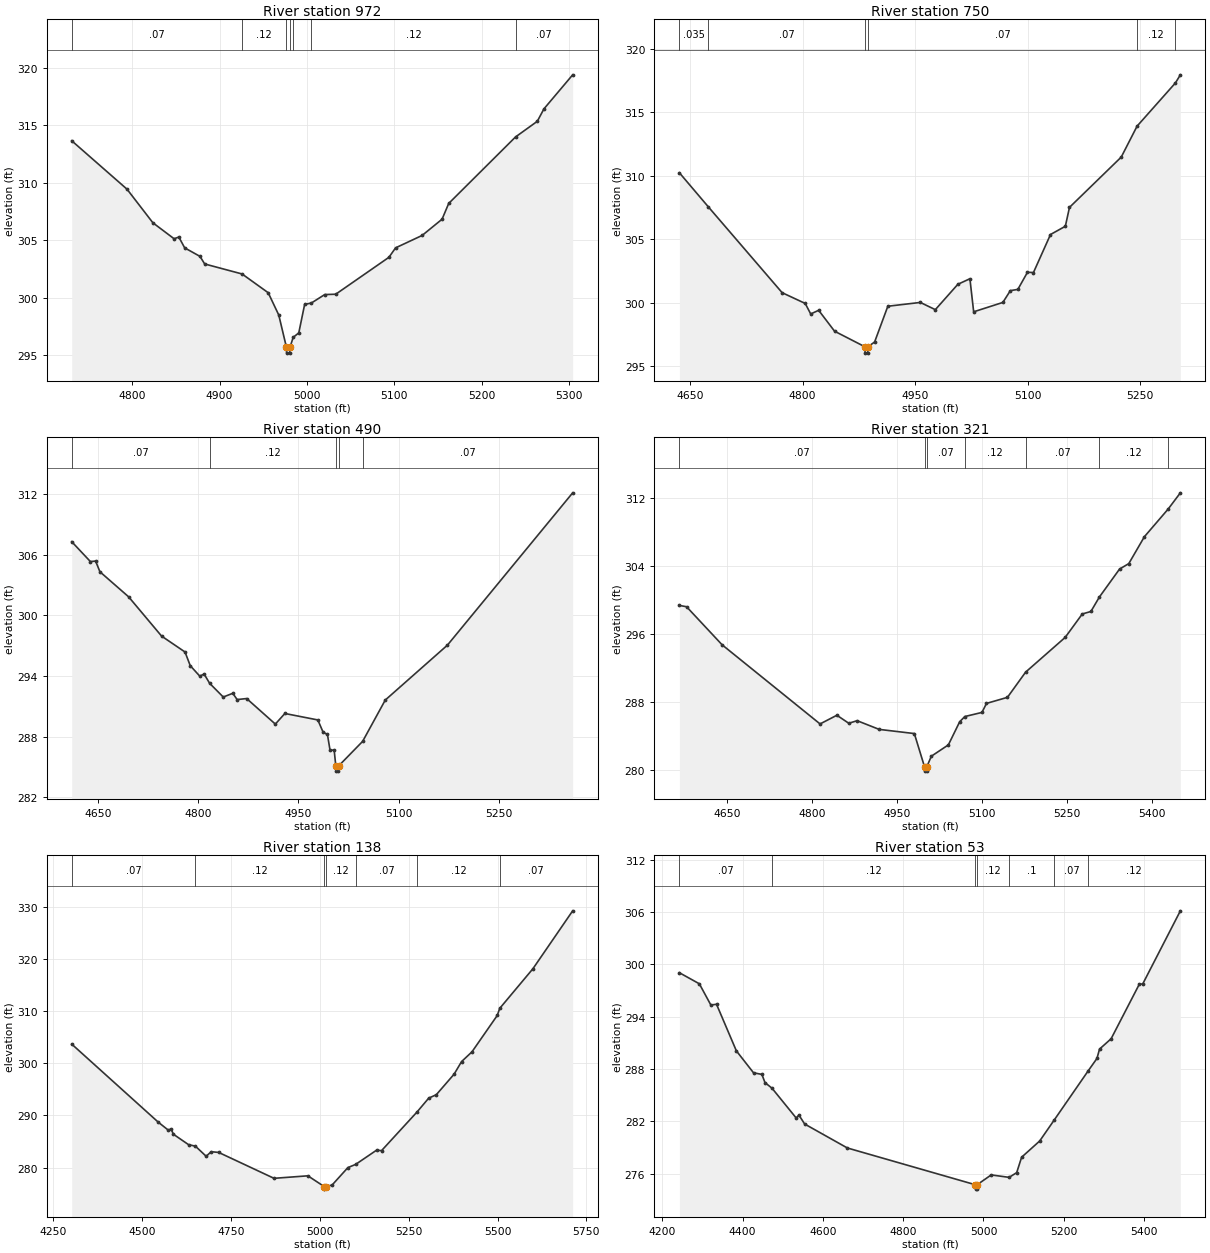
Type RM Length L Ch R = 1,972,222,222,222
BEGIN DESCRIPTION:
Stream0520 2.0
END DESCRIPTION:
XS GIS Cut Line= 3
      2483674.96     13642624.99      2483925.00     13642725.00
      2484224.97     13642675.01
#Sta/Elev= 30
  4730.8  313.64  4794.1  309.43  4823.7  306.51  4848.0  305.12  4853.4  305.27
  4860.1  304.33  4877.6  303.59  4883.0  302.93  4925.8  302.06  4955.7  300.43
  4967.8  298.49  4976.6  295.68  4976.8  295.18  4980.3  295.18  4980.6  295.68
  4984.3  296.55  4990.7  296.94  4997.4  299.41  5005.2  299.54  5020.4  300.27
  5033.0  300.30  5093.9  303.51  5101.5  304.33  5131.9  305.41  5154.7  306.82
  5162.3  308.19  5238.8  313.97  5263.7  315.33  5271.3  316.41  5304.2  319.37
#Mann=7,-1,0
  4730.8    0.07       0  4925.8    0.12       0  4976.6    0.05       0
  4980.6    0.12       0  4984.3    0.07       0  5005.2    0.12       0
  5238.8    0.07       0
Bank Sta=4976.6,4980.6
Exp/Cntr=0.3,0.1

Type RM Length L Ch R = 1,750,260,260,260
BEGIN DESCRIPTION:
E21133
END DESCRIPTION:
XS GIS Cut Line= 4
      2483620.19     13642834.34      2483883.82     13642928.29
      2484061.94     13642931.10      2484259.12     13642859.78
#Sta/Elev= 30
  4635.9  310.24  4674.2  307.57  4772.8  300.78  4803.6  299.93  4810.9  299.10
  4821.5  299.39  4842.7  297.74  4883.2  296.51  4883.4  296.01  4886.9  296.01
  4887.2  296.51  4896.1  296.89  4913.7  299.71  4957.0  300.01  4977.0  299.44
  5007.0  301.44  5023.1  301.88  5028.1  299.27  5067.0  300.01  5077.0  300.94
  5087.0  301.04  5099.8  302.39  5107.8  302.37  5130.5  305.37  5150.3  306.02
  5155.8  307.51  5224.8  311.48  5245.9  313.92  5297.0  317.33  5303.6  317.97
#Mann=6,-1,0
  4635.9   0.035       0  4674.2    0.07       0  4883.2    0.05       0
  4887.2    0.07       0  5245.9    0.12       0  5297.0    0.07       0
Bank Sta=4883.2,4887.2
Exp/Cntr=0.3,0.1

Type RM Length L Ch R = 1,490,169,169,169
BEGIN DESCRIPTION:
Stream0520 1.0
END DESCRIPTION:
XS GIS Cut Line= 3
      2483624.99     13642924.99      2483925.00     13643175.00
      2484225.02     13642974.99
#Sta/Elev= 30
  4610.0  307.31  4638.0  305.34  4645.8  305.39  4652.3  304.33  4695.3  301.85
  4744.7  297.96  4779.9  296.38  4787.7  295.03  4802.0  293.99  4808.5  294.20
  4816.8  293.28  4837.2  291.92  4851.5  292.29  4858.0  291.67  4872.3  291.77
  4915.3  289.24  4929.6  290.29  4979.0  289.65  4986.9  288.44  4993.4  288.21
  4997.3  286.66  5003.5  286.66  5006.0  285.08  5006.3  284.58  5009.8  284.58
  5010.0  285.08  5046.2  287.53  5080.1  291.62  5173.3  297.06  5361.1  312.15
#Mann=5,-1,0
  4610.0    0.07       0  4816.8    0.12       0  5006.0    0.05       0
  5010.0    0.12       0  5046.2    0.07       0
Bank Sta=5006,5010
Exp/Cntr=0.3,0.1

Type RM Length L Ch R = 1,321,183,183,183
BEGIN DESCRIPTION:
E21132
END DESCRIPTION:
XS GIS Cut Line= 4
      2483603.35     13643130.28      2483895.04     13643332.22
      2484084.38     13643319.60      2484384.34     13643159.16
#Sta/Elev= 30
  4565.1  299.34  4577.7  299.19  4640.5  294.72  4813.5  285.43  4843.2  286.45
  4864.2  285.51  4879.0  285.81  4917.9  284.79  4980.0  284.30  4998.0  280.39
  4998.3  279.89  5001.8  279.89  5002.0  280.39  5010.0  281.64  5040.1  282.97
  5060.1  285.69  5069.2  286.30  5099.4  286.78  5107.4  287.84  5144.4  288.55
  5176.5  291.51  5246.4  295.59  5276.6  298.34  5291.8  298.63  5306.7  300.32
  5342.4  303.61  5358.7  304.25  5386.3  307.41  5428.3  310.66  5449.8  312.56
#Mann=7,-1,0
  4565.1    0.07       0  4998.0    0.05       0  5002.0    0.07       0
  5069.2    0.12       0  5176.5    0.07       0  5306.7    0.12       0
  5428.3    0.07       0
Bank Sta=4998,5002
Exp/Cntr=0.3,0.1

Type RM Length L Ch R = 1,138,85,85,85
BEGIN DESCRIPTION:
XS7022
END DESCRIPTION:
XS GIS Cut Line= 4
      2483511.61     13643123.66      2483921.24     13643524.38
      2484206.22     13643444.24      2484641.33     13643124.56
#Sta/Elev= 30
  4302.4  303.67  4546.1  288.70  4574.4  287.17  4581.6  287.44  4588.5  286.40
  4631.0  284.41  4650.3  284.12  4680.6  282.18  4694.7  283.06  4715.8  282.92
  4871.4  277.96  4966.6  278.44  5012.4  276.39  5012.6  275.89  5016.4  276.39
  5034.7  276.67  5079.1  280.01  5101.0  280.63  5159.8  283.35  5173.8  283.26
  5273.8  290.68  5306.5  293.32  5327.9  293.98  5378.0  297.92  5398.9  300.32
  5428.2  302.19  5499.2  309.15  5506.3  310.52  5599.5  318.10  5711.4  329.20
#Mann=7,-1,0
  4302.4    0.07       0  4650.3    0.12       0  5012.4    0.05       0
  5016.4    0.12       0  5101.0    0.07       0  5273.8    0.12       0
  5506.3    0.07       0
Bank Sta=5012.4,5016.4
Exp/Cntr=0.3,0.1

Type RM Length L Ch R = 1,53,0,0,0
BEGIN DESCRIPTION:
E21131
END DESCRIPTION:
XS GIS Cut Line= 5
      2483498.16     13643211.64      2483823.51     13643590.29
      2484022.67     13643586.08      2484174.15     13643522.96
      2484477.13     13643284.51
#Sta/Elev= 30
  4242.5  299.05  4292.2  297.78  4320.8  295.35  4335.0  295.43  4384.4  290.09
  4427.2  287.57  4448.0  287.39  4455.7  286.45  4473.3  285.80  4533.6  282.38
  4540.2  282.73  4554.5  281.70  4660.9  278.95  4980.0  274.73  4980.2  274.23
  4983.9  274.23  4984.2  274.73  5019.3  275.86  5064.0  275.58  5082.8  276.12
  5095.1  277.89  5140.1  279.75  5176.5  282.17  5261.3  287.82  5282.8  289.22
  5289.2  290.29  5318.1  291.48  5388.6  297.76  5396.7  297.75  5490.6  306.15
#Mann=7,-1,0
  4242.5    0.07       0  4473.3    0.12       0  4980.0    0.05       0
  4984.2    0.12       0  5064.0     0.1       0  5176.5    0.07       0
  5261.3    0.12       0
Bank Sta=4980,4984.2
Exp/Cntr=0.3,0.1

Chan Stop Cuts=-1