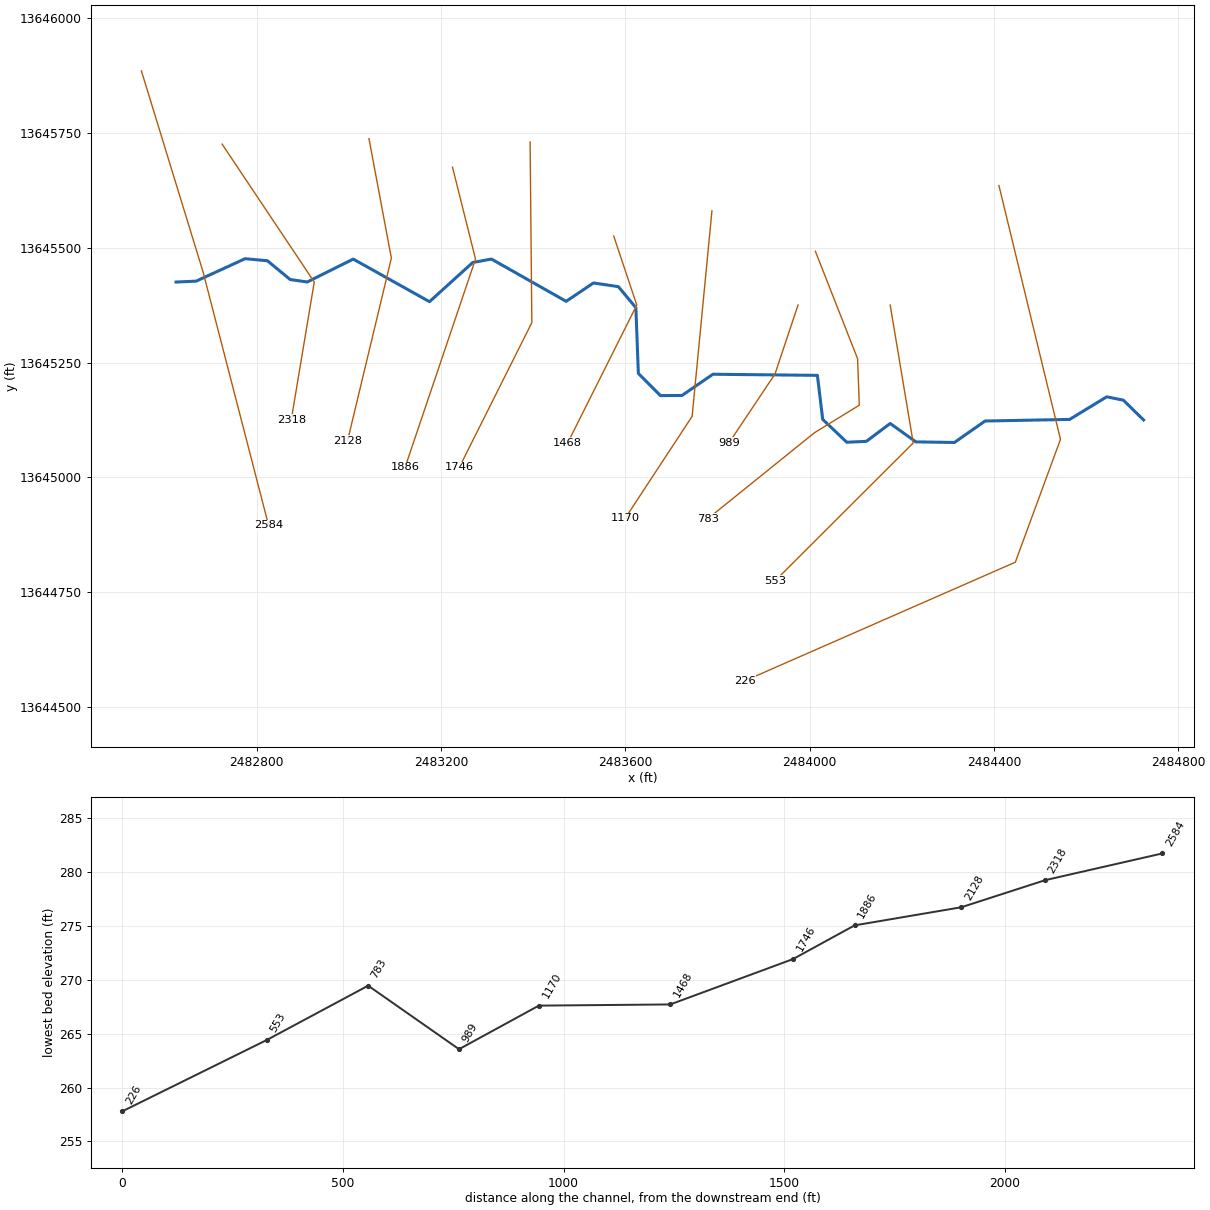
--- Stream0521.prj (project) ---

Proj Title=Stream0521 Base Level Engineering
Current Plan=p01
Default Exp/Contr=0.3,0.1
English Units
Geom File=g01
Flow File=f01
Plan File=p01
BEGIN DESCRIPTION:
Stream0521
END DESCRIPTION:

--- Stream0521.p01 (plan) ---

Plan Title=Multiple Run
Short Identifier=Multiple
Geom File=g01
Flow File=f01
Subcritical Flow
K Sum by GR= 0
Std Step Tol= 0.01
Critical Tol= 0.01
Num of Std Step Trials= 20
Max Error Tol= 0.3
Flow Tol Ratio= 0.001
Split Flow NTrial= 30
Split Flow Tol= 0.02
Split Flow Ratio= 0.02
Log Output Level= 0
Friction Slope Method= 1
Unsteady Friction Slope Method= 2
Unsteady Bridges Friction Slope Method= 1
Parabolic Critical Depth
Global Vel Dist=  1 , 1 , 1
Global Log Level= 0
CheckData=True
Encroach Param= -1, 0, 0, 0
BEGIN DESCRIPTION:
Multiple Run
END DESCRIPTION:

--- Stream0521.f01 (steady flow) ---

Flow Title=Multiple
Number of Profiles=7
Profile Names=10-year,25-year,50-year,1pct_min,100-year,1pct_plu,500-year
River Rch & RM= Stream0521,Reach-1,2584
     417     658     873     563    1122    2239    1834
Boundary for River Rch & Prof#=Stream0521,Reach-1,1
Up Type=0
Dn Type=3
Dn Slope=0.005
Boundary for River Rch & Prof#=Stream0521,Reach-1,2
Up Type=0
Dn Type=3
Dn Slope=0.005
Boundary for River Rch & Prof#=Stream0521,Reach-1,3
Up Type=0
Dn Type=3
Dn Slope=0.005
Boundary for River Rch & Prof#=Stream0521,Reach-1,4
Up Type=0
Dn Type=3
Dn Slope=0.005
Boundary for River Rch & Prof#=Stream0521,Reach-1,5
Up Type=0
Dn Type=3
Dn Slope=0.005
Boundary for River Rch & Prof#=Stream0521,Reach-1,6
Up Type=0
Dn Type=3
Dn Slope=0.005
Boundary for River Rch & Prof#=Stream0521,Reach-1,7
Up Type=0
Dn Type=3
Dn Slope=0.005

--- Stream0521.g01 (geometry) ---

Geom Title=Existing Conditions

River Reach=Stream0521,Reach-1
Reach XY= 30
      2482625.00     13645425.00      2482668.73     13645426.99
      2482775.00     13645475.82      2482823.42     13645471.27
      2482872.82     13645430.38      2482909.61     13645425.11
      2483009.61     13645474.92      2483175.08     13645382.30
      2483268.94     13645467.48      2483309.59     13645474.98
      2483471.69     13645383.07      2483531.09     13645423.04
      2483585.05     13645414.95      2483623.01     13645369.37
      2483628.45     13645226.19      2483676.39     13645178.03
      2483723.22     13645178.33      2483790.21     13645224.46
      2484017.03     13645222.06      2484028.56     13645126.30
      2484080.85     13645076.57      2484123.32     13645078.56
      2484174.99     13645117.40      2484230.89     13645077.36
      2484314.45     13645076.11      2484380.94     13645122.74
      2484564.51     13645126.23      2484645.11     13645175.44
      2484681.15     13645168.05      2484725.00     13645125.00

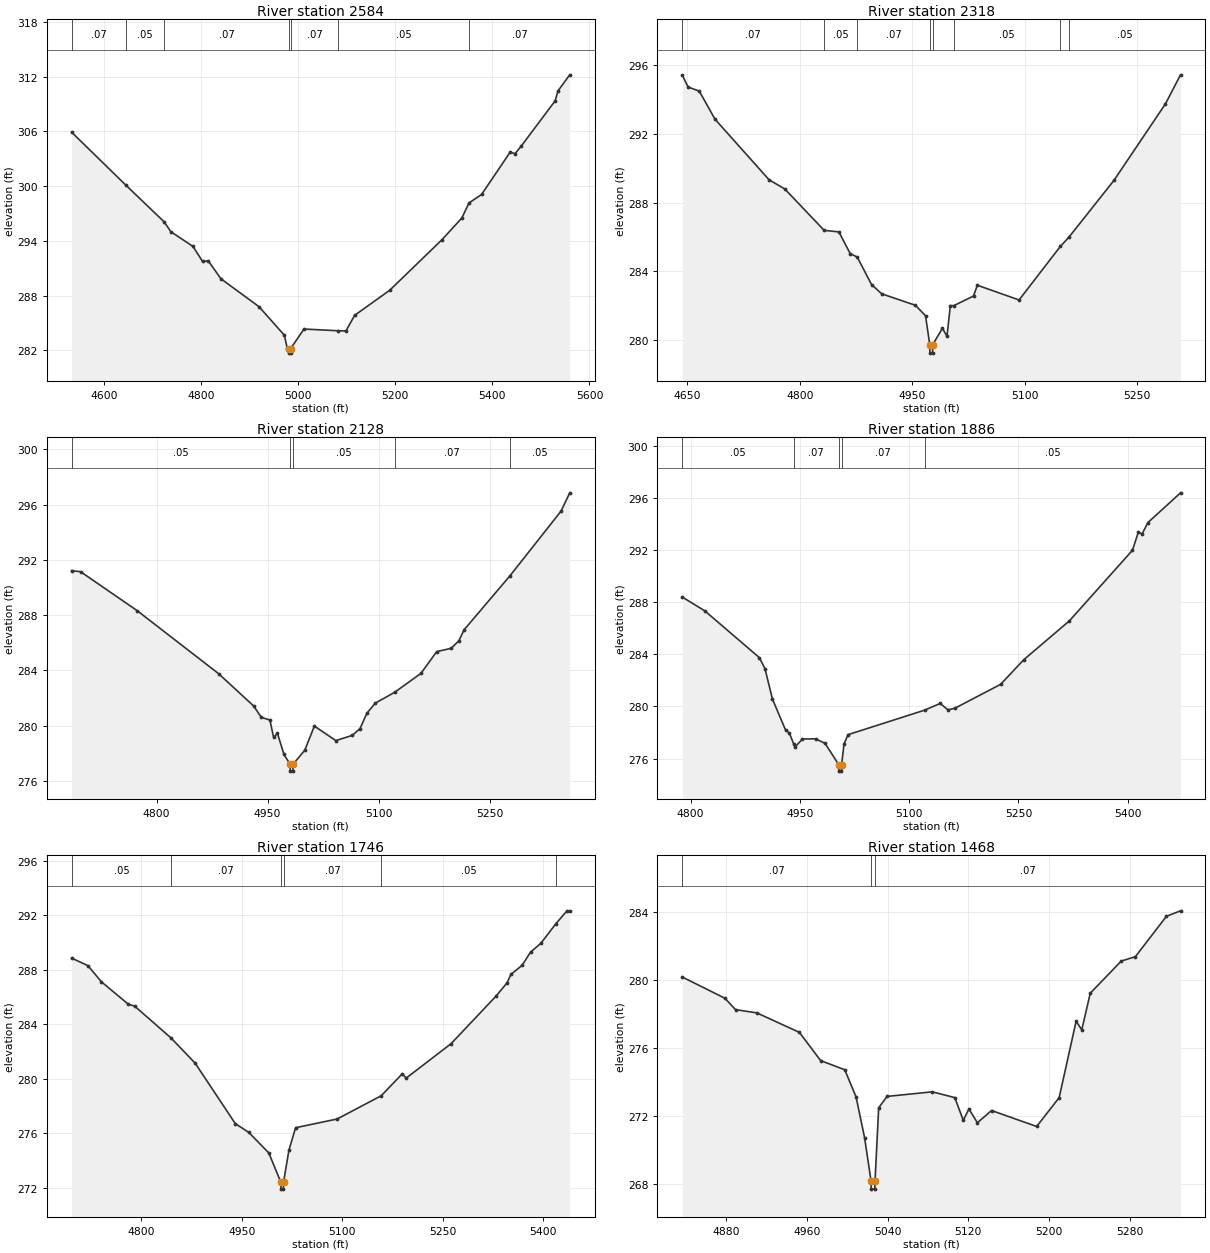
Type RM Length L Ch R = 1,2584,266,266,266
BEGIN DESCRIPTION:
XS7021
END DESCRIPTION:
XS GIS Cut Line= 3
      2482549.82     13645884.28      2482683.39     13645447.96
      2482825.87     13644895.86
#Sta/Elev= 30
  4532.8  305.91  4644.1  300.13  4723.8  296.07  4737.2  295.01  4783.0  293.39
  4802.7  291.74  4814.4  291.81  4840.7  289.84  4919.0  286.79  4971.3  283.66
  4977.0  282.29  4980.3  282.20  4980.5  281.70  4984.0  281.70  4984.3  282.20
  5011.6  284.34  5082.2  284.15  5098.1  284.13  5116.1  285.84  5188.4  288.59
  5296.3  294.14  5336.9  296.50  5351.9  298.16  5377.6  299.08  5436.3  303.70
  5446.6  303.56  5458.9  304.35  5529.2  309.34  5535.1  310.43  5559.3  312.19
#Mann=7,-1,0
  4532.8    0.07       0  4644.1    0.05       0  4723.8    0.07       0
  4980.3    0.05       0  4984.3    0.07       0  5082.2    0.05       0
  5351.9    0.07       0
Bank Sta=4980.3,4984.3
Exp/Cntr=0.3,0.1

Type RM Length L Ch R = 1,2318,190,190,190
BEGIN DESCRIPTION:
Stream0521 5.0
END DESCRIPTION:
XS GIS Cut Line= 3
      2482724.97     13645725.04      2482925.00     13645425.00
      2482875.01     13645125.04
#Sta/Elev= 30
  4643.3  295.43  4650.9  294.74  4665.9  294.50  4686.9  292.86  4759.0  289.33
  4780.1  288.79  4832.5  286.38  4852.2  286.29  4867.2  285.03  4876.7  284.82
  4895.7  283.22  4909.3  282.68  4954.3  282.01  4967.8  281.40  4973.4  279.72
  4973.6  279.22  4977.1  279.22  4977.4  279.72  4990.4  280.67  4996.4  280.20
  5000.9  281.99  5005.6  281.99  5031.8  282.55  5036.9  283.18  5092.6  282.32
  5147.6  285.44  5158.9  285.97  5219.3  289.30  5287.8  293.75  5308.0  295.45
#Mann=8,-1,0
  4643.3    0.07       0  4832.5    0.05       0  4876.7    0.07       0
  4973.4    0.05       0  4977.4    0.07       0  5005.6    0.05       0
  5147.6    0.07       0  5158.9    0.05       0
Bank Sta=4973.4,4977.4
Exp/Cntr=0.3,0.1

Type RM Length L Ch R = 1,2128,242,242,242
BEGIN DESCRIPTION:
E21137
END DESCRIPTION:
XS GIS Cut Line= 3
      2483043.73     13645736.97      2483092.36     13645477.03
      2482997.13     13645079.32
#Sta/Elev= 30
  4685.0  291.22  4697.2  291.14  4773.5  288.33  4883.8  283.76  4931.2  281.42
  4941.5  280.60  4953.1  280.41  4958.1  279.16  4963.3  279.44  4972.1  277.92
  4980.4  277.21  4980.6  276.71  4984.1  276.71  4984.4  277.21  5000.2  278.22
  5013.2  279.97  5042.2  278.92  5064.6  279.30  5074.9  279.79  5084.2  280.90
  5095.5  281.63  5121.6  282.41  5157.2  283.78  5178.6  285.36  5198.3  285.60
  5208.6  286.15  5215.5  286.93  5277.5  290.84  5346.7  295.53  5358.4  296.85
#Mann=5,-1,0
  4685.0    0.05       0  4980.4    0.05       0  4984.4    0.05       0
  5121.6    0.07       0  5277.5    0.05       0
Bank Sta=4980.4,4984.4
Exp/Cntr=0.3,0.1

Type RM Length L Ch R = 1,1886,140,140,140
BEGIN DESCRIPTION:
Stream0521 4.0
END DESCRIPTION:
XS GIS Cut Line= 3
      2483225.00     13645675.01      2483275.00     13645475.00
      2483122.29     13645022.54
#Sta/Elev= 30
  4788.8  288.40  4819.7  287.34  4894.5  283.75  4902.2  282.90  4912.5  280.56
  4930.5  278.18  4935.7  277.95  4941.5  277.14  4943.4  276.88  4953.7  277.50
  4971.8  277.51  4984.7  277.16  5003.4  275.53  5003.7  275.03  5007.2  275.03
  5007.4  275.53  5010.7  277.10  5016.1  277.83  5121.6  279.72  5142.7  280.23
  5153.3  279.74  5162.8  279.86  5225.7  281.70  5257.2  283.58  5320.1  286.58
  5406.6  292.00  5414.5  293.37  5419.8  293.25  5427.7  294.12  5472.5  296.41
#Mann=5,-1,0
  4788.8    0.05       0  4941.5    0.07       0  5003.4    0.05       0
  5007.4    0.07       0  5121.6    0.05       0
Bank Sta=5003.4,5007.4
Exp/Cntr=0.3,0.1

Type RM Length L Ch R = 1,1746,278,278,278
BEGIN DESCRIPTION:
E21136
END DESCRIPTION:
XS GIS Cut Line= 3
      2483393.50     13645729.54      2483397.24     13645336.74
      2483240.14     13645022.55
#Sta/Elev= 30
  4695.7  288.87  4720.2  288.31  4740.2  287.13  4780.2  285.49  4790.2  285.33
  4844.3  283.00  4880.3  281.15  4940.3  276.71  4960.3  276.07  4990.3  274.56
  5008.3  272.40  5008.5  271.90  5012.0  271.90  5012.3  272.40  5020.3  274.75
  5030.3  276.41  5092.3  277.05  5158.3  278.76  5189.8  280.38  5195.4  280.05
  5262.5  282.58  5329.6  286.07  5346.3  287.06  5351.9  287.67  5368.7  288.34
  5381.2  289.30  5396.7  289.96  5419.2  291.40  5435.7  292.34  5439.8  292.34
#Mann=6,-1,0
  4695.7    0.05       0  4844.3    0.07       0  5008.3    0.05       0
  5012.3    0.07       0  5158.3    0.05       0  5419.2   0.035       0
Bank Sta=5008.3,5012.3
Exp/Cntr=0.3,0.1

Type RM Length L Ch R = 1,1468,298,298,298
BEGIN DESCRIPTION:
Stream0521 3.0
END DESCRIPTION:
XS GIS Cut Line= 3
      2483575.00     13645525.00      2483625.00     13645375.00
      2483475.01     13645075.02
#Sta/Elev= 30
  4836.7  280.19  4878.9  278.94  4889.4  278.27  4910.5  278.08  4952.7  276.93
  4973.7  275.27  4997.6  274.73  5008.8  273.13  5017.2  270.74  5023.6  268.20
  5023.8  267.70  5027.3  267.70  5027.6  268.20  5031.2  272.49  5039.5  273.16
  5084.3  273.43  5106.6  273.09  5115.0  271.75  5120.6  272.42  5129.0  271.61
  5143.0  272.33  5187.7  271.39  5210.0  273.09  5226.8  277.59  5232.4  277.08
  5240.8  279.24  5271.5  281.13  5285.5  281.39  5316.3  283.77  5330.2  284.09
#Mann=3,-1,0
  4836.7    0.07       0  5023.6    0.05       0  5027.6    0.07       0
Bank Sta=5023.6,5027.6
Exp/Cntr=0.3,0.1

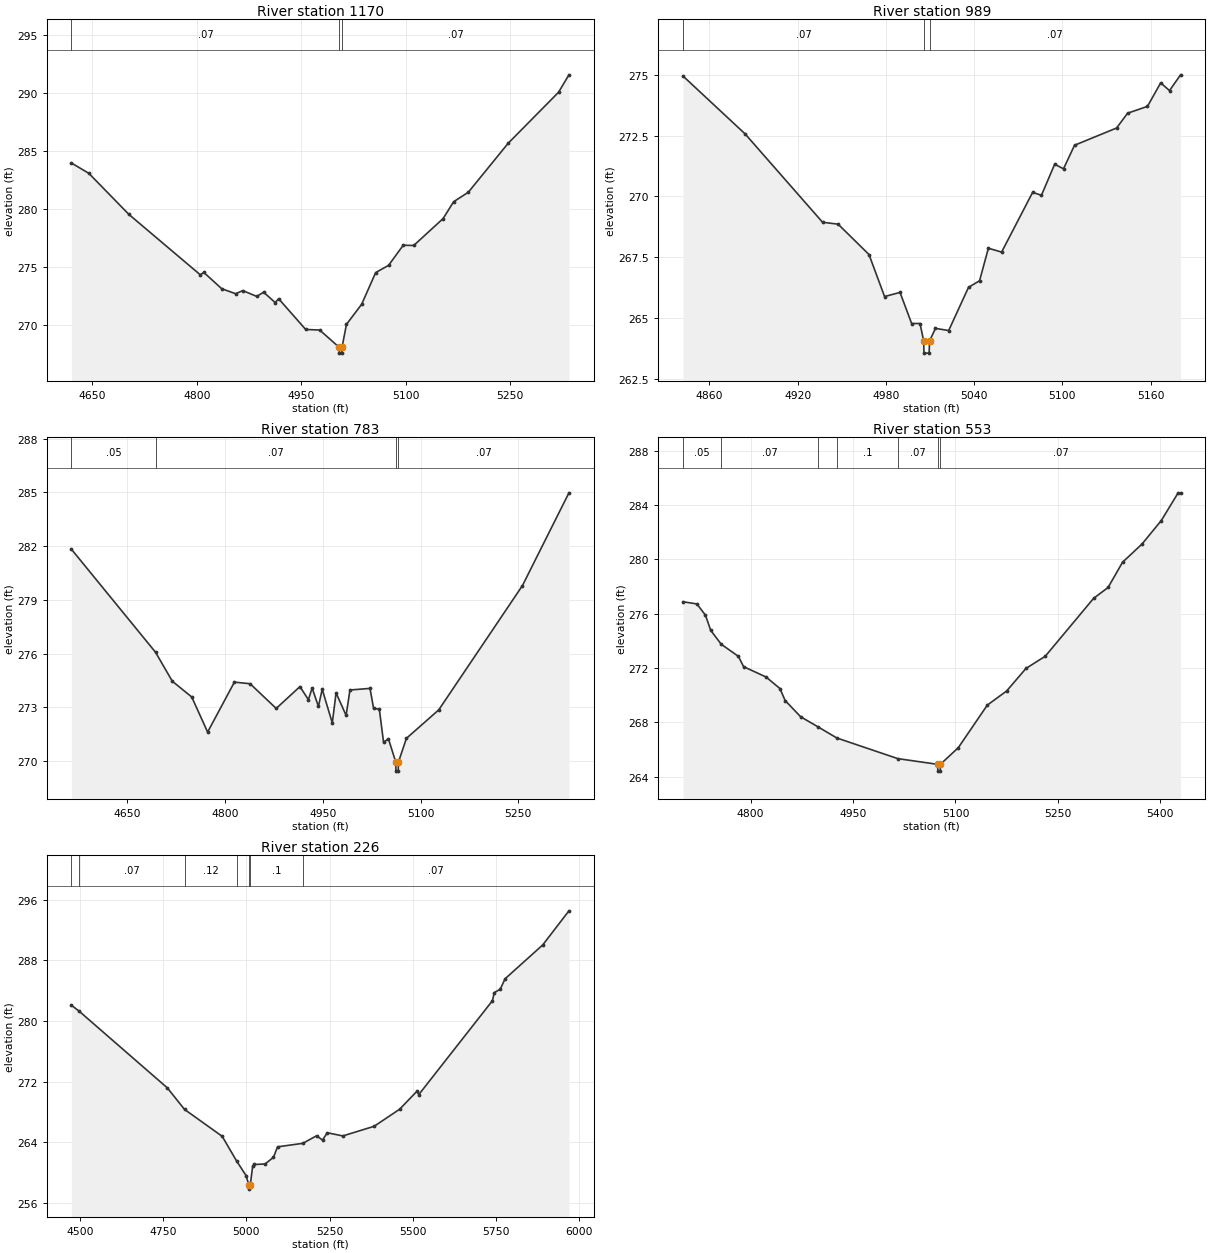
Type RM Length L Ch R = 1,1170,181,181,181
BEGIN DESCRIPTION:
E21135
END DESCRIPTION:
XS GIS Cut Line= 3
      2483788.16     13645579.86      2483745.14     13645132.87
      2483599.63     13644910.87
#Sta/Elev= 30
  4620.0  283.98  4645.0  283.09  4702.7  279.54  4805.1  274.34  4810.1  274.55
  4835.9  273.14  4855.9  272.71  4866.0  272.98  4886.1  272.48  4896.1  272.84
  4912.6  271.95  4917.6  272.28  4956.4  269.63  4976.5  269.58  5004.6  268.09
  5004.9  267.59  5008.4  267.59  5008.6  268.09  5015.0  270.07  5036.8  271.80
  5056.9  274.53  5075.5  275.16  5096.5  276.89  5111.6  276.87  5153.8  279.19
  5168.9  280.64  5190.0  281.46  5247.2  285.68  5319.6  290.08  5334.5  291.58
#Mann=3,-1,0
  4620.0    0.07       0  5004.6    0.05       0  5008.6    0.07       0
Bank Sta=5004.6,5008.6
Exp/Cntr=0.3,0.1

Type RM Length L Ch R = 1,989,206,206,206
BEGIN DESCRIPTION:
Stream0521 2.0
END DESCRIPTION:
XS GIS Cut Line= 3
      2483975.01     13645375.04      2483925.00     13645225.00
      2483825.02     13645075.03
#Sta/Elev= 30
  4842.0  274.96  4884.2  272.58  4936.9  268.94  4947.5  268.86  4968.5  267.61
  4979.1  265.88  4989.6  266.05  4997.5  264.77  5003.2  264.77  5005.7  264.05
  5005.9  263.55  5009.4  263.55  5009.7  264.05  5013.7  264.57  5022.7  264.48
  5036.2  266.26  5043.7  266.53  5049.7  267.87  5058.7  267.71  5079.8  270.17
  5085.8  270.05  5094.8  271.33  5100.8  271.14  5108.3  272.11  5136.9  272.82
  5144.4  273.43  5157.9  273.71  5166.9  274.68  5172.9  274.36  5180.4  275.01
#Mann=3,-1,0
  4842.0    0.07       0  5005.7    0.05       0  5009.7    0.07       0
Bank Sta=5005.7,5009.7
Exp/Cntr=0.3,0.1

Type RM Length L Ch R = 1,783,230,230,230
BEGIN DESCRIPTION:
E21134
END DESCRIPTION:
XS GIS Cut Line= 5
      2484012.61     13645492.00      2484104.27     13645258.19
      2484108.01     13645157.18      2484010.74     13645097.33
      2483779.43     13644910.43
#Sta/Elev= 30
  4564.0  281.83  4693.1  276.08  4718.9  274.46  4748.7  273.58  4773.1  271.62
  4814.2  274.41  4838.3  274.32  4878.4  272.94  4914.8  274.16  4927.8  273.43
  4933.6  274.08  4943.2  273.05  4949.0  274.01  4964.5  272.13  4970.3  273.81
  4985.7  272.55  4991.6  273.97  5022.4  274.06  5027.9  272.94  5036.7  272.90
  5043.2  271.05  5050.7  271.24  5062.0  269.94  5062.2  269.44  5065.7  269.44
  5066.0  269.94  5078.3  271.27  5127.9  272.86  5256.4  279.80  5327.8  284.98
#Mann=4,-1,0
  4564.0    0.05       0  4693.1    0.07       0  5062.0    0.05       0
  5066.0    0.07       0
Bank Sta=5062,5066
Exp/Cntr=0.3,0.1

Type RM Length L Ch R = 1,553,327,327,327
BEGIN DESCRIPTION:
Stream0521 1.0
END DESCRIPTION:
XS GIS Cut Line= 3
      2484175.00     13645374.98      2484225.00     13645075.00
      2483924.99     13644774.99
#Sta/Elev= 30
  4701.1  276.87  4721.4  276.71  4734.0  275.88  4741.6  274.77  4757.1  273.74
  4782.2  272.85  4789.8  272.09  4822.7  271.33  4843.0  270.48  4850.6  269.60
  4873.4  268.40  4898.1  267.68  4926.3  266.84  5015.6  265.32  5073.9  264.90
  5074.2  264.40  5077.7  264.40  5077.9  264.90  5104.2  266.13  5146.6  269.26
  5174.9  270.30  5203.2  271.96  5231.5  272.86  5302.2  277.12  5323.4  277.92
  5344.6  279.78  5372.9  281.11  5401.2  282.84  5426.0  284.89  5429.5  284.89
#Mann=7,-1,0
  4701.1    0.05       0  4757.1    0.07       0  4898.1    0.12       0
  4926.3     0.1       0  5015.6    0.07       0  5073.9    0.05       0
  5077.9    0.07       0
Bank Sta=5073.9,5077.9
Exp/Cntr=0.3,0.1

Type RM Length L Ch R = 1,226,0,0,0
BEGIN DESCRIPTION:
XS7020
END DESCRIPTION:
XS GIS Cut Line= 4
      2484411.05     13645634.96      2484544.62     13645082.84
      2484446.66     13644815.67      2483859.46     13644557.66
#Sta/Elev= 30
  4474.9  282.06  4497.8  281.29  4762.9  271.16  4814.5  268.32  4927.6  264.77
  4970.8  261.52  4999.6  259.57  5007.9  258.30  5008.1  257.80  5011.9  258.30
  5019.1  260.81  5024.3  261.05  5056.5  261.12  5081.7  262.00  5093.9  263.38
  5169.5  263.84  5211.1  264.84  5228.9  264.27  5243.0  265.24  5289.9  264.82
  5383.9  266.09  5460.4  268.34  5512.6  270.72  5518.1  270.28  5739.1  282.66
  5744.6  283.73  5762.5  284.17  5777.2  285.56  5890.2  290.02  5968.9  294.52
#Mann=7,-1,0
  4474.9    0.05       0  4497.8    0.07       0  4814.5    0.12       0
  4970.8     0.1       0  5007.9    0.05       0  5011.9     0.1       0
  5169.5    0.07       0
Bank Sta=5007.9,5011.9
Exp/Cntr=0.3,0.1

Chan Stop Cuts=-1