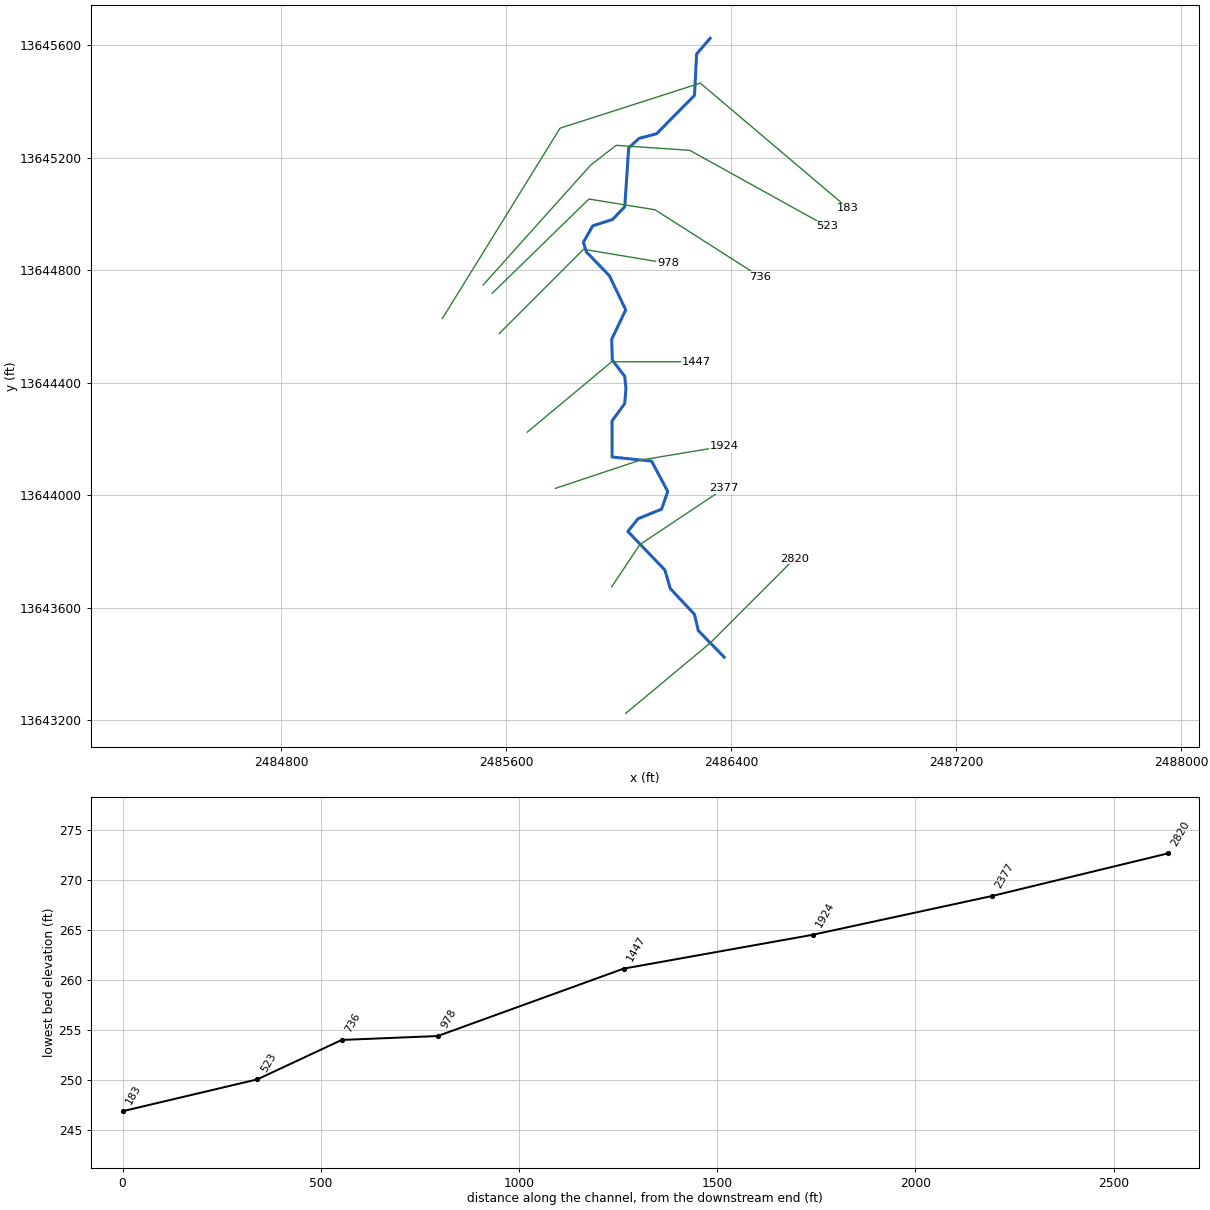
--- Stream0522.prj (project) ---

Proj Title=Stream0522 Base Level Engineering
Current Plan=p01
Default Exp/Contr=0.3,0.1
English Units
Geom File=g01
Flow File=f01
Plan File=p01
BEGIN DESCRIPTION:
Stream0522
END DESCRIPTION:

--- Stream0522.p01 (plan) ---

Plan Title=Multiple Run
Short Identifier=Multiple
Geom File=g01
Flow File=f01
Subcritical Flow
K Sum by GR= 0
Std Step Tol= 0.01
Critical Tol= 0.01
Num of Std Step Trials= 20
Max Error Tol= 0.3
Flow Tol Ratio= 0.001
Split Flow NTrial= 30
Split Flow Tol= 0.02
Split Flow Ratio= 0.02
Log Output Level= 0
Friction Slope Method= 1
Unsteady Friction Slope Method= 2
Unsteady Bridges Friction Slope Method= 1
Parabolic Critical Depth
Global Vel Dist=  1 , 1 , 1
Global Log Level= 0
CheckData=True
Encroach Param= -1, 0, 0, 0
BEGIN DESCRIPTION:
Multiple Run
END DESCRIPTION:

--- Stream0522.f01 (steady flow) ---

Flow Title=Multiple
Number of Profiles=7
Profile Names=10-year,25-year,50-year,1pct_min,100-year,1pct_plu,500-year
River Rch & RM= Stream0522,Reach-1,2820
     518     829    1110     722    1441    2875    2398
Boundary for River Rch & Prof#=Stream0522,Reach-1,1
Up Type=0
Dn Type=3
Dn Slope=0.005
Boundary for River Rch & Prof#=Stream0522,Reach-1,2
Up Type=0
Dn Type=3
Dn Slope=0.005
Boundary for River Rch & Prof#=Stream0522,Reach-1,3
Up Type=0
Dn Type=3
Dn Slope=0.005
Boundary for River Rch & Prof#=Stream0522,Reach-1,4
Up Type=0
Dn Type=3
Dn Slope=0.005
Boundary for River Rch & Prof#=Stream0522,Reach-1,5
Up Type=0
Dn Type=3
Dn Slope=0.005
Boundary for River Rch & Prof#=Stream0522,Reach-1,6
Up Type=0
Dn Type=3
Dn Slope=0.005
Boundary for River Rch & Prof#=Stream0522,Reach-1,7
Up Type=0
Dn Type=3
Dn Slope=0.005

--- Stream0522.g01 (geometry) ---

Geom Title=Existing Conditions

River Reach=Stream0522,Reach-1
Reach XY= 30
      2486375.00     13643425.00      2486283.11     13643518.93
      2486269.14     13643577.29      2486183.18     13643668.96
      2486164.22     13643734.68      2486032.51     13643871.85
      2486068.31     13643916.83      2486152.44     13643951.16
      2486174.33     13644014.27      2486116.71     13644121.92
      2485976.48     13644136.49      2485976.20     13644264.48
      2486021.29     13644326.60      2486025.81     13644380.03
      2486021.29     13644423.40      2485977.17     13644480.97
      2485974.92     13644554.91      2486024.92     13644659.61
      2485966.84     13644781.05      2485885.19     13644865.35
      2485874.38     13644900.09      2485907.79     13644958.50
      2485977.55     13644980.75      2486021.55     13645026.25
      2486035.34     13645235.12      2486072.42     13645269.26
      2486134.66     13645285.79      2486269.54     13645422.55
      2486276.91     13645569.21      2486325.00     13645625.00

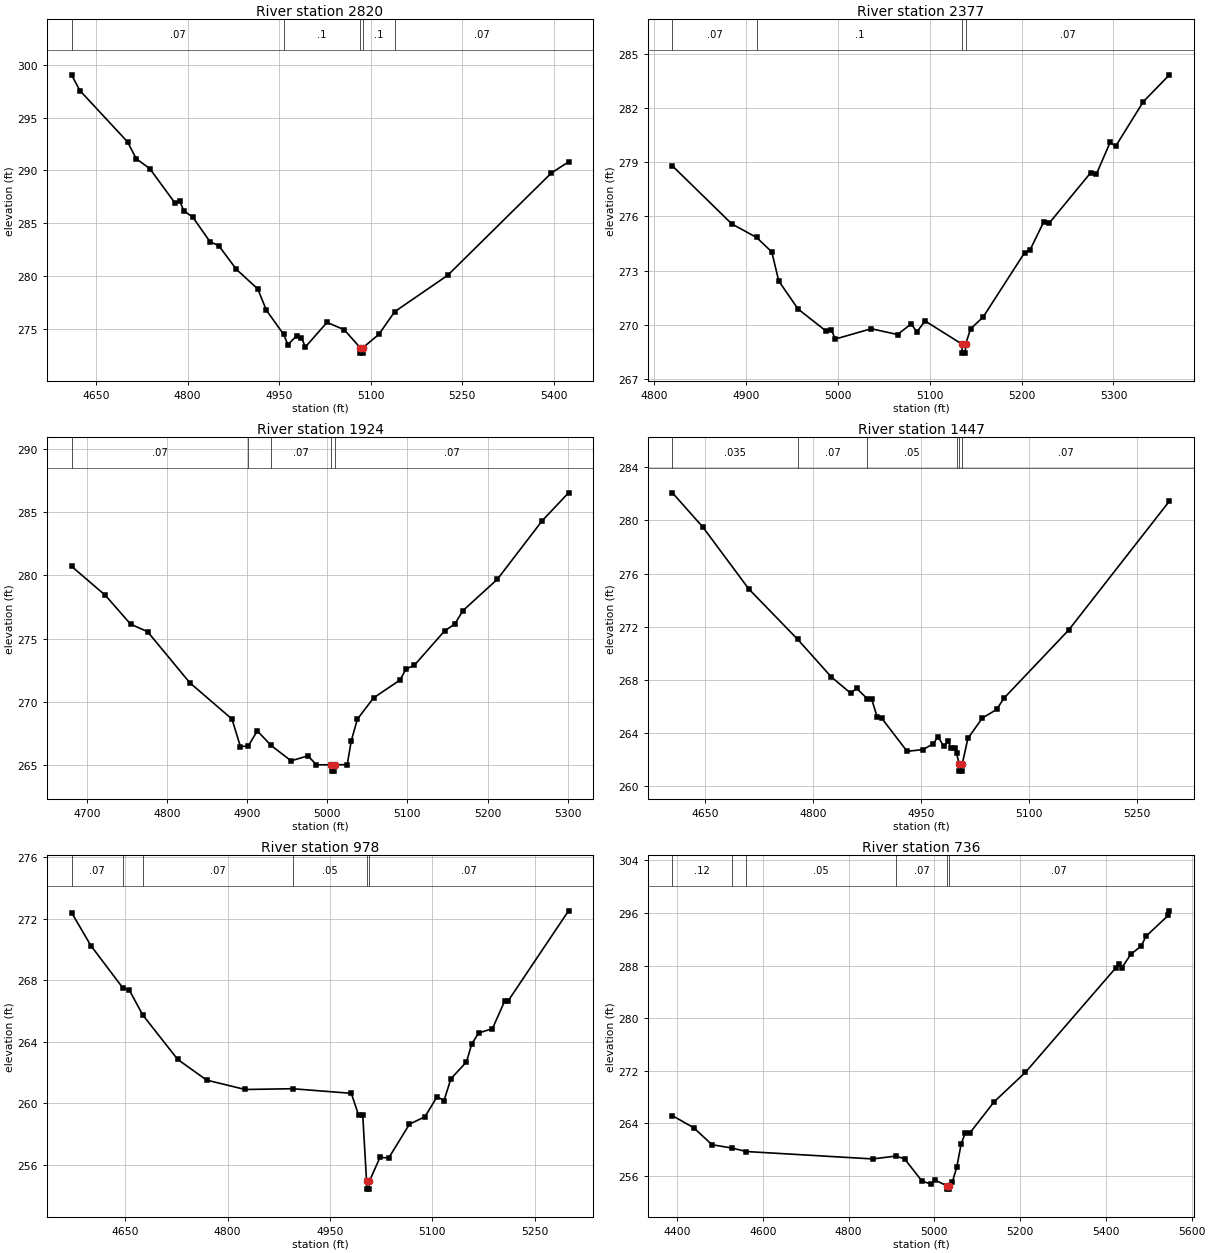
Type RM Length L Ch R = 1,2820,443,443,443
BEGIN DESCRIPTION:
Stream0522 5.0
END DESCRIPTION:
XS GIS Cut Line= 3
      2486025.00     13643225.00      2486325.00     13643475.00
      2486625.02     13643775.02
#Sta/Elev= 30
  4609.8  299.06  4623.5  297.57  4701.6  292.71  4715.9  291.11  4738.0  290.18
  4779.7  286.89  4787.5  287.07  4794.0  286.15  4808.3  285.60  4836.9  283.24
  4851.3  282.87  4879.9  280.64  4915.1  278.77  4929.4  276.74  4957.6  274.46
  4964.5  273.49  4978.8  274.33  4986.6  274.16  4993.2  273.27  5028.6  275.60
  5056.9  274.91  5083.2  273.19  5083.4  272.69  5086.9  272.69  5087.2  273.19
  5113.5  274.46  5139.7  276.62  5226.6  280.07  5396.3  289.75  5424.6  290.81
#Mann=5,-1,0
  4609.8    0.07       0  4957.6     0.1       0  5083.2    0.05       0
  5087.2     0.1       0  5139.7    0.07       0
Bank Sta=5083.2,5087.2
Exp/Cntr=0.3,0.1

Type RM Length L Ch R = 1,2377,453,453,453
BEGIN DESCRIPTION:
Stream0522 4.0
END DESCRIPTION:
XS GIS Cut Line= 3
      2485975.01     13643675.02      2486075.00     13643825.00
      2486374.99     13644024.99
#Sta/Elev= 30
  4820.1  278.79  4884.7  275.58  4911.7  274.83  4928.2  274.03  4935.8  272.42
  4956.8  270.87  4986.8  269.67  4992.8  269.73  4997.4  269.21  5036.4  269.78
  5065.0  269.46  5080.0  270.05  5086.0  269.60  5095.0  270.21  5135.1  268.93
  5135.3  268.43  5138.8  268.43  5139.1  268.93  5144.6  269.78  5158.1  270.42
  5203.2  273.98  5209.2  274.14  5224.2  275.70  5230.2  275.63  5275.3  278.42
  5281.3  278.32  5296.3  280.09  5302.3  279.87  5332.4  282.34  5360.9  283.83
#Mann=4,-1,0
  4820.1    0.07       0  4911.7     0.1       0  5135.1    0.05       0
  5139.1    0.07       0
Bank Sta=5135.1,5139.1
Exp/Cntr=0.3,0.1

Type RM Length L Ch R = 1,1924,477,477,477
BEGIN DESCRIPTION:
Stream0522 3.0
END DESCRIPTION:
XS GIS Cut Line= 3
      2485775.01     13644025.00      2486075.00     13644125.00
      2486375.05     13644175.01
#Sta/Elev= 30
  4680.7  280.71  4722.9  278.42  4754.5  276.14  4775.6  275.55  4828.3  271.52
  4881.0  268.65  4891.5  266.48  4901.3  266.52  4912.6  267.72  4929.8  266.57
  4954.8  265.35  4975.8  265.75  4986.4  265.04  5005.1  265.04  5005.3  264.54
  5008.8  264.54  5009.1  265.04  5024.8  265.05  5029.9  266.93  5037.5  268.64
  5057.7  270.32  5090.7  271.73  5098.3  272.61  5108.4  272.88  5146.4  275.61
  5159.1  276.15  5169.3  277.21  5212.3  279.69  5268.1  284.30  5301.1  286.51
#Mann=5,-1,0
  4680.7    0.07       0  4901.3     0.1       0  4929.8    0.07       0
  5005.1    0.05       0  5009.1    0.07       0
Bank Sta=5005.1,5009.1
Exp/Cntr=0.3,0.1

Type RM Length L Ch R = 1,1447,469,469,469
BEGIN DESCRIPTION:
Stream0522 2.0
END DESCRIPTION:
XS GIS Cut Line= 3
      2485675.02     13644225.02      2485975.00     13644475.00
      2486275.02     13644475.00
#Sta/Elev= 30
  4605.0  282.08  4647.3  279.50  4711.1  274.85  4779.0  271.06  4825.6  268.24
  4852.9  267.00  4860.8  267.38  4875.8  266.59  4881.6  266.60  4889.4  265.23
  4895.9  265.12  4931.0  262.64  4953.2  262.77  4967.5  263.21  4974.0  263.75
  4981.8  263.01  4988.3  263.38  4992.2  262.88  4998.0  262.88  4999.7  262.50
  5003.5  261.65  5003.7  261.15  5007.2  261.15  5007.5  261.65  5015.5  263.61
  5035.5  265.14  5055.5  265.79  5065.5  266.63  5155.5  271.76  5295.5  281.46
#Mann=6,-1,0
  4605.0   0.035       0  4779.0    0.07       0  4875.8    0.05       0
  4999.7    0.07       0  5003.5    0.05       0  5007.5    0.07       0
Bank Sta=5003.5,5007.5
Exp/Cntr=0.3,0.1

Type RM Length L Ch R = 1,978,242,242,242
BEGIN DESCRIPTION:
Stream0522 1.0
END DESCRIPTION:
XS GIS Cut Line= 3
      2485575.01     13644575.01      2485875.00     13644875.00
      2486175.02     13644825.00
#Sta/Elev= 30
  4571.4  272.39  4599.7  270.24  4646.7  267.48  4656.2  267.34  4675.6  265.74
  4726.9  262.84  4769.4  261.49  4825.9  260.88  4895.3  260.93  4981.5  260.63
  4992.1  259.21  4998.2  259.21  5003.8  254.90  5004.0  254.40  5007.5  254.40
  5007.8  254.90  5023.5  256.47  5036.2  256.42  5066.6  258.62  5089.4  259.11
  5107.2  260.41  5117.3  260.16  5127.4  261.58  5150.2  262.67  5157.9  263.84
  5168.0  264.55  5188.3  264.84  5206.0  266.61  5211.1  266.63  5299.8  272.50
#Mann=6,-1,0
  4571.4    0.07       0  4646.7    0.12       0  4675.6    0.07       0
  4895.3    0.05       0  5003.8    0.05       0  5007.8    0.07       0
Bank Sta=5003.8,5007.8
Exp/Cntr=0.3,0.1

Type RM Length L Ch R = 1,736,213,213,213
BEGIN DESCRIPTION:
E21139
END DESCRIPTION:
XS GIS Cut Line= 4
      2485550.49     13644718.80      2485894.14     13645053.64
      2486129.09     13645015.46      2486501.04     13644778.23
#Sta/Elev= 30
  4389.2  265.18  4439.1  263.33  4481.6  260.76  4527.2  260.27  4561.3  259.73
  4856.3  258.60  4910.5  259.04  4930.7  258.60  4971.2  255.23  4991.4  254.80
  5001.6  255.38  5030.0  254.51  5030.2  254.01  5033.7  254.01  5034.0  254.51
  5042.1  255.14  5052.2  257.32  5062.4  260.88  5072.5  262.62  5083.2  262.59
  5139.7  267.31  5212.5  271.78  5422.4  287.61  5430.8  288.17  5436.8  287.63
  5458.0  289.71  5481.7  290.95  5494.3  292.51  5545.9  295.67  5548.2  296.33
#Mann=6,-1,0
  4389.2    0.12       0  4527.2    0.07       0  4561.3    0.05       0
  4910.5    0.07       0  5030.0    0.05       0  5034.0    0.07       0
Bank Sta=5030,5034
Exp/Cntr=0.3,0.1

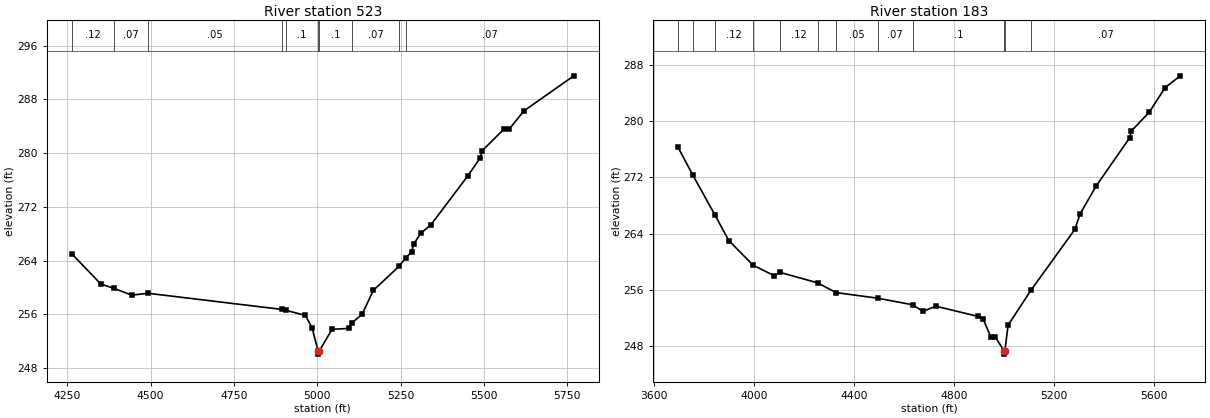
Type RM Length L Ch R = 1,523,340,340,340
BEGIN DESCRIPTION:
E21138
END DESCRIPTION:
XS GIS Cut Line= 5
      2485518.21     13644748.20      2485900.02     13645174.05
      2485991.06     13645244.54      2486252.44     13645226.92
      2486740.00     13644956.70
#Sta/Elev= 30
  4263.4  265.02  4351.2  260.49  4389.7  259.87  4443.1  258.85  4493.0  259.12
  4894.1  256.72  4905.5  256.59  4964.5  255.83  4984.5  254.01  5002.6  250.56
  5002.8  250.06  5006.6  250.56  5044.6  253.76  5094.8  253.88  5104.7  254.74
  5134.8  255.99  5168.3  259.55  5245.6  263.14  5265.1  264.40  5283.4  265.27
  5289.2  266.44  5310.9  268.06  5341.2  269.33  5451.7  276.60  5489.5  279.31
  5495.2  280.37  5560.5  283.58  5576.5  283.61  5620.0  286.28  5769.9  291.51
#Mann=10,-1,0
  4263.4    0.12       0  4389.7    0.07       0  4493.0    0.05       0
  4894.1    0.07       0  4905.5     0.1       0  5002.6    0.05       0
  5006.6     0.1       0  5104.7    0.07       0  5245.6     0.1       0
  5265.1    0.07       0
Bank Sta=5002.6,5006.6
Exp/Cntr=0.3,0.1

Type RM Length L Ch R = 1,183,0,0,0
BEGIN DESCRIPTION:
XS7019
END DESCRIPTION:
XS GIS Cut Line= 4
      2485372.85     13644628.68      2485791.39     13645305.47
      2486290.09     13645465.77      2486815.51     13645020.50
#Sta/Elev= 30
  3695.8  276.24  3754.3  272.32  3843.1  266.64  3898.4  263.01  3995.7  259.50
  4079.5  258.03  4103.5  258.48  4253.6  257.00  4327.6  255.61  4493.6  254.82
  4633.6  253.88  4674.5  252.95  4726.4  253.68  4893.9  252.24  4915.5  251.85
  4947.0  249.27  4963.3  249.35  4998.7  247.37  4998.9  246.87  5002.7  247.37
  5015.3  250.97  5107.4  255.98  5282.3  264.58  5303.2  266.77  5366.9  270.73
  5502.0  277.62  5508.6  278.58  5580.0  281.24  5643.7  284.75  5704.1  286.41
#Mann=12,-1,0
  3695.8   0.035       0  3754.3    0.07       0  3843.1    0.12       0
  3995.7    0.07       0  4103.5    0.12       0  4253.6    0.07       0
  4327.6    0.05       0  4493.6    0.07       0  4633.6     0.1       0
  4998.7    0.05       0  5002.7     0.1       0  5107.4    0.07       0
Bank Sta=4998.7,5002.7
Exp/Cntr=0.3,0.1

Chan Stop Cuts=-1