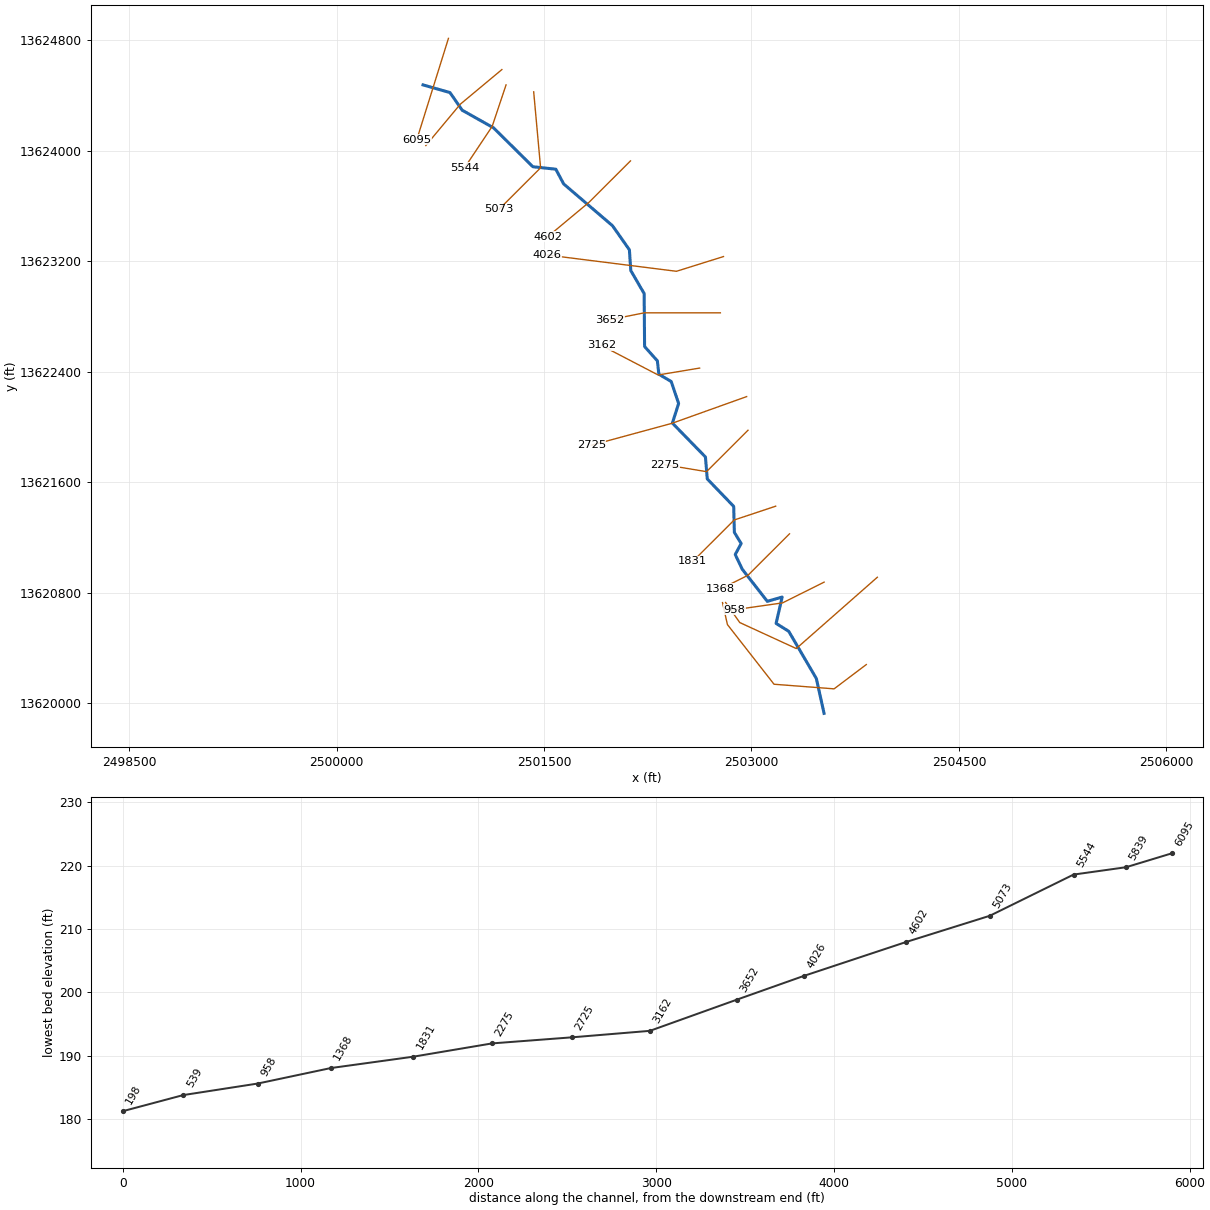
--- Stream0527.prj (project) ---

Proj Title=Stream0527 Base Level Engineering
Current Plan=p01
Default Exp/Contr=0.3,0.1
English Units
Geom File=g01
Flow File=f01
Plan File=p01
BEGIN DESCRIPTION:
Stream0527
END DESCRIPTION:

--- Stream0527.p01 (plan) ---

Plan Title=Multiple Run
Short Identifier=Multiple
Geom File=g01
Flow File=f01
Subcritical Flow
K Sum by GR= 0
Std Step Tol= 0.01
Critical Tol= 0.01
Num of Std Step Trials= 20
Max Error Tol= 0.3
Flow Tol Ratio= 0.001
Split Flow NTrial= 30
Split Flow Tol= 0.02
Split Flow Ratio= 0.02
Log Output Level= 0
Friction Slope Method= 1
Unsteady Friction Slope Method= 2
Unsteady Bridges Friction Slope Method= 1
Parabolic Critical Depth
Global Vel Dist=  1 , 1 , 1
Global Log Level= 0
CheckData=True
Encroach Param= -1, 0, 0, 0
BEGIN DESCRIPTION:
Multiple Run
END DESCRIPTION:

--- Stream0527.f01 (steady flow) ---

Flow Title=Multiple
Number of Profiles=7
Profile Names=10-year,25-year,50-year,1pct_min,100-year,1pct_plu,500-year
River Rch & RM= Stream0527,Reach-1,6095
     369     575     756     482     962    1920    1542
River Rch & RM= Stream0527,Reach-1,4026
     619     992    1327     860    1716    3425    2842
Boundary for River Rch & Prof#=Stream0527,Reach-1,1
Up Type=0
Dn Type=3
Dn Slope=0.005
Boundary for River Rch & Prof#=Stream0527,Reach-1,2
Up Type=0
Dn Type=3
Dn Slope=0.005
Boundary for River Rch & Prof#=Stream0527,Reach-1,3
Up Type=0
Dn Type=3
Dn Slope=0.005
Boundary for River Rch & Prof#=Stream0527,Reach-1,4
Up Type=0
Dn Type=3
Dn Slope=0.005
Boundary for River Rch & Prof#=Stream0527,Reach-1,5
Up Type=0
Dn Type=3
Dn Slope=0.005
Boundary for River Rch & Prof#=Stream0527,Reach-1,6
Up Type=0
Dn Type=3
Dn Slope=0.005
Boundary for River Rch & Prof#=Stream0527,Reach-1,7
Up Type=0
Dn Type=3
Dn Slope=0.005

--- Stream0527.g01 (geometry) ---

Geom Title=Existing Conditions

River Reach=Stream0527,Reach-1
Reach XY= 30
      2500625.00     13624475.00      2500819.53     13624419.75
      2500908.30     13624291.64      2501134.68     13624164.22
      2501418.81     13623882.82      2501585.12     13623864.65
      2501641.66     13623758.34      2501995.38     13623455.16
      2502117.17     13623281.18      2502127.25     13623130.93
      2502223.80     13622964.50      2502227.07     13622580.86
      2502319.44     13622477.36      2502330.29     13622380.49
      2502419.54     13622327.66      2502473.18     13622168.88
      2502428.13     13622026.63      2502667.18     13621781.19
      2502680.40     13621622.32      2502871.45     13621423.53
      2502876.24     13621235.50      2502925.21     13621154.79
      2502882.56     13621075.00      2502933.12     13620968.95
      2503114.64     13620735.99      2503222.02     13620767.40
      2503178.07     13620576.43      2503269.37     13620519.38
      2503469.16     13620177.29      2503525.00     13619925.00

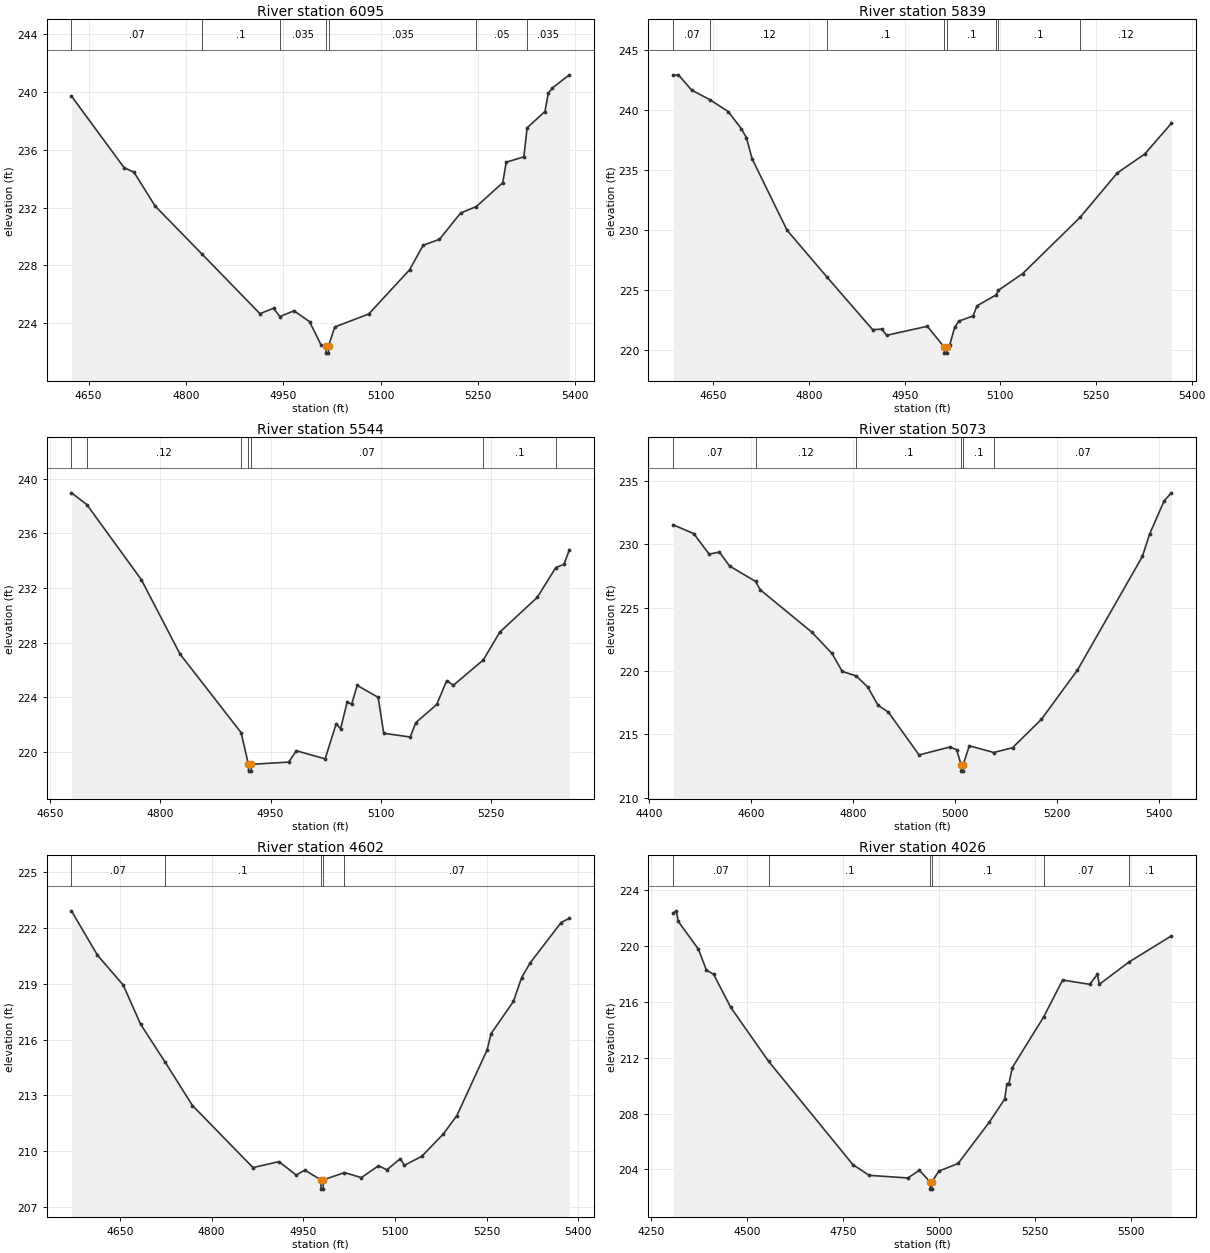
Type RM Length L Ch R = 1,6095,256,256,256
BEGIN DESCRIPTION:
XS7042
END DESCRIPTION:
XS GIS Cut Line= 2
      2500808.69     13624812.30      2500580.07     13624079.85
#Sta/Elev= 30
  4623.5  239.73  4704.5  234.78  4720.0  234.45  4752.5  232.11  4825.3  228.76
  4914.0  224.66  4934.9  225.04  4944.6  224.46  4966.4  224.86  4990.4  224.11
  5008.3  222.48  5015.7  222.43  5015.9  221.93  5019.4  221.93  5019.7  222.43
  5029.2  223.74  5081.6  224.64  5144.5  227.70  5165.4  229.40  5190.6  229.81
  5223.1  231.63  5247.4  232.08  5288.1  233.73  5293.4  235.15  5320.6  235.52
  5325.6  237.53  5353.1  238.66  5358.3  239.93  5364.5  240.29  5390.8  241.20
#Mann=7,-1,0
  4623.5    0.07       0  4825.3     0.1       0  4944.6   0.035       0
  5015.7   0.035       0  5019.7   0.035       0  5247.4    0.05       0
  5325.6   0.035       0
Bank Sta=5015.7,5019.7
Exp/Cntr=0.3,0.1

Type RM Length L Ch R = 1,5839,295,295,295
BEGIN DESCRIPTION:
Stream0527 12.0
END DESCRIPTION:
XS GIS Cut Line= 3
      2501194.98     13624586.10      2500895.00     13624336.11
      2500645.00     13624036.11
#Sta/Elev= 30
  4587.0  242.94  4595.0  242.97  4615.8  241.70  4644.2  240.90  4673.1  239.91
  4693.9  238.46  4701.7  237.73  4710.6  235.97  4765.5  230.00  4827.4  226.14
  4899.6  221.71  4913.9  221.75  4921.7  221.24  4985.4  221.99  5012.0  220.25
  5012.3  219.75  5015.8  219.75  5016.0  220.25  5020.5  220.41  5028.3  221.90
  5034.8  222.42  5057.0  222.84  5063.5  223.70  5093.6  224.62  5096.5  224.98
  5135.1  226.39  5224.9  231.07  5283.5  234.79  5326.4  236.36  5368.0  238.91
#Mann=8,-1,0
  4587.0    0.07       0  4644.2    0.12       0  4827.4     0.1       0
  5012.0    0.05       0  5016.0     0.1       0  5093.6    0.07       0
  5096.5     0.1       0  5224.9    0.12       0
Bank Sta=5012,5016
Exp/Cntr=0.3,0.1

Type RM Length L Ch R = 1,5544,471,471,471
BEGIN DESCRIPTION:
Stream0527 11.0
END DESCRIPTION:
XS GIS Cut Line= 3
      2501225.01     13624475.02      2501125.00     13624175.00
      2500925.00     13623875.00
#Sta/Elev= 30
  4679.3  238.97  4700.2  238.11  4774.2  232.62  4826.9  227.16  4909.9  221.41
  4919.8  219.09  4920.0  218.59  4923.5  218.59  4923.8  219.09  4974.5  219.25
  4985.0  220.08  5024.1  219.49  5039.1  222.06  5045.1  221.69  5054.1  223.66
  5060.1  223.49  5067.7  224.87  5096.2  223.99  5103.7  221.36  5139.8  221.09
  5147.3  222.14  5175.8  223.47  5189.3  225.22  5198.4  224.88  5239.0  226.73
  5261.5  228.77  5312.5  231.32  5337.6  233.50  5348.6  233.73  5356.1  234.80
#Mann=7,-1,0
  4679.3    0.07       0  4700.2    0.12       0  4909.9    0.07       0
  4919.8    0.05       0  4923.8    0.07       0  5239.0     0.1       0
  5337.6    0.07       0
Bank Sta=4919.8,4923.8
Exp/Cntr=0.3,0.1

Type RM Length L Ch R = 1,5073,471,471,471
BEGIN DESCRIPTION:
Stream0527 10.0
END DESCRIPTION:
XS GIS Cut Line= 3
      2501425.00     13624425.04      2501475.00     13623875.00
      2501174.98     13623574.98
#Sta/Elev= 30
  4447.2  231.53  4487.4  230.84  4517.5  229.22  4537.6  229.38  4557.7  228.28
  4608.5  227.07  4617.9  226.40  4718.4  223.08  4758.5  221.38  4778.6  219.96
  4805.8  219.61  4828.8  218.72  4848.9  217.28  4869.0  216.75  4929.2  213.37
  4989.5  213.99  5003.0  213.78  5011.7  212.59  5011.9  212.09  5015.4  212.09
  5015.7  212.59  5027.8  214.09  5075.8  213.56  5112.6  213.94  5169.2  216.18
  5239.9  220.07  5367.2  229.04  5381.3  230.80  5409.6  233.40  5423.8  234.06
#Mann=6,-1,0
  4447.2    0.07       0  4608.5    0.12       0  4805.8     0.1       0
  5011.7    0.05       0  5015.7     0.1       0  5075.8    0.07       0
Bank Sta=5011.7,5015.7
Exp/Cntr=0.3,0.1

Type RM Length L Ch R = 1,4602,576,576,576
BEGIN DESCRIPTION:
Stream0527 9.0
END DESCRIPTION:
XS GIS Cut Line= 3
      2502124.98     13623924.98      2501825.00     13623625.00
      2501525.04     13623375.03
#Sta/Elev= 30
  4570.7  222.93  4613.1  220.55  4655.5  218.93  4683.8  216.83  4723.7  214.80
  4768.7  212.45  4867.7  209.11  4910.1  209.43  4938.4  208.71  4952.5  208.97
  4978.8  208.45  4979.0  207.95  4982.5  207.95  4982.8  208.45  5017.4  208.84
  5045.1  208.57  5073.0  209.21  5086.7  208.99  5108.8  209.59  5115.3  209.23
  5144.0  209.72  5179.1  210.92  5201.3  211.91  5250.7  215.44  5257.2  216.32
  5293.7  218.05  5307.3  219.34  5321.0  220.12  5371.8  222.30  5385.4  222.53
#Mann=5,-1,0
  4570.7    0.07       0  4723.7     0.1       0  4978.8    0.05       0
  4982.8     0.1       0  5017.4    0.07       0
Bank Sta=4978.8,4982.8
Exp/Cntr=0.3,0.1

Type RM Length L Ch R = 1,4026,374,374,374
BEGIN DESCRIPTION:
Stream0527 8.0
END DESCRIPTION:
XS GIS Cut Line= 3
      2502797.54     13623232.34      2502457.57     13623125.68
      2501524.28     13623243.45
#Sta/Elev= 30
  4308.1  222.38  4316.0  222.54  4321.2  221.78  4373.6  219.79  4394.6  218.28
  4413.2  217.99  4457.5  215.63  4556.4  211.75  4775.8  204.35  4818.2  203.58
  4919.0  203.39  4949.2  203.94  4977.5  203.09  4977.7  202.59  4981.2  202.59
  4981.5  203.09  4999.6  203.88  5050.0  204.43  5130.6  207.37  5171.0  209.03
  5177.1  210.13  5182.1  210.13  5191.1  211.30  5272.9  214.94  5322.2  217.58
  5392.7  217.27  5412.8  217.99  5417.8  217.27  5493.9  218.85  5605.1  220.74
#Mann=6,-1,0
  4308.1    0.07       0  4556.4     0.1       0  4977.5    0.05       0
  4981.5     0.1       0  5272.9    0.07       0  5493.9     0.1       0
Bank Sta=4977.5,4981.5
Exp/Cntr=0.3,0.1

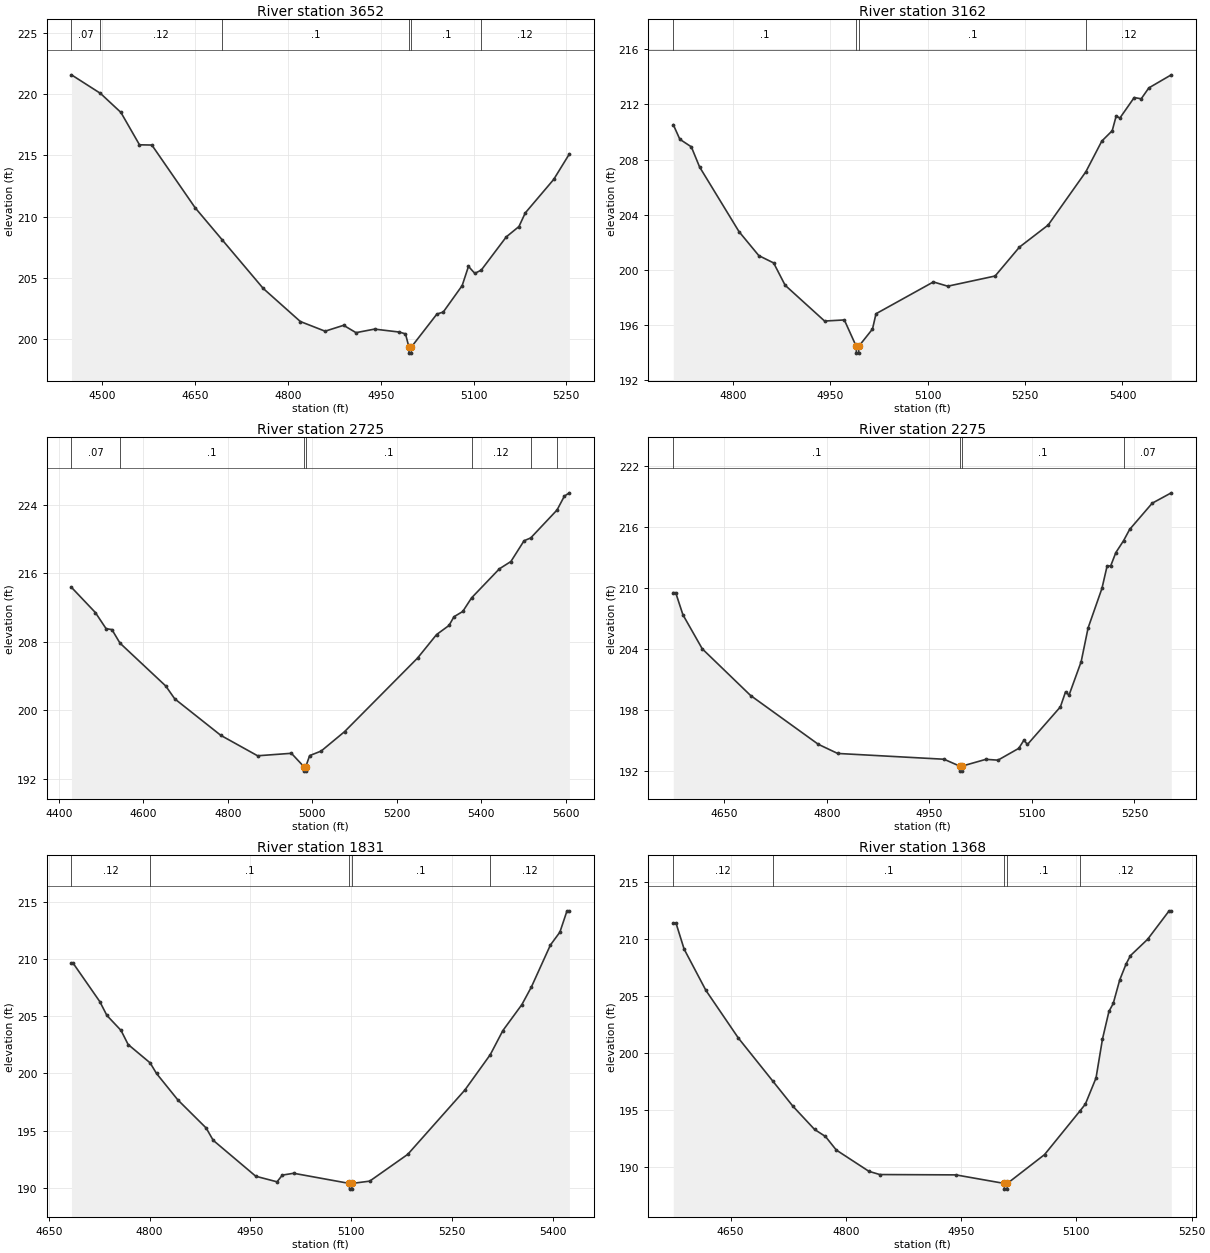
Type RM Length L Ch R = 1,3652,490,490,490
BEGIN DESCRIPTION:
Stream0527 7.0
END DESCRIPTION:
XS GIS Cut Line= 3
      2502775.03     13622825.00      2502225.00     13622825.00
      2501974.98     13622775.00
#Sta/Elev= 30
  4450.0  221.58  4496.8  220.07  4530.0  218.51  4560.0  215.87  4580.0  215.85
  4650.0  210.73  4693.6  208.12  4760.0  204.15  4820.0  201.45  4860.0  200.66
  4890.0  201.14  4910.0  200.54  4940.0  200.83  4980.0  200.59  4990.0  200.44
  4995.5  199.37  4995.8  198.87  4999.3  198.87  4999.5  199.37  5040.8  202.06
  5051.0  202.22  5081.6  204.38  5091.8  205.95  5102.0  205.38  5112.4  205.64
  5153.0  208.36  5173.4  209.20  5183.6  210.31  5229.5  213.04  5255.0  215.13
#Mann=6,-1,0
  4450.0    0.07       0  4496.8    0.12       0  4693.6     0.1       0
  4995.5    0.05       0  4999.5     0.1       0  5112.4    0.12       0
Bank Sta=4995.5,4999.5
Exp/Cntr=0.3,0.1

Type RM Length L Ch R = 1,3162,437,437,437
BEGIN DESCRIPTION:
Stream0527 6.0
END DESCRIPTION:
XS GIS Cut Line= 3
      2502624.96     13622424.99      2502325.00     13622375.00
      2501914.30     13622588.97
#Sta/Elev= 30
  4708.0  210.53  4718.1  209.47  4735.8  208.92  4748.5  207.46  4809.3  202.76
  4839.8  201.02  4862.6  200.49  4880.3  198.87  4941.1  196.27  4971.5  196.35
  4989.8  194.44  4990.1  193.94  4993.6  193.94  4993.8  194.44  5014.9  195.69
  5020.3  196.80  5108.7  199.11  5130.8  198.80  5203.8  199.54  5241.3  201.64
  5285.5  203.24  5343.6  207.11  5368.2  209.34  5384.2  210.09  5390.3  211.16
  5396.0  211.01  5418.1  212.50  5428.9  212.41  5440.6  213.20  5475.2  214.15
#Mann=4,-1,0
  4708.0     0.1       0  4989.8    0.05       0  4993.8     0.1       0
  5343.6    0.12       0
Bank Sta=4989.8,4993.8
Exp/Cntr=0.3,0.1

Type RM Length L Ch R = 1,2725,450,450,450
BEGIN DESCRIPTION:
Stream0527 5.0
END DESCRIPTION:
XS GIS Cut Line= 3
      2502965.17     13622218.42      2502425.00     13622025.00
      2501841.40     13621866.11
#Sta/Elev= 30
  4429.8  214.36  4486.4  211.42  4511.9  209.53  4525.6  209.43  4544.7  207.85
  4653.0  202.85  4674.3  201.35  4783.4  197.09  4870.4  194.71  4950.4  195.00
  4980.3  193.42  4980.6  192.92  4984.1  192.92  4984.3  193.42  4993.5  194.73
  5020.8  195.26  5076.1  197.52  5249.0  206.11  5294.0  208.85  5323.4  209.91
  5335.2  210.93  5355.9  211.54  5376.8  213.13  5442.7  216.52  5469.9  217.37
  5501.0  219.79  5516.8  220.12  5579.1  223.38  5596.5  225.00  5608.4  225.38
#Mann=7,-1,0
  4429.8    0.07       0  4544.7     0.1       0  4980.3    0.05       0
  4984.3     0.1       0  5376.8    0.12       0  5516.8    0.07       0
  5579.1    0.12       0
Bank Sta=4980.3,4984.3
Exp/Cntr=0.3,0.1

Type RM Length L Ch R = 1,2275,444,444,444
BEGIN DESCRIPTION:
Stream0527 4.0
END DESCRIPTION:
XS GIS Cut Line= 3
      2502974.98     13621974.98      2502675.00     13621675.00
      2502374.98     13621725.00
#Sta/Elev= 30
  4575.4  209.52  4578.9  209.52  4589.5  207.34  4617.8  203.99  4688.5  199.40
  4787.5  194.60  4815.8  193.70  4971.4  193.13  4994.1  192.46  4994.4  191.96
  4997.9  191.96  4998.1  192.46  5032.6  193.12  5050.3  193.04  5080.7  194.20
  5088.3  195.01  5093.4  194.58  5141.6  198.28  5149.2  199.77  5154.2  199.43
  5172.0  202.73  5182.1  206.04  5202.4  209.94  5210.0  212.16  5215.1  212.14
  5222.7  213.46  5234.0  214.63  5242.9  215.74  5275.9  218.32  5303.8  219.34
#Mann=4,-1,0
  4575.4     0.1       0  4994.1    0.05       0  4998.1     0.1       0
  5234.0    0.07       0
Bank Sta=4994.1,4998.1
Exp/Cntr=0.3,0.1

Type RM Length L Ch R = 1,1831,463,463,463
BEGIN DESCRIPTION:
Stream0527 3.0
END DESCRIPTION:
XS GIS Cut Line= 3
      2503174.99     13621425.00      2502875.00     13621325.00
      2502574.99     13621024.99
#Sta/Elev= 30
  4683.8  209.66  4686.4  209.66  4726.0  206.30  4736.5  205.09  4757.6  203.77
  4768.1  202.54  4800.8  200.93  4810.3  200.00  4841.9  197.69  4884.1  195.22
  4894.6  194.14  4957.9  190.99  4989.5  190.50  4997.4  191.09  5014.2  191.25
  5097.0  190.36  5097.3  189.86  5100.8  189.86  5101.0  190.36  5127.3  190.56
  5183.9  192.91  5268.7  198.54  5306.6  201.65  5325.3  203.76  5353.6  206.04
  5367.7  207.58  5396.0  211.26  5410.1  212.39  5420.7  214.26  5424.3  214.26
#Mann=5,-1,0
  4683.8    0.12       0  4800.8     0.1       0  5097.0    0.05       0
  5101.0     0.1       0  5306.6    0.12       0
Bank Sta=5097,5101
Exp/Cntr=0.3,0.1

Type RM Length L Ch R = 1,1368,410,410,410
BEGIN DESCRIPTION:
Stream0527 2.0
END DESCRIPTION:
XS GIS Cut Line= 3
      2503274.99     13621224.99      2502975.00     13620925.00
      2502774.97     13620824.98
#Sta/Elev= 30
  4575.5  211.43  4579.0  211.43  4589.6  209.14  4617.9  205.52  4660.3  201.32
  4704.9  197.56  4731.1  195.35  4759.3  193.31  4773.5  192.69  4787.6  191.50
  4830.1  189.63  4844.2  189.35  4943.2  189.32  5006.1  188.57  5006.4  188.07
  5009.9  188.07  5010.1  188.57  5058.5  191.10  5104.2  194.90  5111.6  195.53
  5125.5  197.83  5133.9  201.25  5142.3  203.67  5147.9  204.37  5156.3  206.43
  5164.7  207.85  5170.3  208.57  5192.6  210.00  5220.6  212.50  5223.4  212.50
#Mann=5,-1,0
  4575.5    0.12       0  4704.9     0.1       0  5006.1    0.05       0
  5010.1     0.1       0  5104.2    0.12       0
Bank Sta=5006.1,5010.1
Exp/Cntr=0.3,0.1

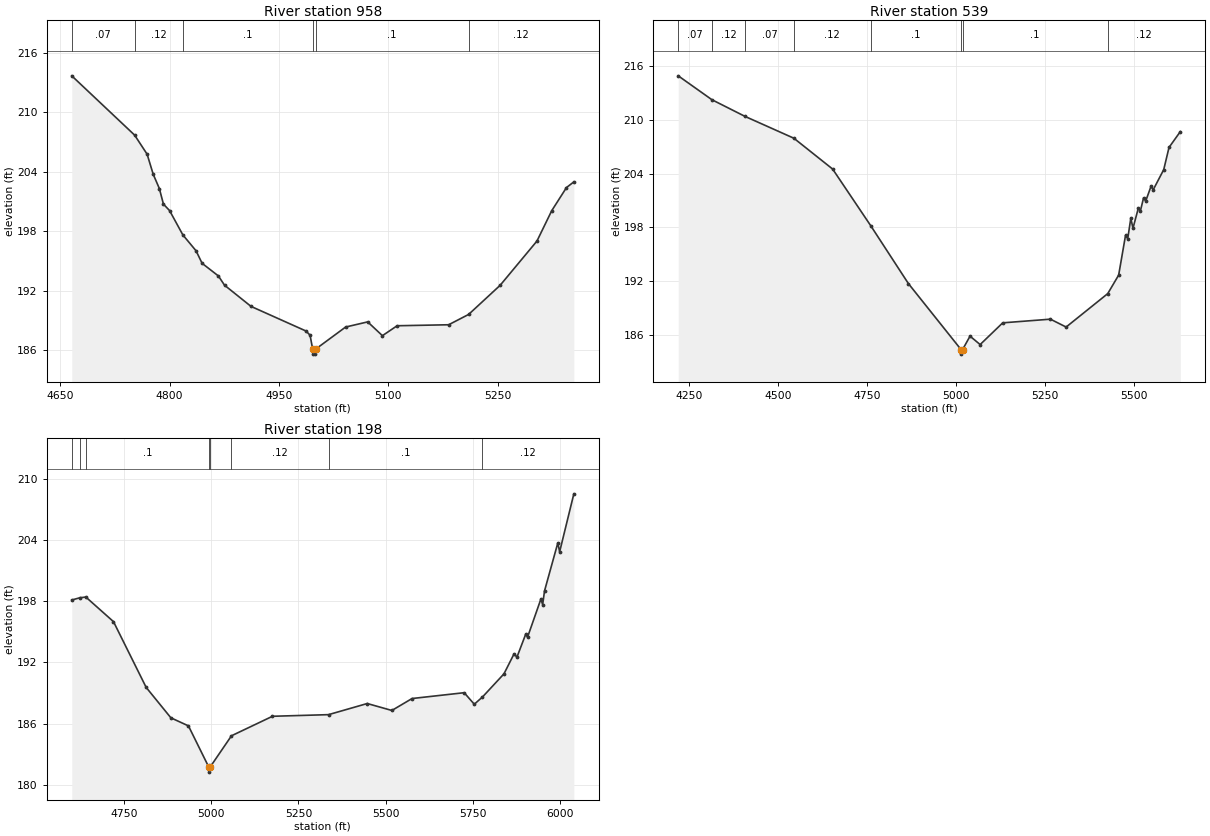
Type RM Length L Ch R = 1,958,419,419,419
BEGIN DESCRIPTION:
Stream0527 1.0
END DESCRIPTION:
XS GIS Cut Line= 3
      2503524.99     13620875.00      2503225.00     13620725.00
      2502874.95     13620674.99
#Sta/Elev= 30
  4665.7  213.68  4752.0  207.70  4769.1  205.78  4777.5  203.75  4785.9  202.32
  4791.5  200.75  4799.9  200.10  4818.2  197.64  4836.2  196.05  4844.6  194.78
  4866.9  193.51  4875.3  192.58  4911.7  190.44  4987.1  187.96  4992.7  187.54
  4996.3  186.13  4996.6  185.63  5000.1  185.63  5000.3  186.13  5041.5  188.36
  5071.8  188.88  5092.0  187.49  5112.2  188.49  5182.9  188.59  5210.3  189.63
  5253.6  192.57  5304.1  197.03  5324.3  200.08  5344.6  202.42  5354.7  202.99
#Mann=6,-1,0
  4665.7    0.07       0  4752.0    0.12       0  4818.2     0.1       0
  4996.3    0.05       0  5000.3     0.1       0  5210.3    0.12       0
Bank Sta=4996.3,5000.3
Exp/Cntr=0.3,0.1

Type RM Length L Ch R = 1,539,341,341,341
BEGIN DESCRIPTION:
XS7041
END DESCRIPTION:
XS GIS Cut Line= 4
      2503910.33     13620910.70      2503324.02     13620394.32
      2502915.22     13620582.58      2502813.05     13620727.77
#Sta/Elev= 30
  4220.6  214.94  4315.0  212.27  4408.1  210.40  4545.1  207.96  4653.9  204.51
  4761.0  198.16  4866.5  191.70  5014.4  184.31  5014.7  183.81  5018.4  184.31
  5039.4  185.82  5067.8  184.88  5131.2  187.31  5265.0  187.72  5309.1  186.84
  5425.9  190.58  5456.5  192.65  5475.8  197.10  5481.9  196.71  5490.6  199.01
  5496.7  197.89  5511.5  200.11  5517.7  199.86  5526.4  201.29  5532.5  200.94
  5547.3  202.58  5553.4  202.19  5583.0  204.45  5597.8  206.93  5629.5  208.70
#Mann=8,-1,0
  4220.6    0.07       0  4315.0    0.12       0  4408.1    0.07       0
  4545.1    0.12       0  4761.0     0.1       0  5014.4    0.05       0
  5018.4     0.1       0  5425.9    0.12       0
Bank Sta=5014.4,5018.4
Exp/Cntr=0.3,0.1

Type RM Length L Ch R = 1,198,0,0,0
BEGIN DESCRIPTION:
E21152
END DESCRIPTION:
XS GIS Cut Line= 5
      2503830.23     13620278.32      2503597.57     13620102.63
      2503163.16     13620135.87      2502826.08     13620567.90
      2502790.47     13620726.97
#Sta/Elev= 30
  4600.6  198.12  4623.9  198.34  4640.9  198.41  4720.1  196.00  4813.7  189.56
  4884.5  186.58  4934.8  185.79  4993.0  181.76  4993.3  181.26  4997.0  181.76
  5058.1  184.82  5175.5  186.73  5336.1  186.89  5447.0  187.98  5517.5  187.30
  5575.4  188.47  5724.7  189.04  5753.6  187.91  5777.1  188.62  5838.7  190.89
  5867.6  192.85  5875.8  192.52  5901.0  194.78  5906.2  194.48  5944.4  198.21
  5949.5  197.67  5954.8  199.01  5992.9  203.71  5998.1  202.84  6038.8  208.52
#Mann=8,-1,0
  4600.6     0.1       0  4623.9    0.12       0  4640.9     0.1       0
  4993.0    0.05       0  4997.0     0.1       0  5058.1    0.12       0
  5336.1     0.1       0  5777.1    0.12       0
Bank Sta=4993,4997
Exp/Cntr=0.3,0.1

Chan Stop Cuts=-1