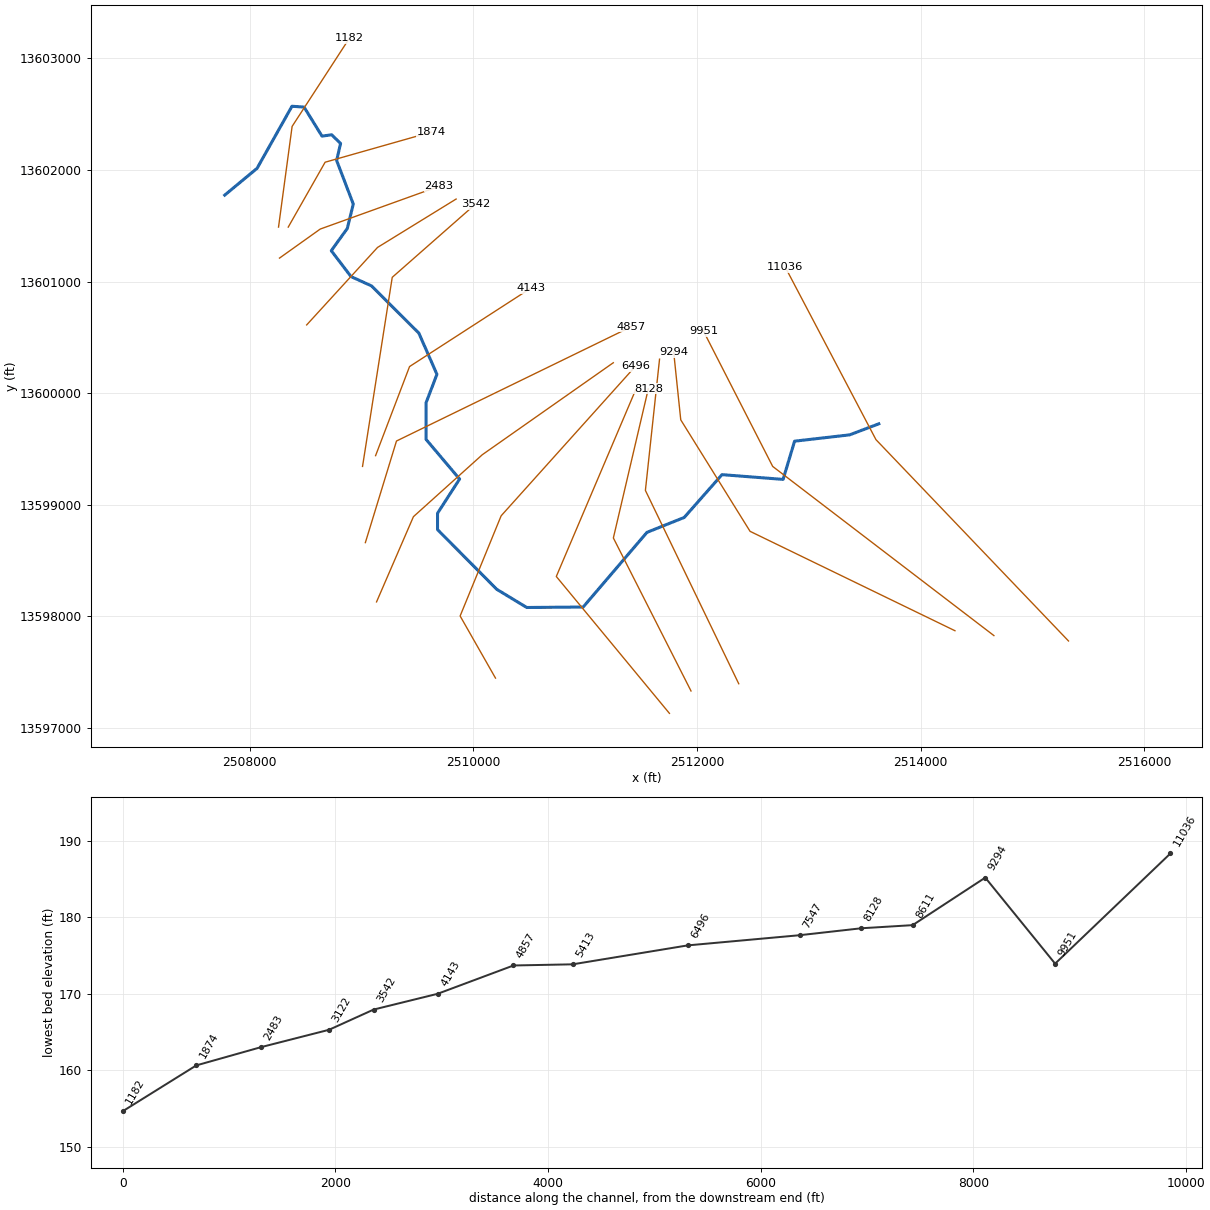
--- Stream0529.prj (project) ---

Proj Title=Stream0529 Base Level Engineering
Current Plan=p01
Default Exp/Contr=0.3,0.1
English Units
Geom File=g01
Flow File=f01
Plan File=p01
BEGIN DESCRIPTION:
Stream0529
END DESCRIPTION:

--- Stream0529.p01 (plan) ---

Plan Title=Multiple Run
Short Identifier=Multiple
Geom File=g01
Flow File=f01
Subcritical Flow
K Sum by GR= 0
Std Step Tol= 0.01
Critical Tol= 0.01
Num of Std Step Trials= 20
Max Error Tol= 0.3
Flow Tol Ratio= 0.001
Split Flow NTrial= 30
Split Flow Tol= 0.02
Split Flow Ratio= 0.02
Log Output Level= 0
Friction Slope Method= 1
Unsteady Friction Slope Method= 2
Unsteady Bridges Friction Slope Method= 1
Parabolic Critical Depth
Global Vel Dist=  1 , 1 , 1
Global Log Level= 0
CheckData=True
Encroach Param= -1, 0, 0, 0
BEGIN DESCRIPTION:
Multiple Run
END DESCRIPTION:

--- Stream0529.f01 (steady flow) ---

Flow Title=Multiple
Number of Profiles=7
Profile Names=10-year,25-year,50-year,1pct_min,100-year,1pct_plu,500-year
River Rch & RM= Stream0529,Reach-1,11036
     453     709     933     595    1186    2367    1899
River Rch & RM= Stream0529,Reach-1,9951
     737    1185    1586    1027    2049    4088    3387
River Rch & RM= Stream0529,Reach-1,8611
     904    1457    1952    1263    2521    5029    4165
Boundary for River Rch & Prof#=Stream0529,Reach-1,1
Up Type=0
Dn Type=3
Dn Slope=0.005
Boundary for River Rch & Prof#=Stream0529,Reach-1,2
Up Type=0
Dn Type=3
Dn Slope=0.005
Boundary for River Rch & Prof#=Stream0529,Reach-1,3
Up Type=0
Dn Type=3
Dn Slope=0.005
Boundary for River Rch & Prof#=Stream0529,Reach-1,4
Up Type=0
Dn Type=3
Dn Slope=0.005
Boundary for River Rch & Prof#=Stream0529,Reach-1,5
Up Type=0
Dn Type=3
Dn Slope=0.005
Boundary for River Rch & Prof#=Stream0529,Reach-1,6
Up Type=0
Dn Type=3
Dn Slope=0.005
Boundary for River Rch & Prof#=Stream0529,Reach-1,7
Up Type=0
Dn Type=3
Dn Slope=0.005

--- Stream0529.g01 (geometry) ---

Geom Title=Existing Conditions

River Reach=Stream0529,Reach-1
Reach XY= 30
      2513625.00     13599725.00      2513364.49     13599626.22
      2512872.00     13599569.54      2512769.35     13599226.97
      2512222.55     13599269.55      2511884.79     13598885.52
      2511551.53     13598751.99      2510981.19     13598082.81
      2510476.55     13598078.75      2510208.33     13598241.65
      2509678.53     13598776.47      2509678.53     13598923.53
      2509875.85     13599230.05      2509576.05     13599585.43
      2509576.22     13599914.50      2509673.18     13600168.88
      2509511.37     13600538.21      2509088.21     13600961.38
      2508904.91     13601044.78      2508728.31     13601276.74
      2508871.46     13601476.47      2508925.10     13601695.10
      2508776.11     13602085.55      2508811.47     13602238.44
      2508731.70     13602315.70      2508644.92     13602304.07
      2508484.81     13602564.58      2508376.49     13602571.55
      2508064.48     13602015.21      2507775.00     13601775.00

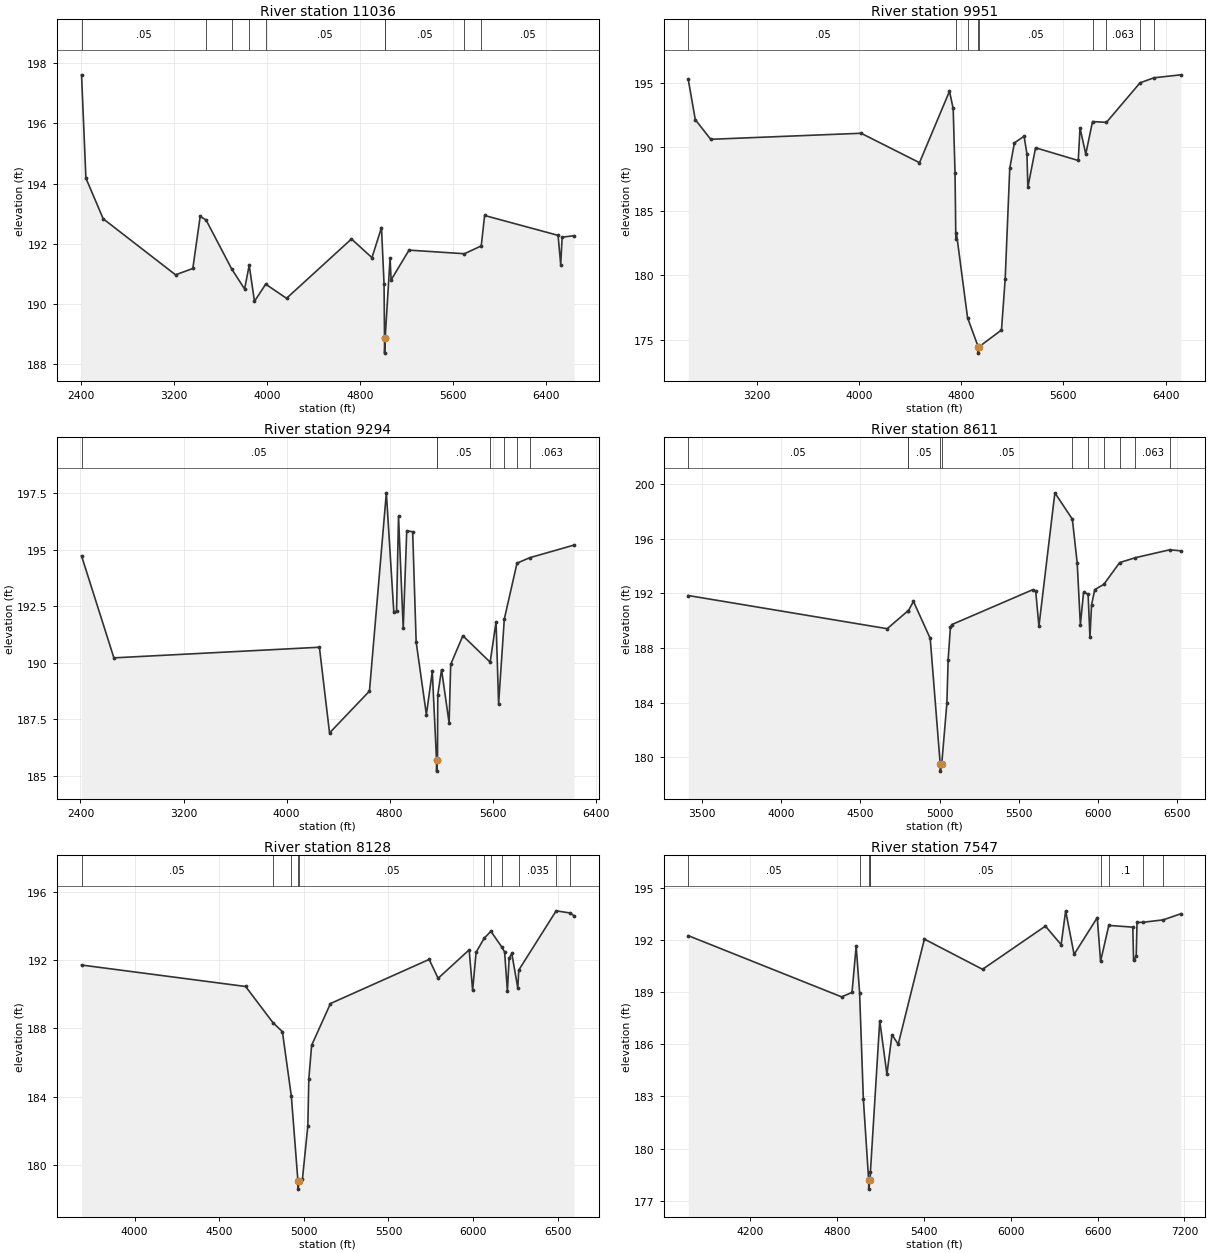
Type RM Length L Ch R = 1,11036,1085,1085,1085
BEGIN DESCRIPTION:
XS7049
END DESCRIPTION:
XS GIS Cut Line= 3
      2515321.94     13597778.54      2513599.56     13599583.65
      2512789.99     13601126.89
#Sta/Elev= 30
  2402.0  197.61  2439.6  194.18  2588.4  192.83  3210.9  190.97  3359.3  191.18
  3422.8  192.91  3473.5  192.79  3694.5  191.16  3805.0  190.50  3844.5  191.29
  3889.9  190.09  3986.2  190.66  4165.7  190.19  4724.3  192.16  4900.6  191.54
  4982.7  192.54  5004.7  190.66  5008.7  188.87  5009.1  188.37  5014.2  188.87
  5056.6  191.53  5065.3  190.80  5219.7  191.79  5696.3  191.67  5840.8  191.93
  5870.0  192.94  6502.1  192.28  6524.6  191.31  6536.8  192.22  6639.7  192.27
#Mann=9,-1,0
  2402.0    0.05       0  3473.5   0.035       0  3694.5    0.05       0
  3844.5   0.035       0  3986.2    0.05       0  5008.7    0.05       0
  5014.2    0.05       0  5696.3   0.063       0  5840.8    0.05       0
Bank Sta=5008.7,5014.2
Exp/Cntr=0.3,0.1

Type RM Length L Ch R = 1,9951,657,657,657
BEGIN DESCRIPTION:
XS7048
END DESCRIPTION:
XS GIS Cut Line= 3
      2514654.62     13597826.93      2512676.16     13599343.31
      2512056.34     13600557.64
#Sta/Elev= 30
  2663.1  195.25  2718.4  192.12  2839.0  190.59  4016.6  191.06  4473.5  188.77
  4708.3  194.33  4737.3  192.99  4751.8  187.97  4758.1  182.81  4762.6  183.30
  4849.8  176.70  4933.0  174.44  4933.5  173.94  4940.5  174.44  5115.4  175.74
  5144.4  179.71  5180.2  188.33  5216.4  190.31  5292.5  190.83  5314.9  189.44
  5321.9  186.85  5382.3  189.93  5716.4  188.94  5730.3  191.47  5775.2  189.44
  5828.3  191.97  5937.3  191.91  6200.3  194.99  6309.5  195.38  6519.2  195.61
#Mann=9,-1,0
  2663.1    0.05       0  4762.6    0.12       0  4849.8    0.05       0
  4933.0    0.05       0  4940.5    0.05       0  5828.3   0.094       0
  5937.3   0.063       0  6200.3   0.094       0  6309.5   0.063       0
Bank Sta=4933,4940.5
Exp/Cntr=0.3,0.1

Type RM Length L Ch R = 1,9294,683,683,683
BEGIN DESCRIPTION:
XS7047
END DESCRIPTION:
XS GIS Cut Line= 4
      2514306.44     13597870.46      2512473.77     13598761.44
      2511853.94     13599760.74      2511790.69     13600367.95
#Sta/Elev= 30
  2408.2  194.72  2659.4  190.21  4254.9  190.68  4333.7  186.89  4643.6  188.74
  4774.7  197.51  4832.6  192.24  4853.8  192.27  4869.2  196.48  4905.8  191.51
  4933.0  195.83  4979.1  195.79  5006.2  190.91  5085.6  187.70  5131.5  189.61
  5164.2  185.70  5164.7  185.20  5171.8  185.70  5174.0  188.57  5203.3  189.69
  5262.1  187.33  5274.3  189.92  5368.8  191.19  5580.5  190.02  5626.6  191.80
  5646.3  188.17  5690.4  191.92  5789.2  194.40  5888.0  194.64  6232.4  195.20
#Mann=7,-1,0
  2408.2    0.05       0  5164.2    0.05       0  5171.8    0.05       0
  5580.5   0.035       0  5690.4   0.063       0  5789.2   0.094       0
  5888.0   0.063       0
Bank Sta=5164.2,5171.8
Exp/Cntr=0.3,0.1

Type RM Length L Ch R = 1,8611,483,483,483
BEGIN DESCRIPTION:
XS7046
END DESCRIPTION:
XS GIS Cut Line= 3
      2512372.58     13597395.29      2511537.71     13599128.27
      2511664.21     13600304.69
#Sta/Elev= 30
  3415.1  191.84  4669.9  189.41  4799.3  190.70  4801.2  190.67  4835.6  191.41
  4941.4  188.70  5004.5  179.48  5005.0  178.98  5013.9  179.48  5046.5  183.96
  5054.5  187.15  5068.7  189.50  5077.1  189.71  5586.9  192.26  5607.0  192.14
  5627.1  189.59  5727.7  199.36  5837.9  197.43  5868.5  194.22  5888.6  189.70
  5908.7  192.09  5937.3  191.94  5948.9  188.77  5959.0  191.15  5979.1  192.27
  6036.7  192.66  6136.1  194.25  6235.5  194.61  6452.6  195.19  6521.9  195.11
#Mann=11,-1,0
  3415.1    0.05       0  4799.3   0.035       0  4801.2    0.05       0
  5004.5    0.05       0  5013.9    0.05       0  5837.9   0.063       0
  5937.3   0.035       0  6036.7   0.063       0  6136.1   0.094       0
  6235.5   0.063       0  6452.6   0.094       0
Bank Sta=5004.5,5013.9
Exp/Cntr=0.3,0.1

Type RM Length L Ch R = 1,8128,581,581,581
BEGIN DESCRIPTION:
E21159
END DESCRIPTION:
XS GIS Cut Line= 3
      2511945.67     13597330.38      2511251.22     13598701.93
      2511563.72     13600038.75
#Sta/Elev= 30
  3686.5  191.72  4656.1  190.46  4817.3  188.34  4873.3  187.81  4926.2  184.01
  4964.8  179.07  4965.3  178.57  4974.2  179.07  4991.9  179.19  5023.6  182.29
  5029.2  185.01  5045.9  187.01  5157.3  189.46  5740.5  192.05  5793.3  190.94
  5976.7  192.61  5997.2  190.23  6017.8  192.47  6065.9  193.30  6105.2  193.70
  6167.8  192.80  6186.1  192.49  6202.6  190.19  6212.9  192.11  6228.6  192.40
  6264.2  190.36  6269.6  191.42  6490.8  194.90  6575.2  194.77  6596.7  194.60
#Mann=11,-1,0
  3686.5    0.05       0  4817.3   0.035       0  4926.2    0.05       0
  4964.8    0.05       0  4974.2    0.05       0  6065.9   0.063       0
  6105.2    0.05       0  6167.8   0.063       0  6269.6   0.035       0
  6490.8   0.094       0  6575.2   0.063       0
Bank Sta=4964.8,4974.2
Exp/Cntr=0.3,0.1

Type RM Length L Ch R = 1,7547,1051,1051,1051
BEGIN DESCRIPTION:
XS7045
END DESCRIPTION:
XS GIS Cut Line= 3
      2511752.75     13597129.66      2510740.80     13598356.66
      2511449.15     13600026.36
#Sta/Elev= 30
  3771.2  192.27  4831.5  188.74  4903.2  189.00  4931.8  191.67  4955.5  188.99
  4981.4  182.87  5018.3  178.16  5018.8  177.66  5027.8  178.16  5030.2  178.64
  5094.8  187.37  5144.3  184.28  5179.4  186.56  5222.4  186.01  5403.3  192.07
  5805.2  190.33  6239.7  192.82  6348.4  191.75  6379.7  193.70  6437.9  191.19
  6598.2  193.31  6621.0  190.79  6677.9  192.86  6843.7  192.76  6849.1  190.85
  6867.3  191.07  6872.8  193.03  6914.1  193.04  7054.3  193.18  7175.4  193.53
#Mann=9,-1,0
  3771.2    0.05       0  4955.5   0.035       0  5018.3   0.035       0
  5027.8   0.035       0  5030.2    0.05       0  6621.0   0.063       0
  6677.9     0.1       0  6914.1   0.063       0  7054.3   0.035       0
Bank Sta=5018.3,5027.8
Exp/Cntr=0.3,0.1

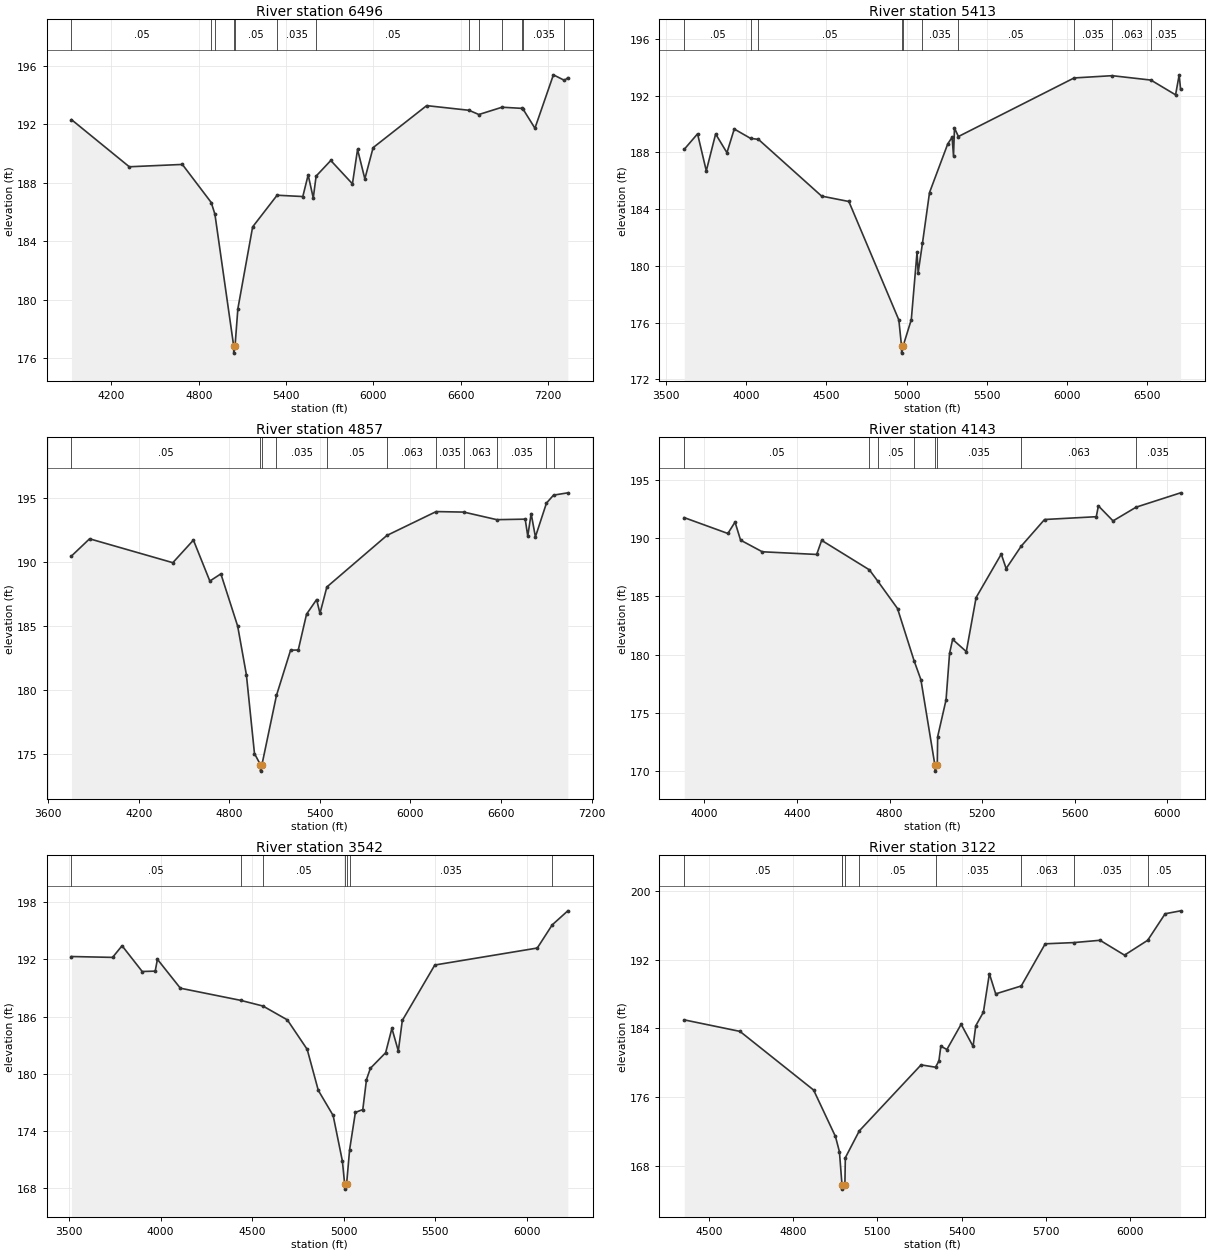
Type RM Length L Ch R = 1,6496,1083,1083,1083
BEGIN DESCRIPTION:
XS7044
END DESCRIPTION:
XS GIS Cut Line= 4
      2510196.87     13597445.90      2509880.64     13598002.47
      2510247.47     13598900.58      2511448.56     13600240.74
#Sta/Elev= 30
  3925.1  192.33  4322.2  189.10  4686.8  189.26  4885.3  186.65  4910.5  185.85
  5039.3  176.83  5039.8  176.33  5048.9  176.83  5068.2  179.37  5169.7  184.98
  5337.8  187.15  5514.4  187.06  5551.1  188.54  5586.2  186.96  5605.8  188.46
  5706.6  189.53  5855.4  187.93  5890.5  190.29  5940.6  188.27  5997.4  190.41
  6365.2  193.29  6656.3  192.97  6723.8  192.68  6883.2  193.18  7023.6  193.10
  7025.1  193.09  7109.1  191.74  7236.1  195.40  7311.9  195.02  7335.0  195.20
#Mann=13,-1,0
  3925.1    0.05       0  4885.3   0.035       0  4910.5    0.05       0
  5039.3    0.05       0  5048.9    0.05       0  5337.8   0.035       0
  5605.8    0.05       0  6656.3   0.035       0  6723.8   0.063       0
  6883.2     0.1       0  7023.6   0.063       0  7025.1   0.035       0
  7311.9   0.094       0
Bank Sta=5039.3,5048.9
Exp/Cntr=0.3,0.1

Type RM Length L Ch R = 1,5413,556,556,556
BEGIN DESCRIPTION:
E21158
END DESCRIPTION:
XS GIS Cut Line= 4
      2509133.14     13598128.97      2509463.02     13598892.90
      2510079.34     13599448.45      2511250.63     13600272.69
#Sta/Elev= 30
  3614.3  188.22  3697.1  189.31  3751.6  186.70  3809.8  189.30  3880.3  187.98
  3925.9  189.65  4027.6  188.99  4076.5  188.92  4470.6  184.92  4640.3  184.54
  4951.9  176.19  4968.6  174.35  4969.1  173.85  4978.5  174.35  5029.6  176.21
  5065.5  180.99  5072.2  179.51  5099.0  181.58  5143.2  185.17  5256.8  188.60
  5284.0  189.07  5292.7  187.76  5298.8  189.72  5323.3  189.12  6044.5  193.25
  6281.7  193.41  6523.3  193.10  6677.1  192.06  6699.6  193.47  6708.4  192.44
#Mann=10,-1,0
  3614.3    0.05       0  4027.6   0.035       0  4076.5    0.05       0
  4968.6    0.05       0  4978.5    0.05       0  5099.0   0.035       0
  5323.3    0.05       0  6044.5   0.035       0  6281.7   0.063       0
  6523.3   0.035       0
Bank Sta=4968.6,4978.5
Exp/Cntr=0.3,0.1

Type RM Length L Ch R = 1,4857,714,714,714
BEGIN DESCRIPTION:
XS7050
END DESCRIPTION:
XS GIS Cut Line= 3
      2509033.11     13598660.20      2509311.41     13599571.00
      2511410.57     13600595.29
#Sta/Elev= 30
  3754.4  190.45  3874.4  191.79  4425.8  189.93  4562.2  191.69  4671.0  188.50
  4744.1  189.06  4855.4  184.99  4913.2  181.20  4966.7  175.07  5006.2  174.20
  5006.7  173.70  5016.2  174.20  5112.3  179.59  5206.0  183.12  5256.7  183.13
  5311.6  185.92  5378.4  187.06  5400.6  185.98  5446.3  188.04  5843.8  192.05
  6170.4  193.91  6353.5  193.87  6572.2  193.28  6760.2  193.32  6777.2  192.00
  6799.7  193.75  6827.8  191.94  6901.1  194.57  6947.8  195.19  7042.5  195.37
#Mann=11,-1,0
  3754.4    0.05       0  5006.2    0.05       0  5016.2    0.05       0
  5112.3   0.035       0  5446.3    0.05       0  5843.8   0.063       0
  6170.4   0.035       0  6353.5   0.063       0  6572.2   0.035       0
  6901.1   0.063       0  6947.8   0.094       0
Bank Sta=5006.2,5016.2
Exp/Cntr=0.3,0.1

Type RM Length L Ch R = 1,4143,601,601,601
BEGIN DESCRIPTION:
E21157
END DESCRIPTION:
XS GIS Cut Line= 3
      2509124.49     13599439.80      2509428.30     13600238.39
      2510512.21     13600940.76
#Sta/Elev= 30
  3912.6  191.75  4101.1  190.39  4132.1  191.37  4156.0  189.82  4249.8  188.82
  4485.2  188.59  4506.6  189.80  4712.9  187.27  4750.0  186.28  4834.6  183.95
  4906.2  179.47  4935.7  177.84  4996.4  170.49  4996.9  169.99  5006.5  170.49
  5008.2  172.95  5044.5  176.11  5059.6  180.09  5072.9  181.30  5132.1  180.25
  5174.4  184.89  5283.2  188.62  5304.3  187.38  5369.3  189.30  5470.4  191.59
  5694.0  191.83  5703.2  192.76  5766.5  191.47  5866.4  192.65  6058.6  193.88
#Mann=8,-1,0
  3912.6    0.05       0  4712.9   0.035       0  4750.0    0.05       0
  4906.2   0.035       0  4996.4   0.035       0  5006.5   0.035       0
  5369.3   0.063       0  5866.4   0.035       0
Bank Sta=4996.4,5006.5
Exp/Cntr=0.3,0.1

Type RM Length L Ch R = 1,3542,420,420,420
BEGIN DESCRIPTION:
XS7043
END DESCRIPTION:
XS GIS Cut Line= 3
      2509007.83     13599343.33      2509273.46     13601038.33
      2510019.78     13601696.10
#Sta/Elev= 30
  3513.4  192.31  3737.8  192.22  3789.6  193.44  3899.7  190.74  3970.6  190.78
  3982.7  192.02  4108.0  188.99  4436.5  187.72  4559.2  187.12  4692.2  185.67
  4800.6  182.58  4861.3  178.28  4942.3  175.65  4992.9  170.87  5005.4  168.43
  5005.9  167.93  5015.6  168.43  5032.4  172.07  5063.8  175.97  5104.3  176.27
  5124.5  179.42  5146.0  180.60  5229.1  182.23  5263.2  184.78  5298.3  182.41
  5320.1  185.61  5497.5  191.42  6057.2  193.20  6138.8  195.63  6223.9  197.10
#Mann=7,-1,0
  3513.4    0.05       0  4436.5   0.035       0  4559.2    0.05       0
  5005.4    0.05       0  5015.6    0.05       0  5032.4   0.035       0
  6138.8    0.05       0
Bank Sta=5005.4,5015.6
Exp/Cntr=0.3,0.1

Type RM Length L Ch R = 1,3122,639,639,639
BEGIN DESCRIPTION:
E21156
END DESCRIPTION:
XS GIS Cut Line= 3
      2508508.16     13600611.65      2509141.84     13601306.09
      2509844.88     13601740.07
#Sta/Elev= 30
  4412.6  184.99  4610.8  183.65  4872.9  176.82  4950.6  171.41  4964.8  169.63
  4973.8  165.80  4973.9  165.78  4974.4  165.28  4984.2  165.78  4985.8  168.94
  5035.4  172.06  5255.3  179.75  5306.7  179.48  5318.8  180.20  5325.6  181.93
  5347.2  181.54  5397.9  184.48  5440.4  181.90  5449.9  184.30  5477.1  185.89
  5498.4  190.37  5520.9  188.02  5611.8  188.94  5697.1  193.85  5798.2  193.99
  5892.2  194.26  5979.3  192.53  6061.8  194.26  6123.9  197.35  6178.9  197.69
#Mann=9,-1,0
  4412.6    0.05       0  4973.8    0.12       0  4973.9    0.05       0
  4984.2    0.12       0  5035.4    0.05       0  5306.7   0.035       0
  5611.8   0.063       0  5798.2   0.035       0  6061.8    0.05       0
Bank Sta=4973.9,4984.2
Exp/Cntr=0.3,0.1

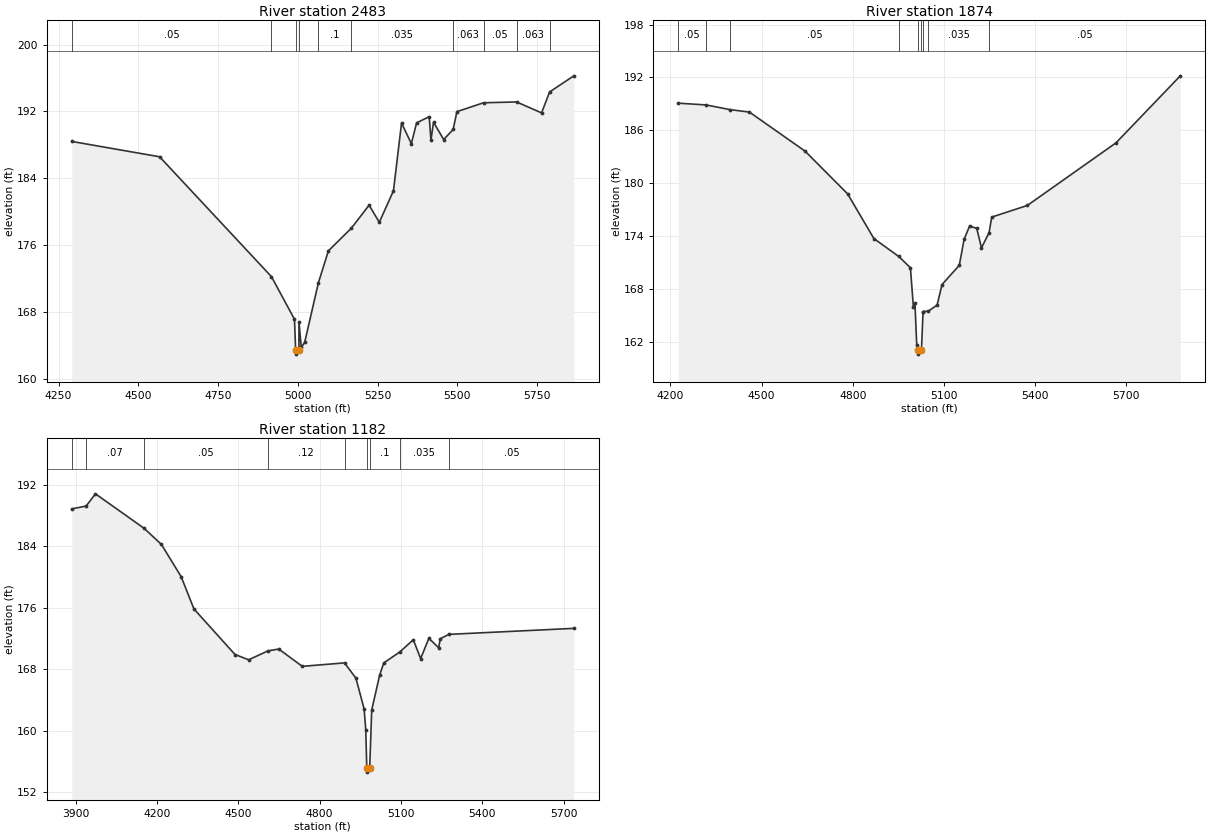
Type RM Length L Ch R = 1,2483,609,609,609
BEGIN DESCRIPTION:
E21155
END DESCRIPTION:
XS GIS Cut Line= 3
      2508265.09     13601210.60      2508629.69     13601471.02
      2509688.76     13601852.98
#Sta/Elev= 30
  4291.3  188.42  4566.6  186.59  4917.4  172.26  4989.5  167.17  4993.1  163.51
  4993.6  163.01  5003.4  163.51  5003.5  166.87  5010.8  163.82  5021.4  164.41
  5064.5  171.54  5095.8  175.35  5168.0  178.07  5223.4  180.81  5255.3  178.76
  5299.7  182.52  5325.1  190.62  5355.8  188.16  5372.2  190.64  5411.8  191.38
  5417.2  188.57  5425.4  190.72  5457.2  188.65  5486.8  189.85  5498.6  191.98
  5582.1  193.04  5685.6  193.14  5764.1  191.83  5789.1  194.33  5865.2  196.26
#Mann=10,-1,0
  4291.3    0.05       0  4917.4    0.12       0  4993.1    0.05       0
  5003.4    0.12       0  5064.5     0.1       0  5168.0   0.035       0
  5486.8   0.063       0  5582.1    0.05       0  5685.6   0.063       0
  5789.1    0.05       0
Bank Sta=4993.1,5003.4
Exp/Cntr=0.3,0.1

Type RM Length L Ch R = 1,1874,692,692,692
BEGIN DESCRIPTION:
E21154
END DESCRIPTION:
XS GIS Cut Line= 3
      2508343.25     13601488.42      2508673.09     13602069.98
      2509619.28     13602339.08
#Sta/Elev= 30
  4225.8  189.08  4317.2  188.88  4397.7  188.34  4460.0  188.07  4643.2  183.64
  4783.1  178.80  4869.6  173.73  4951.2  171.70  4989.9  170.42  4999.6  165.99
  5004.8  166.43  5010.7  161.61  5015.9  161.12  5016.4  160.62  5026.3  161.12
  5031.5  165.44  5032.5  165.45  5049.4  165.50  5077.8  166.19  5093.9  168.51
  5150.7  170.69  5166.7  173.64  5184.6  175.15  5208.3  174.87  5223.7  172.67
  5248.7  174.39  5257.5  176.16  5374.7  177.48  5666.5  184.58  5878.1  192.18
#Mann=9,-1,0
  4225.8    0.05       0  4317.2    0.07       0  4397.7    0.05       0
  4951.2     0.1       0  5015.9    0.05       0  5026.3     0.1       0
  5032.5    0.12       0  5049.4   0.035       0  5248.7    0.05       0
Bank Sta=5015.9,5026.3
Exp/Cntr=0.3,0.1

Type RM Length L Ch R = 1,1182,0,0,0
BEGIN DESCRIPTION:
E21153
END DESCRIPTION:
XS GIS Cut Line= 3
      2508256.43     13601488.41      2508377.95     13602391.16
      2508889.71     13603180.48
#Sta/Elev= 30
  3886.0  188.86  3939.0  189.23  3973.4  190.82  4152.9  186.33  4216.6  184.24
  4289.4  180.04  4336.6  175.84  4488.0  169.92  4538.4  169.23  4609.3  170.39
  4649.4  170.63  4736.2  168.38  4891.9  168.83  4933.9  166.84  4964.2  162.84
  4970.2  160.16  4974.0  155.12  4974.5  154.62  4984.7  155.12  4992.2  162.71
  5021.6  167.25  5036.7  168.83  5095.4  170.24  5145.5  171.84  5172.6  169.39
  5202.9  172.02  5239.2  170.80  5245.1  171.97  5276.8  172.54  5737.6  173.32
#Mann=9,-1,0
  3886.0    0.05       0  3939.0    0.07       0  4152.9    0.05       0
  4609.3    0.12       0  4891.9     0.1       0  4974.0    0.05       0
  4984.7     0.1       0  5095.4   0.035       0  5276.8    0.05       0
Bank Sta=4974,4984.7
Exp/Cntr=0.3,0.1

Chan Stop Cuts=-1