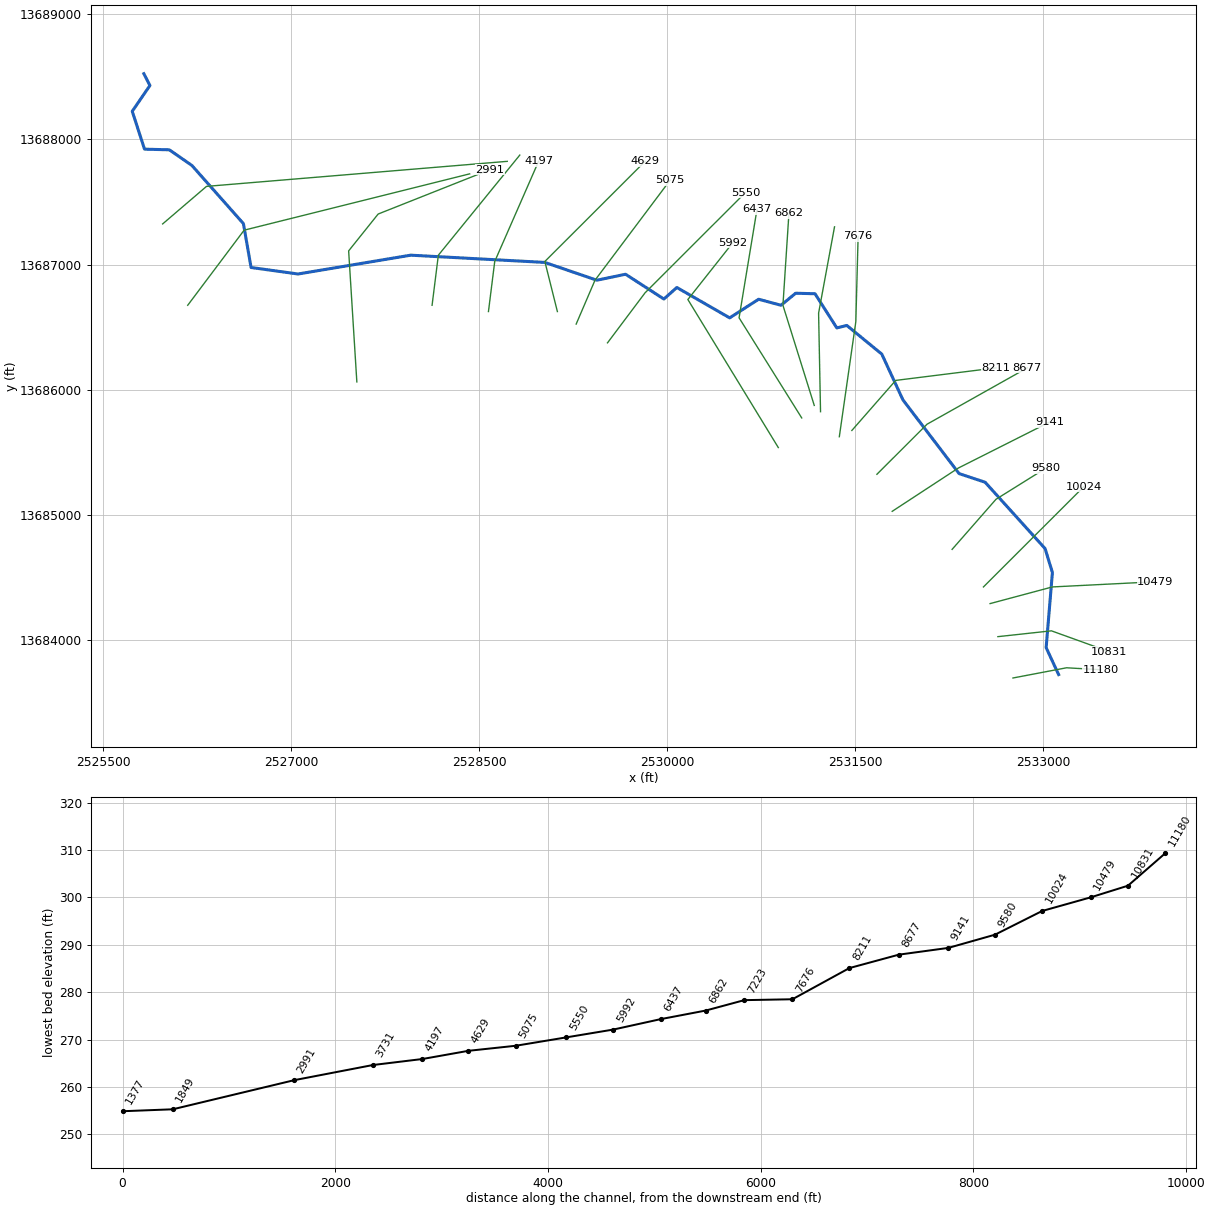
--- Turkey Creek 3.prj (project) ---

Proj Title=Turkey Creek 3 Base Level Engineering
Current Plan=p01
Default Exp/Contr=0.3,0.1
English Units
Geom File=g01
Flow File=f01
Plan File=p01
Y Axis Title=Elevation
X Axis Title(PF)=Main Channel Distance
X Axis Title(XS)=Station
BEGIN DESCRIPTION:
Turkey Creek 3
END DESCRIPTION:
DSS Export Rating Curves= 0
DSS Export Rating Curve Sorted= 0
DSS Export Volume Flow Curves= 0
DXF OffsetX= 0
DXF OffsetY= 0
DXF ScaleX= 1
DXF ScaleY= 10

--- Turkey Creek 3.p01 (plan) ---

Plan Title=Multiple Run
Short Identifier=Multiple
Geom File=g01
Flow File=f01
Subcritical Flow
K Sum by GR= 0
Std Step Tol= 0.01
Critical Tol= 0.01
Num of Std Step Trials= 20
Max Error Tol= 0.3
Flow Tol Ratio= 0.001
Split Flow NTrial= 30
Split Flow Tol= 0.02
Split Flow Ratio= 0.02
Log Output Level= 0
Friction Slope Method= 1
Unsteady Friction Slope Method= 2
Unsteady Bridges Friction Slope Method= 1
Parabolic Critical Depth
Global Vel Dist=  1 , 1 , 1
Global Log Level= 0
CheckData=True
Encroach Param= -1, 0, 0, 0
BEGIN DESCRIPTION:
Multiple Run
END DESCRIPTION:

--- Turkey Creek 3.f01 (steady flow) ---

Flow Title=Multiple
Number of Profiles=7
Profile Names=10-year,25-year,50-year,1pct_min,100-year,1pct_plu,500-year
River Rch & RM= Turkey Creek 3,Reach-1,11180
    1005    1662    2273    1506    3004    5994    5191
River Rch & RM= Turkey Creek 3,Reach-1,7676
    2123    3657    5136    3486    6955   13876   12631
River Rch & RM= Turkey Creek 3,Reach-1,5550
    2515    4334    6088    4127    8235   16431   14929
Boundary for River Rch & Prof#=Turkey Creek 3,Reach-1,1
Up Type=0
Dn Type=3
Dn Slope=0.005
Boundary for River Rch & Prof#=Turkey Creek 3,Reach-1,2
Up Type=0
Dn Type=3
Dn Slope=0.005
Boundary for River Rch & Prof#=Turkey Creek 3,Reach-1,3
Up Type=0
Dn Type=3
Dn Slope=0.005
Boundary for River Rch & Prof#=Turkey Creek 3,Reach-1,4
Up Type=0
Dn Type=3
Dn Slope=0.005
Boundary for River Rch & Prof#=Turkey Creek 3,Reach-1,5
Up Type=0
Dn Type=3
Dn Slope=0.005
Boundary for River Rch & Prof#=Turkey Creek 3,Reach-1,6
Up Type=0
Dn Type=3
Dn Slope=0.005
Boundary for River Rch & Prof#=Turkey Creek 3,Reach-1,7
Up Type=0
Dn Type=3
Dn Slope=0.005

--- Turkey Creek 3.g01 (geometry) ---

Geom Title=Existing Conditions
Program Version=4.10

River Reach=Turkey Creek 3  ,Reach-1
Reach XY= 30
        2533125.       13683725.      2533025.38     13683940.27
      2533075.43     13684540.18      2533017.14     13684731.17
      2532538.33     13685261.61      2532330.61     13685330.59
      2531882.88     13685918.83      2531714.24     13686284.68
        2531435.     13686513.91      2531354.96     13686494.35
      2531181.21      13686767.2      2531026.47     13686771.46
      2530909.78     13686675.25      2530731.03     13686723.38
      2530499.97      13686574.5      2530078.23     13686817.23
        2529975.       13686725.      2529669.11     13686923.04
      2529440.27     13686875.38        2529025.     13687017.44
      2527954.85     13687075.36      2527054.96     13686925.05
      2526680.65     13686976.97      2526619.54     13687327.45
       2526208.5     13687792.05      2526028.41     13687917.19
      2525830.34     13687922.26       2525732.3     13688224.92
      2525873.45     13688430.97        2525825.       13688525.

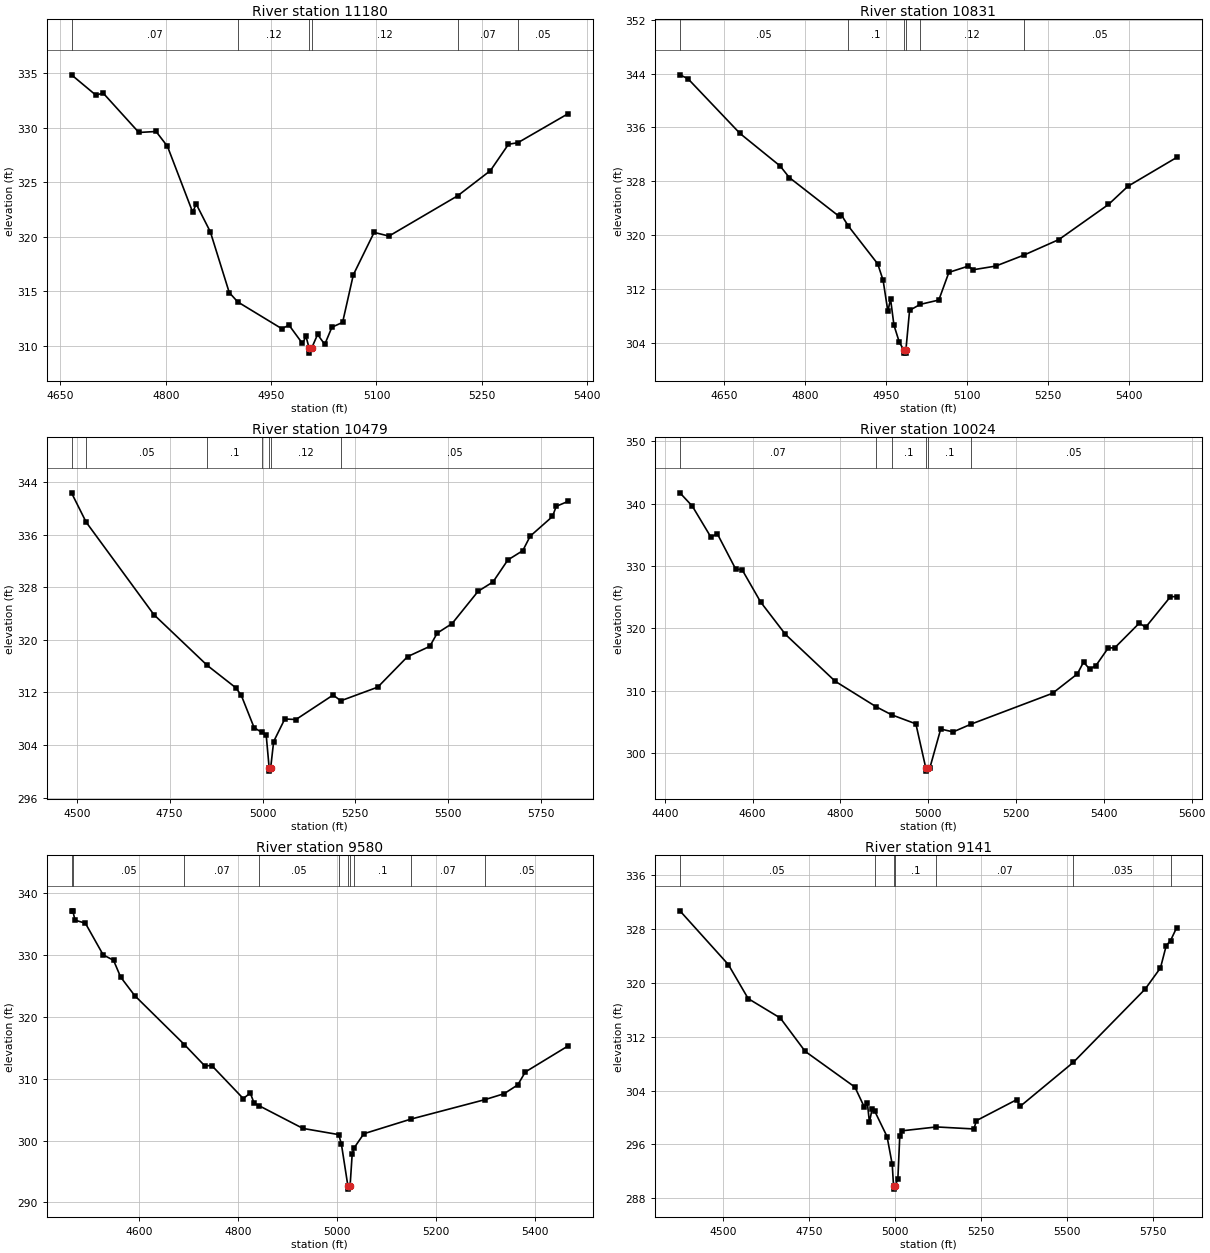
Type RM Length L Ch R = 1 ,11180   ,349,349,349
BEGIN DESCRIPTION:
XS7870
END DESCRIPTION:
XS GIS Cut Line= 3
      2532760.79     13683697.61      2533188.04     13683779.17
      2533459.93     13683763.64
#Sta/Elev= 30
  4665.8  334.85  4700.6  332.98  4710.8  333.18  4761.7  329.56  4786.2  329.65
  4802.4  328.29  4838.3  322.25  4843.4  322.99  4863.5  320.44  4890.4  314.87
  4902.5  314.01  4965.3  311.55  4975.5  311.88  4994.6   310.2  4999.7  310.84
    5004  309.81  5004.3  309.31    5008  309.81  5016.2  311.02  5026.4  310.11
  5036.6  311.69  5051.8  312.13  5067.1   316.5  5096.7  320.39  5117.8  320.05
  5215.7  323.75  5262.3  326.06    5288  328.48  5301.4  328.62  5373.1  331.29
#Mann= 6 ,-1 , 0
  4665.8     .07       0  4902.5     .12       0    5004     .05       0
    5008     .12       0  5215.7     .07       0  5301.4     .05       0
Bank Sta=5004,5008
XS Rating Curve= 0 ,0
Exp/Cntr=0.3,0.1

Type RM Length L Ch R = 1 ,10831   ,352,352,352
BEGIN DESCRIPTION:
Turkey Creek 3 19.0
END DESCRIPTION:
XS GIS Cut Line= 3
       2532640.3     13684027.77      2533067.62     13684074.39
      2533529.91     13683907.35
#Sta/Elev= 30
  4567.9  343.81  4582.7  343.24  4679.4   335.1  4753.7  330.28  4770.8  328.56
  4862.2  322.86  4867.2  323.02  4880.4  321.35  4934.8  315.74  4944.8   313.3
  4953.6  308.71  4958.6  310.52  4964.9  306.64    4975  304.07    4983  302.99
  4983.3  302.49  4986.8  302.49  4987.1  302.99  4993.9  308.84  5013.7  309.73
  5048.1  310.37  5066.8  314.48  5102.8  315.41  5111.9  314.87  5153.5  315.41
  5205.8  317.04  5270.8  319.35  5362.8  324.56    5399  327.27  5489.3  331.54
#Mann= 6 ,-1 , 0
  4567.9     .05       0  4880.4      .1       0    4983     .05       0
  4987.1      .1       0  5013.7     .12       0  5205.8     .05       0
Bank Sta=4983,4987.1
XS Rating Curve= 0 ,0
Exp/Cntr=0.3,0.1

Type RM Length L Ch R = 1 ,10479   ,455,455,455
BEGIN DESCRIPTION:
Turkey Creek 3 18.0
END DESCRIPTION:
XS GIS Cut Line= 3
      2532578.14     13684291.91        2533075.       13684425.
      2533897.38     13684466.41
#Sta/Elev= 30
  4485.6   342.4  4525.1  337.93  4707.5  323.85  4851.4  316.11  4927.5  312.74
  4942.5  311.61  4977.4  306.64  4997.5  305.94    5010  305.47  5017.9  300.52
  5018.2  300.02    5022  300.52    5030  304.52    5060  307.96  5090.1  307.88
  5190.2  311.61  5210.8  310.73  5310.4  312.81  5390.5  317.45  5450.5  319.02
  5470.6  321.04  5510.6  322.49  5580.7  327.41  5620.8  328.83  5660.8  332.18
  5700.9  333.59  5720.9   335.8    5781   338.8    5791  340.34  5823.4  341.11
#Mann= 7 ,-1 , 0
  4485.6     .07       0  4525.1     .05       0  4851.4      .1       0
  4997.5     .12       0  5017.9     .05       0    5022     .12       0
  5210.8     .05       0
Bank Sta=5017.9,5022
XS Rating Curve= 0 ,0
Exp/Cntr=0.3,0.1

Type RM Length L Ch R = 1 ,10024   ,444,444,444
BEGIN DESCRIPTION:
Turkey Creek 3 17.0
END DESCRIPTION:
XS GIS Cut Line= 3
      2532524.98     13684424.98        2532925.       13684825.
        2533325.       13685225.
#Sta/Elev= 30
  4434.5  341.71  4462.8  339.57  4505.2   334.6  4519.4  335.19  4561.8  329.46
  4575.9  329.43  4618.4  324.22  4674.9  319.04  4788.1  311.54  4881.8  307.44
    4917  306.16  4971.9  304.72  4994.5  297.65  4994.8  297.15  4998.9  297.65
  5003.7  297.65  5028.5  303.89  5056.8  303.43  5098.5   304.7  5283.1  309.61
  5339.6  312.71  5353.8   314.6  5367.9  313.48    5382  314.05  5410.3   316.9
  5424.5  316.87    5481  320.86  5495.2  320.18  5551.8  325.08  5565.9  325.09
#Mann= 6 ,-1 , 0
  4434.5     .07       0  4881.8     .05       0    4917      .1       0
  4994.5     .05       0  4998.9      .1       0  5098.5     .05       0
Bank Sta=4994.5,4998.9
XS Rating Curve= 0 ,0
Exp/Cntr=0.3,0.1

Type RM Length L Ch R = 1 ,9580    ,439,439,439
BEGIN DESCRIPTION:
Turkey Creek 3 16.0
END DESCRIPTION:
XS GIS Cut Line= 3
      2532275.02     13684725.02        2532625.       13685125.
      2533025.02     13685375.01
#Sta/Elev= 30
  4464.1  337.16  4466.7  337.16  4471.2  335.65  4492.1  335.16  4528.1  330.03
    4549  329.16  4563.3  326.45  4591.7  323.45    4692  315.53  4733.1  312.09
  4747.4  312.13    4811  306.79  4825.2  307.69  4832.8  306.05  4842.3  305.66
  4931.5  301.96  5003.7  300.96  5009.1  299.46  5022.3  292.64  5022.6  292.14
  5026.7  292.64    5031  297.87  5035.3  298.86  5054.5   301.1  5149.3  303.46
  5298.3   306.6  5337.6  307.57  5365.3     309  5380.6  311.09  5467.3  315.32
#Mann= 10 ,-1 , 0
  4464.1    .035       0  4466.7     .05       0    4692     .07       0
  4842.3     .05       0  5003.7     .15       0  5022.3     .05       0
  5026.7     .15       0  5035.3      .1       0  5149.3     .07       0
  5298.3     .05       0
Bank Sta=5022.3,5026.7
XS Rating Curve= 0 ,0
Exp/Cntr=0.3,0.1

Type RM Length L Ch R = 1 ,9141    ,464,464,464
BEGIN DESCRIPTION:
Turkey Creek 3 15.0
END DESCRIPTION:
XS GIS Cut Line= 3
      2531797.13     13685029.09        2532325.       13685375.
      2533051.64      13685741.4
#Sta/Elev= 30
  4373.6   330.7  4514.5  322.71  4572.1  317.66  4665.6  314.77  4737.9  309.82
  4882.6  304.51  4909.7  301.57  4918.8  302.15  4924.8   299.3    4933  301.32
  4939.8  300.98  4976.1  297.16  4991.2  293.01  4994.9  289.85  4995.2  289.35
  4999.4  289.85  5007.5  290.84  5013.1  297.23  5018.7  298.01  5119.9  298.59
  5228.7  298.29  5236.1  299.53  5353.2  302.64  5363.1  301.64    5518  308.19
  5726.8  319.07  5771.4  322.22  5788.1  325.52  5800.8  326.29  5818.5   328.2
#Mann= 7 ,-1 , 0
  4373.6     .05       0  4939.8      .1       0  4994.9     .05       0
  4999.4      .1       0  5119.9     .07       0    5518    .035       0
  5800.8     .05       0
Bank Sta=4994.9,4999.4
XS Rating Curve= 0 ,0
Exp/Cntr=0.3,0.1

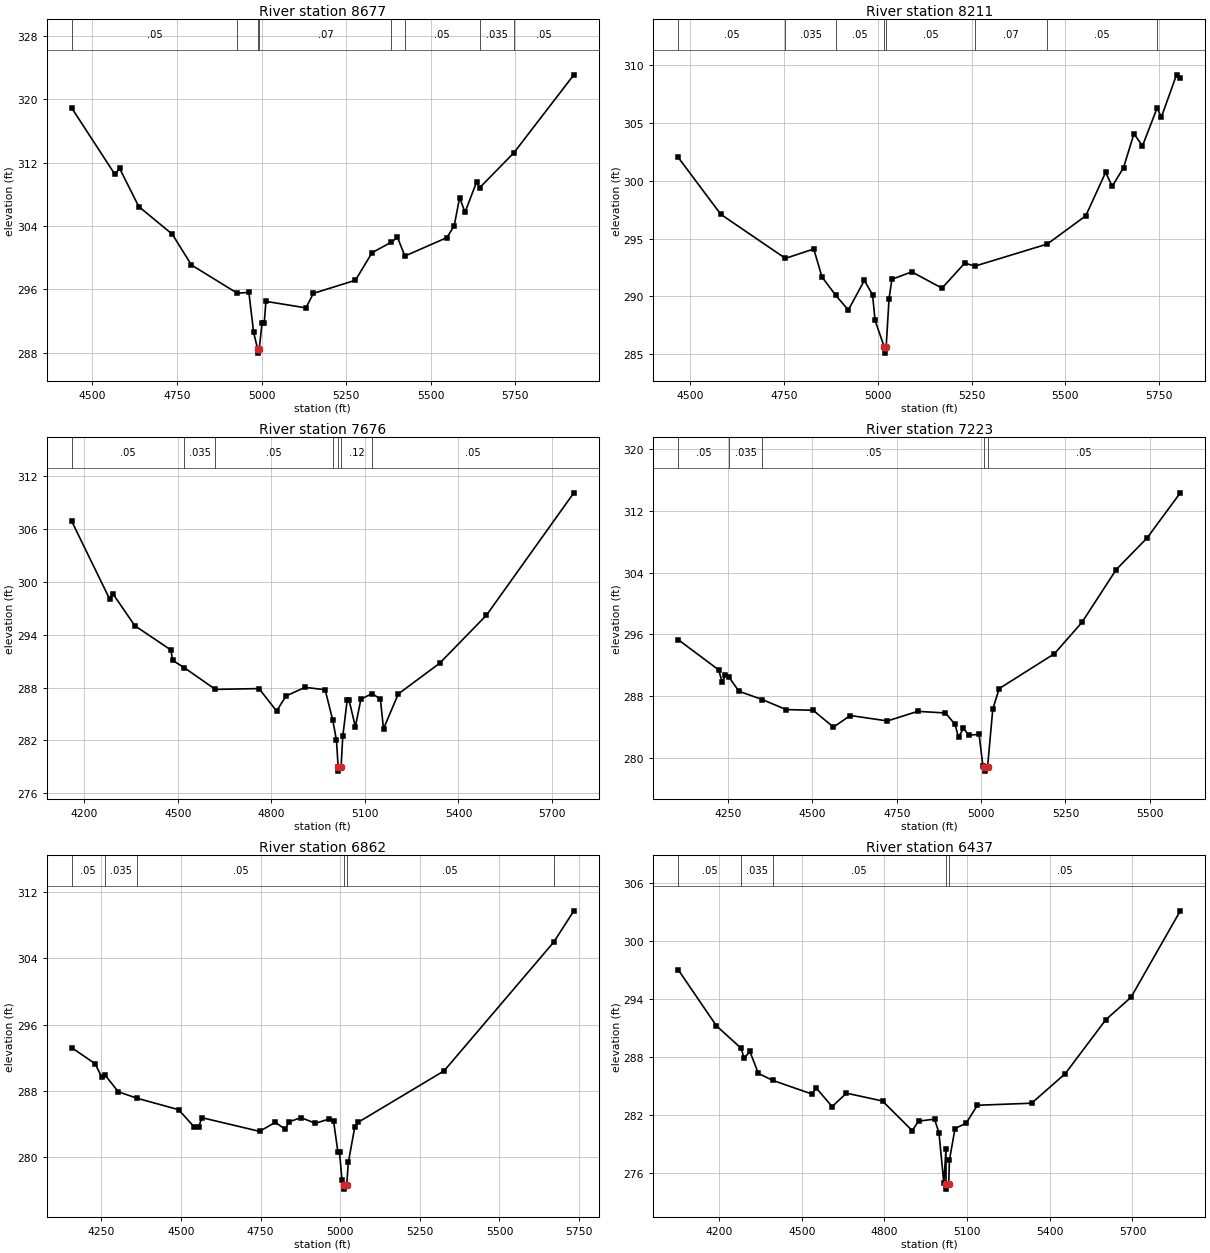
Type RM Length L Ch R = 1 ,8677    ,466,466,466
BEGIN DESCRIPTION:
Turkey Creek 3 14.0
END DESCRIPTION:
XS GIS Cut Line= 3
      2531674.99     13685324.99        2532075.       13685725.
      2532875.01     13686175.01
#Sta/Elev= 30
    4439   318.9  4566.3  310.53  4580.4  311.27    4637  306.45    4736  302.96
  4792.6  299.07  4928.1   295.5  4962.3  295.61  4976.4  290.55  4988.3  288.43
  4988.6  287.93  4992.8  288.43  5001.2  291.69  5007.6  291.69  5012.7  294.47
  5130.9  293.65  5152.9  295.48  5277.2  297.14  5326.3  300.62  5383.6  301.96
  5401.5  302.56  5423.3   300.2  5547.5  302.53  5569.1  304.04  5585.1  307.58
    5601  305.73  5635.7  309.61  5644.1  308.82  5745.6  313.26  5922.6   323.1
#Mann= 8 ,-1 , 0
    4439     .05       0  4928.1     .07       0  4988.3     .05       0
  4992.8     .07       0  5383.6    .035       0  5423.3     .05       0
  5644.1    .035       0  5745.6     .05       0
Bank Sta=4988.3,4992.8
XS Rating Curve= 0 ,0
Exp/Cntr=0.3,0.1

Type RM Length L Ch R = 1 ,8211    ,535,535,535
BEGIN DESCRIPTION:
Turkey Creek 3 13.0
END DESCRIPTION:
XS GIS Cut Line= 3
      2531475.02     13685675.03        2531825.       13686075.
        2532625.       13686175.
#Sta/Elev= 30
  4468.5  302.02  4581.9   297.1    4754  293.29  4829.6   294.1  4851.4  291.68
  4888.2  290.09  4921.7  288.82  4964.4  291.38  4986.2  290.14  4992.9  287.92
  5017.8  285.59  5018.1  285.09  5022.4  285.59  5030.2  289.81  5037.8  291.48
  5090.7  292.12  5171.3  290.71  5231.8  292.88  5259.2  292.62  5451.8  294.53
  5554.3  296.97  5607.2  300.73  5624.8  299.52    5655  301.15  5682.7  304.07
  5705.4  303.02  5744.3  306.29  5755.8  305.52  5796.1  309.17  5806.2  308.86
#Mann= 8 ,-1 , 0
  4468.5     .05       0    4754    .035       0  4888.2     .05       0
  5017.8     .05       0  5022.4     .05       0  5259.2     .07       0
  5451.8     .05       0  5744.3    .035       0
Bank Sta=5017.8,5022.4
XS Rating Curve= 0 ,0
Exp/Cntr=0.3,0.1

Type RM Length L Ch R = 1 ,7676    ,453,453,453
BEGIN DESCRIPTION:
Turkey Creek 3 12.0
END DESCRIPTION:
XS GIS Cut Line= 3
        2531375.       13685625.       2531506.8     13686545.25
        2531525.     13687224.97
#Sta/Elev= 30
  4160.3  306.86  4281.5  298.06  4291.6  298.67  4362.3  295.02  4478.1  292.26
  4483.6  291.08  4520.7  290.26  4620.6  287.79  4760.6  287.88  4816.9  285.33
  4847.2  287.04  4907.8  288.02  4972.5  287.75  4997.2  284.26  5008.9  282.02
  5014.2  279.01  5014.7  278.51  5023.7  279.01  5029.1  282.45  5043.1  286.53
  5049.3  286.56  5069.5  283.55  5087.3  286.69  5123.6  287.31  5149.7  286.67
  5159.7  283.32  5207.1  287.27  5339.8  290.76  5489.8  296.21  5769.9   310.1
#Mann= 7 ,-1 , 0
  4160.3     .05       0  4520.7    .035       0  4620.6     .05       0
  4997.2     .12       0  5014.2     .05       0  5023.7     .12       0
  5123.6     .05       0
Bank Sta=5014.2,5023.7
XS Rating Curve= 0 ,0
Exp/Cntr=0.3,0.1

Type RM Length L Ch R = 1 ,7223    ,361,361,361
BEGIN DESCRIPTION:
Turkey Creek 3 11.0
END DESCRIPTION:
XS GIS Cut Line= 3
        2531225.     13685825.02      2531209.59     13686611.97
      2531336.66     13687301.76
#Sta/Elev= 30
    4102  295.32    4222  291.41    4232  289.82    4242  290.75    4253  290.43
    4282  288.65  4351.5  287.57    4422  286.28  4502.1  286.19  4562.1  284.01
  4612.1  285.51  4722.1  284.81  4812.1  286.05  4894.3  285.84  4922.7  284.37
  4932.9  282.67  4947.3  283.87  4963.4  282.97  4993.9  283.07  5005.4  278.94
  5009.5  278.82    5010  278.32    5019  278.82  5034.5  286.32  5053.4  288.99
  5217.5  293.51  5298.9  297.56  5400.6  304.39  5492.1  308.48  5590.5  314.31
#Mann= 5 ,-1 , 0
    4102     .05       0    4253    .035       0  4351.5     .05       0
  5009.5     .05       0    5019     .05       0
Bank Sta=5009.5,5019
XS Rating Curve= 0 ,0
Exp/Cntr=0.3,0.1

Type RM Length L Ch R = 1 ,6862    ,425,425,425
BEGIN DESCRIPTION:
Turkey Creek 3 10.0
END DESCRIPTION:
XS GIS Cut Line= 3
      2531174.99     13685875.02        2530925.       13686675.
      2530972.95     13687411.31
#Sta/Elev= 30
  4157.5  293.21  4230.8  291.28  4251.8  289.64    4261  289.96  4303.6  287.89
  4363.3   287.1  4492.7  285.73  4541.5  283.65  4555.6  283.62  4566.1  284.76
  4746.8  283.11  4796.6   284.2    4828  283.34  4838.5  284.24  4876.7  284.77
  4922.3  284.08  4964.2  284.59  4979.4  284.32    4993  280.58  4998.1  280.58
  5005.7   277.2  5010.9  276.63  5011.4  276.13  5020.4  276.63  5025.7  279.37
  5045.7   283.6  5055.8  284.19  5326.3  290.42  5670.8  305.99  5733.5  309.75
#Mann= 6 ,-1 , 0
  4157.5     .05       0    4261    .035       0  4363.3     .05       0
  5010.9     .05       0  5020.4     .05       0  5670.8     .07       0
Bank Sta=5010.9,5020.4
XS Rating Curve= 0 ,0
Exp/Cntr=0.3,0.1

Type RM Length L Ch R = 1 ,6437    ,445,445,445
BEGIN DESCRIPTION:
Turkey Creek 3 9.0
END DESCRIPTION:
XS GIS Cut Line= 3
      2531074.98     13685775.03        2530575.       13686575.
      2530718.04      13687441.5
#Sta/Elev= 30
    4052  297.01  4190.5  291.21  4280.1  288.89  4290.8  287.85    4312  288.56
  4342.7  286.28  4394.2  285.57  4537.2  284.15  4552.6  284.78  4610.3  282.85
  4662.2  284.24  4793.1  283.43    4901  280.36    4924  281.35  4981.8  281.55
  4997.9  280.15  5015.6  274.94  5023.4  278.46  5023.6  274.81  5024.1  274.31
  5033.3  274.81  5035.9  277.31  5056.2  280.58  5096.7  281.14  5137.3  282.99
    5334   283.2  5456.2  286.26  5603.5  291.85  5694.7  294.16  5873.6  303.11
#Mann= 5 ,-1 , 0
    4052     .05       0  4280.1    .035       0  4394.2     .05       0
  5023.6     .05       0  5033.3     .05       0
Bank Sta=5023.6,5033.3
XS Rating Curve= 0 ,0
Exp/Cntr=0.3,0.1

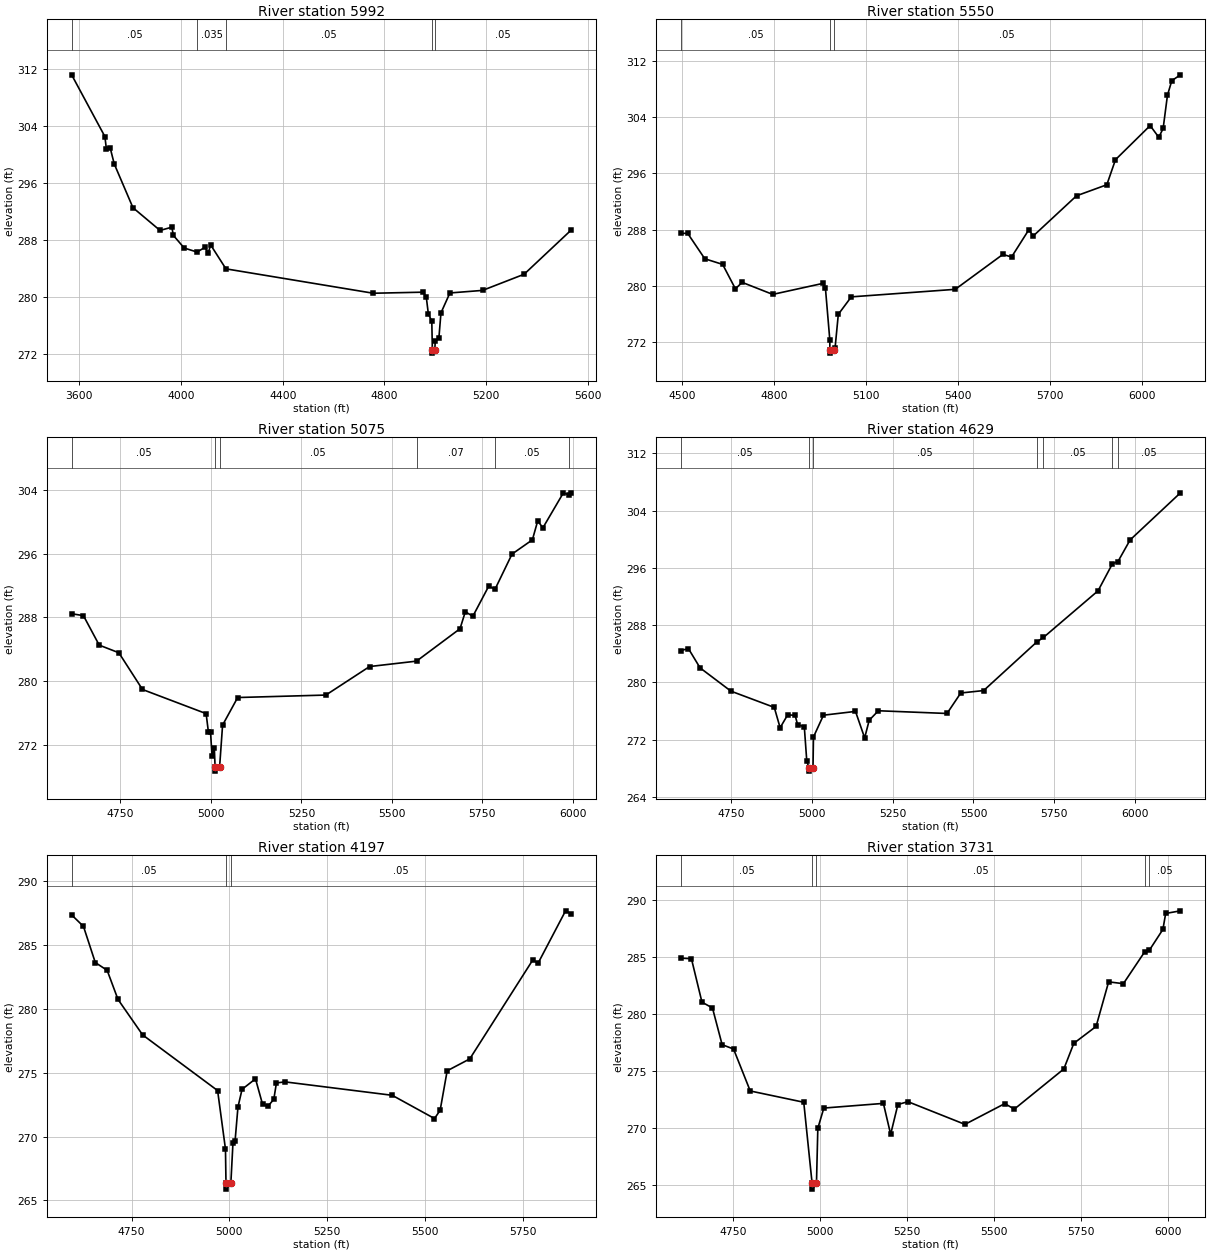
Type RM Length L Ch R = 1 ,5992    ,442,442,442
BEGIN DESCRIPTION:
Turkey Creek 3 8.0
END DESCRIPTION:
XS GIS Cut Line= 3
       2530888.1     13685538.39      2530166.31     13686721.15
      2530525.01     13687175.01
#Sta/Elev= 30
  3570.1  311.24  3700.8  302.56  3706.7  300.82  3722.2  300.89  3737.6  298.71
  3811.1  292.56  3917.7  289.36  3964.1  289.82  3969.9  288.67  4012.6  286.89
  4063.3  286.32  4093.3  286.97  4107.4  286.23  4116.7  287.32  4176.7  283.96
  4755.9  280.53  4951.5  280.68  4964.3  280.01  4972.4  277.67  4986.1  276.57
  4988.3  272.61  4988.8  272.11    4998  272.61  4999.6  273.81    5014  274.24
  5022.1  277.77  5057.3  280.57  5185.6  280.93    5349   283.2  5534.2  289.42
#Mann= 5 ,-1 , 0
  3570.1     .05       0  4063.3    .035       0  4176.7     .05       0
  4988.3     .05       0    4998     .05       0
Bank Sta=4988.3,4998
XS Rating Curve= 0 ,0
Exp/Cntr=0.3,0.1

Type RM Length L Ch R = 1 ,5550    ,475,475,475
BEGIN DESCRIPTION:
Turkey Creek 3 7.0
END DESCRIPTION:
XS GIS Cut Line= 3
      2529525.01     13686375.02        2529825.       13686775.
      2530624.97     13687574.97
#Sta/Elev= 30
  4495.7  287.45  4517.6  287.49  4573.8  283.86  4632.1  283.06  4673.8  279.59
  4695.7  280.51  4795.7   278.8  4959.2  280.36  4967.6  279.76  4982.1  272.31
  4982.2  270.96  4982.7  270.46  4994.5  270.96  4999.2  271.17  5009.8  275.97
  5052.2  278.45  5391.7  279.52  5547.2  284.48  5575.5  284.11  5632.1  287.99
  5646.2  287.09  5787.6   292.8  5886.6  294.37  5914.9  297.93  6028.1  302.77
  6056.3  301.11  6070.5  302.36  6084.6  307.08  6098.8  309.15    6127  309.98
#Mann= 3 ,-1 , 0
  4495.7     .05       0  4982.2     .05       0  4994.5     .05       0
Bank Sta=4982.2,4994.5
XS Rating Curve= 0 ,0
Exp/Cntr=0.3,0.1

Type RM Length L Ch R = 1 ,5075    ,446,446,446
BEGIN DESCRIPTION:
Turkey Creek 3 6.0
END DESCRIPTION:
XS GIS Cut Line= 3
        2529275.     13686525.01        2529425.       13686875.
      2530025.01     13687675.01
#Sta/Elev= 30
    4615  288.45  4647.6  288.21  4691.2  284.51  4745.5  283.55  4810.8  278.94
  4986.7  275.91  4993.1  273.57  4998.9  273.57  5003.1  270.53  5009.3  271.64
  5011.5  269.19    5012  268.69  5023.9  269.19  5032.2  274.47  5073.9  277.93
  5317.7  278.24  5438.5  281.82  5568.3   282.5  5688.5  286.57  5703.1   288.7
  5723.9  288.13  5767.7   291.9  5785.4  291.54  5832.2  295.94  5888.5  297.73
  5903.1  300.09  5917.7  299.25  5973.9  303.61  5989.1  303.39  5995.8  303.63
#Mann= 6 ,-1 , 0
    4615     .05       0  5011.5     .05       0  5023.9     .05       0
  5568.3     .07       0  5785.4     .05       0  5989.1     .07       0
Bank Sta=5011.5,5023.9
XS Rating Curve= 0 ,0
Exp/Cntr=0.3,0.1

Type RM Length L Ch R = 1 ,4629    ,432,432,432
BEGIN DESCRIPTION:
Turkey Creek 3 5.0
END DESCRIPTION:
XS GIS Cut Line= 3
        2529125.     13686624.99        2529025.       13687025.
      2529825.01     13687825.01
#Sta/Elev= 30
  4595.8  284.45    4619  284.74  4655.1  282.04  4750.4  278.79  4884.4  276.52
  4902.5  273.68  4925.7  275.47  4948.8  275.42  4956.6  274.09  4977.2  273.83
  4984.9     269  4991.6  268.12  4992.1  267.62  5004.1  268.12  5005.5  272.38
  5036.4  275.43  5135.4  275.96  5163.7  272.26  5177.8  274.73  5206.1  276.05
  5418.2  275.67  5460.7  278.53  5531.4  278.87  5695.8  285.66  5716.3  286.29
  5884.9   292.8  5929.4  296.58  5946.4  296.88  5983.9   299.9  6139.5  306.48
#Mann= 7 ,-1 , 0
  4595.8     .05       0  4991.6     .05       0  5004.1     .05       0
  5695.8    .035       0  5716.3     .05       0  5929.4    .035       0
  5946.4     .05       0
Bank Sta=4991.6,5004.1
XS Rating Curve= 0 ,0
Exp/Cntr=0.3,0.1

Type RM Length L Ch R = 1 ,4197    ,466,466,466
BEGIN DESCRIPTION:
Turkey Creek 3 4.0
END DESCRIPTION:
XS GIS Cut Line= 3
        2528575.     13686625.03        2528625.       13687025.
        2528975.       13687825.
#Sta/Elev= 30
  4596.9  287.37  4627.1  286.47  4657.3  283.64  4687.6  283.03  4715.3  280.75
  4778.3  277.97  4969.8  273.61  4989.9  269.03  4991.2  266.39  4991.7  265.89
  5003.7  266.39    5009  269.49  5014.4  269.65  5021.8  272.32  5032.3  273.71
  5066.6  274.53  5084.6  272.54  5098.2  272.37  5113.4  272.93  5120.1  274.21
  5142.3  274.29  5415.9  273.24  5523.9  271.42  5538.3  272.06  5556.3  275.16
    5614  276.09    5775  283.84  5788.6  283.59  5858.8  287.69  5873.2  287.47
#Mann= 3 ,-1 , 0
  4596.9     .05       0  4991.2     .05       0  5003.7     .05       0
Bank Sta=4991.2,5003.7
XS Rating Curve= 0 ,0
Exp/Cntr=0.3,0.1

Type RM Length L Ch R = 1 ,3731    ,740,740,740
BEGIN DESCRIPTION:
Turkey Creek 3 3.0
END DESCRIPTION:
XS GIS Cut Line= 3
        2528125.     13686674.98        2528175.       13687075.
      2528824.99     13687874.99
#Sta/Elev= 30
  4601.2  284.88  4631.5  284.83  4661.7  281.02  4691.9  280.51  4719.6  277.29
  4752.4  276.91  4800.3  273.23  4953.9  272.24  4977.9  265.12  4978.4  264.62
  4990.4  265.12  4994.3  269.95  5011.5  271.73  5182.5  272.14  5203.3  269.43
  5224.1  272.04  5252.9  272.29  5416.6   270.3  5530.9  272.12  5558.4  271.64
  5700.4  275.16  5729.1  277.41    5793  278.89    5829   282.8  5871.3  282.64
  5932.4  285.43  5945.8  285.57  5984.8   287.4  5992.7   288.8  6035.1  289.03
#Mann= 5 ,-1 , 0
  4601.2     .05       0  4977.9     .05       0  4990.4     .05       0
  5932.4    .035       0  5945.8     .05       0
Bank Sta=4977.9,4990.4
XS Rating Curve= 0 ,0
Exp/Cntr=0.3,0.1

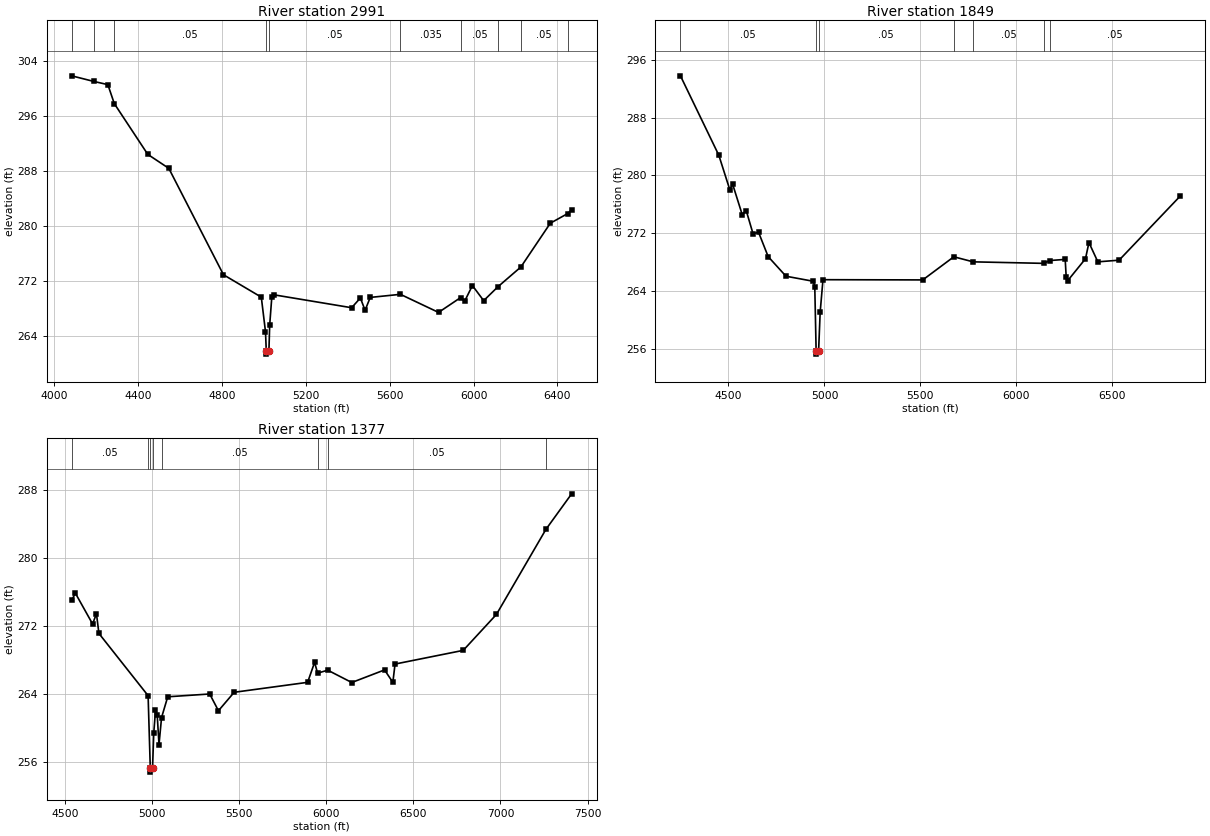
Type RM Length L Ch R = 1 ,2991    ,1142,1142,1142
BEGIN DESCRIPTION:
H21506
END DESCRIPTION:
XS GIS Cut Line= 4
      2527524.71     13686062.81      2527459.28     13687109.68
      2527694.82     13687404.11      2528584.67     13687757.43
#Sta/Elev= 30
  4084.1  301.91  4188.8   301.1  4256.6  300.63  4287.3  297.87    4447  290.48
  4547.2  288.45  4807.7  272.97  4988.1  269.71  5008.1  264.67  5011.8  261.92
  5012.3  261.42  5024.4  261.92  5028.1  265.65  5038.2  269.74  5048.2  270.05
  5418.7  268.17  5460.4  269.59  5482.8   267.8  5507.4  269.67  5651.2  270.12
    5833  267.49  5938.4  269.65  5958.2  269.16  5994.4   271.4  6048.2   269.2
  6116.4  271.23  6225.6   274.1  6365.9  280.47  6448.1  281.86  6467.5  282.42
#Mann= 10 ,-1 , 0
  4084.1     .12       0  4188.8    .035       0  4287.3     .05       0
  5011.8     .05       0  5024.4     .05       0  5651.2    .035       0
  5938.4     .05       0  6116.4    .035       0  6225.6     .05       0
  6448.1    .035       0
Bank Sta=5011.8,5024.4
XS Rating Curve= 0 ,0
Exp/Cntr=0.3,0.1

Type RM Length L Ch R = 1 ,1849    ,472,472,472
BEGIN DESCRIPTION:
Turkey Creek 3 2.0
END DESCRIPTION:
XS GIS Cut Line= 3
      2526175.03     13686675.04        2526625.       13687275.
      2528424.95     13687724.99
#Sta/Elev= 30
  4249.6  293.78  4449.6  282.79  4506.8  278.02  4521.4   278.8  4571.4  274.58
  4592.3  275.14  4627.7  271.94  4656.8  272.12  4706.8  268.76  4799.6  266.05
  4942.3  265.35  4949.6  264.61  4956.6  255.77  4957.1  255.27  4969.6  255.77
  4977.7  261.08  4992.3  265.57  5512.4  265.54  5674.2  268.74  5774.9  268.04
  6141.9  267.83  6174.3  268.22  6254.5  268.38  6259.7  265.94  6267.4  265.43
  6360.2  268.47  6378.2  270.71  6424.6  268.04  6535.4  268.27  6854.9  277.17
#Mann= 7 ,-1 , 0
  4249.6     .05       0  4956.6     .05       0  4969.6     .05       0
  5674.2    .035       0  5774.9     .05       0  6141.9    .035       0
  6174.3     .05       0
Bank Sta=4956.6,4969.6
XS Rating Curve= 0 ,0
Exp/Cntr=0.3,0.1

Type RM Length L Ch R = 1 ,1377    ,0,0,0
BEGIN DESCRIPTION:
Turkey Creek 3 1.0
END DESCRIPTION:
XS GIS Cut Line= 3
      2525974.97     13687324.97        2526325.       13687625.
      2528724.96       13687825.
#Sta/Elev= 30
    4539  275.07  4560.4   275.9  4659.2  272.28  4681.2   273.5  4695.4  271.17
  4977.7  263.85  4990.2  255.36  4990.7  254.86  5003.2  255.36  5010.1  259.45
  5020.1  262.11  5030.1  261.53  5040.2   258.1  5054.9  261.28  5090.3  263.72
  5331.2  264.05  5381.3  262.08  5471.6  264.25  5893.1  265.42  5933.2  267.77
  5950.3   266.5  6008.6  266.85  6146.5   265.4  6334.6  266.88  6382.3  265.42
  6394.8  267.57  6786.2  269.18  6976.8  273.41    7261  283.42  7408.3  287.59
#Mann= 8 ,-1 , 0
    4539     .05       0  4977.7     .12       0  4990.2     .05       0
  5003.2     .12       0  5054.9     .05       0  5950.3    .035       0
  6008.6     .05       0    7261    .035       0
Bank Sta=4990.2,5003.2
XS Rating Curve= 0 ,0
Exp/Cntr=0.3,0.1

Chan Stop Cuts=-1
Use User Specified Reach Order=0
Composite Channel Slope=5