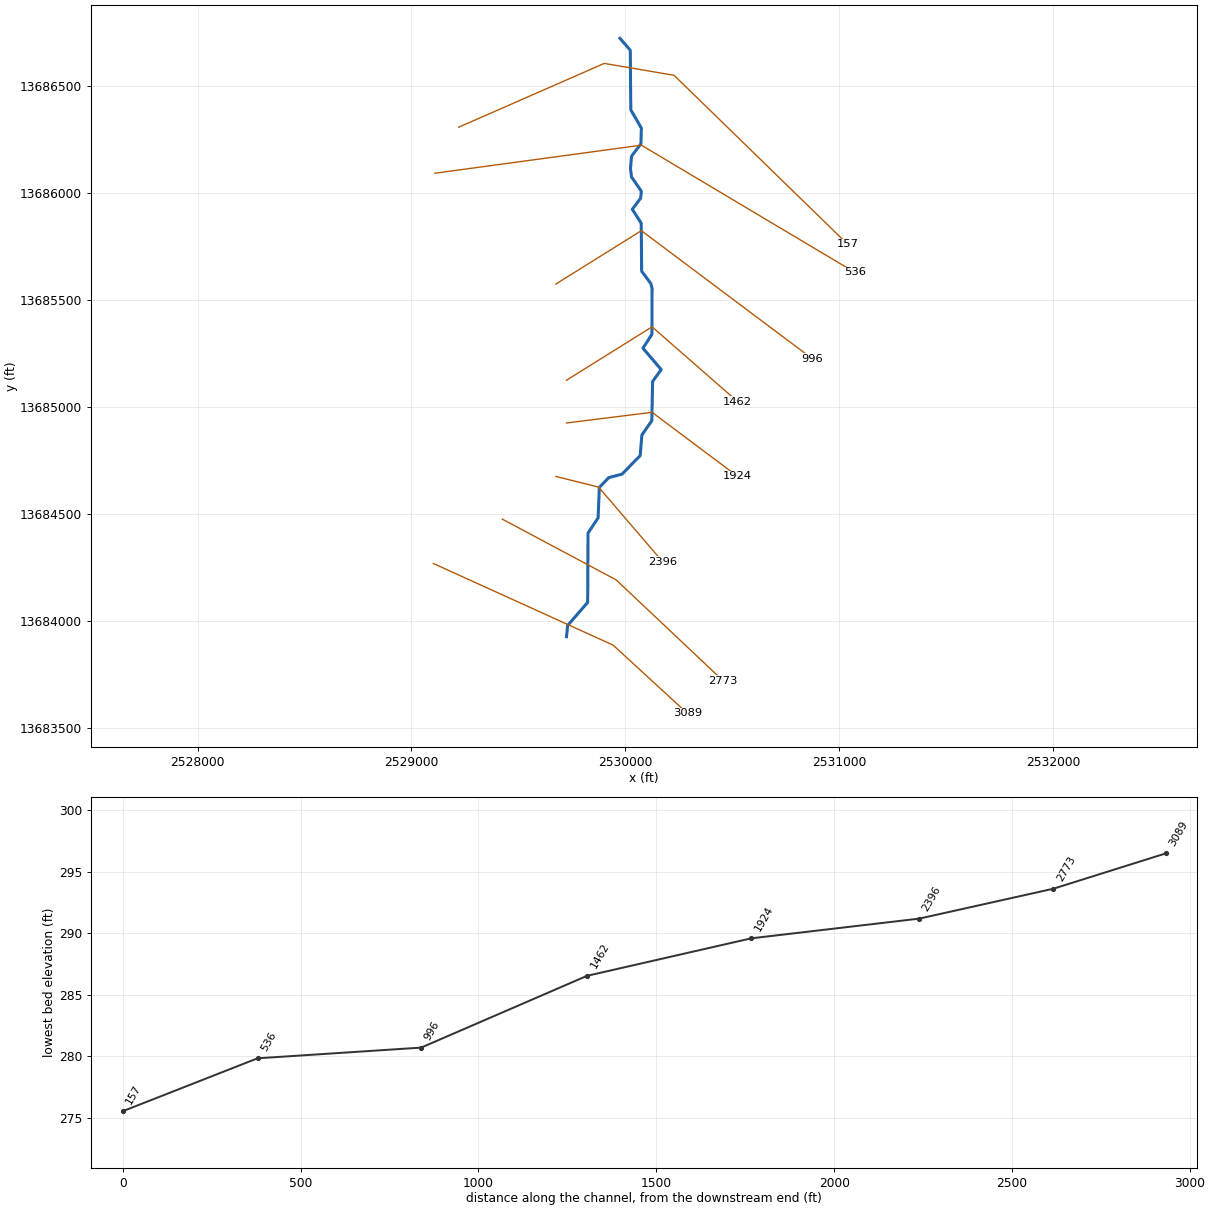
--- Turkey Creek 5.prj (project) ---

Proj Title=Turkey Creek 5 Base Level Engineering
Current Plan=p01
Default Exp/Contr=0.3,0.1
English Units
Geom File=g01
Flow File=f01
Plan File=p01
BEGIN DESCRIPTION:
Turkey Creek 5
END DESCRIPTION:

--- Turkey Creek 5.p01 (plan) ---

Plan Title=Multiple Run
Short Identifier=Multiple
Geom File=g01
Flow File=f01
Subcritical Flow
K Sum by GR= 0
Std Step Tol= 0.01
Critical Tol= 0.01
Num of Std Step Trials= 20
Max Error Tol= 0.3
Flow Tol Ratio= 0.001
Split Flow NTrial= 30
Split Flow Tol= 0.02
Split Flow Ratio= 0.02
Log Output Level= 0
Friction Slope Method= 1
Unsteady Friction Slope Method= 2
Unsteady Bridges Friction Slope Method= 1
Parabolic Critical Depth
Global Vel Dist=  1 , 1 , 1
Global Log Level= 0
CheckData=True
Encroach Param= -1, 0, 0, 0
BEGIN DESCRIPTION:
Multiple Run
END DESCRIPTION:

--- Turkey Creek 5.f01 (steady flow) ---

Flow Title=Multiple
Number of Profiles=7
Profile Names=10-year,25-year,50-year,1pct_min,100-year,1pct_plu,500-year
River Rch & RM= Turkey Creek 5,Reach-1,3089
     993    1645    2252    1493    2978    5943    5158
Boundary for River Rch & Prof#=Turkey Creek 5,Reach-1,1
Up Type=0
Dn Type=3
Dn Slope=0.005
Boundary for River Rch & Prof#=Turkey Creek 5,Reach-1,2
Up Type=0
Dn Type=3
Dn Slope=0.005
Boundary for River Rch & Prof#=Turkey Creek 5,Reach-1,3
Up Type=0
Dn Type=3
Dn Slope=0.005
Boundary for River Rch & Prof#=Turkey Creek 5,Reach-1,4
Up Type=0
Dn Type=3
Dn Slope=0.005
Boundary for River Rch & Prof#=Turkey Creek 5,Reach-1,5
Up Type=0
Dn Type=3
Dn Slope=0.005
Boundary for River Rch & Prof#=Turkey Creek 5,Reach-1,6
Up Type=0
Dn Type=3
Dn Slope=0.005
Boundary for River Rch & Prof#=Turkey Creek 5,Reach-1,7
Up Type=0
Dn Type=3
Dn Slope=0.005

--- Turkey Creek 5.g01 (geometry) ---

Geom Title=Existing Conditions

River Reach=Turkey Creek 5,Reach-1
Reach XY= 30
      2529725.00     13683925.00      2529730.33     13683977.51
      2529823.95     13684085.43      2529825.52     13684409.78
      2529872.73     13684480.94      2529878.45     13684623.75
      2529922.43     13684669.26      2529984.68     13684685.78
      2530069.48     13684772.56      2530077.36     13684869.02
      2530123.78     13684935.50      2530127.47     13685119.15
      2530167.66     13685175.10      2530082.34     13685274.90
      2530124.34     13685340.16      2530124.93     13685554.97
      2530119.25     13685577.33      2530076.22     13685635.50
      2530074.34     13685859.84      2530032.59     13685925.01
      2530071.39     13685976.64      2530074.85     13686009.58
      2530028.73     13686076.58      2530024.23     13686114.95
      2530028.71     13686173.40      2530072.83     13686230.97
      2530075.09     13686304.90      2530025.52     13686390.22
      2530023.11     13686669.22      2529975.00     13686725.00

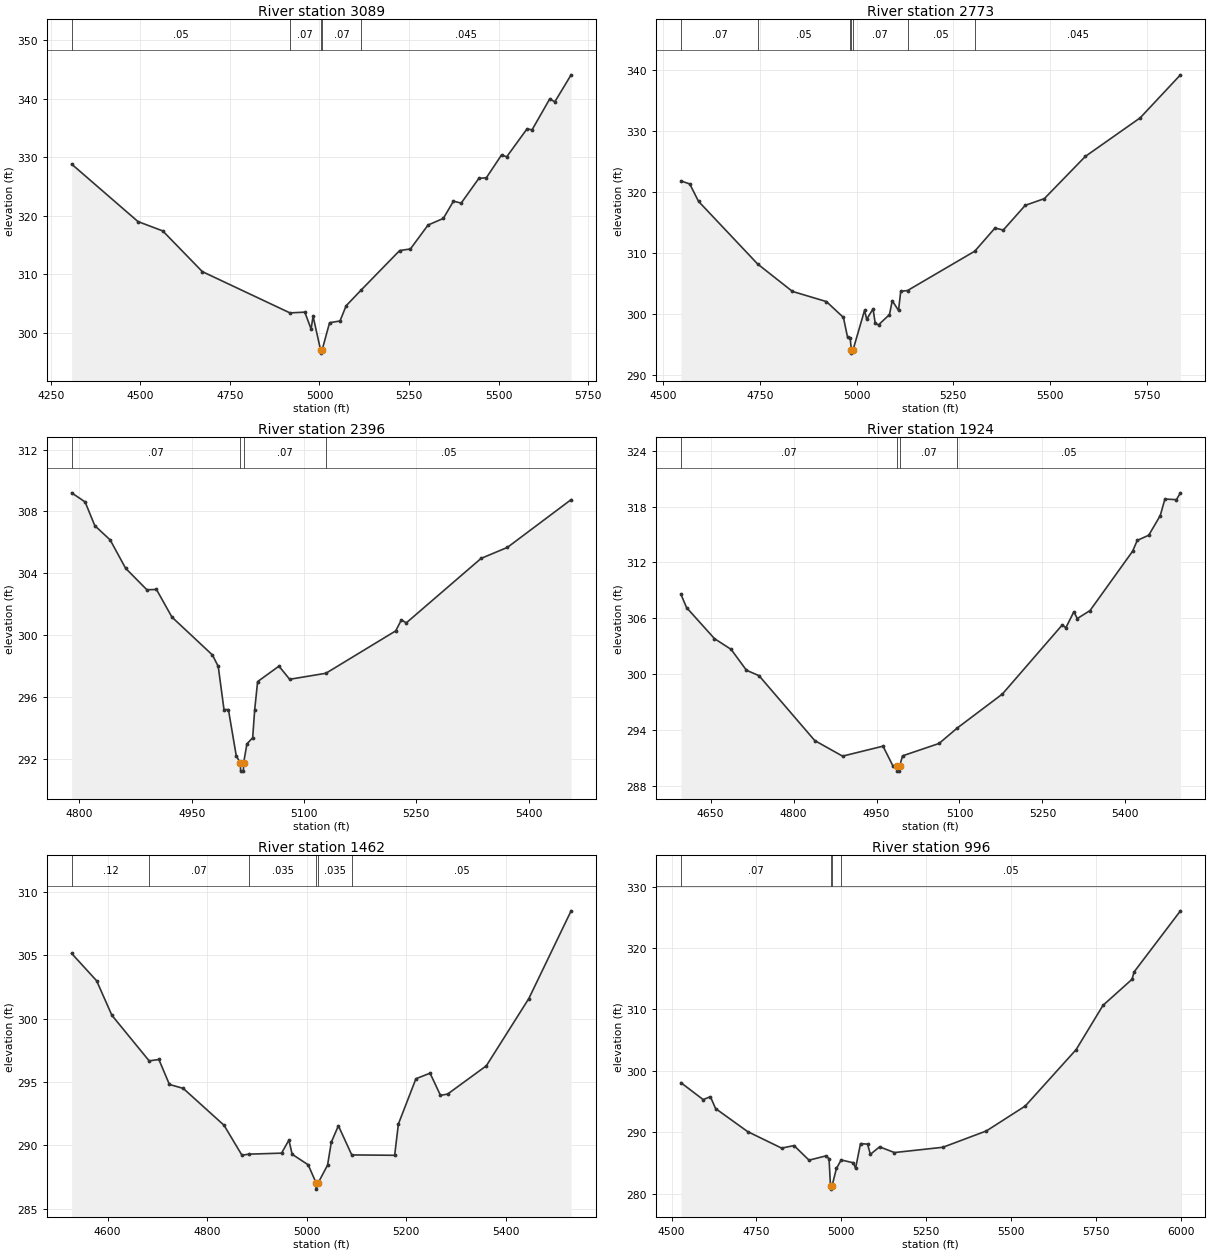
Type RM Length L Ch R = 1,3089,316,316,316
BEGIN DESCRIPTION:
XS7877
END DESCRIPTION:
XS GIS Cut Line= 3
      2529102.80     13684267.35      2529943.06     13683885.42
      2530290.13     13683566.11
#Sta/Elev= 30
  4308.1  328.83  4493.4  319.00  4562.6  317.40  4673.0  310.44  4917.7  303.38
  4959.1  303.51  4976.7  300.63  4982.2  302.82  5003.3  297.00  5003.5  296.50
  5007.3  297.00  5028.3  301.70  5057.5  302.00  5074.5  304.60  5116.3  307.28
  5223.9  314.04  5254.0  314.32  5303.3  318.41  5345.9  319.54  5374.2  322.49
  5395.8  322.16  5445.1  326.39  5466.1  326.50  5508.6  330.41  5522.8  330.07
  5579.5  334.85  5593.7  334.70  5643.0  339.98  5657.2  339.48  5702.7  344.10
#Mann=5,-1,0
  4308.1    0.05       0  4917.7    0.07       0  5003.3    0.05       0
  5007.3    0.07       0  5116.3   0.045       0
Bank Sta=5003.3,5007.3
Exp/Cntr=0.3,0.1

Type RM Length L Ch R = 1,2773,377,377,377
BEGIN DESCRIPTION:
Turkey Creek 5 6.0
END DESCRIPTION:
XS GIS Cut Line= 3
      2529425.04     13684474.98      2529956.94     13684190.97
      2530456.27     13683719.39
#Sta/Elev= 30
  4546.6  321.86  4569.2  321.37  4591.9  318.52  4744.8  308.23  4834.4  303.75
  4922.2  302.08  4966.1  299.48  4976.7  296.27  4983.6  296.05  4986.6  294.13
  4986.8  293.63  4990.8  294.13  5020.6  300.63  5026.3  299.19  5042.6  300.88
  5048.3  298.50  5056.7  298.26  5085.0  299.95  5092.2  302.22  5108.4  300.63
  5114.1  303.77  5131.6  303.89  5305.4  310.35  5357.5  314.14  5378.9  313.81
  5435.6  317.86  5484.9  318.96  5590.9  325.89  5732.5  332.21  5836.4  339.26
#Mann=7,-1,0
  4546.6    0.07       0  4744.8    0.05       0  4983.6    0.07       0
  4986.6    0.05       0  4990.8    0.07       0  5131.6    0.05       0
  5305.4   0.045       0
Bank Sta=4986.6,4990.8
Exp/Cntr=0.3,0.1

Type RM Length L Ch R = 1,2396,472,472,472
BEGIN DESCRIPTION:
Turkey Creek 5 5.0
END DESCRIPTION:
XS GIS Cut Line= 3
      2529675.04     13684674.99      2529875.00     13684625.00
      2530175.01     13684274.99
#Sta/Elev= 30
  4789.6  309.20  4807.6  308.61  4820.5  307.08  4841.1  306.15  4861.7  304.32
  4890.1  302.93  4902.9  302.95  4923.6  301.16  4977.7  298.71  4985.4  297.97
  4993.1  295.18  4999.0  295.18  5009.4  292.21  5015.0  291.70  5015.3  291.20
  5019.0  291.20  5019.2  291.70  5023.7  292.96  5031.4  293.36  5034.1  295.18
  5038.0  296.99  5066.5  297.99  5080.8  297.14  5129.2  297.53  5222.4  300.27
  5230.0  300.98  5236.6  300.79  5336.5  304.96  5371.6  305.67  5456.7  308.76
#Mann=4,-1,0
  4789.6    0.07       0  5015.0    0.05       0  5019.2    0.07       0
  5129.2    0.05       0
Bank Sta=5015,5019.2
Exp/Cntr=0.3,0.1

Type RM Length L Ch R = 1,1924,462,462,462
BEGIN DESCRIPTION:
Turkey Creek 5 4.0
END DESCRIPTION:
XS GIS Cut Line= 3
      2529725.01     13684925.00      2530125.00     13684975.00
      2530525.00     13684675.00
#Sta/Elev= 30
  4596.4  308.58  4606.5  307.16  4656.9  303.83  4687.1  302.67  4714.8  300.43
  4737.5  299.85  4838.3  292.88  4888.6  291.21  4961.7  292.28  4979.3  290.20
  4987.3  290.10  4987.6  289.60  4991.3  289.60  4991.6  290.10  4997.0  291.24
  5063.0  292.57  5096.2  294.24  5177.6  297.88  5286.0  305.31  5292.2  304.98
  5306.8  306.71  5313.0  305.98  5336.0  306.84  5413.0  313.21  5421.4  314.37
  5442.2  314.93  5463.0  317.04  5471.4  318.81  5492.2  318.75  5499.5  319.48
#Mann=4,-1,0
  4596.4    0.07       0  4987.3    0.05       0  4991.6    0.07       0
  5096.2    0.05       0
Bank Sta=4987.3,4991.6
Exp/Cntr=0.3,0.1

Type RM Length L Ch R = 1,1462,466,466,466
BEGIN DESCRIPTION:
Turkey Creek 5 3.0
END DESCRIPTION:
XS GIS Cut Line= 3
      2529724.96     13685124.98      2530125.00     13685375.00
      2530524.96     13685025.03
#Sta/Elev= 30
  4527.8  305.15  4578.0  302.99  4608.6  300.27  4683.5  296.67  4703.0  296.78
  4724.2  294.81  4751.9  294.50  4833.9  291.59  4869.8  289.23  4884.4  289.31
  4949.4  289.39  4964.2  290.42  4970.7  289.30  5002.9  288.47  5018.7  287.05
  5019.0  286.55  5023.0  287.05  5041.8  288.44  5049.4  290.26  5063.6  291.55
  5090.4  289.25  5176.6  289.22  5184.1  291.69  5219.3  295.26  5247.7  295.70
  5268.6  293.95  5282.9  294.05  5360.7  296.28  5446.1  301.59  5531.0  308.51
#Mann=6,-1,0
  4527.8    0.12       0  4683.5    0.07       0  4884.4   0.035       0
  5018.7   0.035       0  5023.0   0.035       0  5090.4    0.05       0
Bank Sta=5018.7,5023
Exp/Cntr=0.3,0.1

Type RM Length L Ch R = 1,996,460,460,460
BEGIN DESCRIPTION:
Turkey Creek 5 2.0
END DESCRIPTION:
XS GIS Cut Line= 3
      2529675.02     13685575.01      2530075.00     13685825.00
      2530875.02     13685224.98
#Sta/Elev= 30
  4527.9  298.06  4593.3  295.31  4614.6  295.78  4629.9  293.85  4724.2  290.10
  4824.5  287.40  4861.0  287.82  4905.2  285.44  4955.4  286.14  4964.2  285.66
  4968.5  281.22  4968.8  280.72  4972.9  281.22  4986.0  284.10  5000.0  285.47
  5036.0  285.01  5042.3  284.09  5056.9  288.14  5077.7  288.05  5086.0  286.39
  5113.1  287.61  5156.9  286.68  5299.6  287.54  5427.7  290.20  5542.3  294.26
  5692.3  303.46  5771.4  310.67  5856.9  314.91  5863.1  316.12  5999.6  326.07
#Mann=4,-1,0
  4527.9    0.07       0  4968.5    0.05       0  4972.9    0.07       0
  5000.0    0.05       0
Bank Sta=4968.5,4972.9
Exp/Cntr=0.3,0.1

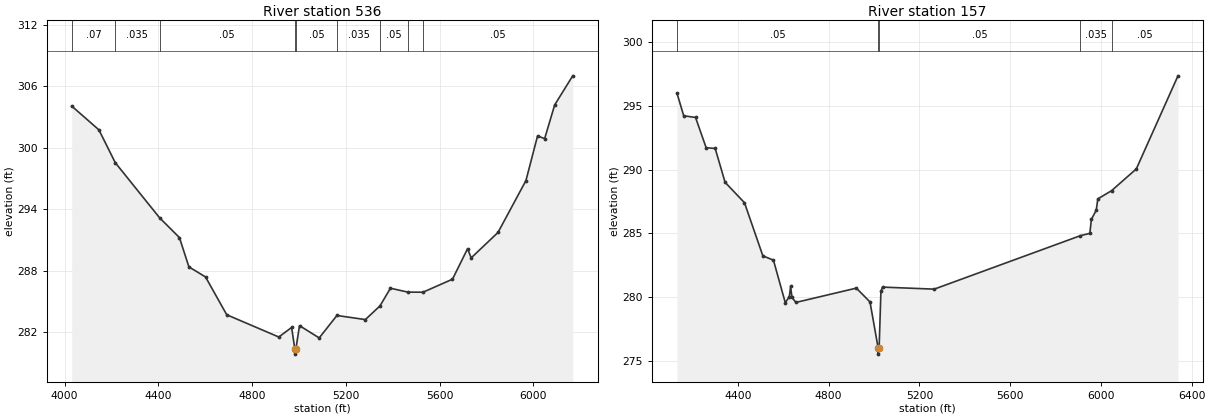
Type RM Length L Ch R = 1,536,379,379,379
BEGIN DESCRIPTION:
Turkey Creek 5 1.0
END DESCRIPTION:
XS GIS Cut Line= 3
      2529109.69     13686093.75      2530075.00     13686225.00
      2531073.71     13685629.24
#Sta/Elev= 30
  4030.7  304.05  4146.7  301.73  4216.4  298.53  4405.6  293.15  4490.2  291.22
  4530.6  288.36  4601.5  287.38  4692.0  283.69  4914.1  281.52  4968.7  282.45
  4982.5  280.35  4982.8  279.85  4986.9  280.35  5002.4  282.63  5086.4  281.43
  5162.0  283.62  5283.2  283.22  5345.6  284.55  5390.3  286.28  5464.5  285.90
  5529.2  285.89  5655.0  287.16  5719.2  290.13  5734.8  289.24  5849.1  291.72
  5968.3  296.78  6017.9  301.14  6048.1  300.87  6090.9  304.16  6167.8  307.00
#Mann=9,-1,0
  4030.7    0.07       0  4216.4   0.035       0  4405.6    0.05       0
  4982.5    0.05       0  4986.9    0.05       0  5162.0   0.035       0
  5345.6    0.05       0  5464.5   0.035       0  5529.2    0.05       0
Bank Sta=4982.5,4986.9
Exp/Cntr=0.3,0.1

Type RM Length L Ch R = 1,157,0,0,0
BEGIN DESCRIPTION:
XS7876
END DESCRIPTION:
XS GIS Cut Line= 4
      2529220.84     13686309.03      2529901.39     13686607.64
      2530227.78     13686552.08      2531040.15     13685760.54
#Sta/Elev= 30
  4131.3  295.99  4160.9  294.22  4213.1  294.09  4259.8  291.72  4299.7  291.66
  4343.3  289.01  4428.8  287.41  4509.8  283.25  4556.5  282.91  4608.7  279.58
  4626.6  280.05  4632.1  280.85  4638.2  279.99  4655.5  279.60  4921.9  280.72
  4982.1  279.64  5017.9  276.05  5018.3  275.55  5022.4  276.05  5030.3  280.46
  5037.3  280.80  5265.2  280.64  5909.7  284.83  5951.2  285.01  5958.1  286.11
  5979.5  286.82  5986.4  287.71  6046.8  288.35  6156.2  290.06  6339.8  297.35
#Mann=5,-1,0
  4131.3    0.05       0  5017.9    0.05       0  5022.4    0.05       0
  5909.7   0.035       0  6046.8    0.05       0
Bank Sta=5017.9,5022.4
Exp/Cntr=0.3,0.1

Chan Stop Cuts=-1