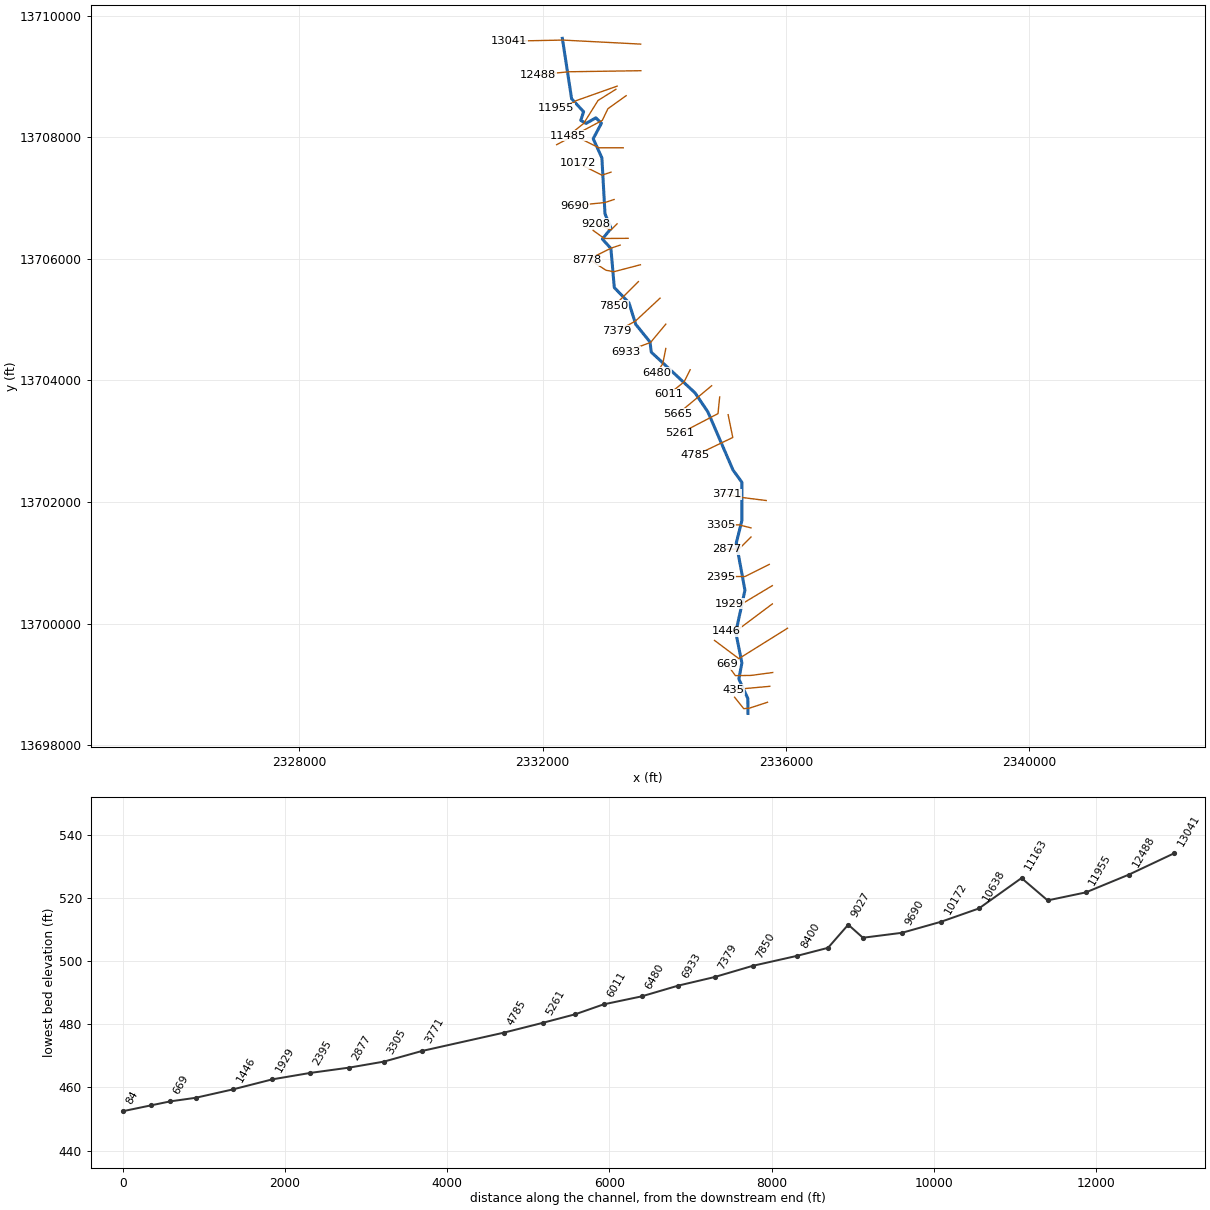
--- BEAR HOLLOW CREEK.prj (project) ---

Proj Title=BEAR HOLLOW CREEK Base Level Engineering
Current Plan=p01
Default Exp/Contr=0.3,0.1
English Units
Geom File=g01
Flow File=f01
Plan File=p01
Y Axis Title=Elevation
X Axis Title(PF)=Main Channel Distance
X Axis Title(XS)=Station
BEGIN DESCRIPTION:
BEAR HOLLOW CREEK
END DESCRIPTION:
DSS Export Rating Curves= 0
DSS Export Rating Curve Sorted= 0
DSS Export Volume Flow Curves= 0
DXF OffsetX= 0
DXF OffsetY= 0
DXF ScaleX= 1
DXF ScaleY= 10

--- BEAR HOLLOW CREEK.p01 (plan) ---

Plan Title=Multiple Run
Short Identifier=Multiple
Geom File=g01
Flow File=f01
Subcritical Flow
K Sum by GR= 0
Std Step Tol= 0.01
Critical Tol= 0.01
Num of Std Step Trials= 20
Max Error Tol= 0.3
Flow Tol Ratio= 0.001
Split Flow NTrial= 30
Split Flow Tol= 0.02
Split Flow Ratio= 0.02
Log Output Level= 0
Friction Slope Method= 1
Unsteady Friction Slope Method= 2
Unsteady Bridges Friction Slope Method= 1
Parabolic Critical Depth
Global Vel Dist=  1 , 1 , 1
Global Log Level= 0
CheckData=True
Encroach Param= -1, 0, 0, 0
BEGIN DESCRIPTION:
Multiple Run
END DESCRIPTION:

--- BEAR HOLLOW CREEK.f01 (steady flow) ---

Flow Title=Multiple
Number of Profiles=7
Profile Names=10-year,25-year,50-year,1pct_min,100-year,1pct_plu,500-year
River Rch & RM= BEAR HOLLOW CREE,Reach-1,13041
     912    1523    2094    1395    2783    5553    4871
River Rch & RM= BEAR HOLLOW CREE,Reach-1,11485
    1423    2425    3378    2273    4536    9050    8116
River Rch & RM= BEAR HOLLOW CREE,Reach-1,7850
    1642    2812    3929    2651    5290   10556    9518
River Rch & RM= BEAR HOLLOW CREE,Reach-1,3771
    1788    3070    4298    2904    5795   11563   10457
Boundary for River Rch & Prof#=BEAR HOLLOW CREE,Reach-1,1
Up Type=0
Dn Type=3
Dn Slope=0.005
Boundary for River Rch & Prof#=BEAR HOLLOW CREE,Reach-1,2
Up Type=0
Dn Type=3
Dn Slope=0.005
Boundary for River Rch & Prof#=BEAR HOLLOW CREE,Reach-1,3
Up Type=0
Dn Type=3
Dn Slope=0.005
Boundary for River Rch & Prof#=BEAR HOLLOW CREE,Reach-1,4
Up Type=0
Dn Type=3
Dn Slope=0.005
Boundary for River Rch & Prof#=BEAR HOLLOW CREE,Reach-1,5
Up Type=0
Dn Type=3
Dn Slope=0.005
Boundary for River Rch & Prof#=BEAR HOLLOW CREE,Reach-1,6
Up Type=0
Dn Type=3
Dn Slope=0.005
Boundary for River Rch & Prof#=BEAR HOLLOW CREE,Reach-1,7
Up Type=0
Dn Type=3
Dn Slope=0.005

--- BEAR HOLLOW CREEK.g01 (geometry) ---

Geom Title=Existing Conditions

River Reach=BEAR HOLLOW CREE,Reach-1
Reach XY= 30
      2332325.00     13709625.00      2332477.24     13708630.93
      2332673.72     13708418.96      2332628.04     13708276.36
      2332714.24     13708225.68      2332875.11     13708317.71
      2332967.21     13708228.45      2332832.10     13707975.00
      2332974.48     13707659.78      2333025.52     13706740.22
      2333125.50     13706499.96      2332982.01     13706324.80
      2333122.77     13706169.10      2333178.49     13705526.27
      2333419.15     13705277.29      2333530.47     13704922.55
      2333765.69     13704631.66      2333785.75     13704465.32
      2334505.22     13703795.09      2334716.86     13703481.06
      2335128.82     13702526.58      2335275.00     13702325.00
      2335274.93     13701695.03      2335182.56     13701325.00
      2335325.20     13700549.92      2335174.61     13699854.87
      2335274.95     13699354.96      2335225.38     13699090.27
      2335372.76     13698769.07      2335375.00     13698525.00

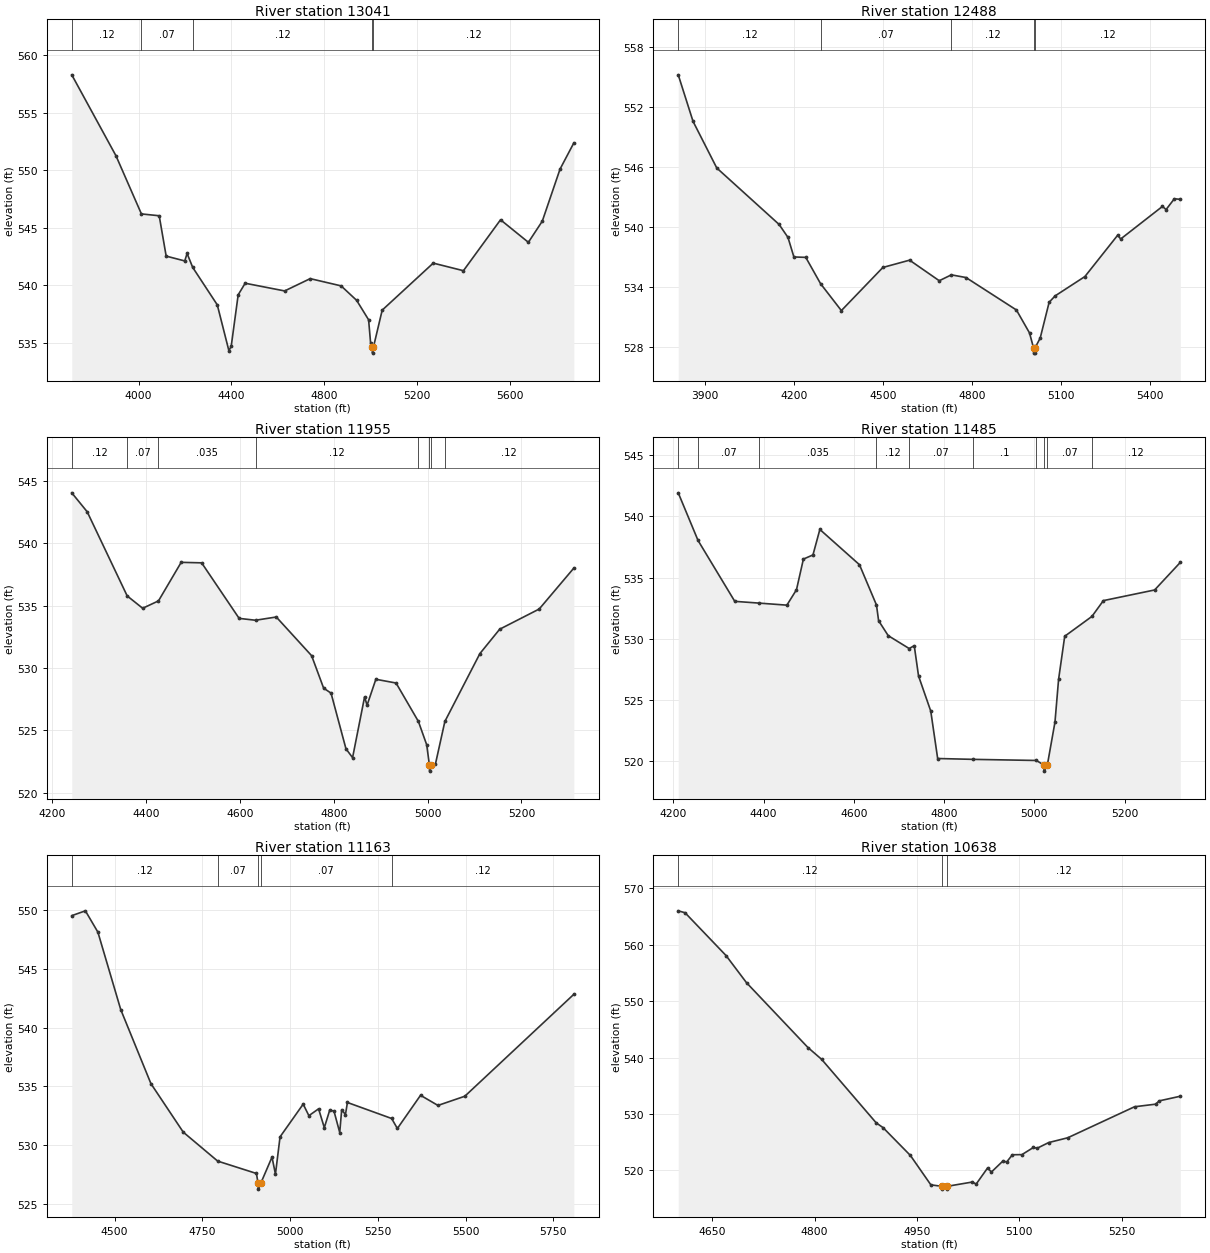
Type RM Length L Ch R = 1,13041,553,553,553
BEGIN DESCRIPTION:
X18170
END DESCRIPTION:
XS GIS Cut Line= 3
      2333611.39     13709530.23      2332333.57     13709596.21
      2331449.06     13709578.86
#Sta/Elev= 30
  3711.9  558.30  3902.4  551.26  4012.1  546.20  4088.8  546.04  4118.8  542.53
  4198.9  542.11  4209.0  542.76  4233.1  541.55  4339.1  538.29  4389.2  534.30
  4399.2  534.69  4429.2  539.16  4459.3  540.17  4629.5  539.50  4739.7  540.57
  4872.9  539.94  4939.9  538.68  4991.4  536.99  5000.0  534.97  5007.9  534.59
  5008.2  534.09  5012.0  534.59  5050.0  537.83  5270.0  541.92  5400.1  541.26
  5560.1  545.69  5680.1  543.73  5740.1  545.57  5816.6  550.10  5876.1  552.38
#Mann=5,-1,0
  3711.9    0.12       0  4012.1    0.07       0  4233.1    0.12       0
  5007.9    0.05       0  5012.0    0.12       0
Bank Sta=5007.9,5012
Exp/Cntr=0.3,0.1

Type RM Length L Ch R = 1,12488,533,533,533
BEGIN DESCRIPTION:
BEAR HOLLOW CREEK 22.0
END DESCRIPTION:
XS GIS Cut Line= 3
      2333614.85     13709092.73      2332430.79     13709075.37
      2331924.98     13709025.00
#Sta/Elev= 30
  3810.4  555.26  3860.3  550.60  3940.3  545.93  4150.3  540.28  4180.3  538.98
  4200.3  537.02  4240.3  536.98  4290.3  534.34  4360.3  531.65  4500.3  535.97
  4590.3  536.70  4690.3  534.64  4731.1  535.23  4780.4  534.96  4950.4  531.71
  4994.6  529.41  5008.3  527.89  5008.6  527.39  5012.4  527.39  5012.7  527.89
  5030.6  528.90  5060.7  532.48  5080.8  533.12  5181.3  535.06  5291.8  539.20
  5301.9  538.82  5442.6  542.08  5455.0  541.77  5482.8  542.85  5502.9  542.79
#Mann=5,-1,0
  3810.4    0.12       0  4290.3    0.07       0  4731.1    0.12       0
  5008.3    0.05       0  5012.7    0.12       0
Bank Sta=5008.3,5012.7
Exp/Cntr=0.3,0.1

Type RM Length L Ch R = 1,11955,470,470,470
BEGIN DESCRIPTION:
BEAR HOLLOW CREEK 21.0
END DESCRIPTION:
XS GIS Cut Line= 4
      2333225.90     13708839.25      2332538.92     13708595.88
      2332525.00     13708575.00      2332225.03     13708475.01
#Sta/Elev= 30
  4241.5  544.04  4274.4  542.52  4359.6  535.78  4392.6  534.79  4426.3  535.38
  4474.7  538.47  4518.3  538.43  4598.2  533.98  4633.1  533.83  4677.4  534.09
  4752.7  530.99  4778.3  528.39  4794.1  527.99  4825.9  523.53  4840.0  522.82
  4865.6  527.69  4870.9  527.02  4889.6  529.10  4932.7  528.80  4980.3  525.72
  4998.0  523.85  5003.7  522.24  5004.0  521.74  5008.1  522.24  5016.5  522.29
  5036.7  525.72  5111.4  531.16  5153.5  533.11  5237.8  534.73  5311.6  538.01
#Mann=8,-1,0
  4241.5    0.12       0  4359.6    0.07       0  4426.3   0.035       0
  4633.1    0.12       0  4980.3     0.1       0  5003.7    0.05       0
  5008.1     0.1       0  5036.7    0.12       0
Bank Sta=5003.7,5008.1
Exp/Cntr=0.3,0.1

Type RM Length L Ch R = 1,11485,322,322,322
BEGIN DESCRIPTION:
BEAR HOLLOW CREEK 20.0
END DESCRIPTION:
XS GIS Cut Line= 4
      2333205.09     13708787.18      2332911.54     13708603.46
      2332675.00     13708225.00      2332424.97     13708024.97
#Sta/Elev= 30
  4210.8  541.93  4254.7  538.04  4336.1  533.07  4388.9  532.93  4451.6  532.76
  4472.9  534.02  4488.2  536.52  4509.4  536.86  4524.7  538.94  4612.5  536.06
  4650.2  532.77  4654.9  531.49  4676.2  530.27  4722.6  529.22  4733.9  529.45
  4743.4  526.98  4770.5  524.11  4785.8  520.24  4865.0  520.17  5004.5  520.08
  5021.2  519.71  5021.7  519.21  5028.9  519.71  5045.8  523.21  5053.8  526.70
  5067.4  530.22  5127.7  531.84  5153.1  533.13  5266.7  534.00  5323.6  536.25
#Mann=10,-1,0
  4210.8    0.12       0  4254.7    0.07       0  4388.9   0.035       0
  4650.2    0.12       0  4722.6    0.07       0  4865.0     0.1       0
  5004.5    0.07       0  5021.2    0.05       0  5028.9    0.07       0
  5127.7    0.12       0
Bank Sta=5021.2,5028.9
Exp/Cntr=0.3,0.1

Type RM Length L Ch R = 1,11163,525,525,525
BEGIN DESCRIPTION:
BEAR HOLLOW CREEK 19.0
END DESCRIPTION:
XS GIS Cut Line= 4
      2333372.57     13708681.81      2333073.69     13708467.65
      2332981.48     13708276.19      2332231.48     13707876.19
#Sta/Elev= 30
  4378.0  549.51  4416.8  549.92  4452.4  548.11  4517.5  541.53  4603.5  535.24
  4695.6  531.12  4793.7  528.66  4904.0  527.61  4908.7  526.78  4909.2  526.28
  4916.4  526.78  4948.4  529.00  4958.2  527.55  4971.3  530.72  5037.2  533.50
  5053.4  532.52  5081.1  533.10  5097.4  531.50  5112.9  533.00  5125.0  532.90
  5141.3  531.09  5146.9  533.03  5157.6  532.61  5163.2  533.64  5289.2  532.28
  5305.5  531.43  5371.5  534.25  5421.1  533.39  5497.6  534.17  5808.2  542.83
#Mann=5,-1,0
  4378.0    0.12       0  4793.7    0.07       0  4908.7    0.05       0
  4916.4    0.07       0  5289.2    0.12       0
Bank Sta=4908.7,4916.4
Exp/Cntr=0.3,0.1

Type RM Length L Ch R = 1,10638,466,466,466
BEGIN DESCRIPTION:
BEAR HOLLOW CREEK 18.0
END DESCRIPTION:
XS GIS Cut Line= 3
      2333325.02     13707825.00      2332925.00     13707825.00
      2332625.02     13707974.99
#Sta/Elev= 30
  4600.3  566.03  4610.3  565.69  4670.3  558.10  4700.3  553.28  4790.3  541.78
  4810.3  539.69  4890.3  528.41  4900.3  527.57  4940.3  522.64  4970.3  517.42
  4986.4  517.16  4986.9  516.66  4993.7  516.66  4994.2  517.16  5031.1  517.92
  5036.7  517.56  5053.4  520.41  5059.0  519.69  5075.8  521.64  5081.4  521.48
  5089.8  522.76  5103.7  522.78  5120.5  524.05  5126.1  523.92  5142.9  524.92
  5170.8  525.77  5268.6  531.27  5299.4  531.73  5305.0  532.32  5335.7  533.14
#Mann=3,-1,0
  4600.3    0.12       0  4986.4    0.05       0  4994.2    0.12       0
Bank Sta=4986.4,4994.2
Exp/Cntr=0.3,0.1

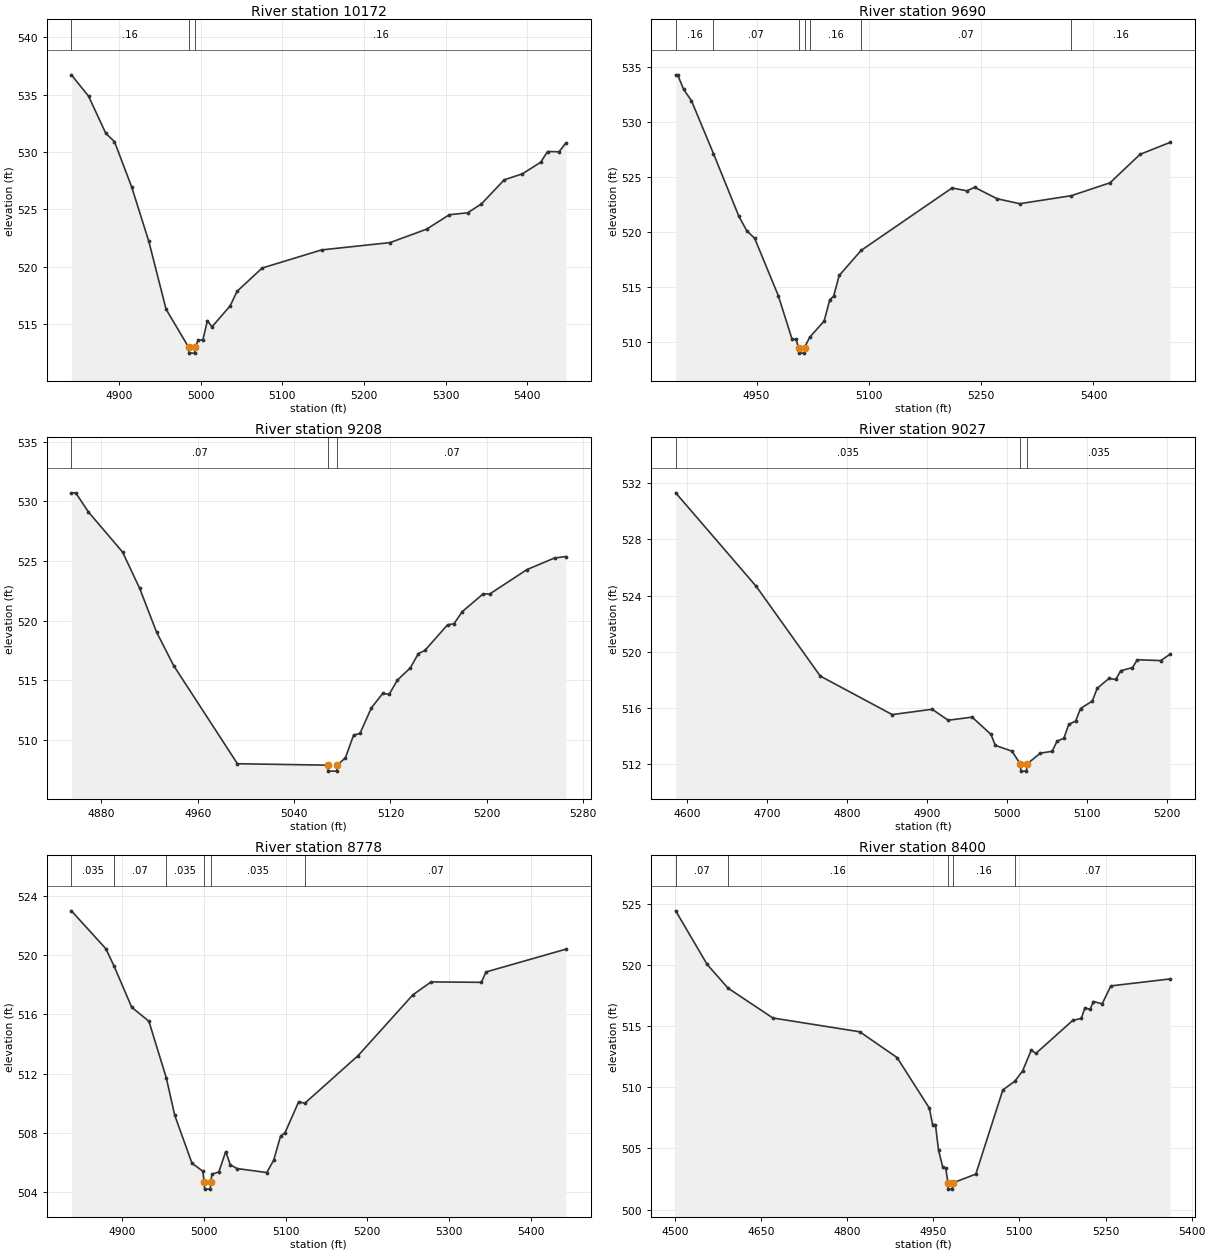
Type RM Length L Ch R = 1,10172,482,482,482
BEGIN DESCRIPTION:
BEAR HOLLOW CREEK 17.0
END DESCRIPTION:
XS GIS Cut Line= 3
      2333124.97     13707424.99      2332975.00     13707375.00
      2332574.99     13707575.00
#Sta/Elev= 30
  4841.9  536.72  4862.9  534.86  4884.0  531.62  4894.6  530.90  4915.7  526.94
  4936.7  522.19  4957.8  516.28  4985.5  512.95  4986.0  512.45  4992.8  512.45
  4993.3  512.95  4997.3  513.59  5002.8  513.59  5008.4  515.28  5014.0  514.74
  5036.3  516.58  5044.7  517.84  5075.4  519.87  5148.1  521.45  5232.0  522.09
  5276.7  523.26  5304.6  524.52  5327.0  524.69  5343.8  525.46  5371.7  527.56
  5394.1  528.09  5416.4  529.10  5424.8  530.03  5438.8  530.01  5447.2  530.77
#Mann=3,-1,0
  4841.9    0.16       0  4985.5    0.07       0  4993.3    0.16       0
Bank Sta=4985.5,4993.3
Exp/Cntr=0.3,0.1

Type RM Length L Ch R = 1,9690,482,482,482
BEGIN DESCRIPTION:
BEAR HOLLOW CREEK 16.0
END DESCRIPTION:
XS GIS Cut Line= 3
      2333175.00     13706975.00      2333025.00     13706925.00
      2332525.01     13706875.00
#Sta/Elev= 30
  4841.9  534.26  4844.5  534.26  4852.4  532.95  4863.0  531.90  4892.4  527.09
  4926.2  521.41  4936.8  520.08  4947.3  519.40  4978.9  514.19  4997.4  510.21
  5002.5  510.21  5006.1  509.45  5006.6  508.95  5013.5  508.95  5014.0  509.45
  5021.0  510.41  5040.2  511.86  5047.8  513.82  5052.8  514.11  5060.3  516.01
  5089.6  518.29  5211.1  523.97  5231.2  523.71  5241.2  524.03  5271.4  522.99
  5301.5  522.54  5370.6  523.27  5422.1  524.44  5462.3  527.03  5502.5  528.12
#Mann=7,-1,0
  4841.9    0.16       0  4892.4    0.07       0  5006.1    0.07       0
  5014.0    0.07       0  5021.0    0.16       0  5089.6    0.07       0
  5370.6    0.16       0
Bank Sta=5006.1,5014
Exp/Cntr=0.3,0.1

Type RM Length L Ch R = 1,9208,181,181,181
BEGIN DESCRIPTION:
BEAR HOLLOW CREEK 15.0
END DESCRIPTION:
XS GIS Cut Line= 3
      2333225.03     13706575.03      2333125.00     13706475.00
      2332875.02     13706574.99
#Sta/Elev= 30
  4855.0  530.70  4858.6  530.70  4869.2  529.09  4897.5  525.74  4911.6  522.72
  4925.7  519.04  4939.9  516.23  4992.9  508.00  5067.9  507.88  5068.4  507.38
  5075.4  507.38  5075.9  507.88  5082.6  508.50  5089.4  510.40  5094.7  510.54
  5104.2  512.69  5113.6  513.89  5119.0  513.82  5125.7  515.00  5136.5  516.03
  5143.2  517.23  5148.6  517.49  5167.4  519.64  5172.8  519.73  5179.6  520.74
  5197.1  522.24  5202.4  522.22  5233.4  524.27  5256.3  525.24  5265.7  525.36
#Mann=3,-1,0
  4855.0    0.07       0  5067.9    0.07       0  5075.9    0.07       0
Bank Sta=5067.9,5075.9
Exp/Cntr=0.3,0.1

Type RM Length L Ch R = 1,9027,249,249,249
BEGIN DESCRIPTION:
BEAR HOLLOW CREEK 14.5
END DESCRIPTION:
XS GIS Cut Line= 3
      2333405.89     13706336.46      2333013.80     13706333.62
      2332830.50     13706466.84
#Sta/Elev= 30
  4585.7  531.31  4686.6  524.65  4766.6  518.28  4856.6  515.54  4906.6  515.92
  4926.6  515.14  4956.6  515.36  4980.2  514.13  4985.6  513.35  5006.4  512.94
  5017.1  512.02  5017.6  511.52  5024.6  511.52  5025.1  512.02  5042.0  512.80
  5056.7  512.93  5062.9  513.65  5071.4  513.86  5077.5  514.84  5086.1  515.08
  5092.2  515.97  5106.9  516.50  5113.1  517.41  5127.8  518.11  5136.3  518.04
  5142.5  518.66  5157.2  518.88  5163.3  519.44  5192.7  519.38  5204.4  519.84
#Mann=3,-1,0
  4585.7   0.035       0  5017.1   0.035       0  5025.1   0.035       0
Bank Sta=5017.1,5025.1
Exp/Cntr=0.3,0.1

Type RM Length L Ch R = 1,8778,378,378,378
BEGIN DESCRIPTION:
BEAR HOLLOW CREEK 14.0
END DESCRIPTION:
XS GIS Cut Line= 3
      2333275.02     13706225.01      2333125.00     13706175.00
      2332725.04     13705975.02
#Sta/Elev= 30
  4837.8  522.99  4880.0  520.43  4890.1  519.25  4911.6  516.48  4932.7  515.53
  4954.1  511.68  4964.3  509.18  4985.4  505.94  4998.7  505.40  5000.3  504.69
  5000.8  504.19  5007.8  504.19  5008.3  504.69  5009.9  505.20  5018.3  505.35
  5026.7  506.73  5032.3  505.83  5040.7  505.58  5077.0  505.31  5085.4  506.14
  5093.8  507.76  5099.4  508.01  5116.1  510.10  5123.5  509.99  5188.8  513.21
  5255.9  517.32  5278.2  518.19  5339.7  518.16  5345.3  518.86  5443.1  520.40
#Mann=6,-1,0
  4837.8   0.035       0  4890.1    0.07       0  4954.1   0.035       0
  5000.3   0.035       0  5008.3   0.035       0  5123.5    0.07       0
Bank Sta=5000.3,5008.3
Exp/Cntr=0.3,0.1

Type RM Length L Ch R = 1,8400,550,550,550
BEGIN DESCRIPTION:
X18169
END DESCRIPTION:
XS GIS Cut Line= 4
      2333607.84     13705901.75      2333170.37     13705787.18
      2333041.90     13705811.48      2332809.59     13705964.05
#Sta/Elev= 30
  4501.7  524.47  4556.3  520.09  4592.7  518.14  4670.9  515.69  4822.2  514.56
  4887.1  512.45  4943.4  508.30  4948.9  506.96  4953.9  506.96  4959.4  504.84
  4966.8  503.45  4971.9  503.39  4975.7  502.17  4976.2  501.67  4983.2  501.67
  4983.7  502.17  5024.2  502.90  5071.3  509.80  5091.9  510.50  5105.5  511.34
  5120.6  513.05  5128.8  512.79  5192.9  515.49  5208.0  515.66  5214.0  516.51
  5223.1  516.40  5229.1  517.04  5244.2  516.85  5259.3  518.32  5362.6  518.89
#Mann=5,-1,0
  4501.7    0.07       0  4592.7    0.16       0  4975.7    0.07       0
  4983.7    0.16       0  5091.9    0.07       0
Bank Sta=4975.7,4983.7
Exp/Cntr=0.3,0.1

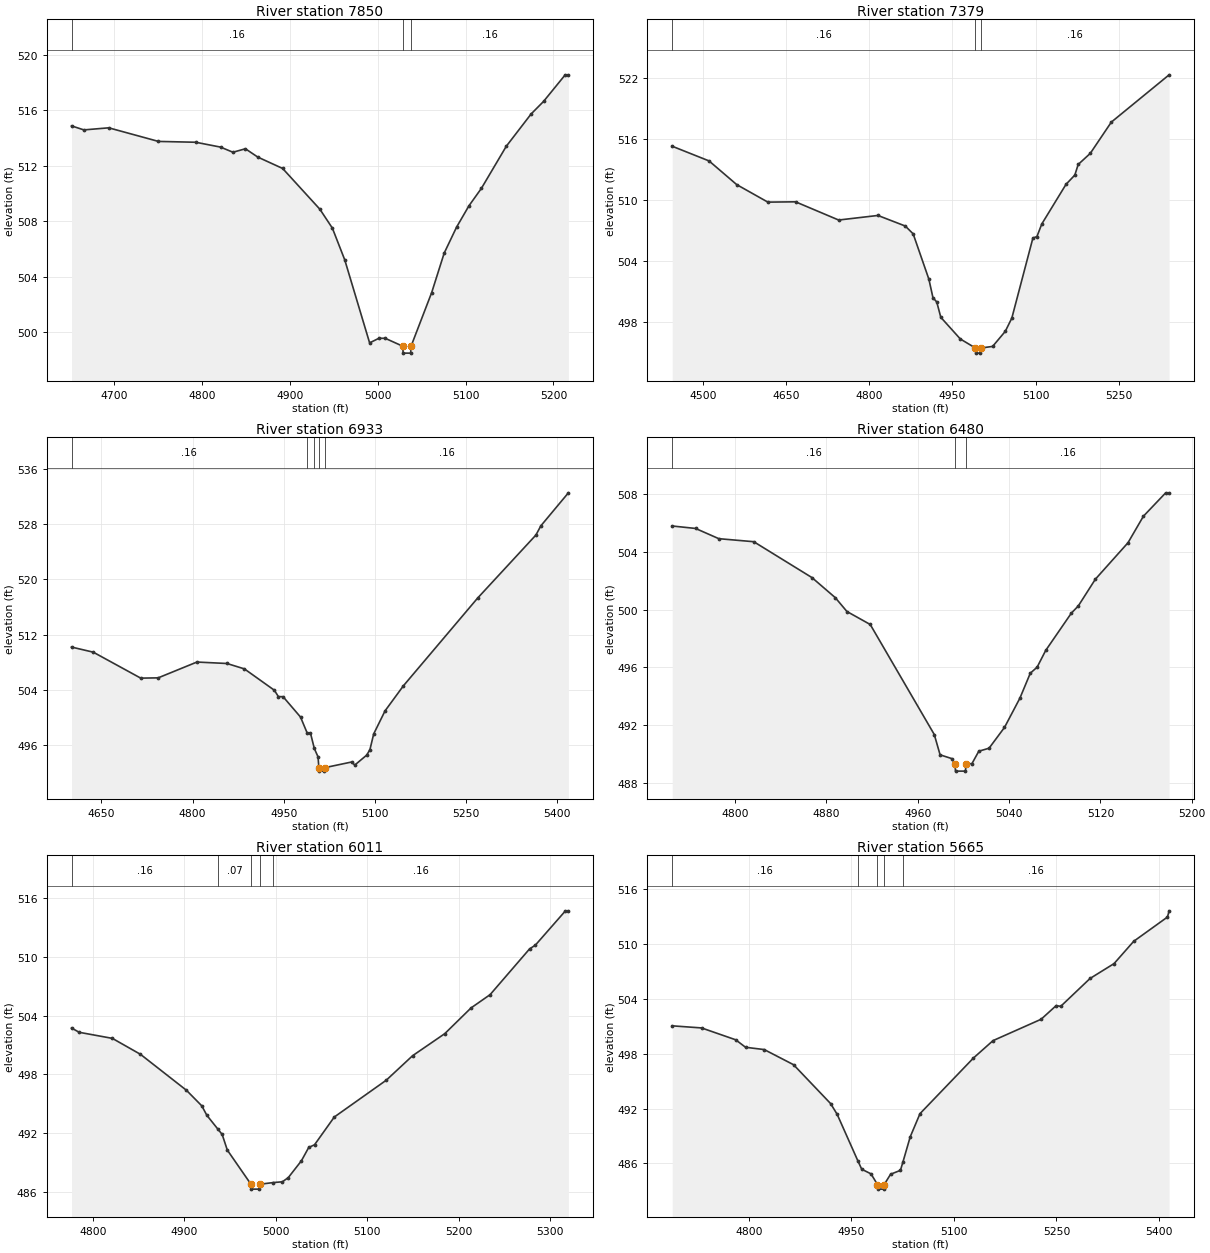
Type RM Length L Ch R = 1,7850,471,471,471
BEGIN DESCRIPTION:
BEAR HOLLOW CREEK 13.0
END DESCRIPTION:
XS GIS Cut Line= 3
      2333575.00     13705625.00      2333325.00     13705375.00
      2333174.99     13705224.99
#Sta/Elev= 30
  4651.3  514.87  4665.4  514.58  4693.7  514.73  4750.3  513.75  4792.7  513.69
  4821.0  513.34  4835.1  512.97  4849.3  513.22  4863.4  512.62  4891.7  511.80
  4934.1  508.86  4948.3  507.50  4962.4  505.21  4990.7  499.23  5001.3  499.56
  5008.4  499.56  5028.4  498.99  5028.9  498.49  5037.4  498.49  5037.9  498.99
  5061.4  502.86  5075.6  505.70  5089.7  507.57  5103.8  509.11  5118.0  510.37
  5146.3  513.40  5174.6  515.73  5188.7  516.63  5213.4  518.55  5217.0  518.55
#Mann=3,-1,0
  4651.3    0.16       0  5028.4    0.07       0  5037.9    0.16       0
Bank Sta=5028.4,5037.9
Exp/Cntr=0.3,0.1

Type RM Length L Ch R = 1,7379,446,446,446
BEGIN DESCRIPTION:
BEAR HOLLOW CREEK 12.0
END DESCRIPTION:
XS GIS Cut Line= 3
      2333930.76     13705353.12      2333525.00     13704975.00
      2333225.92     13704811.48
#Sta/Elev= 30
  4445.0  515.26  4511.3  513.82  4561.2  511.49  4617.3  509.77  4667.2  509.80
  4744.9  508.01  4815.7  508.46  4865.0  507.42  4879.2  506.65  4907.5  502.20
  4914.9  500.37  4921.7  499.96  4929.0  498.45  4964.2  496.32  4991.5  495.43
  4992.0  494.93  5000.5  494.93  5001.0  495.43  5022.4  495.59  5045.2  497.07
  5057.0  498.37  5095.0  506.24  5102.2  506.38  5111.1  507.63  5154.7  511.52
  5170.6  512.43  5176.6  513.47  5198.4  514.56  5236.3  517.63  5340.5  522.28
#Mann=3,-1,0
  4445.0    0.16       0  4991.5    0.07       0  5001.0    0.16       0
Bank Sta=4991.5,5001
Exp/Cntr=0.3,0.1

Type RM Length L Ch R = 1,6933,453,453,453
BEGIN DESCRIPTION:
BEAR HOLLOW CREEK 11.0
END DESCRIPTION:
XS GIS Cut Line= 3
      2334025.02     13704925.03      2333775.00     13704625.00
      2333375.04     13704475.02
#Sta/Elev= 30
  4600.8  510.20  4636.6  509.46  4714.7  505.70  4743.4  505.74  4807.2  508.03
  4856.6  507.82  4885.3  507.04  4934.7  503.94  4941.2  503.03  4949.0  503.01
  4977.7  500.06  4988.6  497.76  4994.0  497.76  5000.4  495.51  5006.5  494.30
  5007.9  492.73  5008.4  492.23  5017.0  492.23  5017.5  492.73  5061.7  493.55
  5067.0  493.11  5086.6  494.55  5091.9  495.34  5098.1  497.62  5116.8  500.96
  5147.1  504.60  5269.0  517.28  5365.1  526.43  5373.2  527.76  5418.5  532.54
#Mann=5,-1,0
  4600.8    0.16       0  4988.6    0.07       0  5000.4    0.16       0
  5007.9    0.07       0  5017.5    0.16       0
Bank Sta=5007.9,5017.5
Exp/Cntr=0.3,0.1

Type RM Length L Ch R = 1,6480,469,469,469
BEGIN DESCRIPTION:
BEAR HOLLOW CREEK 10.0
END DESCRIPTION:
XS GIS Cut Line= 3
      2334025.00     13704525.01      2333975.00     13704275.00
      2333875.02     13704125.03
#Sta/Elev= 30
  4745.0  505.81  4765.4  505.64  4785.8  504.93  4816.4  504.72  4867.4  502.23
  4887.8  500.84  4898.0  499.88  4918.4  498.98  4974.5  491.35  4979.6  489.94
  4989.8  489.68  4992.6  489.31  4993.1  488.81  5001.8  488.81  5002.3  489.31
  5007.5  489.33  5013.5  490.19  5022.5  490.40  5036.0  491.84  5049.5  493.87
  5058.6  495.60  5064.6  496.02  5072.1  497.18  5094.6  499.77  5100.6  500.26
  5115.6  502.12  5144.2  504.65  5157.7  506.49  5177.2  508.11  5180.2  508.11
#Mann=3,-1,0
  4745.0    0.16       0  4992.6    0.07       0  5002.3    0.16       0
Bank Sta=4992.6,5002.3
Exp/Cntr=0.3,0.1

Type RM Length L Ch R = 1,6011,346,346,346
BEGIN DESCRIPTION:
BEAR HOLLOW CREEK 9.0
END DESCRIPTION:
XS GIS Cut Line= 3
      2334425.00     13704175.00      2334325.00     13703975.00
      2334074.97     13703774.98
#Sta/Elev= 30
  4776.4  502.73  4784.8  502.29  4821.1  501.67  4851.9  500.04  4902.2  496.37
  4919.0  494.78  4924.5  493.82  4936.9  492.37  4941.3  491.86  4946.9  490.27
  4972.8  486.78  4973.3  486.28  4982.0  486.28  4982.5  486.78  4997.3  486.95
  5007.2  487.03  5013.6  487.45  5028.0  489.17  5036.0  490.53  5042.4  490.81
  5064.0  493.64  5120.9  497.40  5149.7  499.90  5184.9  502.15  5213.7  504.78
  5234.5  506.13  5277.7  510.80  5284.1  511.19  5317.0  514.69  5320.2  514.69
#Mann=5,-1,0
  4776.4    0.16       0  4936.9    0.07       0  4972.8    0.07       0
  4982.5    0.07       0  4997.3    0.16       0
Bank Sta=4972.8,4982.5
Exp/Cntr=0.3,0.1

Type RM Length L Ch R = 1,5665,404,404,404
BEGIN DESCRIPTION:
X18168
END DESCRIPTION:
XS GIS Cut Line= 2
      2334778.00     13703912.17      2334219.53     13703447.35
#Sta/Elev= 30
  4688.2  501.06  4731.1  500.83  4781.0  499.53  4795.4  498.71  4822.7  498.46
  4865.6  496.80  4919.8  492.54  4929.4  491.36  4959.8  486.24  4965.3  485.35
  4978.9  484.84  4988.3  483.67  4988.8  483.17  4997.6  483.17  4998.1  483.67
  5007.5  484.80  5021.9  485.23  5025.5  486.13  5036.2  488.90  5050.5  491.44
  5128.6  497.53  5157.3  499.44  5227.6  501.78  5249.7  503.28  5256.2  503.19
  5299.2  506.25  5334.3  507.88  5363.0  510.32  5412.4  512.98  5414.8  513.66
#Mann=5,-1,0
  4688.2    0.16       0  4959.8    0.07       0  4988.3    0.07       0
  4998.1    0.07       0  5025.5    0.16       0
Bank Sta=4988.3,4998.1
Exp/Cntr=0.3,0.1

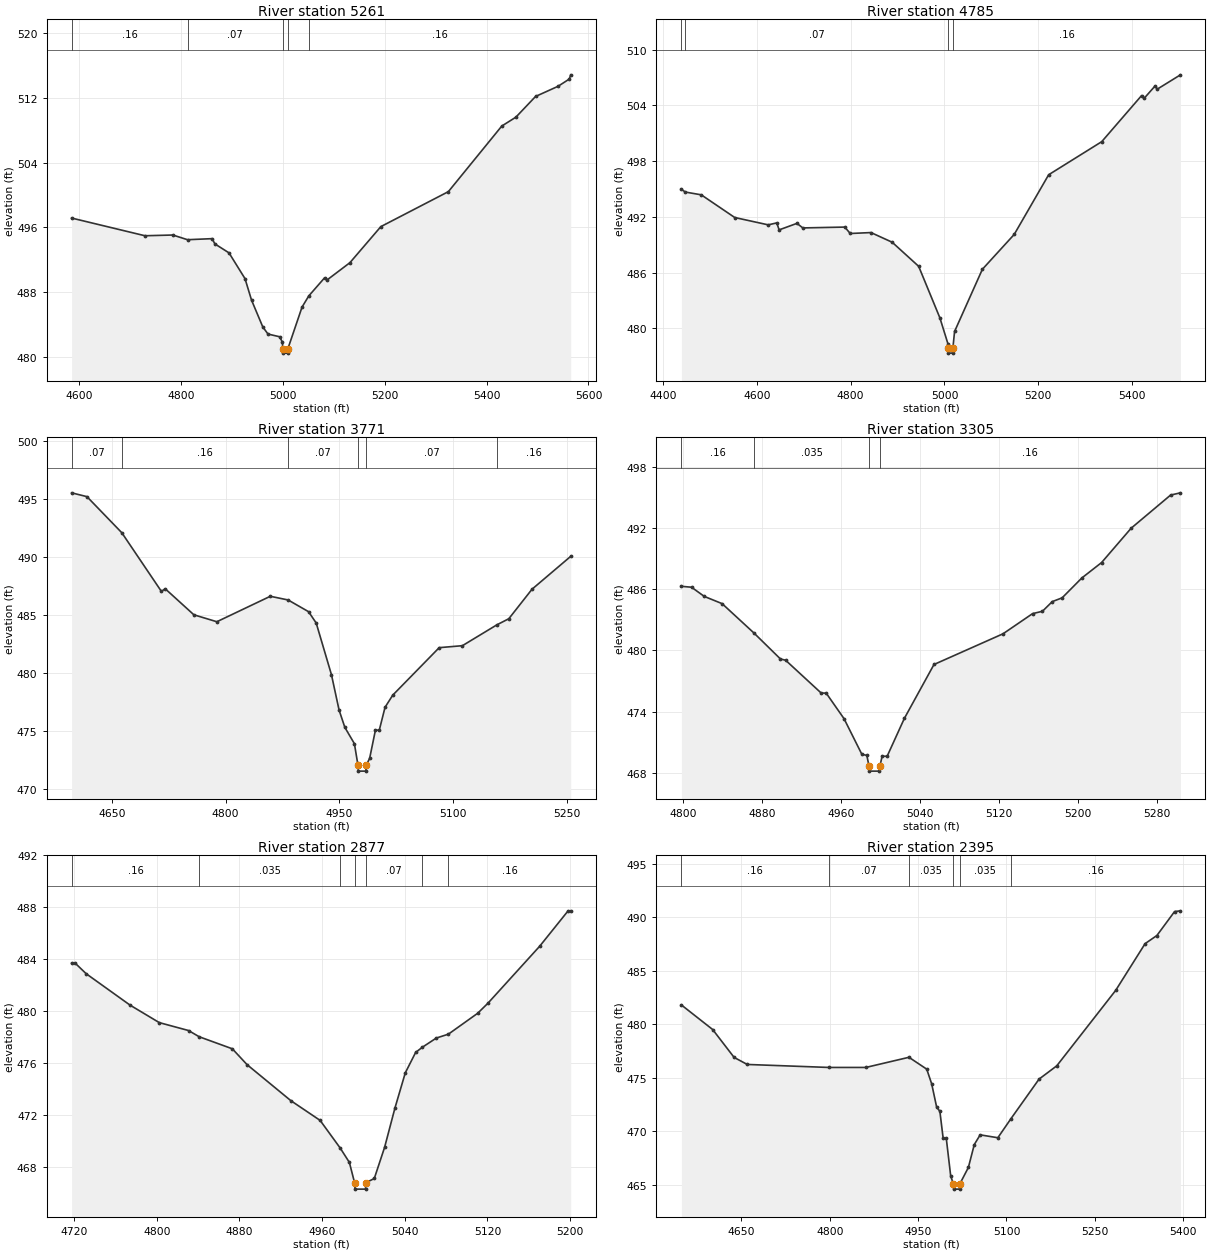
Type RM Length L Ch R = 1,5261,476,476,476
BEGIN DESCRIPTION:
X18167
END DESCRIPTION:
XS GIS Cut Line= 3
      2334909.96     13703728.15      2334882.18     13703453.84
      2334258.60     13703128.20
#Sta/Elev= 30
  4585.9  497.15  4729.8  494.96  4784.5  495.05  4813.3  494.47  4861.6  494.60
  4867.0  493.95  4894.7  492.84  4926.1  489.65  4938.9  486.99  4961.0  483.67
  4971.2  482.79  4993.8  482.46  4999.5  481.80  5000.2  480.93  5000.7  480.43
  5009.5  480.43  5010.0  480.93  5038.0  486.13  5051.3  487.52  5082.2  489.75
  5087.8  489.52  5132.0  491.63  5192.6  496.09  5325.1  500.42  5429.9  508.54
  5457.6  509.64  5496.1  512.20  5540.3  513.46  5562.4  514.36  5565.1  514.88
#Mann=5,-1,0
  4585.9    0.16       0  4813.3    0.07       0  5000.2    0.07       0
  5010.0    0.07       0  5051.3    0.16       0
Bank Sta=5000.2,5010
Exp/Cntr=0.3,0.1

Type RM Length L Ch R = 1,4785,1014,1014,1014
BEGIN DESCRIPTION:
X18166
END DESCRIPTION:
XS GIS Cut Line= 3
      2335048.84     13703436.52      2335125.24     13703061.48
      2334510.66     13702766.35
#Sta/Elev= 30
  4438.9  494.98  4447.1  494.67  4481.3  494.37  4552.7  491.93  4624.1  491.14
  4642.3  491.35  4647.4  490.60  4685.4  491.30  4697.9  490.81  4787.4  490.90
  4799.1  490.21  4843.3  490.31  4888.5  489.27  4945.0  486.68  4990.3  481.13
  5007.4  478.35  5008.0  477.84  5008.5  477.34  5017.4  477.34  5017.9  477.84
  5021.6  479.67  5080.9  486.36  5148.8  490.11  5222.3  496.53  5335.5  500.09
  5420.5  505.05  5426.1  504.76  5448.7  506.05  5454.3  505.75  5503.4  507.28
#Mann=4,-1,0
  4438.9    0.16       0  4447.1    0.07       0  5008.0    0.07       0
  5017.9    0.16       0
Bank Sta=5008,5017.9
Exp/Cntr=0.3,0.1

Type RM Length L Ch R = 1,3771,466,466,466
BEGIN DESCRIPTION:
BEAR HOLLOW CREEK 7.0
END DESCRIPTION:
XS GIS Cut Line= 3
      2335674.99     13702025.00      2335275.00     13702075.00
      2335024.96     13702125.01
#Sta/Elev= 30
  4596.9  495.56  4617.1  495.23  4663.1  492.11  4715.3  487.04  4720.3  487.27
  4758.1  485.02  4788.4  484.42  4858.9  486.62  4882.4  486.30  4909.3  485.29
  4919.4  484.31  4939.5  479.85  4949.6  476.78  4957.2  475.29  4969.8  473.88
  4974.5  472.01  4975.0  471.51  4984.8  471.51  4985.3  472.01  4989.9  472.62
  4997.5  475.05  5002.6  475.05  5010.2  477.03  5020.4  478.08  5081.6  482.18
  5112.2  482.35  5157.6  484.15  5173.4  484.68  5204.0  487.23  5255.0  490.07
#Mann=6,-1,0
  4596.9    0.07       0  4663.1    0.16       0  4882.4    0.07       0
  4974.5    0.07       0  4985.3    0.07       0  5157.6    0.16       0
Bank Sta=4974.5,4985.3
Exp/Cntr=0.3,0.1

Type RM Length L Ch R = 1,3305,428,428,428
BEGIN DESCRIPTION:
BEAR HOLLOW CREEK 6.0
END DESCRIPTION:
XS GIS Cut Line= 3
      2335425.03     13701574.99      2335225.00     13701625.00
      2334924.98     13701625.00
#Sta/Elev= 30
  4798.0  486.29  4808.3  486.20  4821.2  485.30  4839.3  484.59  4871.6  481.71
  4898.5  479.16  4903.7  479.04  4939.8  475.82  4944.9  475.81  4963.0  473.30
  4981.0  469.82  4986.1  469.70  4988.3  468.66  4988.8  468.16  4998.9  468.16
  4999.4  468.66  5001.6  469.62  5006.7  469.62  5024.2  473.34  5054.2  478.62
  5124.2  481.63  5154.2  483.61  5164.2  483.84  5174.2  484.79  5184.2  485.16
  5204.2  487.11  5224.2  488.62  5254.2  491.99  5294.2  495.24  5304.2  495.46
#Mann=4,-1,0
  4798.0    0.16       0  4871.6   0.035       0  4988.3    0.07       0
  4999.4    0.16       0
Bank Sta=4988.3,4999.4
Exp/Cntr=0.3,0.1

Type RM Length L Ch R = 1,2877,482,482,482
BEGIN DESCRIPTION:
BEAR HOLLOW CREEK 5.0
END DESCRIPTION:
XS GIS Cut Line= 3
      2335424.99     13701424.99      2335225.00     13701225.00
      2335025.02     13701225.00
#Sta/Elev= 30
  4717.7  483.68  4721.2  483.68  4731.8  482.87  4774.2  480.45  4802.5  479.10
  4830.8  478.49  4841.1  478.01  4873.2  477.08  4887.4  475.86  4929.8  473.08
  4958.1  471.56  4977.5  469.43  4986.4  468.32  4991.4  466.76  4991.9  466.26
  5002.0  466.26  5002.5  466.76  5010.5  467.08  5020.5  469.49  5030.5  472.52
  5040.5  475.23  5050.5  476.80  5056.8  477.19  5070.5  477.91  5082.2  478.21
  5110.5  479.82  5120.5  480.60  5170.5  484.99  5198.0  487.72  5200.5  487.72
#Mann=7,-1,0
  4717.7    0.16       0  4841.1   0.035       0  4977.5    0.07       0
  4991.4   0.035       0  5002.5    0.07       0  5056.8    0.07       0
  5082.2    0.16       0
Bank Sta=4991.4,5002.5
Exp/Cntr=0.3,0.1

Type RM Length L Ch R = 1,2395,466,466,466
BEGIN DESCRIPTION:
BEAR HOLLOW CREEK 4.0
END DESCRIPTION:
XS GIS Cut Line= 3
      2335725.01     13700975.01      2335325.00     13700775.00
      2334925.03     13700775.00
#Sta/Elev= 30
  4548.2  481.81  4601.3  479.51  4637.7  476.90  4660.0  476.24  4798.3  475.96
  4861.3  475.96  4934.5  476.91  4964.7  475.80  4973.1  474.42  4981.5  472.25
  4987.0  471.85  4992.6  469.31  4997.9  469.31  5005.4  465.79  5009.9  465.07
  5010.4  464.57  5020.5  464.57  5021.0  465.07  5035.4  466.60  5045.4  468.74
  5055.4  469.65  5085.4  469.38  5107.6  471.16  5155.4  474.87  5185.4  476.11
  5285.4  483.17  5335.4  487.55  5355.4  488.31  5385.4  490.55  5395.4  490.62
#Mann=6,-1,0
  4548.2    0.16       0  4798.3    0.07       0  4934.5   0.035       0
  5009.9   0.035       0  5021.0   0.035       0  5107.6    0.16       0
Bank Sta=5009.9,5021
Exp/Cntr=0.3,0.1

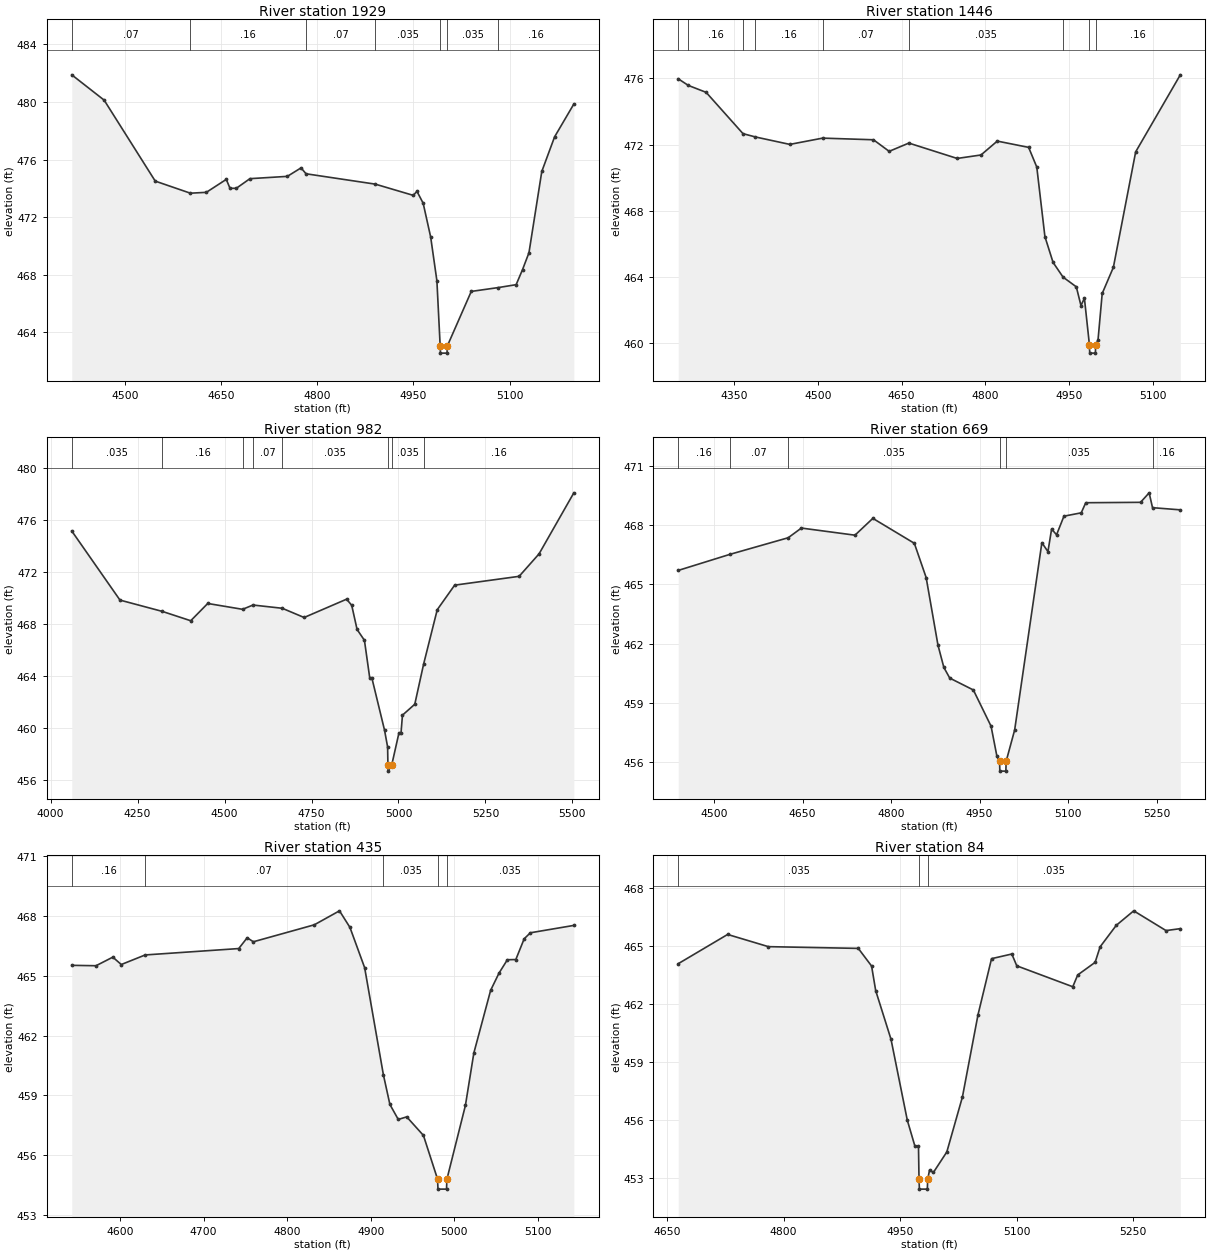
Type RM Length L Ch R = 1,1929,483,483,483
BEGIN DESCRIPTION:
BEAR HOLLOW CREEK 3.0
END DESCRIPTION:
XS GIS Cut Line= 3
      2335775.00     13700625.00      2335275.00     13700325.00
      2335074.99     13700325.00
#Sta/Elev= 30
  4417.0  481.89  4467.5  480.13  4547.2  474.50  4602.0  473.66  4626.9  473.72
  4658.0  474.62  4663.8  474.00  4673.6  474.00  4694.9  474.67  4753.2  474.83
  4774.6  475.42  4782.4  475.01  4890.4  474.29  4949.6  473.51  4955.4  473.79
  4965.1  472.96  4976.8  470.61  4986.5  467.57  4991.6  463.04  4992.1  462.54
  5002.3  462.54  5002.8  463.04  5040.1  466.83  5082.5  467.10  5110.1  467.30
  5120.1  468.35  5130.1  469.52  5150.1  475.17  5170.1  477.58  5200.1  479.86
#Mann=7,-1,0
  4417.0    0.07       0  4602.0    0.16       0  4782.4    0.07       0
  4890.4   0.035       0  4991.6   0.035       0  5002.8   0.035       0
  5082.5    0.16       0
Bank Sta=4991.6,5002.8
Exp/Cntr=0.3,0.1

Type RM Length L Ch R = 1,1446,464,464,464
BEGIN DESCRIPTION:
BEAR HOLLOW CREEK 2.0
END DESCRIPTION:
XS GIS Cut Line= 3
      2335775.01     13700325.01      2335175.00     13699875.00
      2335025.02     13699875.00
#Sta/Elev= 30
  4249.5  475.98  4267.5  475.58  4299.5  475.16  4365.6  472.66  4387.9  472.46
  4449.5  472.01  4508.3  472.39  4599.5  472.29  4627.6  471.59  4662.9  472.09
  4749.5  471.16  4792.2  471.37  4821.4  472.21  4877.6  471.83  4892.2  470.64
  4906.8  466.43  4921.4  464.87  4939.3  463.98  4963.1  463.39  4971.4  462.26
  4977.6  462.70  4986.6  459.88  4987.1  459.38  4997.3  459.38  4997.8  459.88
  5002.0  460.18  5009.5  462.99  5029.5  464.57  5069.5  471.56  5149.5  476.22
#Mann=9,-1,0
  4249.5    0.07       0  4267.5    0.16       0  4365.6    0.07       0
  4387.9    0.16       0  4508.3    0.07       0  4662.9   0.035       0
  4939.3    0.16       0  4986.6    0.07       0  4997.8    0.16       0
Bank Sta=4986.6,4997.8
Exp/Cntr=0.3,0.1

Type RM Length L Ch R = 1,982,313,313,313
BEGIN DESCRIPTION:
BEAR HOLLOW CREEK 1.0
END DESCRIPTION:
XS GIS Cut Line= 3
      2336024.99     13699925.00      2335225.00     13699425.00
      2334824.99     13699725.01
#Sta/Elev= 30
  4060.8  475.18  4199.4  469.86  4321.0  468.99  4402.8  468.27  4451.7  469.60
  4551.9  469.15  4581.7  469.48  4665.9  469.23  4728.8  468.52  4850.9  469.93
  4865.6  469.46  4881.0  467.60  4902.2  466.76  4917.5  463.85  4923.4  463.88
  4960.0  459.84  4968.8  458.55  4969.7  457.19  4970.2  456.69  4980.9  457.19
  5001.2  459.61  5007.3  459.61  5011.5  461.00  5046.9  461.84  5072.3  464.93
  5111.5  469.12  5161.5  471.01  5346.9  471.69  5404.2  473.42  5504.2  478.12
#Mann=8,-1,0
  4060.8   0.035       0  4321.0    0.16       0  4551.9   0.035       0
  4581.7    0.07       0  4665.9   0.035       0  4969.7   0.035       0
  4980.9   0.035       0  5072.3    0.16       0
Bank Sta=4969.7,4980.9
Exp/Cntr=0.3,0.1

Type RM Length L Ch R = 1,669,234,234,234
BEGIN DESCRIPTION:
X18165
END DESCRIPTION:
XS GIS Cut Line= 4
      2335781.87     13699196.94      2335423.66     13699148.97
      2335167.82     13699145.77      2335030.27     13699334.49
#Sta/Elev= 30
  4439.4  465.70  4526.8  466.51  4625.7  467.35  4648.1  467.84  4738.9  467.48
  4769.2  468.33  4839.5  467.07  4859.5  465.34  4879.5  461.93  4889.5  460.80
  4899.5  460.26  4939.5  459.66  4969.5  457.83  4979.5  456.30  4983.9  456.06
  4984.4  455.56  4994.6  455.56  4995.1  456.06  5009.5  457.64  5055.6  467.10
  5065.9  466.65  5072.1  467.79  5080.5  467.50  5093.0  468.44  5122.3  468.61
  5130.0  469.12  5222.8  469.14  5237.4  469.62  5243.1  468.87  5290.2  468.76
#Mann=6,-1,0
  4439.4    0.16       0  4526.8    0.07       0  4625.7   0.035       0
  4983.9   0.035       0  4995.1   0.035       0  5243.1    0.16       0
Bank Sta=4983.9,4995.1
Exp/Cntr=0.3,0.1

Type RM Length L Ch R = 1,435,351,351,351
BEGIN DESCRIPTION:
X18164
END DESCRIPTION:
XS GIS Cut Line= 2
      2335733.91     13698969.88      2335135.88     13698915.51
#Sta/Elev= 30
  4542.4  465.52  4571.4  465.50  4591.5  465.93  4601.6  465.56  4630.2  466.04
  4742.1  466.36  4752.2  466.90  4759.6  466.70  4832.5  467.55  4862.6  468.25
  4875.1  467.42  4892.7  465.40  4915.1  460.04  4922.9  458.55  4932.9  457.80
  4943.0  457.93  4963.0  457.00  4979.9  454.81  4980.4  454.31  4990.6  454.31
  4991.1  454.81  5013.2  458.50  5023.3  461.13  5043.4  464.27  5053.4  465.13
  5063.4  465.80  5073.5  465.81  5083.5  466.85  5090.9  467.15  5142.9  467.52
#Mann=5,-1,0
  4542.4    0.16       0  4630.2    0.07       0  4915.1   0.035       0
  4979.9   0.035       0  4991.1   0.035       0
Bank Sta=4979.9,4991.1
Exp/Cntr=0.3,0.1

Type RM Length L Ch R = 1,84,0,0,0
BEGIN DESCRIPTION:
X18163
END DESCRIPTION:
XS GIS Cut Line= 4
      2335695.45     13698707.62      2335401.28     13698611.69
      2335305.33     13698602.10      2335155.32     13698790.41
#Sta/Elev= 30
  4664.2  464.08  4727.8  465.59  4780.3  464.96  4896.1  464.87  4913.2  463.96
  4918.5  462.69  4938.2  460.18  4959.2  456.00  4969.0  454.66  4973.6  454.66
  4974.3  452.94  4974.8  452.44  4985.0  452.44  4985.5  452.94  4987.8  453.42
  4992.8  453.30  5010.1  454.36  5030.2  457.20  5050.3  461.45  5067.7  464.34
  5093.8  464.58  5100.2  463.97  5172.3  462.89  5178.7  463.50  5201.1  464.15
  5207.5  464.95  5228.3  466.06  5250.8  466.81  5292.4  465.79  5310.8  465.89
#Mann=3,-1,0
  4664.2   0.035       0  4974.3   0.035       0  4985.5   0.035       0
Bank Sta=4974.3,4985.5
Exp/Cntr=0.3,0.1

Chan Stop Cuts=-1