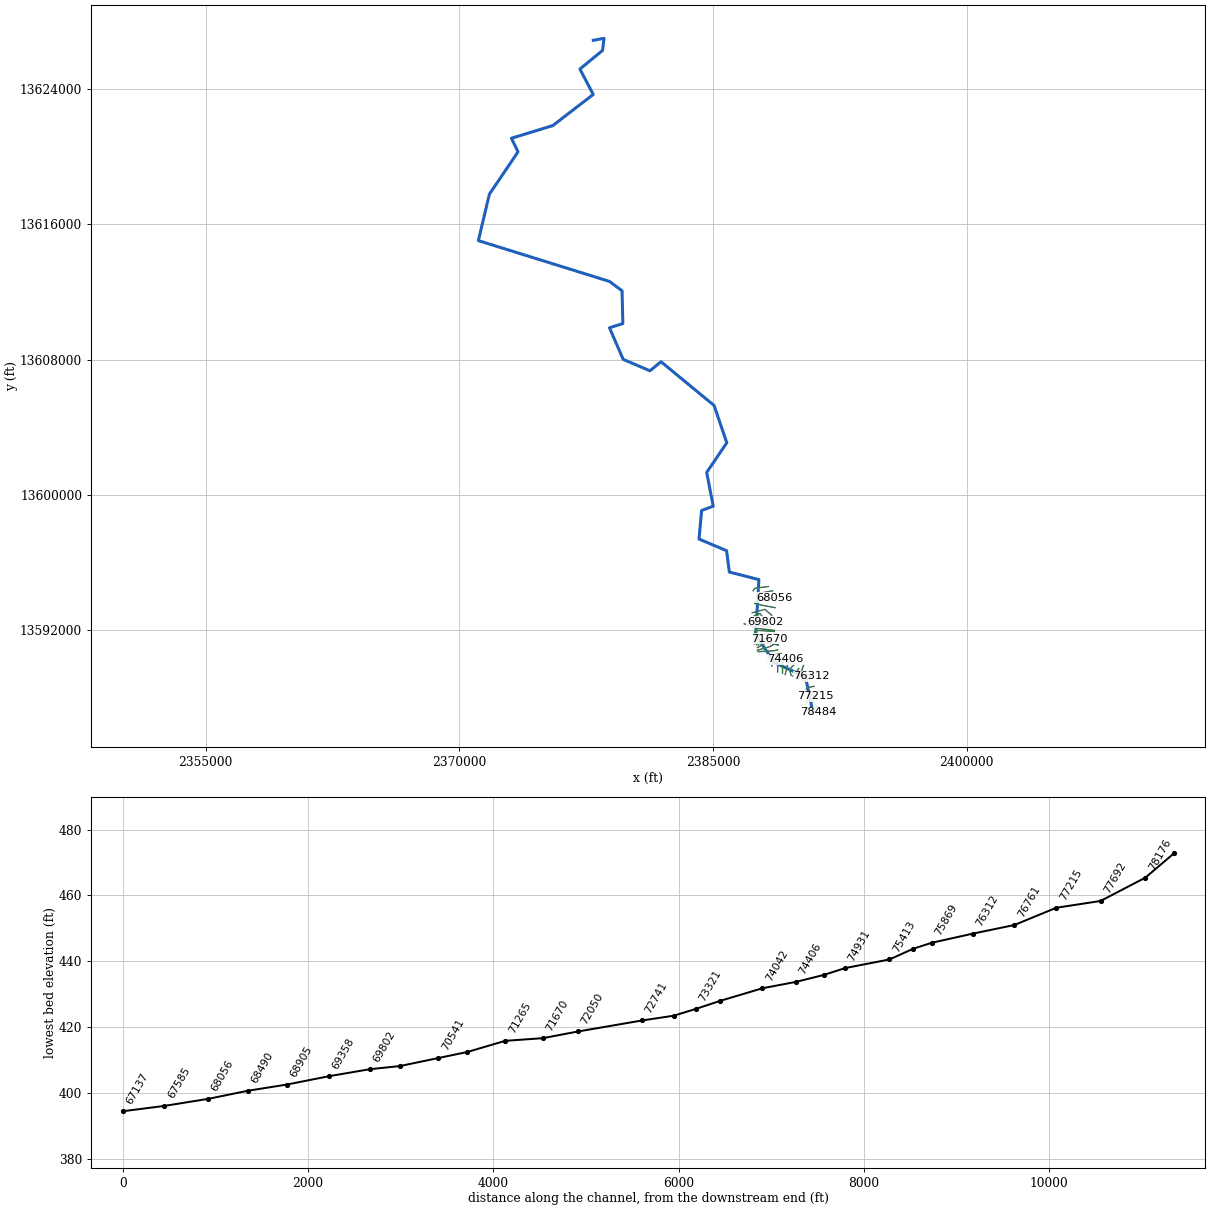
--- BRUSHY CREEK.prj (project) ---

Proj Title=BRUSHY CREEK Base Level Engineering
Current Plan=p01
Default Exp/Contr=0.3,0.1
English Units
Geom File=g01
Flow File=f01
Plan File=p01
Y Axis Title=Elevation
X Axis Title(PF)=Main Channel Distance
X Axis Title(XS)=Station
BEGIN DESCRIPTION:
BRUSHY CREEK
END DESCRIPTION:
DSS Export Rating Curves= 0
DSS Export Rating Curve Sorted= 0
DSS Export Volume Flow Curves= 0
DXF OffsetX= 0
DXF OffsetY= 0
DXF ScaleX= 1
DXF ScaleY= 10

--- BRUSHY CREEK.p01 (plan) ---

Plan Title=Multiple Run
Short Identifier=Multiple
Geom File=g01
Flow File=f01
Subcritical Flow
K Sum by GR= 0
Std Step Tol= 0.01
Critical Tol= 0.01
Num of Std Step Trials= 20
Max Error Tol= 0.3
Flow Tol Ratio= 0.001
Split Flow NTrial= 30
Split Flow Tol= 0.02
Split Flow Ratio= 0.02
Log Output Level= 0
Friction Slope Method= 1
Unsteady Friction Slope Method= 2
Unsteady Bridges Friction Slope Method= 1
Parabolic Critical Depth
Global Vel Dist=  1 , 1 , 1
Global Log Level= 0
CheckData=True
Encroach Param= -1, 0, 0, 0
BEGIN DESCRIPTION:
Multiple Run
END DESCRIPTION:

--- BRUSHY CREEK.f01 (steady flow) ---

Flow Title=Multiple
Number of Profiles=7
Profile Names=10-year,25-year,50-year,1pct_min,100-year,1pct_plu,500-year
River Rch & RM= BRUSHY CREEK,Reach-1,78484
     498     807    1087     711    1418    2829    2391
River Rch & RM= BRUSHY CREEK,Reach-1,75670
     815    1356    1859    1235    2463    4915    4289
River Rch & RM= BRUSHY CREEK,Reach-1,72050
     790    1309    1789    1185    2363    4716    4090
River Rch & RM= BRUSHY CREEK,Reach-1,70541
    1178    1990    2756    1845    3682    7347    6521
River Rch & RM= BRUSHY CREEK,Reach-1,66241
    1440    2455    3421    2303    4595    9169    8228
River Rch & RM= BRUSHY CREEK,Reach-1,64497
    1457    2477    3446    2315    4618    9214    8233
River Rch & RM= BRUSHY CREEK,Reach-1,62225
    1497    2538    3521    2359    4706    9390    8343
River Rch & RM= BRUSHY CREEK,Reach-1,58783
    1730    2946    4100    2753    5493   10960    9786
River Rch & RM= BRUSHY CREEK,Reach-1,52789
    1913    3267    4556    3064    6113   12196   10922
River Rch & RM= BRUSHY CREEK,Reach-1,49553
    1984    3385    4717    3168    6322   12614   11273
River Rch & RM= BRUSHY CREEK,Reach-1,46153
    2073    3531    4914    3295    6575   13119   11687
River Rch & RM= BRUSHY CREEK,Reach-1,40613
    2603    4463    6238    4198    8377   16714   14995
River Rch & RM= BRUSHY CREEK,Reach-1,33622
    2883    4952    6929    4667    9312   18580   16692
River Rch & RM= BRUSHY CREEK,Reach-1,23174
    2871    4926    6888    4636    9249   18455   16556
River Rch & RM= BRUSHY CREEK,Reach-1,21462
    4842    8441   11933    8109   16181   32284   29518
River Rch & RM= BRUSHY CREEK,Reach-1,15346
    4960    8640   12210    8293   16547   33015   30153
River Rch & RM= BRUSHY CREEK,Reach-1,13577
    4950    8606   12143    8235   16431   32783   29847
River Rch & RM= BRUSHY CREEK,Reach-1,11618
    4992    8674   12237    8295   16551   33024   30045
Boundary for River Rch & Prof#=BRUSHY CREEK,Reach-1,1
Up Type=0
Dn Type=3
Dn Slope=0.0008
Boundary for River Rch & Prof#=BRUSHY CREEK,Reach-1,2
Up Type=0
Dn Type=3
Dn Slope=0.0008
Boundary for River Rch & Prof#=BRUSHY CREEK,Reach-1,3
Up Type=0
Dn Type=3
Dn Slope=0.0008
Boundary for River Rch & Prof#=BRUSHY CREEK,Reach-1,4
Up Type=0
Dn Type=3
Dn Slope=0.0008
Boundary for River Rch & Prof#=BRUSHY CREEK,Reach-1,5
Up Type=0
Dn Type=3
Dn Slope=0.0008
Boundary for River Rch & Prof#=BRUSHY CREEK,Reach-1,6
Up Type=0
Dn Type=3
Dn Slope=0.0008
Boundary for River Rch & Prof#=BRUSHY CREEK,Reach-1,7
Up Type=0
Dn Type=3
Dn Slope=0.0008

--- BRUSHY CREEK.g01 (geometry) ---

Geom Title=Existing Conditions
Program Version=4.10

River Reach=BRUSHY CREEK    ,Reach-1
Reach XY= 30
        2390925.       13587075.       2390467.2     13589231.21
      2388607.75     13590091.14      2387527.98      13591732.6
      2387714.66     13594985.08      2385968.81     13595432.75
      2385805.65     13596695.05      2384176.97      13597380.9
      2384328.52     13599073.55      2385017.69     13599324.89
      2384626.96     13601319.11      2385817.93     13603075.01
      2385067.15     13605281.19       2381927.7     13607869.64
       2381274.9     13607332.34      2379688.23     13608011.27
      2378882.01     13609875.21      2379671.48     13610126.22
      2379624.05     13612064.59      2378881.19     13612617.19
      2371126.97      13615030.9      2371778.31     13617773.27
      2373472.74     13620280.94      2373085.03     13621085.07
      2375527.59     13621830.71      2377919.26     13623672.66
      2377132.31     13625175.11      2378471.55     13626276.25
      2378558.59      13626991.8        2377925.       13626875.

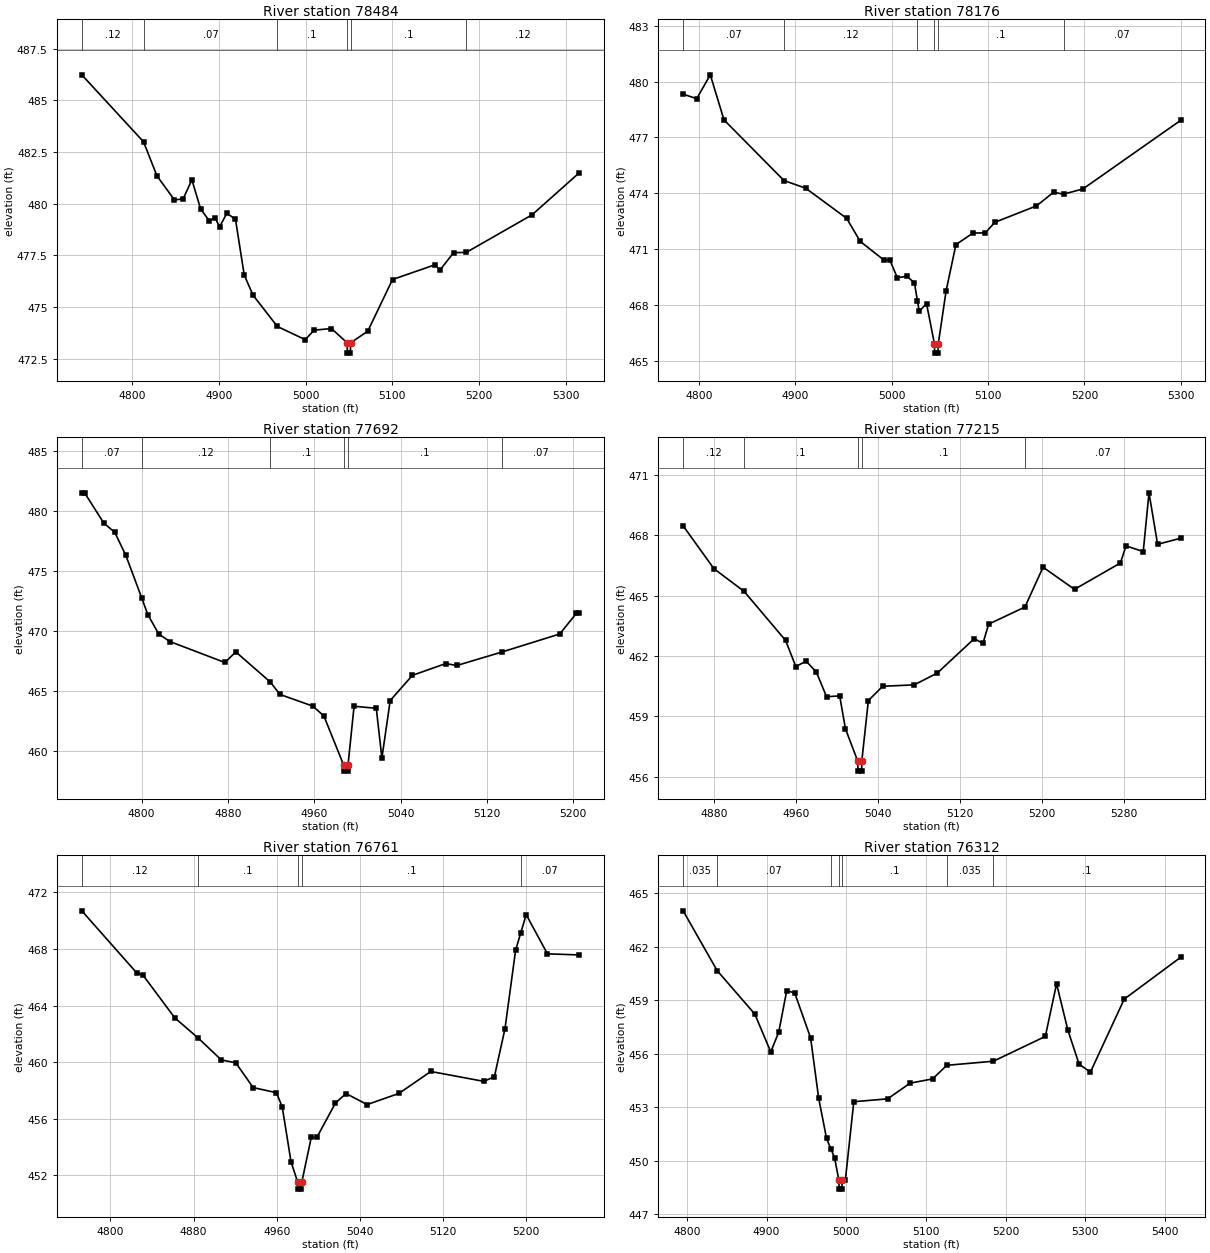
Type RM Length L Ch R = 1 ,78484   ,308,308,308
BEGIN DESCRIPTION:
X18336
END DESCRIPTION:
XS GIS Cut Line= 2
      2390668.78     13587081.82      2391239.05     13587148.91
#Sta/Elev= 30
  4741.6  486.23  4812.9  482.99  4828.4  481.34  4848.6  480.18  4858.6  480.23
  4868.7  481.15  4878.8  479.74  4888.8  479.17  4895.5  479.32  4900.6  478.87
    4909  479.53    4919  479.25  4929.1  476.55  4939.2  475.58  4967.3  474.06
  4999.6  473.42  5009.7  473.88  5029.8  473.96  5047.9  473.27  5048.2  472.77
  5051.7  472.77  5051.9  473.27  5071.7  473.83  5100.3  476.33  5149.8  477.05
  5154.8  476.77  5170.8  477.63  5185.4  477.64  5261.4  479.46  5315.8  481.49
#Mann= 6 ,-1 , 0
  4741.6     .12       0  4812.9     .07       0  4967.3      .1       0
  5047.9     .05       0  5051.9      .1       0  5185.4     .12       0
Bank Sta=5047.9,5051.9
XS Rating Curve= 0 ,0
Exp/Cntr=0.3,0.1

Type RM Length L Ch R = 1 ,78176   ,484,484,484
BEGIN DESCRIPTION:
BRUSHY CREEK 102.0
END DESCRIPTION:
XS GIS Cut Line= 3
      2390725.03     13587225.03        2390875.       13587375.
      2391174.97     13587424.99
#Sta/Elev= 30
  4783.6  479.32  4797.7  479.08  4811.8  480.36    4826  477.94  4888.3  474.68
  4910.8  474.27  4953.3  472.65  4967.4  471.41  4992.2   470.4  4998.2   470.4
  5005.8  469.47    5016  469.53  5023.6  469.19  5026.8  468.21  5028.6  467.66
  5036.2  468.07  5044.4  465.91  5044.6  465.41  5048.1  465.41  5048.4  465.91
  5056.5  468.75  5066.7  471.24  5084.4  471.86  5097.1  471.87  5107.2  472.44
  5150.3  473.32    5168  474.05  5178.4  473.95  5198.5  474.23  5299.8  477.91
#Mann= 6 ,-1 , 0
  4783.6     .07       0  4888.3     .12       0  5026.8      .1       0
  5044.4     .05       0  5048.4      .1       0  5178.4     .07       0
Bank Sta=5044.4,5048.4
XS Rating Curve= 0 ,0
Exp/Cntr=0.3,0.1

Type RM Length L Ch R = 1 ,77692   ,477,477,477
BEGIN DESCRIPTION:
BRUSHY CREEK 101.0
END DESCRIPTION:
XS GIS Cut Line= 3
      2390524.98       13587775.        2390775.       13587825.
      2390974.98     13587775.01
#Sta/Elev= 30
  4744.5  481.53  4747.1  481.53  4764.9  479.01  4775.1  478.23  4785.3  476.32
    4800  472.78  4805.7  471.37  4815.9  469.75  4826.1  469.13  4877.1  467.38
  4887.3  468.26  4919.4  465.74  4928.1  464.72  4958.7  463.74  4968.9  462.92
  4987.3  458.82  4987.5  458.32    4991  458.32  4991.3  458.82  4996.9  463.73
  5017.5  463.56  5022.7  459.41  5030.4  464.21    5051  466.31  5081.9  467.29
  5092.2  467.13  5134.2  468.26  5187.6  469.76    5203  471.48  5205.6  471.48
#Mann= 6 ,-1 , 0
  4744.5     .07       0    4800     .12       0  4919.4      .1       0
  4987.3     .05       0  4991.3      .1       0  5134.2     .07       0
Bank Sta=4987.3,4991.3
XS Rating Curve= 0 ,0
Exp/Cntr=0.3,0.1

Type RM Length L Ch R = 1 ,77215   ,454,454,454
BEGIN DESCRIPTION:
BRUSHY CREEK 100.0
END DESCRIPTION:
XS GIS Cut Line= 3
      2390624.96       13588225.        2390775.       13588225.
      2391075.04     13588074.98
#Sta/Elev= 30
  4849.9  468.47  4879.9  466.34  4909.4  465.21  4949.9  462.77  4959.9  461.47
  4969.9  461.74  4979.9   461.2  4989.9  459.97  5002.7  460.01  5008.3  458.38
  5020.3  456.77  5020.6  456.27  5024.1  456.27  5024.3  456.77  5030.7  459.78
  5044.7  460.49  5075.4  460.56  5097.8  461.14  5134.1  462.86  5142.5  462.62
  5148.1  463.58  5183.5  464.43  5201.2  466.41  5231.9  465.31  5276.7  466.62
  5282.2  467.47    5299  467.19  5304.6  470.11    5313  467.55  5335.4  467.85
#Mann= 5 ,-1 , 0
  4849.9     .12       0  4909.4      .1       0  5020.3     .05       0
  5024.3      .1       0  5183.5     .07       0
Bank Sta=5020.3,5024.3
XS Rating Curve= 0 ,0
Exp/Cntr=0.3,0.1

Type RM Length L Ch R = 1 ,76761   ,449,449,449
BEGIN DESCRIPTION:
BRUSHY CREEK 99.0
END DESCRIPTION:
XS GIS Cut Line= 3
      2390524.98     13588524.99        2390725.       13588625.
      2390975.02       13588675.
#Sta/Elev= 30
  4772.4   470.7  4825.5  466.29  4831.1  466.17  4861.9  463.13  4884.3  461.71
  4906.6  460.16  4920.6  459.95  4937.3   458.2  4959.7  457.84  4965.3  456.82
  4973.7  452.96  4980.1  451.52  4980.3  451.02  4983.8  451.02  4984.1  451.52
  4993.2  454.68  4998.6  454.68  5016.4   457.1  5026.6  457.78    5047     457
  5077.6  457.79  5108.2  459.34  5159.2  458.64  5169.4  458.97  5179.6  462.37
  5189.8  467.91  5194.8  469.15    5200  470.43  5220.4  467.66    5251  467.58
#Mann= 5 ,-1 , 0
  4772.4     .12       0  4884.3      .1       0  4980.1     .05       0
  4984.1      .1       0  5194.8     .07       0
Bank Sta=4980.1,4984.1
XS Rating Curve= 0 ,0
Exp/Cntr=0.3,0.1

Type RM Length L Ch R = 1 ,76312   ,443,443,443
BEGIN DESCRIPTION:
BRUSHY CREEK 98.0
END DESCRIPTION:
XS GIS Cut Line= 3
      2390324.95       13588975.        2390525.       13588975.
      2390824.99     13589274.99
#Sta/Elev= 30
  4795.3     464    4838  460.65  4885.3  458.21  4905.3  456.09  4915.3   457.2
  4925.3  459.52  4935.3   459.4  4955.3  456.88  4965.3  453.53  4975.3  451.24
  4980.8  450.65  4985.3  450.17  4990.8   448.9  4991.1   448.4  4994.6   448.4
  4994.8   448.9  4998.9   448.9  5009.5   453.3  5051.9  453.46  5080.2  454.34
  5108.5  454.58  5126.2  455.34  5184.7  455.57  5249.9  456.96    5264  459.91
  5278.2  457.31  5292.3   455.4  5306.5  454.96  5348.9  459.05  5419.6  461.39
#Mann= 7 ,-1 , 0
  4795.3    .035       0    4838     .07       0  4980.8      .1       0
  4990.8     .05       0  4994.8      .1       0  5126.2    .035       0
  5184.7      .1       0
Bank Sta=4990.8,4994.8
XS Rating Curve= 0 ,0
Exp/Cntr=0.3,0.1

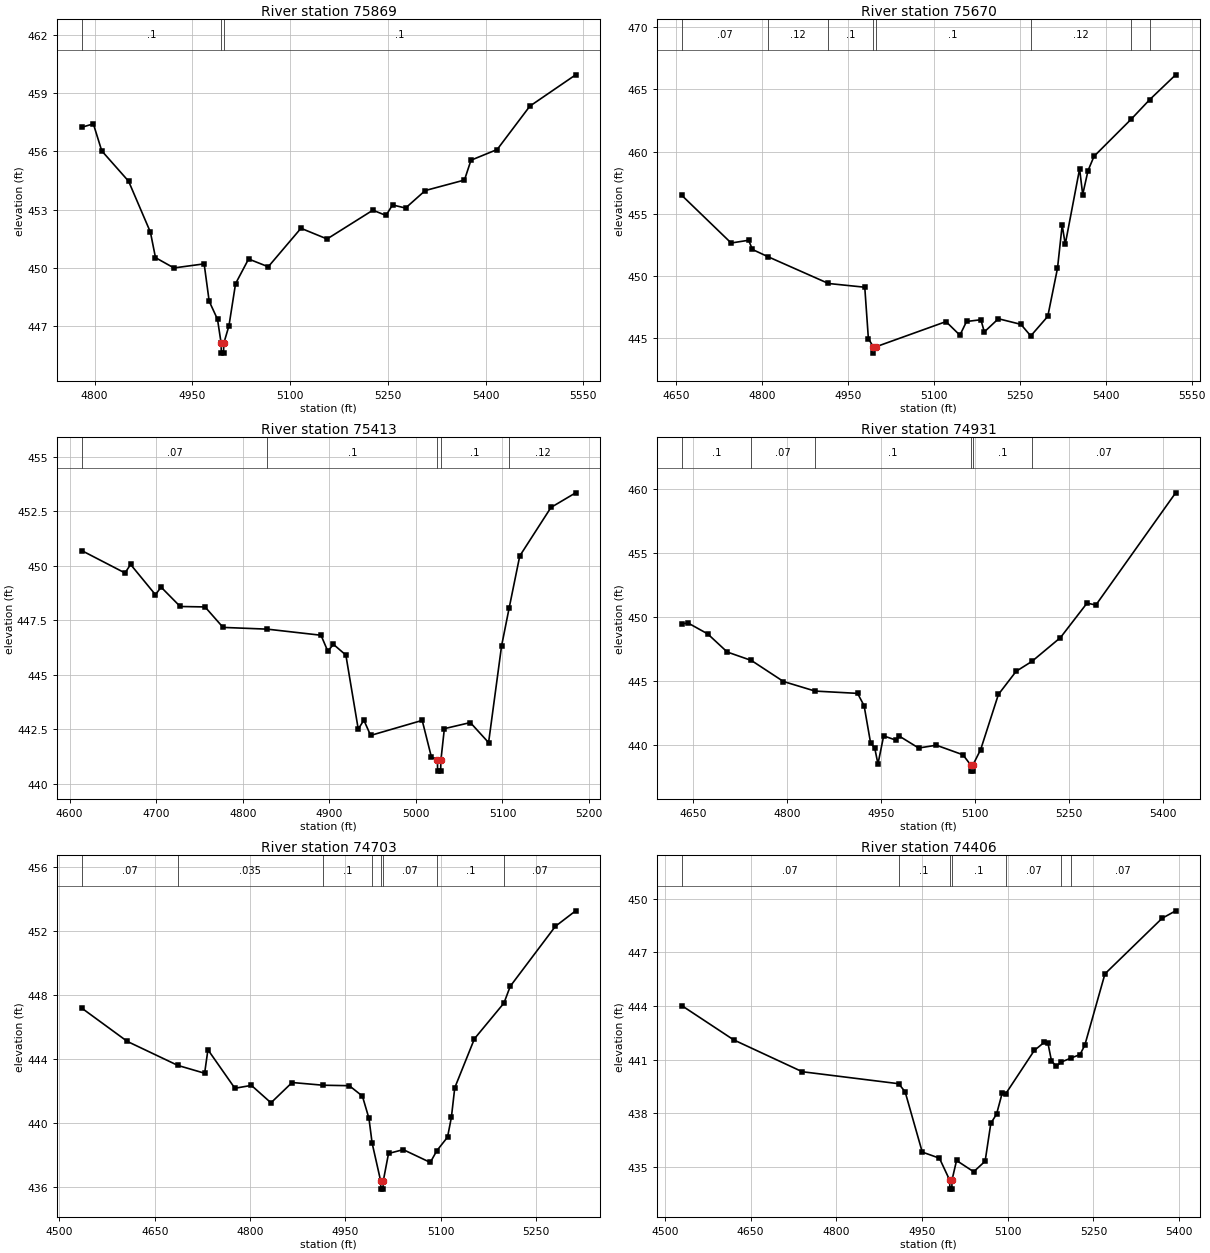
Type RM Length L Ch R = 1 ,75869   ,199,199,199
BEGIN DESCRIPTION:
BRUSHY CREEK 97.0
END DESCRIPTION:
XS GIS Cut Line= 3
        2390275.     13589125.02        2390325.       13589325.
      2390874.99       13589375.
#Sta/Elev= 30
    4780  457.24    4798  457.42  4810.9  456.03  4852.1  454.47  4885.6  451.85
  4893.4  450.54  4921.7  450.01  4968.1  450.22  4975.8   448.3  4988.6  447.37
  4994.2  446.13  4994.4  445.63  4997.9  445.63  4998.2  446.13  5006.2  447.04
  5016.3   449.2  5036.3  450.47  5066.5  450.07  5116.7  452.05  5156.8   451.5
  5227.1  452.98  5247.2  452.71  5257.3  453.25  5277.3  453.09  5307.5  453.99
  5367.7  454.53  5377.7  455.55  5417.9   456.1  5468.1  458.33  5538.4  459.94
#Mann= 3 ,-1 , 0
    4780      .1       0  4994.2     .05       0  4998.2      .1       0
Bank Sta=4994.2,4998.2
XS Rating Curve= 0 ,0
Exp/Cntr=0.3,0.1

Type RM Length L Ch R = 1 ,75670   ,257,257,257
BEGIN DESCRIPTION:
X18335
END DESCRIPTION:
XS GIS Cut Line= 2
      2390060.18     13589108.86      2390357.27     13589918.69
#Sta/Elev= 30
  4659.5   456.5    4746  452.66  4776.5  452.88  4783.2  452.14  4809.8  451.57
  4915.9  449.41  4979.3  449.11  4985.6  444.99  4994.2  444.32  4994.5  443.82
  4998.2  444.32  5121.1  446.35  5145.4  445.26    5157  446.36  5182.1   446.5
    5188  445.52  5212.6  446.58  5251.9  446.13  5269.1   445.2  5298.8  446.77
  5315.8  450.63    5324   454.1  5329.3  452.55  5354.4  458.61  5359.8  456.55
  5369.1  458.47  5379.6  459.62  5444.7  462.61  5476.6  464.16  5522.1  466.16
#Mann= 8 ,-1 , 0
  4659.5     .07       0  4809.8     .12       0  4915.9      .1       0
  4994.2     .05       0  4998.2      .1       0  5269.1     .12       0
  5444.7     .07       0  5476.6     .12       0
Bank Sta=4994.2,4998.2
XS Rating Curve= 0 ,0
Exp/Cntr=0.3,0.1

Type RM Length L Ch R = 1 ,75413   ,482,482,482
BEGIN DESCRIPTION:
BRUSHY CREEK 96.0
END DESCRIPTION:
XS GIS Cut Line= 3
      2389724.99     13589274.99        2389975.       13589575.
        2390075.     13589724.99
#Sta/Elev= 30
  4613.8   450.7  4663.9  449.67  4670.4  450.06  4699.1  448.67  4705.6  449.02
  4727.7  448.13  4756.4  448.11  4777.2  447.17  4828.3  447.09  4890.4  446.81
  4898.2  446.08  4904.8  446.39  4919.1   445.9  4933.4   442.5  4939.9  442.91
  4947.7  442.21  5007.3   442.9  5017.9  441.22  5024.9  441.07  5025.1  440.57
  5028.6  440.57  5028.9  441.07  5032.9  442.52  5062.9   442.8    5084  441.88
    5099  446.32  5107.7  448.05    5120  450.45  5156.1  452.68  5184.6  453.35
#Mann= 5 ,-1 , 0
  4613.8     .07       0  4828.3      .1       0  5024.9     .05       0
  5028.9      .1       0  5107.7     .12       0
Bank Sta=5024.9,5028.9
XS Rating Curve= 0 ,0
Exp/Cntr=0.3,0.1

Type RM Length L Ch R = 1 ,74931   ,228,228,228
BEGIN DESCRIPTION:
BRUSHY CREEK 95.0
END DESCRIPTION:
XS GIS Cut Line= 3
      2389625.01     13589324.96        2389525.       13589675.
      2389824.99     13589974.99
#Sta/Elev= 30
  4631.3  449.46  4641.7  449.52  4672.9  448.67  4704.1  447.25  4742.6  446.59
  4793.8  444.94  4844.3  444.19  4912.1  444.01  4922.5  443.04  4932.9  440.11
  4939.4  439.74  4944.6  438.48  4953.7  440.68  4973.2  440.35  4978.4  440.67
  5009.5  439.73  5037.8  439.95  5080.2   439.2  5092.3  438.42  5092.6  437.92
  5096.1  437.92  5096.3  438.42  5108.5  439.61  5136.8  443.93  5165.1  445.74
  5190.1  446.51  5235.8  448.38  5278.2  451.08  5292.3  450.93  5419.6  459.72
#Mann= 6 ,-1 , 0
  4631.3      .1       0  4742.6     .07       0  4844.3      .1       0
  5092.3     .05       0  5096.3      .1       0  5190.1     .07       0
Bank Sta=5092.3,5096.3
XS Rating Curve= 0 ,0
Exp/Cntr=0.3,0.1

Type RM Length L Ch R = 1 ,74703   ,297,297,297
BEGIN DESCRIPTION:
BRUSHY CREEK 94.0
END DESCRIPTION:
XS GIS Cut Line= 3
        2389275.     13589374.99      2389403.66     13589923.52
      2389475.02     13590125.04
#Sta/Elev= 30
    4535  447.18  4606.9  445.09  4686.3  443.59  4728.5   443.1  4733.7  444.57
  4776.1  442.16  4802.1  442.34  4832.9  441.25  4866.1  442.52  4914.8  442.35
  4956.1  442.32  4976.7  441.67    4987  440.28    4992  438.73  5005.5  436.35
  5005.7  435.85  5009.2  435.85  5009.5  436.35  5017.8  438.08    5041  438.32
  5083.5  437.52  5093.9  438.26  5110.6   439.1  5116.7  440.34    5122  442.19
    5153  445.26  5199.4  447.49  5209.3  448.54  5280.3  452.29  5312.2  453.26
#Mann= 8 ,-1 , 0
    4535     .07       0  4686.3    .035       0  4914.8      .1       0
    4992     .07       0  5005.5     .05       0  5009.5     .07       0
  5093.9      .1       0  5199.4     .07       0
Bank Sta=5005.5,5009.5
XS Rating Curve= 0 ,0
Exp/Cntr=0.3,0.1

Type RM Length L Ch R = 1 ,74406   ,364,364,364
BEGIN DESCRIPTION:
X18334
END DESCRIPTION:
XS GIS Cut Line= 3
      2389111.34     13589453.87      2389116.14     13590072.07
      2389264.67     13590268.52
#Sta/Elev= 30
  4529.3  444.03  4620.4  442.11  4740.4  440.33  4909.1  439.66  4920.4  439.21
  4950.4  435.84  4980.4   435.5  4998.4  434.27  4998.7  433.77  5002.2  433.77
  5002.4  434.27  5010.4  435.37  5040.4  434.74  5060.4  435.33  5070.4  437.45
  5080.4  437.96  5090.4  439.15  5096.3  439.09  5146.5  441.52  5163.7  441.97
  5170.3  441.93  5176.5  440.94  5184.8  440.63  5193.5  440.87  5210.4  441.09
  5226.5  441.29  5234.8  441.81  5270.1   445.8    5370   448.9  5393.8  449.32
#Mann= 7 ,-1 , 0
  4529.3     .07       0  4909.1      .1       0  4998.4     .05       0
  5002.4      .1       0  5096.3     .07       0  5193.5    .035       0
  5210.4     .07       0
Bank Sta=4998.4,5002.4
XS Rating Curve= 0 ,0
Exp/Cntr=0.3,0.1

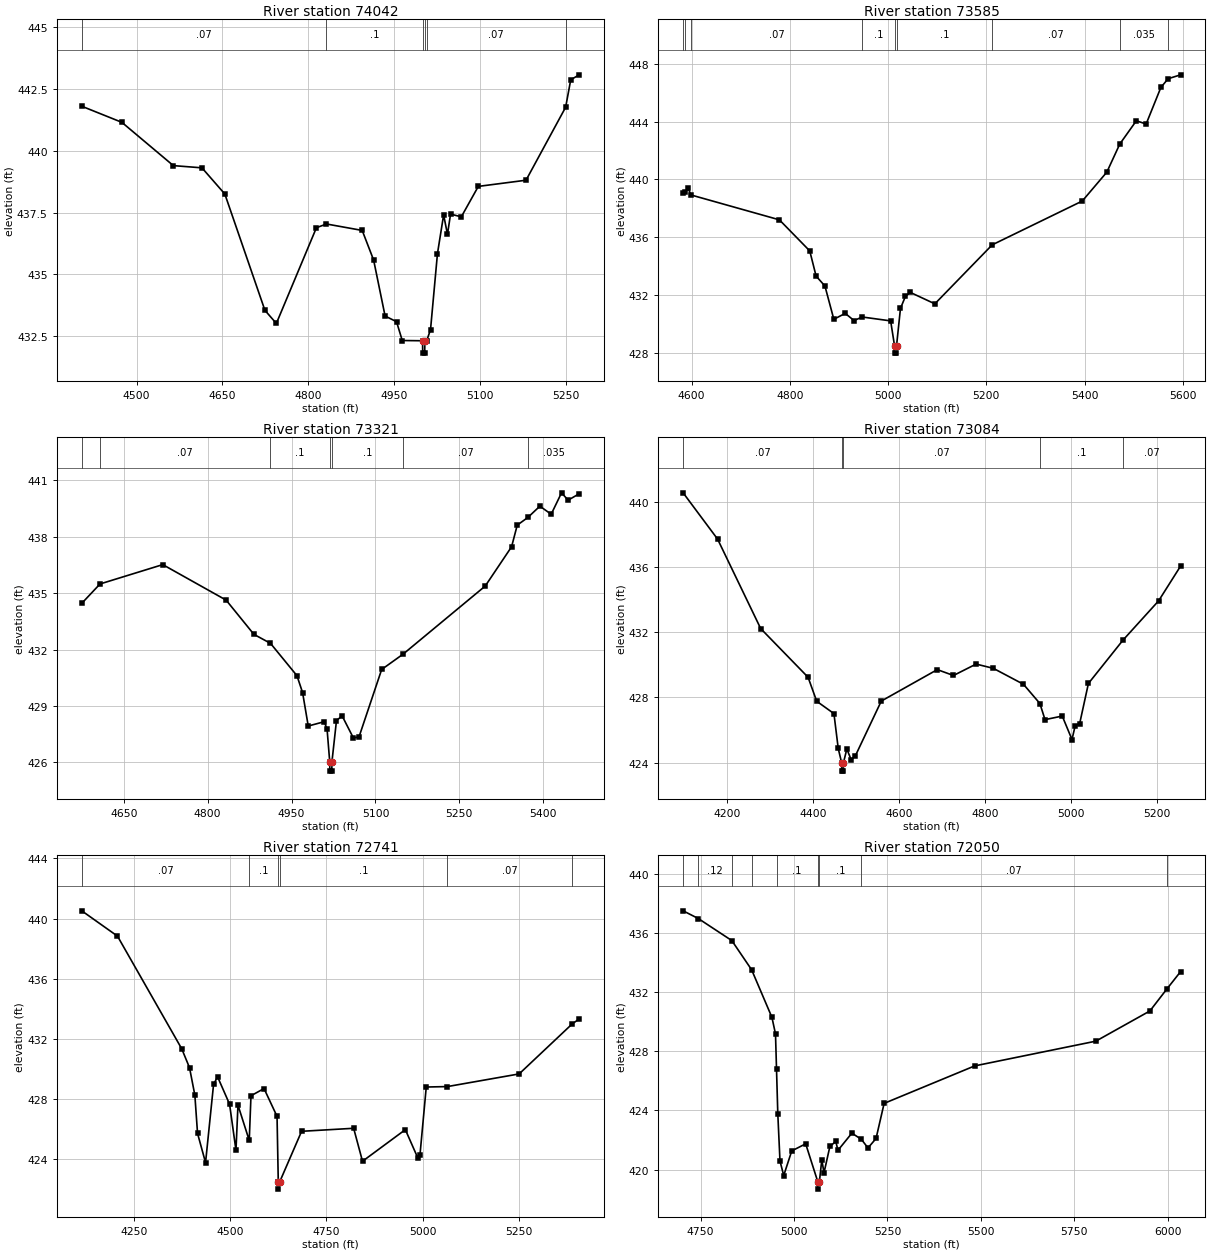
Type RM Length L Ch R = 1 ,74042   ,457,457,457
BEGIN DESCRIPTION:
BRUSHY CREEK 93.0
END DESCRIPTION:
XS GIS Cut Line= 3
        2388825.     13589525.04        2388825.       13590125.
      2389074.98     13590224.99
#Sta/Elev= 30
  4404.3   441.8  4474.3  441.15  4564.3   439.4  4614.3  439.31  4654.3  438.25
  4724.3  433.55  4744.3  433.02  4814.3  436.89  4831.9  437.04  4894.3  436.78
  4914.3  435.58  4934.3  433.32  4954.3  433.09  4964.3  432.33  4999.8  432.32
    5000  431.82  5003.5  431.82  5003.8  432.32    5007  432.32  5013.7  432.77
  5025.8  435.84  5036.6  437.41  5043.3  436.62  5048.7  437.44  5067.5  437.33
  5097.2  438.56  5180.6  438.81  5249.8  441.76  5258.7  442.87  5273.5  443.07
#Mann= 6 ,-1 , 0
  4404.3     .07       0  4831.9      .1       0  4999.8     .05       0
  5003.8      .1       0    5007     .07       0  5249.8    .035       0
Bank Sta=4999.8,5003.8
XS Rating Curve= 0 ,0
Exp/Cntr=0.3,0.1

Type RM Length L Ch R = 1 ,73585   ,264,264,264
BEGIN DESCRIPTION:
BRUSHY CREEK 92.0
END DESCRIPTION:
XS GIS Cut Line= 3
      2388474.99     13589874.98        2388575.       13590275.
      2389174.96       13590275.
#Sta/Elev= 30
  4582.9  439.06  4587.5  439.14  4593.2  439.38  4598.9  438.93  4778.8  437.21
  4840.6  435.06  4853.5  433.32  4871.5  432.63  4889.6  430.33  4912.8  430.74
  4930.8  430.24  4947.2  430.49  5005.2  430.22  5013.2  428.49  5013.5  427.99
    5017  427.99  5017.2  428.49  5025.2  431.08  5035.2  431.91  5045.2  432.19
  5095.2   431.4  5211.9  435.48  5395.2  438.51  5445.2  440.51  5471.5  442.45
  5505.2  444.06  5525.2  443.84  5555.2  446.37  5569.9  446.97  5595.2  447.24
#Mann= 9 ,-1 , 0
  4582.9     .07       0  4587.5     .12       0  4598.9     .07       0
  4947.2      .1       0  5013.2     .05       0  5017.2      .1       0
  5211.9     .07       0  5471.5    .035       0  5569.9     .07       0
Bank Sta=5013.2,5017.2
XS Rating Curve= 0 ,0
Exp/Cntr=0.3,0.1

Type RM Length L Ch R = 1 ,73321   ,237,237,237
BEGIN DESCRIPTION:
X18333
END DESCRIPTION:
XS GIS Cut Line= 3
      2388229.61     13590306.89      2388497.96     13590527.32
      2389034.64     13590603.99
#Sta/Elev= 30
  4574.9  434.46  4607.5  435.49  4719.7  436.52    4833  434.63  4882.6  432.81
  4912.3  432.33  4959.6  430.61  4969.7  429.71  4979.8  427.93  5008.4  428.16
  5013.5  427.76  5018.2  426.03  5018.4  425.53  5021.9  425.53  5022.2  426.03
  5030.3  428.22  5040.4  428.47  5060.6  427.29  5070.7  427.36  5111.1  430.94
  5149.6  431.76  5296.3  435.38  5343.4  437.47  5353.5  438.62  5372.5  439.03
    5394  439.63  5414.2   439.2  5432.7  440.34  5444.5  439.95  5464.3  440.29
#Mann= 7 ,-1 , 0
  4574.9     .12       0  4607.5     .07       0  4912.3      .1       0
  5018.2     .05       0  5022.2      .1       0  5149.6     .07       0
  5372.5    .035       0
Bank Sta=5018.2,5022.2
XS Rating Curve= 0 ,0
Exp/Cntr=0.3,0.1

Type RM Length L Ch R = 1 ,73084   ,343,343,343
BEGIN DESCRIPTION:
BRUSHY CREEK 91.0
END DESCRIPTION:
XS GIS Cut Line= 3
      2387674.98       13590725.        2388575.       13590775.
      2388825.04     13590825.01
#Sta/Elev= 30
  4098.2  440.56  4178.3  437.72  4278.5  432.23  4388.7  429.24  4408.7  427.77
  4448.8  427.01  4458.8  424.87  4466.8  423.98    4467  423.48  4470.5  423.48
  4470.8  423.98  4478.8  424.84  4488.8  424.18  4498.8  424.43  4558.9  427.78
  4689.1  429.71  4726.7  429.35  4779.3  430.05  4819.3  429.79  4889.4  428.81
  4927.6  427.63  4939.5  426.64  4979.6  426.86  5002.2  425.42  5009.8  426.28
    5020  426.39  5040.4  428.86  5120.8  431.52  5203.6  433.93  5254.6  436.06
#Mann= 5 ,-1 , 0
  4098.2     .07       0  4466.8     .05       0  4470.8     .07       0
  4927.6      .1       0  5120.8     .07       0
Bank Sta=4466.8,4470.8
XS Rating Curve= 0 ,0
Exp/Cntr=0.3,0.1

Type RM Length L Ch R = 1 ,72741   ,691,691,691
BEGIN DESCRIPTION:
X18332
END DESCRIPTION:
XS GIS Cut Line= 4
      2387625.82     13590810.06      2388315.86     13591006.53
      2388614.68     13591161.76      2388847.99     13591115.25
#Sta/Elev= 30
  4114.4  440.51  4207.1  438.83  4374.2  431.34  4394.3  430.09  4408.1  428.27
  4415.1  425.73  4435.9  423.79  4456.7  428.98  4467.1  429.49  4498.3  427.67
  4514.9  424.61  4520.1  427.61  4549.4  425.26  4553.9  428.23  4587.8  428.71
  4621.6  426.86  4624.8  422.53  4625.1  422.03  4628.8  422.53  4685.4  425.87
  4820.6  426.07  4843.6  423.88  4954.9  425.98  4987.1  424.11  4992.8  424.28
  5009.2  428.81  5064.1  428.84  5250.5  429.68  5388.3     433  5406.5  433.33
#Mann= 6 ,-1 , 0
  4114.4     .07       0  4549.4      .1       0  4624.8     .05       0
  4628.8      .1       0  5064.1     .07       0  5388.3    .035       0
Bank Sta=4624.8,4628.8
XS Rating Curve= 0 ,0
Exp/Cntr=0.3,0.1

Type RM Length L Ch R = 1 ,72050   ,380,380,380
BEGIN DESCRIPTION:
X18331
END DESCRIPTION:
XS GIS Cut Line= 3
      2387630.61     13590963.41       2388172.1     13591274.89
      2388865.36     13591136.08
#Sta/Elev= 30
    4703  437.48  4743.6  436.96  4833.4  435.47  4886.4   433.5  4940.7  430.29
  4950.3  429.17    4953  426.81  4956.5  423.75  4962.3  420.59  4972.3  419.61
  4993.8  421.27  5031.1  421.75  5063.5  419.19  5063.8  418.69  5067.8  419.19
  5074.3  420.67  5080.1  419.79  5095.9  421.57  5111.7  421.91  5117.5  421.31
  5154.8  422.47  5180.3  422.05  5197.9  421.47  5219.5  422.11  5241.1  424.48
  5483.6  427.01  5807.9  428.68  5952.7  430.72    5998   432.2  6034.7  433.37
#Mann= 9 ,-1 , 0
    4703     .07       0  4743.6     .12       0  4833.4     .07       0
  4886.4     .12       0    4953      .1       0  5063.5     .05       0
  5067.8      .1       0  5180.3     .07       0    5998    .035       0
Bank Sta=5063.5,5067.8
XS Rating Curve= 0 ,0
Exp/Cntr=0.3,0.1

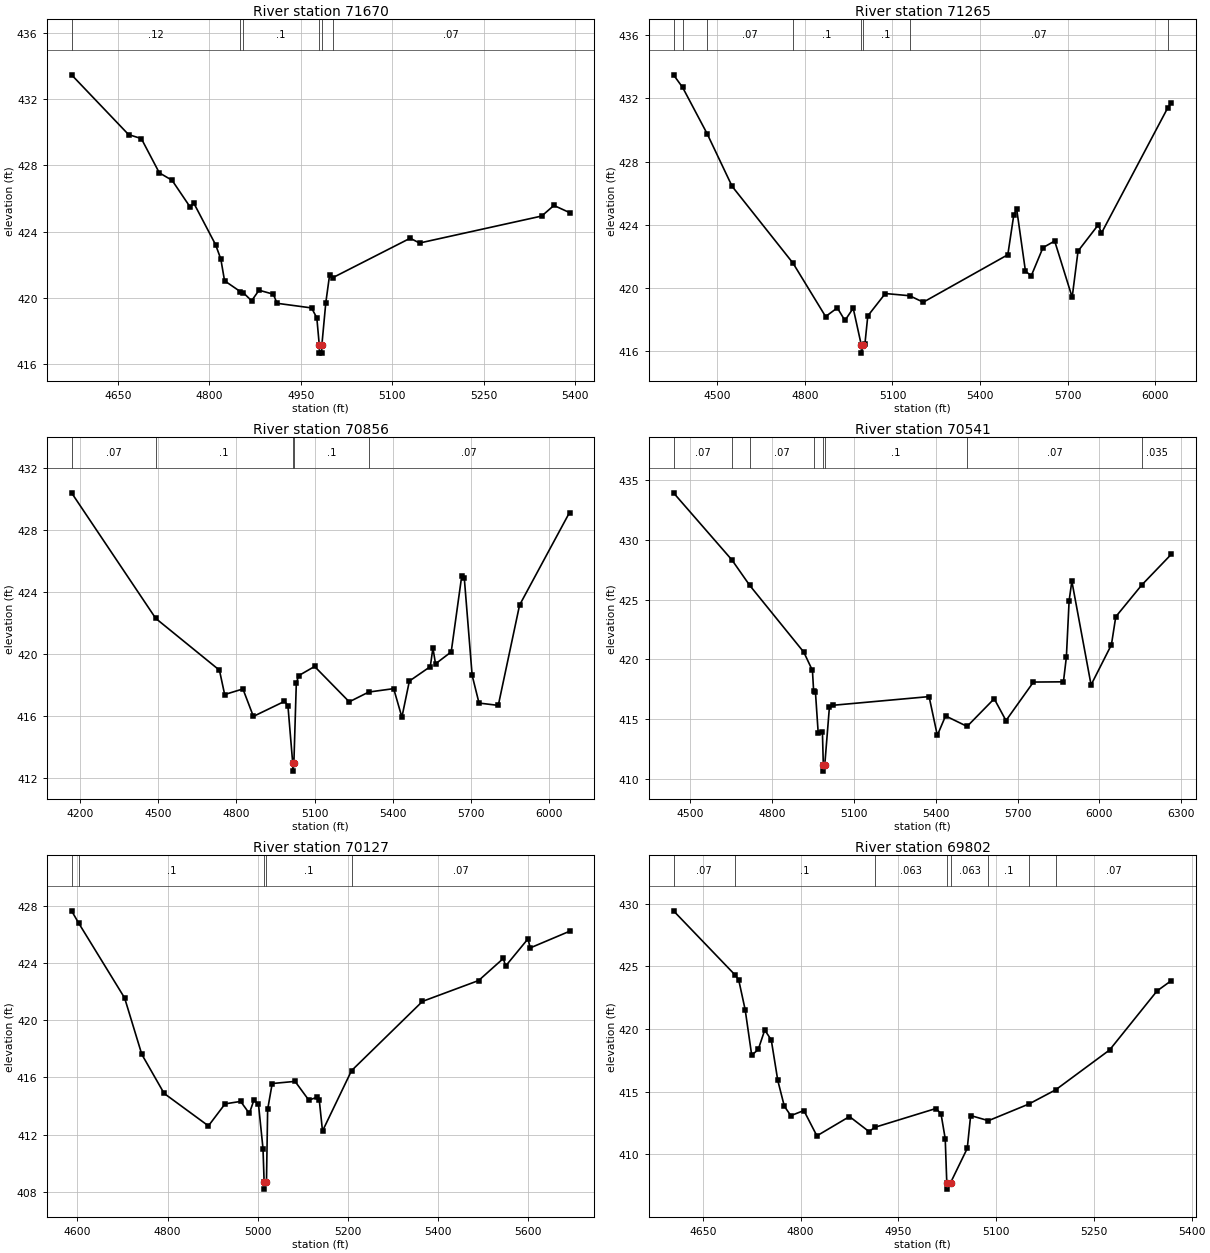
Type RM Length L Ch R = 1 ,71670   ,405,405,405
BEGIN DESCRIPTION:
BRUSHY CREEK 90.0
END DESCRIPTION:
XS GIS Cut Line= 3
      2387674.99     13591124.98        2387925.       13591475.
      2388310.55     13591490.51
#Sta/Elev= 30
  4574.4  433.47  4667.8  429.86  4688.7  429.62  4718.2  427.55  4739.1   427.1
  4768.6  425.49  4774.7  425.72  4810.4  423.21    4819  422.34  4825.1  421.03
  4851.2  420.37  4855.5  420.32  4869.4  419.82  4881.6  420.46    4905  420.22
  4911.1  419.67  4967.7  419.39  4976.3  418.79  4980.3  417.16  4980.6  416.66
  4984.3  416.66  4984.6  417.16    4991   419.7  4997.2  421.37  5002.6  421.22
  5129.3   423.6  5144.6  423.31  5344.8  424.94  5364.8  425.58  5390.4  425.15
#Mann= 6 ,-1 , 0
  4574.4     .12       0  4851.2     .07       0  4855.5      .1       0
  4980.3     .05       0  4984.6      .1       0  5002.6     .07       0
Bank Sta=4980.3,4984.6
XS Rating Curve= 0 ,0
Exp/Cntr=0.3,0.1

Type RM Length L Ch R = 1 ,71265   ,409,409,409
BEGIN DESCRIPTION:
BRUSHY CREEK 89.0
END DESCRIPTION:
XS GIS Cut Line= 3
        2387575.     13591125.04      2387621.01     13591725.34
      2388725.03       13591775.
#Sta/Elev= 30
  4349.2   433.5  4380.5   432.7  4464.4  429.77  4550.1  426.43  4758.8  421.56
  4870.7  418.17  4910.8  418.72    4937  417.92  4965.3   418.7  4993.2  416.35
  4993.4  415.85  4997.5  416.35  5005.3   416.4  5015.3  418.21  5075.4  419.63
  5158.7  419.49  5205.5  419.08  5495.4  422.09  5515.8  424.61  5525.8  424.98
  5555.9  421.04  5575.9  420.76  5615.9  422.54    5656  422.96    5716  419.39
  5736.1  422.32  5806.1     424  5816.1  423.45  6042.9  431.38  6056.4  431.74
#Mann= 8 ,-1 , 0
  4349.2     .07       0  4380.5     .12       0  4464.4     .07       0
  4758.8      .1       0  4993.2     .05       0  4997.5      .1       0
  5158.7     .07       0  6042.9     .05       0
Bank Sta=4993.2,4997.5
XS Rating Curve= 0 ,0
Exp/Cntr=0.3,0.1

Type RM Length L Ch R = 1 ,70856   ,315,315,315
BEGIN DESCRIPTION:
X18330
END DESCRIPTION:
XS GIS Cut Line= 4
      2387434.12     13591188.61      2387458.08     13591917.02
      2387692.89     13591979.32      2388627.37     13591917.02
#Sta/Elev= 30
  4168.6  430.42  4491.2  422.32  4735.3  418.98  4755.3  417.41  4825.3  417.77
  4865.4     416  4984.6  416.97  4997.7   416.7  5016.2  412.97  5016.5  412.47
  5020.5  412.97  5029.9  418.14  5039.1  418.63    5100  419.22  5232.7  416.94
  5307.4  417.57    5403  417.79  5434.5  415.95  5463.2  418.28  5543.3  419.21
  5553.4  420.41  5563.4  419.39  5623.5  420.16  5663.6  425.03  5673.6  424.93
  5703.7  418.65  5730.1  416.86  5803.9  416.71  5885.5  423.18  6076.9  429.15
#Mann= 5 ,-1 , 0
  4168.6     .07       0  4491.2      .1       0  5016.2     .05       0
  5020.5      .1       0  5307.4     .07       0
Bank Sta=5016.2,5020.5
XS Rating Curve= 0 ,0
Exp/Cntr=0.3,0.1

Type RM Length L Ch R = 1 ,70541   ,414,414,414
BEGIN DESCRIPTION:
X18329
END DESCRIPTION:
XS GIS Cut Line= 3
      2386844.65     13592372.29      2387601.84     13592103.92
      2388617.76     13591984.11
#Sta/Elev= 30
  4438.2  433.96  4652.5  428.33    4718  426.19    4916   420.6  4947.8  419.06
  4952.1  417.35  4958.8  417.24    4969  413.79  4984.4  413.87  4987.7  411.12
  4988.1  410.62  4992.9  411.12    5010  415.98  5022.1  416.14  5375.6  416.87
  5405.8  413.62    5436  415.25  5515.1  414.37  5614.4  416.69  5657.6  414.86
  5758.3  418.09  5868.3  418.11  5879.1  420.18  5889.2  424.92  5899.2  426.55
  5969.7  417.85  6044.3  421.22  6060.3  423.57  6155.6  426.23  6264.5  428.82
#Mann= 8 ,-1 , 0
  4438.2     .07       0  4652.5     .12       0    4718     .07       0
  4952.1      .1       0  4987.7     .05       0  4992.9      .1       0
  5515.1     .07       0  6155.6    .035       0
Bank Sta=4987.7,4992.9
XS Rating Curve= 0 ,0
Exp/Cntr=0.3,0.1

Type RM Length L Ch R = 1 ,70127   ,325,325,325
BEGIN DESCRIPTION:
BRUSHY CREEK 88.0
END DESCRIPTION:
XS GIS Cut Line= 3
      2387324.98     13592475.01      2387649.76     13592300.39
      2388374.96     13592175.01
#Sta/Elev= 30
  4586.9  427.64  4602.7  426.78  4704.6  421.55  4742.7  417.61  4792.2  414.88
  4890.5  412.61  4927.5  414.15    4962  414.32  4981.3  413.48  4991.4  414.41
  5001.6  414.11  5011.6  411.02  5014.1  408.69  5014.5  408.19  5019.3  408.69
  5021.9  413.76    5032  415.57  5082.7  415.72  5113.2  414.41  5131.2  414.61
  5136.3  414.45  5143.6  412.25    5208  416.47  5365.3  421.31    5490  422.77
  5544.7  424.31  5549.8  423.78  5599.4  425.68  5604.5  425.05  5691.6  426.21
#Mann= 5 ,-1 , 0
  4586.9     .07       0  4602.7      .1       0  5014.1     .05       0
  5019.3      .1       0    5208     .07       0
Bank Sta=5014.1,5019.3
XS Rating Curve= 0 ,0
Exp/Cntr=0.3,0.1

Type RM Length L Ch R = 1 ,69802   ,444,444,444
BEGIN DESCRIPTION:
BRUSHY CREEK 87.0
END DESCRIPTION:
XS GIS Cut Line= 3
      2387324.96       13592575.        2387725.       13592575.
      2388074.95     13592475.01
#Sta/Elev= 30
    4605  429.43    4699  424.34    4705  423.93    4715  421.53    4725  417.91
    4735  418.37    4745  419.92    4755  419.13    4765   415.9    4775  413.85
    4785  413.09    4805   413.5    4825  411.48    4875  413.02    4905  411.82
  4913.8  412.16  5007.6  413.66  5015.4  413.25  5021.9  411.25  5024.3  407.73
  5024.7  407.23    5030  407.73  5055.7  410.48  5060.9   413.1  5088.2  412.69
  5150.3  414.02  5191.3  415.15  5274.1  418.33  5346.9  423.04    5369  423.87
#Mann= 8 ,-1 , 0
    4605     .07       0    4699      .1       0  4913.8    .063       0
  5024.3    .063       0    5030    .063       0  5088.2      .1       0
  5150.3    .035       0  5191.3     .07       0
Bank Sta=5024.3,5030
XS Rating Curve= 0 ,0
Exp/Cntr=0.3,0.1

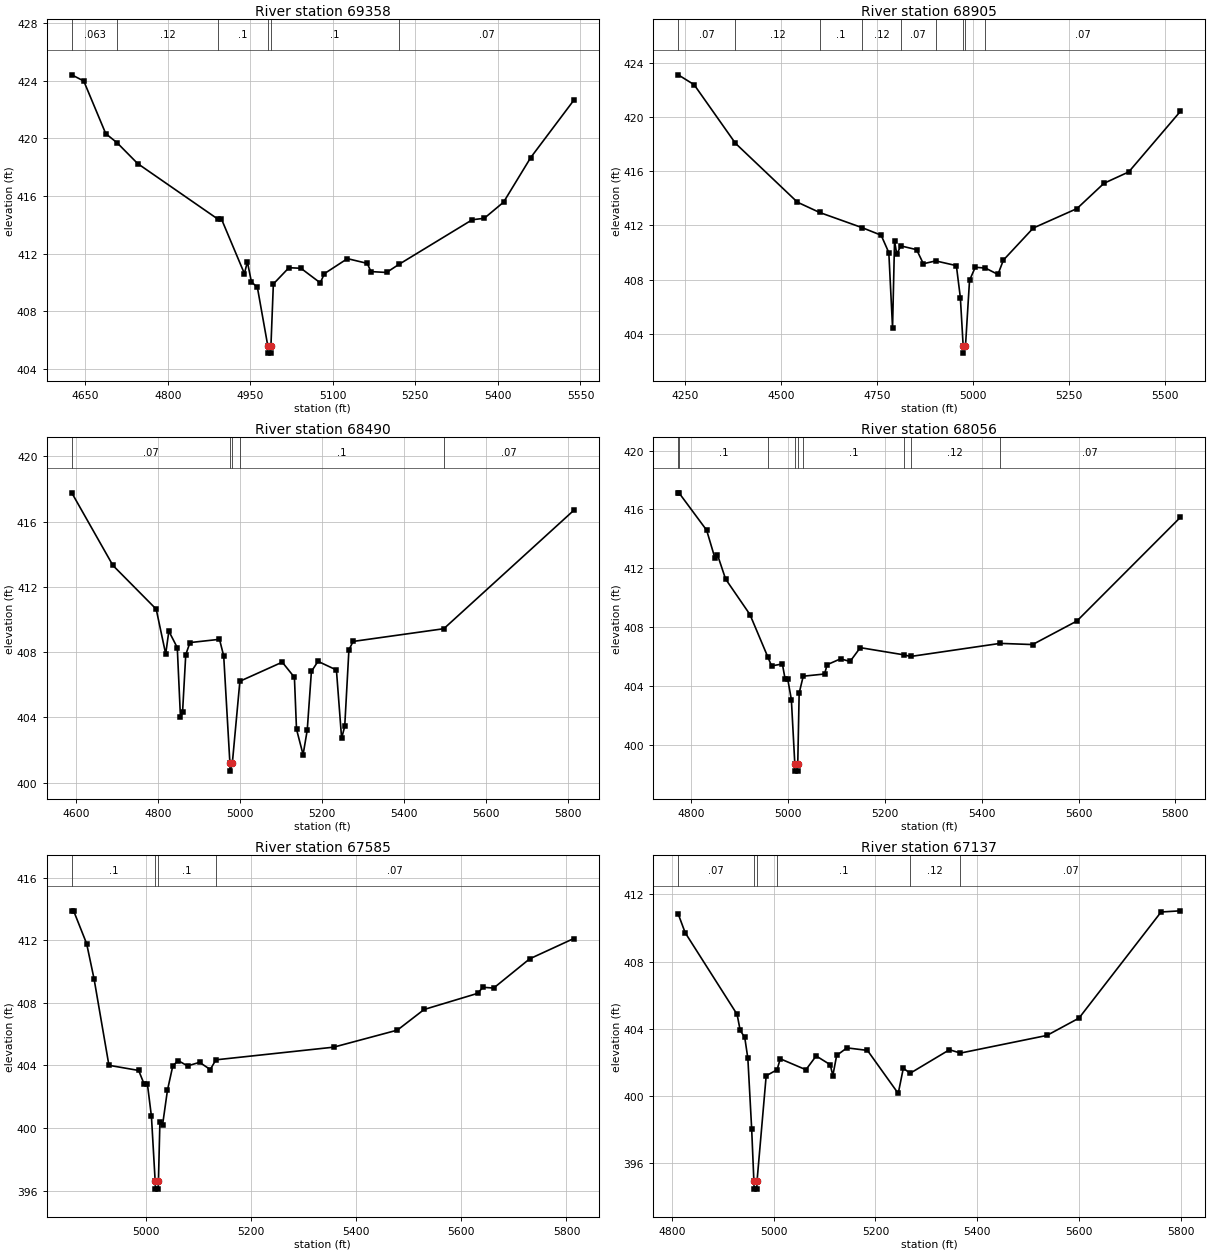
Type RM Length L Ch R = 1 ,69358   ,453,453,453
BEGIN DESCRIPTION:
BRUSHY CREEK 86.0
END DESCRIPTION:
XS GIS Cut Line= 3
      2387424.99       13592825.        2387775.       13592975.
        2388125.       13592575.
#Sta/Elev= 30
  4625.7  424.41  4647.5  423.98  4687.4  420.33  4708.4  419.68  4745.4  418.25
  4891.3  414.39  4897.7   414.4  4939.4  410.61  4944.8  411.43  4952.1  410.04
    4963  409.65  4981.9  405.59  4982.3  405.09  4987.1  405.09  4987.6  405.59
    4992  409.89  5020.3  411.02  5042.1  410.98  5077.2  409.97  5084.8  410.61
  5126.6  411.65  5162.6  411.32  5169.3  410.75  5197.7  410.69  5220.1  411.25
  5353.4  414.35  5375.2  414.45  5410.3  415.57  5459.7  418.67    5538  422.65
#Mann= 6 ,-1 , 0
  4625.7    .063       0  4708.4     .12       0  4891.3      .1       0
  4981.9     .05       0  4987.6      .1       0  5220.1     .07       0
Bank Sta=4981.9,4987.6
XS Rating Curve= 0 ,0
Exp/Cntr=0.3,0.1

Type RM Length L Ch R = 1 ,68905   ,415,415,415
BEGIN DESCRIPTION:
BRUSHY CREEK 85.0
END DESCRIPTION:
XS GIS Cut Line= 3
      2387325.02       13593025.        2388075.       13593225.
        2388475.       13592875.
#Sta/Elev= 30
  4231.9  423.14  4273.3  422.41  4380.8  418.08  4542.4  413.72  4600.3  412.96
  4710.7  411.84  4760.4  411.28  4780.4  409.99  4790.1  404.43  4795.3  410.85
  4801.1  409.88  4811.7  410.49  4852.8  410.21  4870.3  409.17  4902.5  409.38
  4956.3  409.03  4966.7  406.67  4974.1  403.06  4974.6  402.56    4980  403.06
  4990.6  407.94  5005.5  408.91    5032  408.85  5064.6  408.38  5078.8  409.44
  5156.6  411.81  5270.5  413.25  5340.8  415.12  5405.3  415.96  5539.6  420.43
#Mann= 9 ,-1 , 0
  4231.9     .07       0  4380.8     .12       0  4600.3      .1       0
  4710.7     .12       0  4811.7     .07       0  4902.5      .1       0
  4974.1     .05       0    4980      .1       0    5032     .07       0
Bank Sta=4974.1,4980
XS Rating Curve= 0 ,0
Exp/Cntr=0.3,0.1

Type RM Length L Ch R = 1 ,68490   ,434,434,434
BEGIN DESCRIPTION:
BRUSHY CREEK 84.0
END DESCRIPTION:
XS GIS Cut Line= 3
      2387474.96     13593575.01        2387875.       13593475.
      2388675.01       13593325.
#Sta/Elev= 30
  4588.6  417.77  4689.1  413.32  4794.8  410.64    4818  407.89  4825.7  409.29
  4846.3  408.28  4854.1     404  4859.2  404.33    4867  407.85  4877.3  408.59
  4949.4  408.79  4959.7  407.77  4974.8  401.21  4975.3  400.71  4980.8  401.21
  4999.2  406.22  5102.7  407.39  5132.4  406.46  5137.5  403.28  5153.6  401.72
  5163.7  403.22  5173.9  406.82    5190  407.44    5235  406.91  5247.7  402.72
  5255.3  403.46  5265.5  408.14  5275.7  408.66  5497.3  409.44  5814.9   416.7
#Mann= 5 ,-1 , 0
  4588.6     .07       0  4974.8     .05       0  4980.8     .07       0
  4999.2      .1       0  5497.3     .07       0
Bank Sta=4974.8,4980.8
XS Rating Curve= 0 ,0
Exp/Cntr=0.3,0.1

Type RM Length L Ch R = 1 ,68056   ,471,471,471
BEGIN DESCRIPTION:
BRUSHY CREEK 83.0
END DESCRIPTION:
XS GIS Cut Line= 3
      2387624.98     13593875.01        2387825.       13593775.
      2388625.03       13593925.
#Sta/Elev= 30
  4772.6  417.13  4774.1  417.13  4831.3  414.59  4848.1  412.73  4853.7  412.92
  4870.5  411.27  4920.8  408.86  4957.7  405.98  4965.5  405.37  4987.8   405.5
  4993.4  404.49  4998.8  404.49  5006.4  403.08  5013.5  398.72    5014  398.22
  5019.1  398.22  5019.6  398.72  5022.5  403.52  5030.9  404.67  5075.1  404.82
  5080.2  405.45  5108.1  405.85  5127.7  405.67  5148.8  406.61  5239.2  406.12
  5252.7  406.01  5437.8   406.9  5504.9  406.82  5596.5  408.42  5810.2  415.46
#Mann= 9 ,-1 , 0
  4772.6     .07       0  4774.1      .1       0  4957.7     .07       0
  5013.5     .05       0  5019.6     .07       0  5030.9      .1       0
  5239.2     .07       0  5252.7     .12       0  5437.8     .07       0
Bank Sta=5013.5,5019.6
XS Rating Curve= 0 ,0
Exp/Cntr=0.3,0.1

Type RM Length L Ch R = 1 ,67585   ,448,448,448
BEGIN DESCRIPTION:
BRUSHY CREEK 82.0
END DESCRIPTION:
XS GIS Cut Line= 3
        2387625.       13594075.        2387725.       13594175.
      2388525.03     13594325.01
#Sta/Elev= 30
  4858.6  413.89  4862.1  413.89  4886.9  411.79    4901  409.54  4929.3  404.01
  4985.9  403.68  4996.5  402.79  5002.6  402.79  5010.2  400.74  5017.3  396.59
  5017.8  396.09    5023  396.09  5023.5  396.59  5026.3  400.36  5031.4   400.2
  5040.7  402.42  5050.9  403.98  5061.1  404.31  5078.9  403.97  5101.8   404.2
  5122.1  403.74  5132.9  404.36    5357  405.17  5478.2  406.26  5529.1  407.58
  5630.8  408.61    5641     409  5661.4  408.95    5730  410.82    5814  412.12
#Mann= 4 ,-1 , 0
  4858.6      .1       0  5017.3     .05       0  5023.5      .1       0
  5132.9     .07       0
Bank Sta=5017.3,5023.5
XS Rating Curve= 0 ,0
Exp/Cntr=0.3,0.1

Type RM Length L Ch R = 1 ,67137   ,462,462,462
BEGIN DESCRIPTION:
BRUSHY CREEK 81.0
END DESCRIPTION:
XS GIS Cut Line= 3
      2387374.97     13594324.96        2387475.       13594475.
      2388275.05     13594575.01
#Sta/Elev= 30
  4812.6  410.83  4826.2  409.72  4928.3  404.86  4934.3  403.91  4943.3  403.49
  4949.4  402.25  4956.9  398.05  4961.2  394.97  4961.7  394.47    4967  394.47
  4967.5  394.97  4985.4  401.21  5006.8  401.57  5013.1  402.22  5063.5  401.57
  5083.6  402.39  5111.3  401.87  5116.4  401.22  5123.9  402.42  5144.1  402.87
  5184.4  402.72  5244.9  400.16  5254.9  401.66  5268.3  401.36  5345.6  402.76
  5367.1  402.56  5537.1  403.61  5600.1  404.64  5761.4  410.95  5799.2  411.02
#Mann= 6 ,-1 , 0
  4812.6     .07       0  4961.2     .05       0  4967.5     .07       0
  5006.8      .1       0  5268.3     .12       0  5367.1     .07       0
Bank Sta=4961.2,4967.5
XS Rating Curve= 0 ,0
Exp/Cntr=0.3,0.1