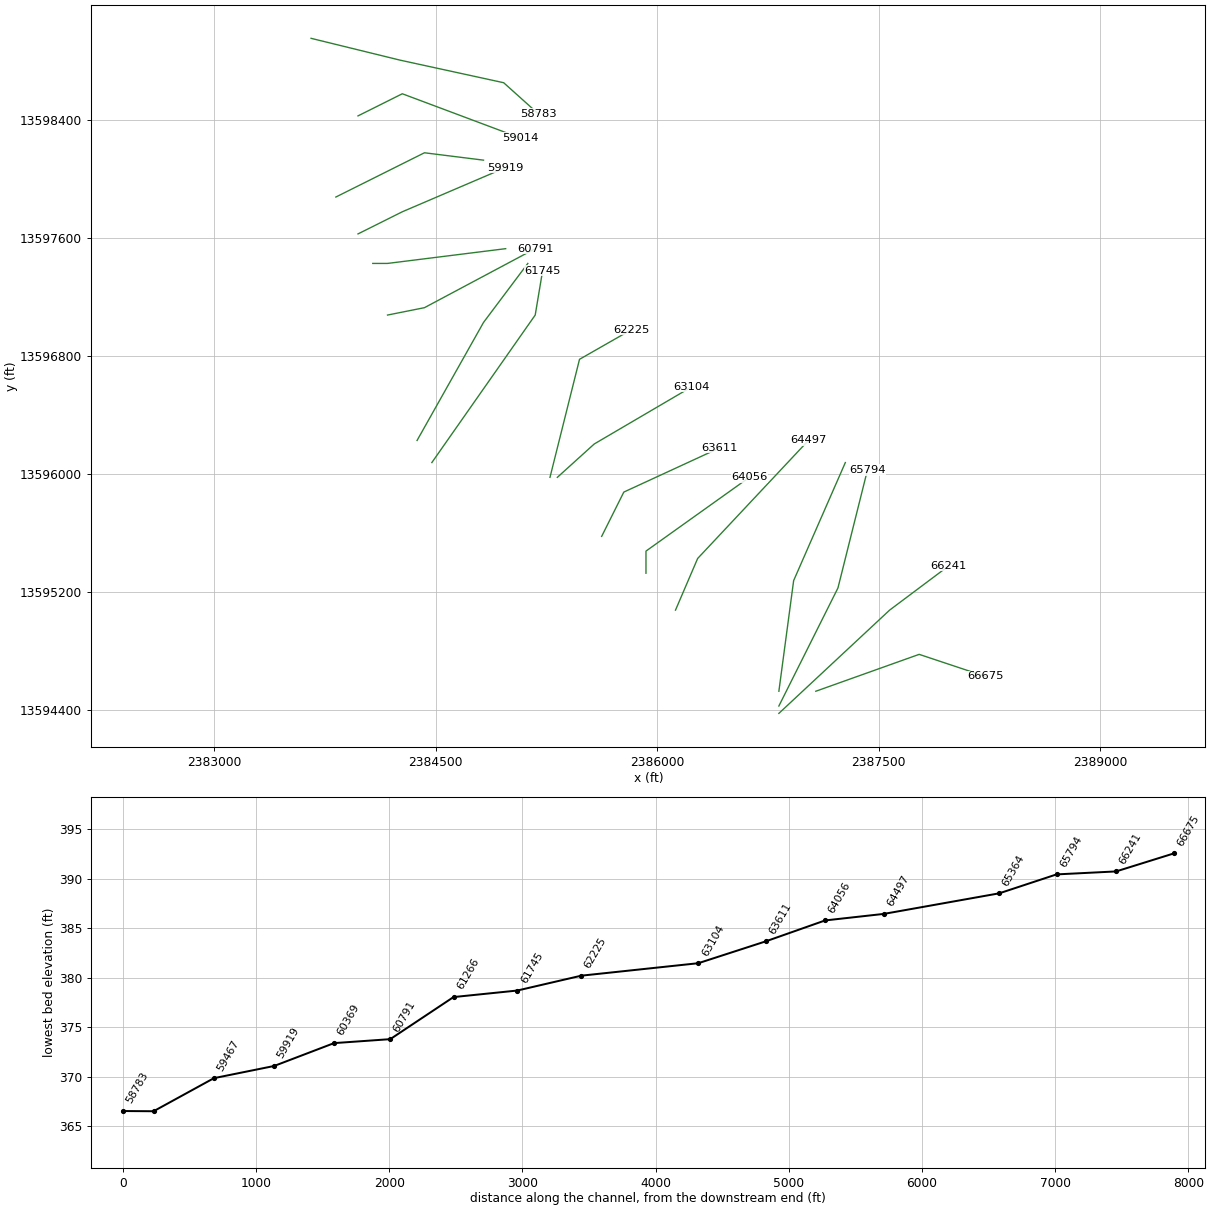
HEC-RAS study BRUSHY CREEK.prj: BRUSHY CREEK Base Level Engineering

--- BRUSHY CREEK.g01 (geometry) --- (continued)

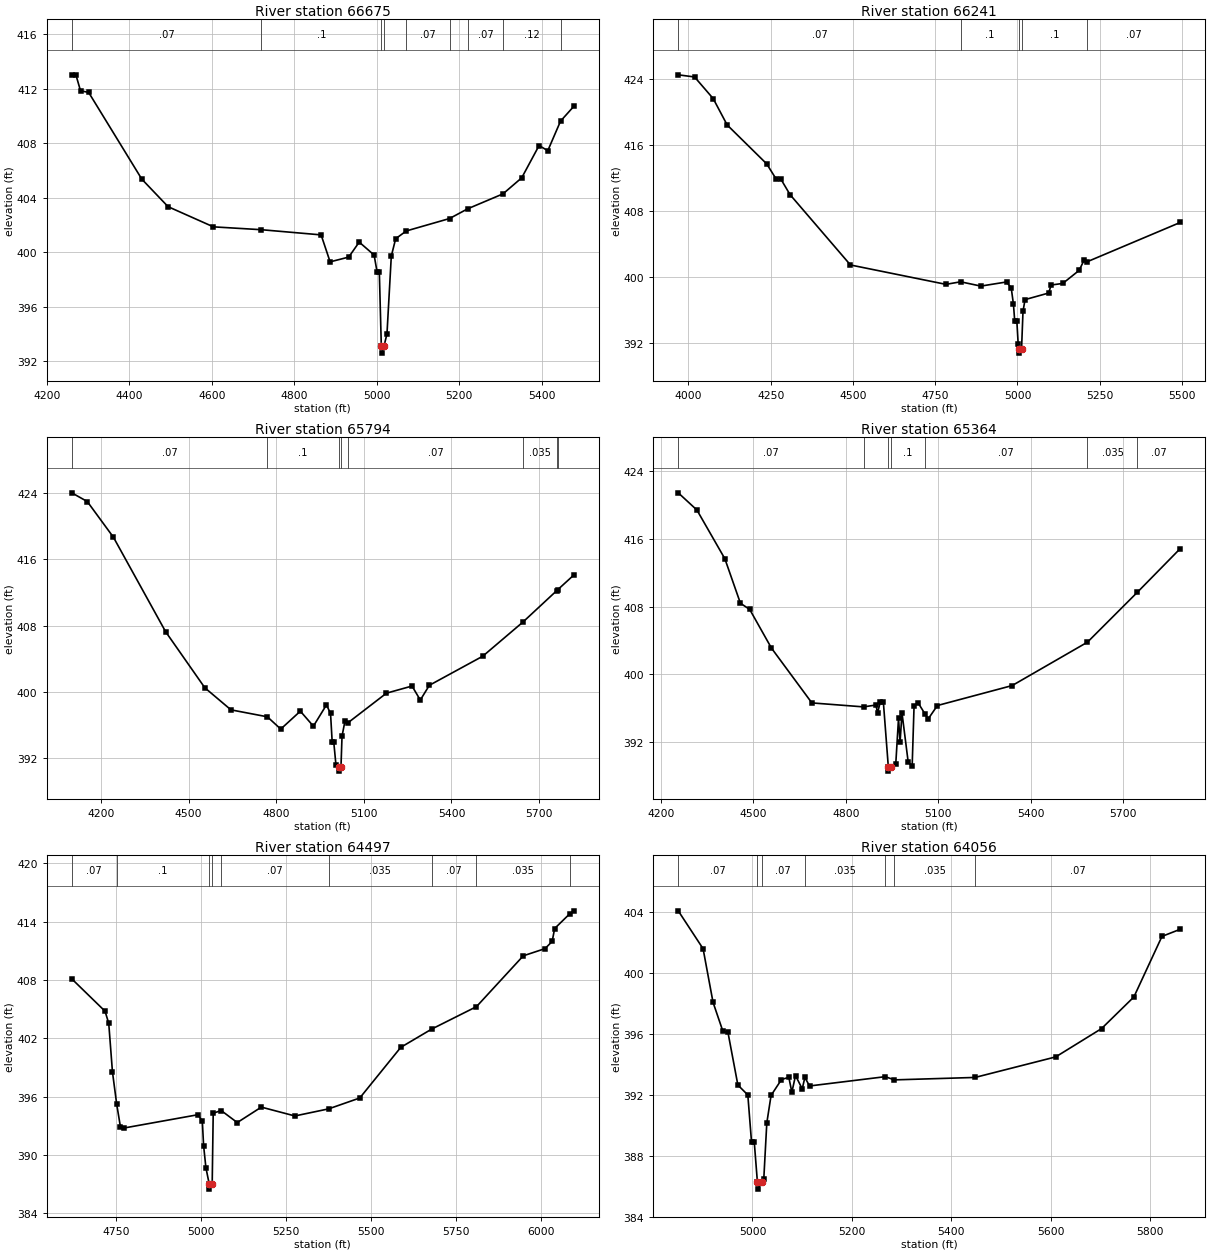
Type RM Length L Ch R = 1 ,66675   ,434,434,434
BEGIN DESCRIPTION:
BRUSHY CREEK 80.0
END DESCRIPTION:
XS GIS Cut Line= 3
        2387075.       13594525.        2387775.       13594775.
      2388224.95     13594625.02
#Sta/Elev= 30
  4260.5  413.01  4270.6     413  4281.7  411.84  4301.4  411.72  4430.4  405.35
  4494.1  403.33    4604  401.85  4720.3  401.64  4865.2  401.26    4887  399.28
  4932.1  399.63  4957.6  400.73  4993.7  399.78  5001.2   398.5  5006.4   398.5
  5011.2  393.08  5011.7  392.58  5017.5  393.08  5024.9  393.99  5035.4   399.7
    5046  400.98  5071.9  401.55  5176.6  402.46    5221  403.18  5306.2  404.27
  5351.7  405.45  5393.8  407.82  5414.9  407.44  5445.8  409.61  5478.1   410.7
#Mann= 9 ,-1 , 0
  4260.5     .07       0  4720.3      .1       0  5011.2     .05       0
  5017.5      .1       0  5071.9     .07       0  5176.6     .12       0
    5221     .07       0  5306.2     .12       0  5445.8     .07       0
Bank Sta=5011.2,5017.5
XS Rating Curve= 0 ,0
Exp/Cntr=0.3,0.1

Type RM Length L Ch R = 1 ,66241   ,447,447,447
BEGIN DESCRIPTION:
BRUSHY CREEK 79.0
END DESCRIPTION:
XS GIS Cut Line= 3
      2386825.01     13594375.01        2387575.       13595075.
        2387975.       13595375.
#Sta/Elev= 30
  3969.1  424.51  4018.7  424.25  4075.3  421.63  4117.8  418.43    4238  413.71
  4266.4  411.89  4280.5   411.9  4308.9  409.98  4492.5  401.45  4782.7   399.1
  4827.3  399.41  4888.7  398.89  4966.9  399.39  4981.1  398.67  4987.9  396.68
  4991.6  394.71  4998.1  394.71  5002.3  391.83  5004.6  391.26  5005.1  390.76
  5012.5  391.26  5016.9  395.83  5023.1  397.25    5095  398.05  5102.3  399.02
  5137.7  399.21  5187.7   400.8  5202.3  402.02  5212.4  401.85    5495  406.61
#Mann= 5 ,-1 , 0
  3969.1     .07       0  4827.3      .1       0  5004.6     .05       0
  5012.5      .1       0  5212.4     .07       0
Bank Sta=5004.6,5012.5
XS Rating Curve= 0 ,0
Exp/Cntr=0.3,0.1

Type RM Length L Ch R = 1 ,65794   ,430,430,430
BEGIN DESCRIPTION:
BRUSHY CREEK 78.0
END DESCRIPTION:
XS GIS Cut Line= 3
      2386825.01     13594425.02        2387225.       13595225.
      2387424.99     13596024.97
#Sta/Elev= 30
  4100.1  424.02  4153.2  422.97  4242.6  418.67  4421.5  407.27  4555.7  400.51
  4645.1  397.85  4769.8  397.01  4815.6  395.53  4882.7  397.69  4927.4  395.88
  4972.1  398.45  4986.1  397.41  4991.7  393.96  4997.1  393.96  5004.8  391.14
  5013.7  390.96  5014.2  390.46  5021.8  390.96  5025.4  394.67  5035.7  396.54
  5046.1   396.3  5177.5  399.86  5265.1  400.72  5293.4  399.03  5324.4  400.81
  5507.3  404.32  5644.6  408.43    5761  412.24  5763.4  412.32  5819.1  414.11
#Mann= 8 ,-1 , 0
  4100.1     .07       0  4769.8      .1       0  5013.7     .05       0
  5021.8      .1       0  5046.1     .07       0  5644.6    .035       0
    5761     .07       0  5763.4    .035       0
Bank Sta=5013.7,5021.8
XS Rating Curve= 0 ,0
Exp/Cntr=0.3,0.1

Type RM Length L Ch R = 1 ,65364   ,867,867,867
BEGIN DESCRIPTION:
BRUSHY CREEK 77.0
END DESCRIPTION:
XS GIS Cut Line= 3
      2386824.99     13594524.96        2386925.       13595275.
        2387275.     13596075.01
#Sta/Elev= 30
  4255.9  421.43  4316.5   419.4  4407.3  413.64  4457.7  408.39    4488  407.65
  4558.6  403.08  4689.7  396.61  4857.4  396.14  4897.8  396.36  4902.9  395.41
  4911.7  396.69  4921.8  396.71  4937.9  389.05  4938.4  388.55    4946  389.05
  4962.1   389.4    4971   394.8    4976  391.97  4982.3  395.42  5002.5  389.59
  5015.3  389.16  5021.5  396.29  5034.4  396.63  5056.4  395.34  5067.2  394.71
  5097.2   396.3    5340  398.66  5584.5  403.79  5746.6  409.69  5885.8  414.85
#Mann= 7 ,-1 , 0
  4255.9     .07       0  4857.4      .1       0  4937.9     .05       0
    4946      .1       0  5056.4     .07       0  5584.5    .035       0
  5746.6     .07       0
Bank Sta=4937.9,4946
XS Rating Curve= 0 ,0
Exp/Cntr=0.3,0.1

Type RM Length L Ch R = 1 ,64497   ,441,441,441
BEGIN DESCRIPTION:
BRUSHY CREEK 76.0
END DESCRIPTION:
XS GIS Cut Line= 3
        2386125.     13595075.01        2386275.       13595425.
      2387025.02     13596225.02
#Sta/Elev= 30
  4619.2  408.11  4717.1  404.78    4728  403.53  4738.9  398.54  4751.4  395.21
  4762.4  392.88  4771.5  392.75  4990.9  394.13  5003.4  393.44  5007.1  390.95
  5013.9  388.68  5023.8  386.97  5024.3  386.47  5032.4  386.97  5035.4  394.28
  5058.8  394.56  5106.2  393.32    5177  394.91  5275.7     394  5375.1  394.73
  5466.7  395.85  5587.3  401.06  5678.3  402.94  5810.1  405.25  5947.8  410.48
  6011.8  411.22  6032.8  411.96  6040.1  413.29  6084.4   414.8  6096.6  415.11
#Mann= 9 ,-1 , 0
  4619.2     .07       0  4751.4      .1       0  5023.8     .05       0
  5032.4      .1       0  5058.8     .07       0  5375.1    .035       0
  5678.3     .07       0  5810.1    .035       0  6084.4     .07       0
Bank Sta=5023.8,5032.4
XS Rating Curve= 0 ,0
Exp/Cntr=0.3,0.1

Type RM Length L Ch R = 1 ,64056   ,445,445,445
BEGIN DESCRIPTION:
BRUSHY CREEK 75.0
END DESCRIPTION:
XS GIS Cut Line= 3
        2385925.     13595325.05        2385925.       13595475.
      2386625.01     13595975.01
#Sta/Elev= 30
  4850.7   404.1  4900.7  401.61  4920.7  398.09  4940.7  396.17  4950.7  396.12
  4970.7  392.65  4990.7     392  4998.2  388.89  5003.7  388.89  5009.9  386.31
  5010.4  385.81  5018.5  386.31  5022.8  386.46  5028.9  390.16  5037.5  391.97
  5058.4  393.01  5073.2  393.16  5079.3  392.18  5086.7  393.27  5100.2   392.4
  5105.5  393.15  5114.9  392.59  5267.2   393.2  5285.7  392.99  5447.9  393.15
  5610.2   394.5  5702.4  396.36  5767.5  398.44    5824  402.42  5860.9  402.89
#Mann= 7 ,-1 , 0
  4850.7     .07       0  5009.9     .05       0  5018.5     .07       0
  5105.5    .035       0  5267.2     .07       0  5285.7    .035       0
  5447.9     .07       0
Bank Sta=5009.9,5018.5
XS Rating Curve= 0 ,0
Exp/Cntr=0.3,0.1

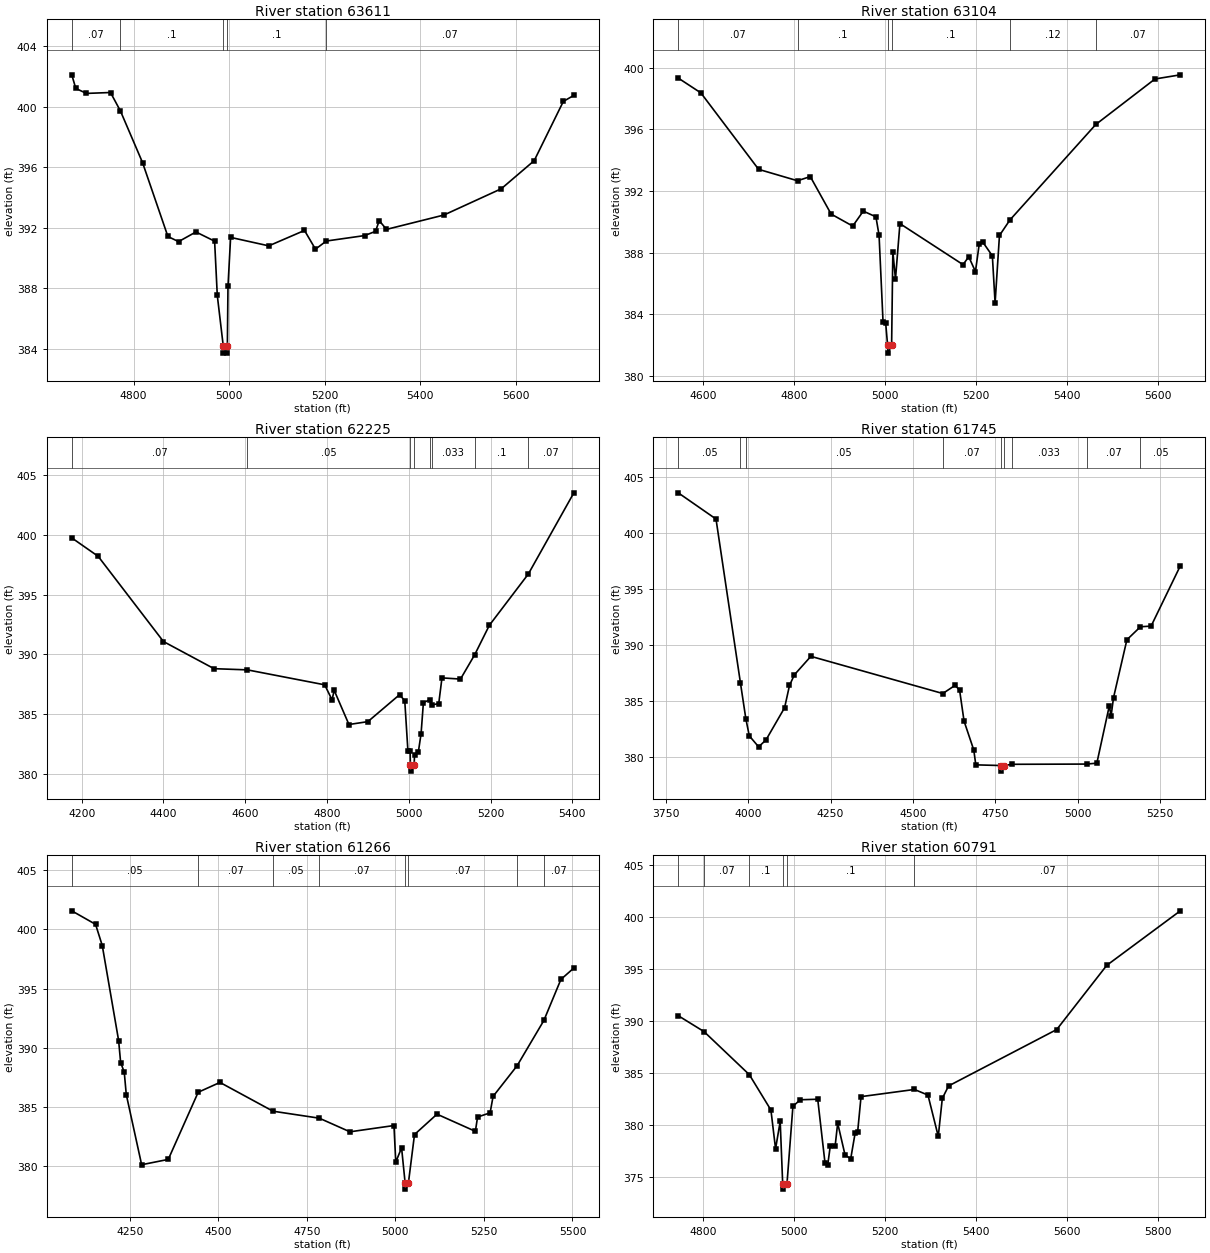
Type RM Length L Ch R = 1 ,63611   ,507,507,507
BEGIN DESCRIPTION:
BRUSHY CREEK 74.0
END DESCRIPTION:
XS GIS Cut Line= 3
      2385624.99     13595574.97        2385775.       13595875.
      2386424.97     13596174.99
#Sta/Elev= 30
  4670.6  402.12    4679  401.22  4701.4  400.89  4751.7  400.95  4772.6  399.72
  4818.8  396.31  4871.9  391.42  4894.2  391.08  4930.6  391.72  4969.7  391.11
  4975.3  387.52  4987.7   384.2  4988.2   383.7  4995.9   383.7  4996.4   384.2
  4997.7  388.12  5003.2  391.36  5083.1   390.8  5157.9  391.82  5180.9  390.58
  5203.6  391.12  5283.7  391.48  5306.6  391.76  5314.4  392.47  5329.6  391.89
  5449.8  392.84    5570  394.58  5638.9  396.44  5699.9  400.36  5721.9  400.76
#Mann= 5 ,-1 , 0
  4670.6     .07       0  4772.6      .1       0  4987.7     .05       0
  4996.4      .1       0  5203.6     .07       0
Bank Sta=4987.7,4996.4
XS Rating Curve= 0 ,0
Exp/Cntr=0.3,0.1

Type RM Length L Ch R = 1 ,63104   ,879,879,879
BEGIN DESCRIPTION:
BRUSHY CREEK 73.0
END DESCRIPTION:
XS GIS Cut Line= 3
        2385325.       13595975.      2385574.79     13596201.14
      2386236.14     13596589.33
#Sta/Elev= 30
  4545.5  399.33  4595.2  398.37  4722.2  393.41  4807.7  392.67  4835.8  392.94
  4881.6  390.51  4929.1  389.73  4952.3   390.7  4980.1  390.33    4987  389.14
  4995.8  383.49  5001.6  383.43  5005.8  381.99  5006.3  381.49  5014.6  381.99
  5017.3  388.08  5023.1  386.29  5032.9  389.89  5171.6  387.23  5184.2  387.74
  5198.9  386.78  5207.4   388.6  5214.6  388.71  5236.1   387.8  5242.1  384.74
  5251.7  389.12  5274.8  390.13  5463.5  396.32  5593.6  399.27  5649.3  399.54
#Mann= 6 ,-1 , 0
  4545.5     .07       0  4807.7      .1       0  5005.8     .05       0
  5014.6      .1       0  5274.8     .12       0  5463.5     .07       0
Bank Sta=5005.8,5014.6
XS Rating Curve= 0 ,0
Exp/Cntr=0.3,0.1

Type RM Length L Ch R = 1 ,62225   ,480,480,480
BEGIN DESCRIPTION:
BRUSHY CREEK 72.0
END DESCRIPTION:
XS GIS Cut Line= 3
      2385274.99     13595974.97        2385475.       13596775.
      2385825.03     13596975.02
#Sta/Elev= 30
  4175.8  399.74  4240.3   398.2    4400  391.07  4523.7   388.8  4605.3   388.7
  4794.3  387.45  4812.3  386.19  4817.5  386.99  4853.6  384.13  4899.9  384.37
  4977.3  386.62  4990.1  386.12  4997.9  381.88  5003.3  381.88  5003.8  380.73
  5004.3  380.23  5012.9  380.73  5014.1  381.57  5023.5  381.87    5030  383.36
  5035.7  385.97  5051.7   386.2  5056.5  385.77  5073.2  385.88  5081.1  388.03
  5126.4  387.93  5161.2  389.97    5197  392.43  5292.3  396.72  5403.6  403.51
#Mann= 8 ,-1 , 0
  4175.8     .07       0  4605.3     .05       0  5003.8     .05       0
  5012.9     .05       0  5051.7      .1       0  5056.5    .033       0
  5161.2      .1       0  5292.3     .07       0
Bank Sta=5003.8,5012.9
XS Rating Curve= 0 ,0
Exp/Cntr=0.3,0.1

Type RM Length L Ch R = 1 ,61745   ,479,479,479
BEGIN DESCRIPTION:
BRUSHY CREEK 71.0
END DESCRIPTION:
XS GIS Cut Line= 3
        2384475.       13596075.        2385175.       13597075.
        2385225.       13597375.
#Sta/Elev= 30
  3787.3  403.58    3902  401.24  3976.1  386.63  3992.6  383.41  4003.1  381.88
  4031.4   380.9  4053.7  381.51  4110.3  384.39  4125.2  386.38    4140  387.33
  4190.1  388.98  4590.7  385.66  4628.2  386.39  4641.8  385.96  4655.3   383.2
  4684.9  380.61    4691  379.29  4766.7  379.23  4767.2  378.73  4775.8  379.23
  4801.7  379.34  5027.2  379.36  5058.6  379.44  5096.7  384.59  5101.7  383.62
  5109.3   385.3  5149.9  390.46    5191  391.62  5223.4  391.68  5312.1  397.06
#Mann= 9 ,-1 , 0
  3787.3     .05       0  3976.1     .07       0  3992.6     .05       0
  4590.7     .07       0  4766.7    .033       0  4775.8     .07       0
  4801.7    .033       0  5027.2     .07       0    5191     .05       0
Bank Sta=4766.7,4775.8
XS Rating Curve= 0 ,0
Exp/Cntr=0.3,0.1

Type RM Length L Ch R = 1 ,61266   ,475,475,475
BEGIN DESCRIPTION:
BRUSHY CREEK 70.0
END DESCRIPTION:
XS GIS Cut Line= 3
        2384375.       13596225.        2384825.       13597025.
      2385125.01     13597425.02
#Sta/Elev= 30
    4086  401.57  4153.2  400.43  4172.1  398.64  4218.3  390.62    4224  388.76
  4234.2  387.95  4239.9  386.06  4283.3  380.13  4358.5  380.58    4443  386.25
  4504.5  387.08  4654.3  384.65  4785.1  384.06  4871.6  382.91  4995.9  383.44
    5001  380.35  5017.4  381.56  5027.5  378.57    5028  378.07  5036.6  378.57
  5053.9  382.68  5117.4   384.4  5225.8  382.95    5232  384.16  5267.4  384.51
  5275.8   385.9  5343.7  388.49  5419.2  392.31  5467.4  395.78  5503.9  396.74
#Mann= 8 ,-1 , 0
    4086     .05       0    4443     .07       0  4654.3     .05       0
  4785.1     .07       0  5027.5     .05       0  5036.6     .07       0
  5343.7     .05       0  5419.2     .07       0
Bank Sta=5027.5,5036.6
XS Rating Curve= 0 ,0
Exp/Cntr=0.3,0.1

Type RM Length L Ch R = 1 ,60791   ,422,422,422
BEGIN DESCRIPTION:
BRUSHY CREEK 69.0
END DESCRIPTION:
XS GIS Cut Line= 3
      2384174.99       13597075.        2384425.       13597125.
      2385175.03     13597525.02
#Sta/Elev= 30
  4744.8  390.49  4801.6  388.96  4901.3  384.82  4948.8  381.42    4959  377.69
  4969.2  380.33  4974.7  374.32  4975.2  373.82  4984.1  374.32  4997.2  381.79
  5013.6  382.41  5051.8  382.46  5067.8  376.34  5073.8  376.14  5079.5     378
  5090.1  377.96  5095.7  380.16    5112  377.09  5124.4  376.74    5134  379.18
  5139.7  379.34  5147.1  382.71  5264.6   383.4  5294.4  382.86  5317.1  378.89
    5326  382.54  5339.8  383.74  5577.8  389.16  5687.9  395.33  5849.8  400.57
#Mann= 6 ,-1 , 0
  4744.8     .05       0  4801.6     .07       0  4901.3      .1       0
  4974.7     .05       0  4984.1      .1       0  5264.6     .07       0
Bank Sta=4974.7,4984.1
XS Rating Curve= 0 ,0
Exp/Cntr=0.3,0.1

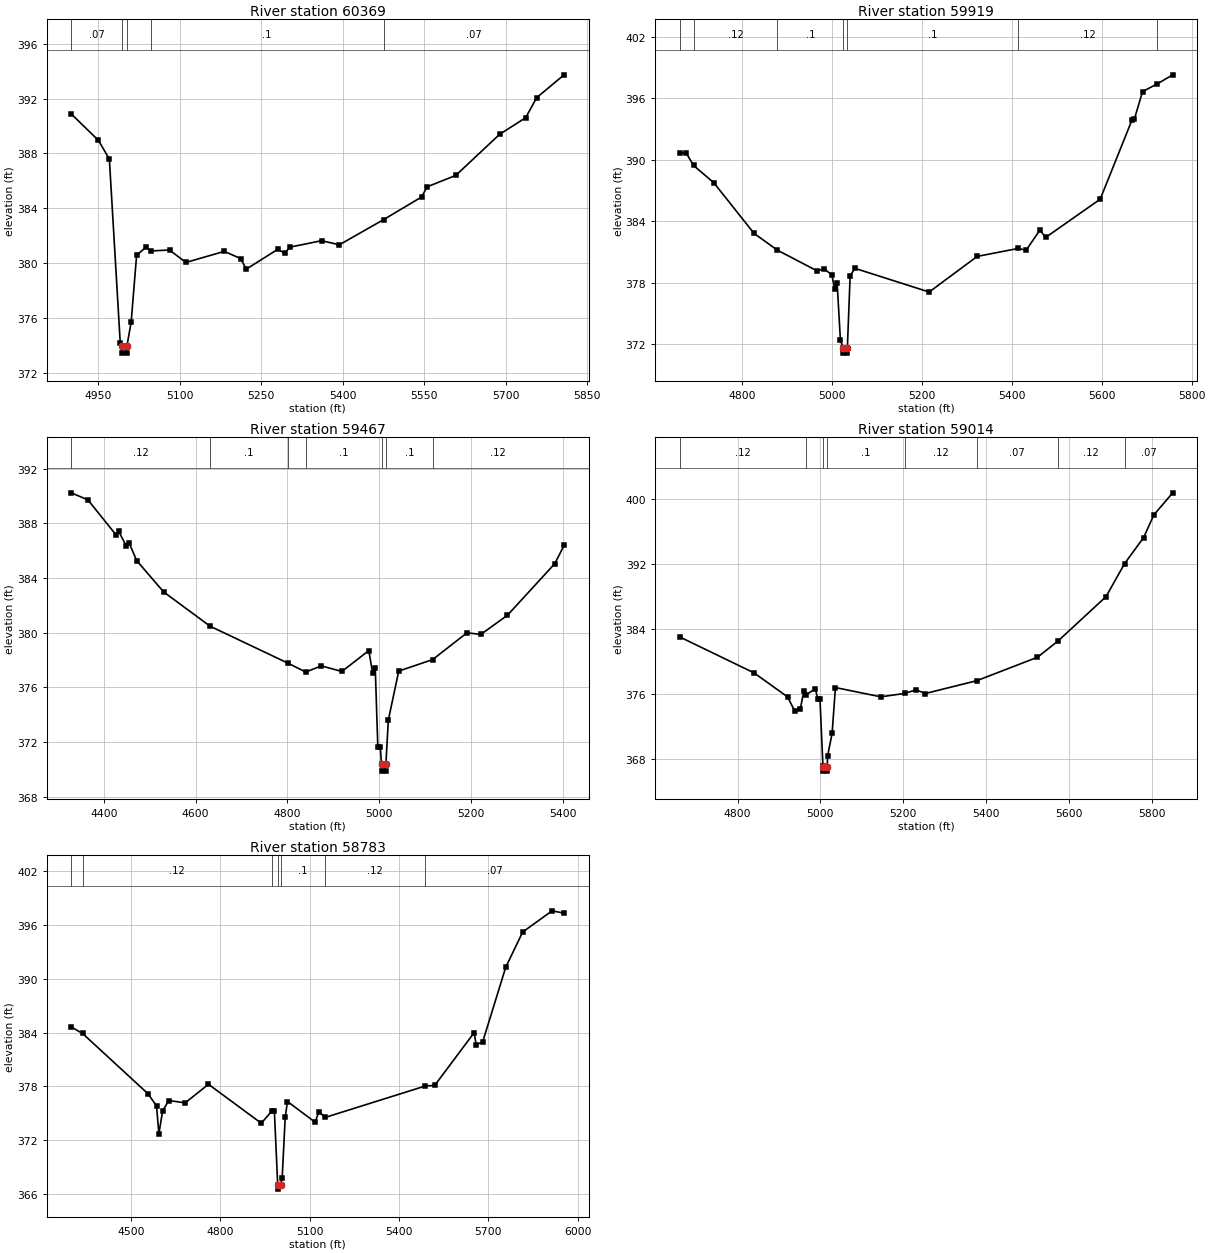
Type RM Length L Ch R = 1 ,60369   ,450,450,450
BEGIN DESCRIPTION:
BRUSHY CREEK 68.0
END DESCRIPTION:
XS GIS Cut Line= 3
      2384075.01       13597425.        2384175.       13597425.
      2384974.98       13597525.
#Sta/Elev= 30
  4900.9  390.88  4950.9  388.95  4970.9  387.58  4990.9  374.17  4993.7  373.92
  4994.2  373.42  5002.6  373.42  5003.1  373.92    5011  375.69    5021  380.57
  5038.7  381.17  5046.9  380.88  5081.5  380.95  5111.7  380.04  5182.3  380.85
  5212.5  380.32  5222.6  379.55  5280.6     381  5293.1  380.72  5303.2  381.16
  5361.2  381.63  5393.9  381.33  5475.3  383.17  5545.1  384.82  5555.2  385.56
  5608.1   386.4  5688.7   389.4  5736.6  390.61  5756.7  392.07  5807.1  393.74
#Mann= 5 ,-1 , 0
  4900.9     .07       0  4993.7     .05       0  5003.1     .07       0
  5046.9      .1       0  5475.3     .07       0
Bank Sta=4993.7,5003.1
XS Rating Curve= 0 ,0
Exp/Cntr=0.3,0.1

Type RM Length L Ch R = 1 ,59919   ,452,452,452
BEGIN DESCRIPTION:
BRUSHY CREEK 67.0
END DESCRIPTION:
XS GIS Cut Line= 3
      2383975.01       13597625.        2384275.       13597775.
      2384975.02     13598075.01
#Sta/Elev= 30
  4660.8  390.67  4674.8  390.65    4691  389.45  4736.3  387.75  4825.7  382.81
  4877.7  381.17  4965.5  379.16  4982.2  379.33  4998.9  378.76  5005.3  377.39
  5010.7  377.99    5018  372.39  5024.1  371.61  5024.6  371.11    5033  371.11
  5033.5  371.61  5039.7  378.68  5050.6  379.39  5215.6  377.08  5322.6  380.56
  5413.9  381.34  5431.4  381.16  5462.2  383.13  5474.9  382.41  5596.4  386.15
  5667.1  393.88  5672.6  393.99  5690.7  396.67  5722.4  397.39  5757.8   398.3
#Mann= 7 ,-1 , 0
  4660.8     .07       0    4691     .12       0  4877.7      .1       0
  5024.1     .05       0  5033.5      .1       0  5413.9     .12       0
  5722.4     .07       0
Bank Sta=5024.1,5033.5
XS Rating Curve= 0 ,0
Exp/Cntr=0.3,0.1

Type RM Length L Ch R = 1 ,59467   ,453,453,453
BEGIN DESCRIPTION:
BRUSHY CREEK 66.0
END DESCRIPTION:
XS GIS Cut Line= 3
      2383825.03     13597875.02        2384425.       13598175.
        2384825.       13598125.
#Sta/Elev= 30
  4329.2  390.24  4365.5  389.72    4427  387.15  4432.6  387.42  4449.4  386.32
  4454.9   386.6  4471.7  385.28  4530.4  382.99  4631.8  380.48  4800.6  377.79
  4840.1  377.13  4874.2  377.58  4918.9  377.17  4977.6   378.7    4986  377.03
  4991.6  377.46  4997.2  371.68  5002.5  371.68  5005.3  370.38  5005.8  369.88
  5014.3  369.88  5014.8  370.38  5020.1  373.61  5042.8   377.2  5116.7  378.04
  5191.5     380  5221.7  379.88  5279.6  381.28  5382.9  385.06  5403.1  386.39
#Mann= 7 ,-1 , 0
  4329.2     .12       0  4631.8      .1       0  4800.6     .12       0
  4840.1      .1       0  5005.3     .05       0  5014.8      .1       0
  5116.7     .12       0
Bank Sta=5005.3,5014.8
XS Rating Curve= 0 ,0
Exp/Cntr=0.3,0.1

Type RM Length L Ch R = 1 ,59014   ,231,231,231
BEGIN DESCRIPTION:
BRUSHY CREEK 65.0
END DESCRIPTION:
XS GIS Cut Line= 3
      2383975.02     13598425.01        2384275.       13598575.
      2385075.01     13598274.99
#Sta/Elev= 30
  4660.8  383.05  4839.7  378.64  4920.7  375.68  4937.5  373.98  4951.5  374.21
  4959.8  376.36  4965.2  375.94  4987.8  376.68  4993.4  375.46  4998.9  375.46
    5006  367.18  5006.6  367.04  5007.1  366.54  5015.6  366.54  5016.1  367.04
  5017.5  368.45  5028.2  371.19  5036.2  376.83  5145.7  375.69  5203.8  376.11
  5231.1  376.56  5252.5  376.09  5377.1  377.67    5524  380.56  5573.6  382.56
  5689.5  388.02  5734.5   392.1  5780.3   395.3  5805.2   398.1  5850.6  400.81
#Mann= 8 ,-1 , 0
  4660.8     .12       0  4965.2      .1       0  5006.6     .05       0
  5016.1      .1       0  5203.8     .12       0  5377.1     .07       0
  5573.6     .12       0  5734.5     .07       0
Bank Sta=5006.6,5016.1
XS Rating Curve= 0 ,0
Exp/Cntr=0.3,0.1

Type RM Length L Ch R = 1 ,58783   ,364,364,364
BEGIN DESCRIPTION:
X18328
END DESCRIPTION:
XS GIS Cut Line= 4
      2383657.37     13598950.73      2384259.71     13598802.93
       2384961.4      13598649.9      2385195.71      13598439.5
#Sta/Elev= 30
  4300.6  384.62  4338.3   383.9  4558.1  377.18  4586.5  375.83  4594.5  372.74
  4607.1  375.28  4627.7  376.43  4682.8  376.17  4760.8  378.24  4938.1   373.9
  4973.7  375.27    4982  375.21  4993.1  367.06  4993.6  366.56  5002.7  367.06
  5008.1  367.77  5018.3  374.56  5025.9  376.32  5118.9  374.01  5130.9  375.18
  5152.7  374.55  5488.6  378.05  5519.9  378.11  5652.2  383.99  5658.9  382.67
  5680.6  382.93  5758.3  391.28  5815.1   395.2  5913.8  397.56  5953.9   397.3
#Mann= 7 ,-1 , 0
  4300.6     .07       0  4338.3     .12       0  4973.7      .1       0
  4993.1     .05       0  5002.7      .1       0  5152.7     .12       0
  5488.6     .07       0
Bank Sta=4993.1,5002.7
XS Rating Curve= 0 ,0
Exp/Cntr=0.3,0.1