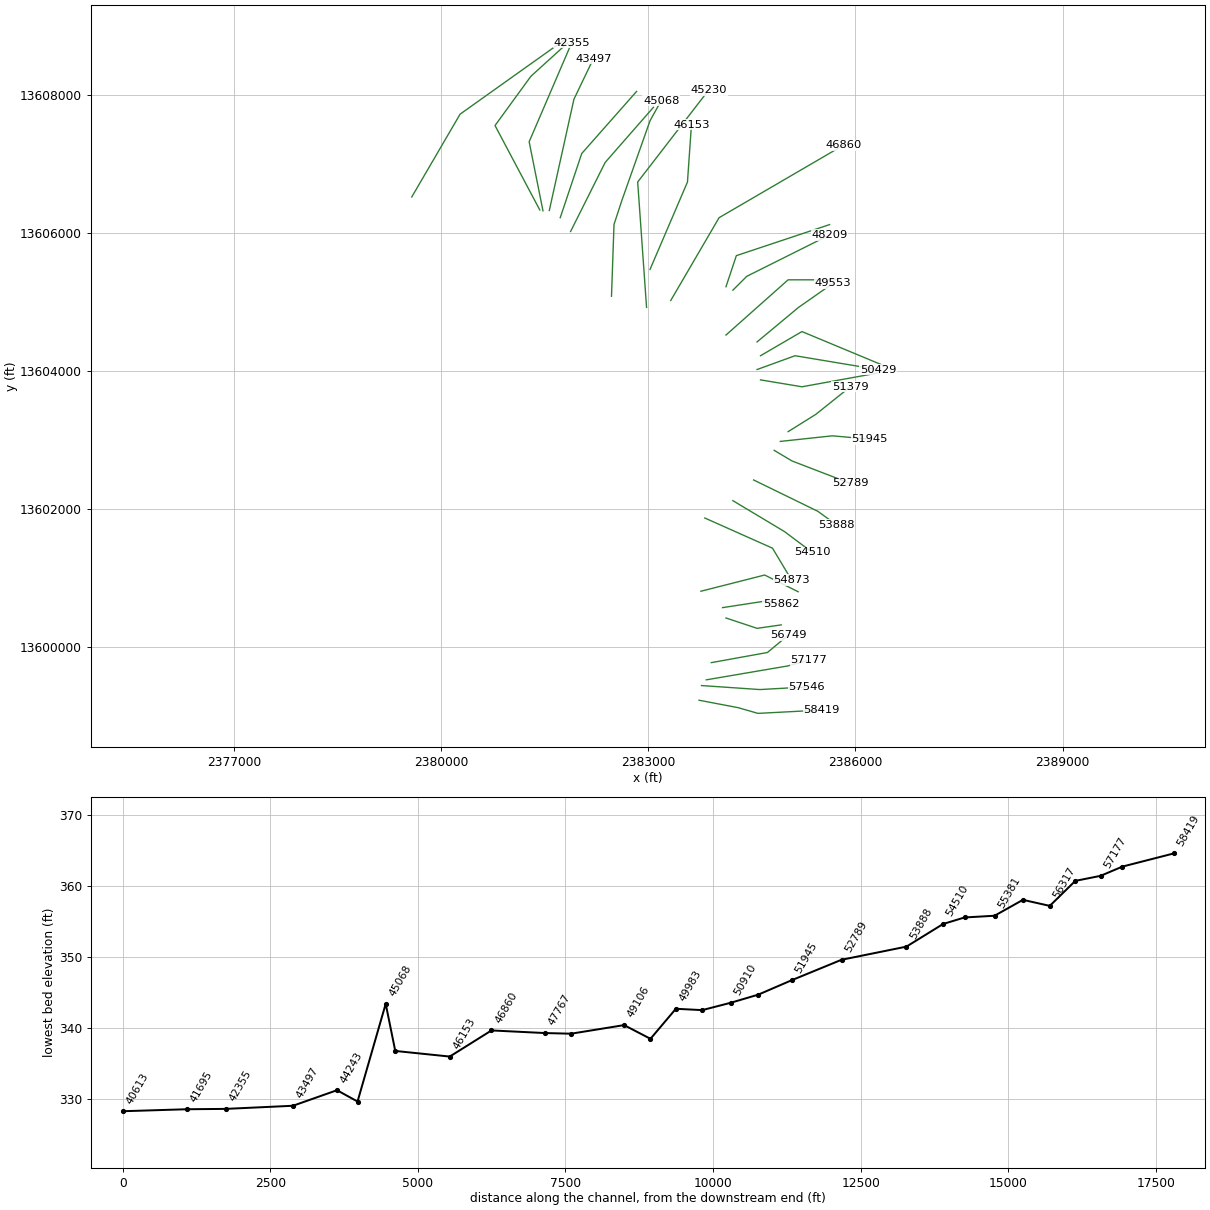
HEC-RAS study BRUSHY CREEK.prj: BRUSHY CREEK Base Level Engineering

--- BRUSHY CREEK.g01 (geometry) --- (continued)

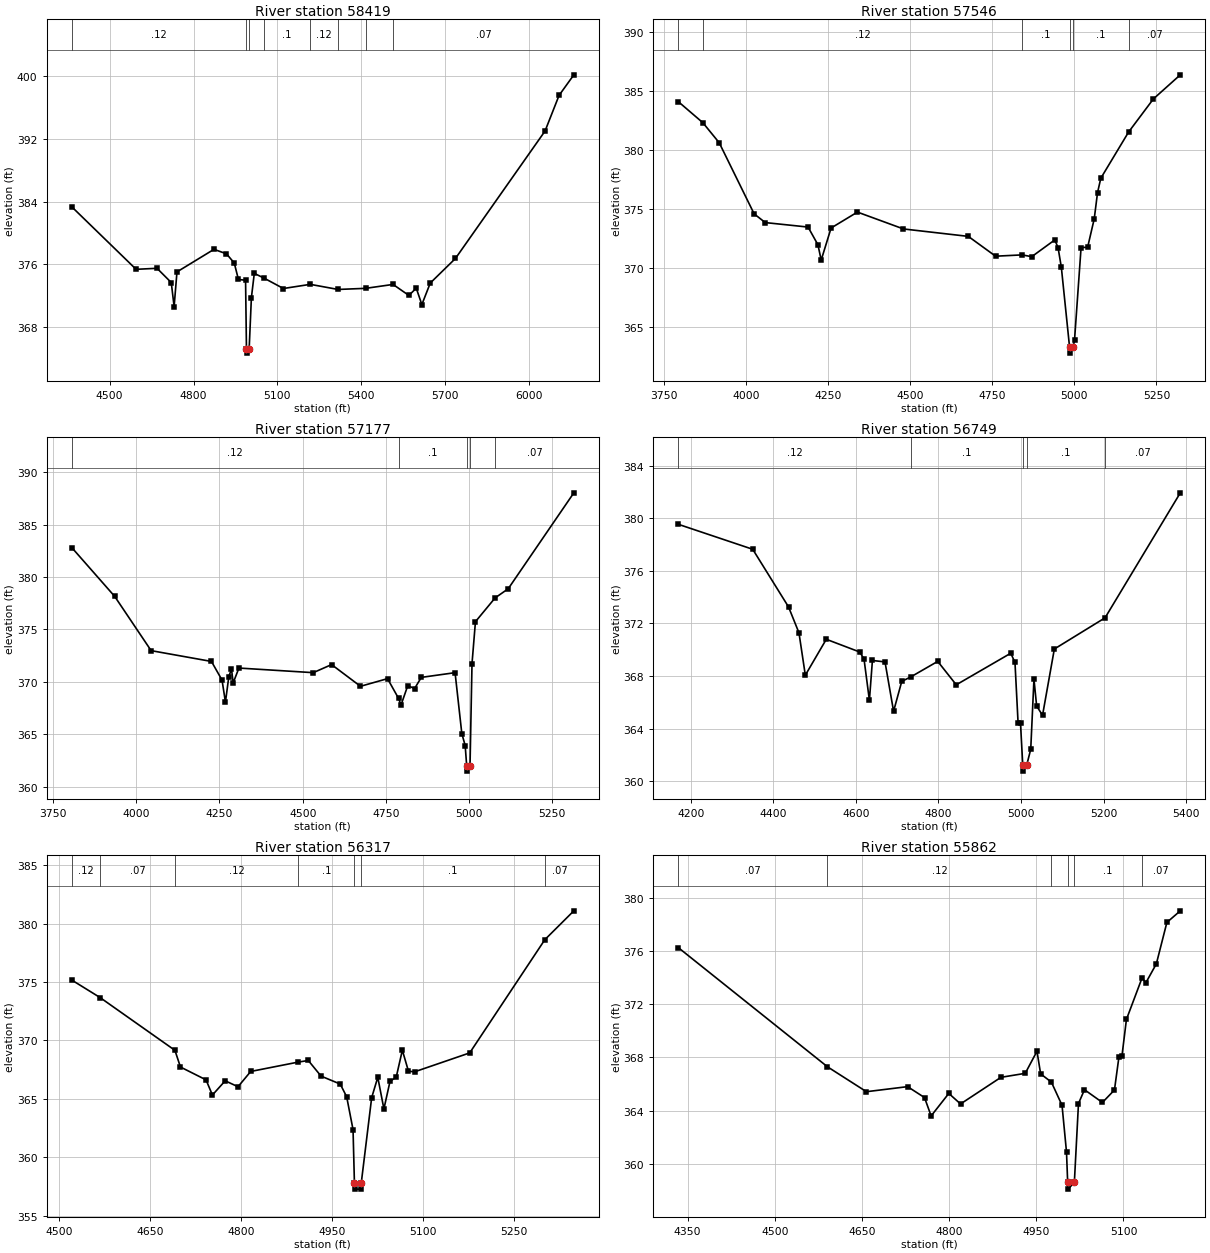
Type RM Length L Ch R = 1 ,58419   ,873,873,873
BEGIN DESCRIPTION:
X18327
END DESCRIPTION:
XS GIS Cut Line= 4
      2383735.44      13599233.3      2384302.43     13599125.31
      2384587.62     13599042.85      2385507.72     13599090.77
#Sta/Elev= 30
  4364.6  383.33  4594.6  375.35  4669.5  375.48  4720.4  373.66  4730.6  370.59
  4740.8  375.02  4873.1   377.9  4917.8  377.33  4945.7  376.15  4960.5  374.06
  4986.1  373.95  4989.3  365.15  4989.8  364.65  4998.9  365.15  5006.9  371.73
  5017.3  374.83    5052  374.23  5121.4   372.9  5217.5  373.43  5316.8  372.78
  5415.2  372.92  5513.5  373.42    5570  372.02  5596.5  372.94  5616.5  370.85
  5646.6   373.6  5736.7  376.74  6057.1  393.01  6107.2  397.56    6160  400.18
#Mann= 8 ,-1 , 0
  4364.6     .12       0  4989.3     .05       0  4998.9     .12       0
    5052      .1       0  5217.5     .12       0  5316.8      .1       0
  5415.2     .12       0  5513.5     .07       0
Bank Sta=4989.3,4998.9
XS Rating Curve= 0 ,0
Exp/Cntr=0.3,0.1

Type RM Length L Ch R = 1 ,57546   ,369,369,369
BEGIN DESCRIPTION:
X18326
END DESCRIPTION:
XS GIS Cut Line= 3
      2383770.47      13599445.9      2384616.37     13599387.88
      2385296.81     13599426.21
#Sta/Elev= 30
  3793.5  384.12  3868.5  382.33  3918.3  380.63  4024.7   374.6  4058.6  373.86
    4189  373.48    4219  371.98    4229  370.68  4259.1   373.4  4339.3  374.75
  4479.6  373.32  4677.1  372.69  4760.2  371.01  4840.8  371.12  4870.4  370.97
  4940.5  372.39  4950.5  371.74  4960.5  370.07  4985.6  363.29  4986.1  362.79
  4995.5  363.29  5000.6  363.87  5020.6  371.74  5040.6  371.77  5060.7  374.18
  5070.7  376.39  5080.7  377.62  5165.4  381.54    5241  384.35  5322.9  386.39
#Mann= 6 ,-1 , 0
  3793.5     .07       0  3868.5     .12       0  4840.8      .1       0
  4985.6     .05       0  4995.5      .1       0  5165.4     .07       0
Bank Sta=4985.6,4995.5
XS Rating Curve= 0 ,0
Exp/Cntr=0.3,0.1

Type RM Length L Ch R = 1 ,57177   ,428,428,428
BEGIN DESCRIPTION:
BRUSHY CREEK 64.0
END DESCRIPTION:
XS GIS Cut Line= 3
      2383840.02     13599528.76      2385018.91     13599730.03
      2385320.38     13599811.38
#Sta/Elev= 30
  3806.3  382.81  3935.3  378.15  4044.7  372.98  4225.9  371.95  4257.7  370.17
  4267.9  368.07    4278  370.49  4286.1  371.23  4291.1   369.9  4308.4  371.32
  4531.7  370.88  4586.8  371.65  4673.6  369.58  4754.8  370.31  4787.9  368.43
  4795.4   367.8  4815.7  369.65    4836  369.36  4856.3  370.43  4957.7  370.88
    4978  365.07  4988.1  363.93  4992.6  361.99  4993.1  361.49  5002.6  361.99
  5008.6  371.75  5018.9  375.74    5078  378.01  5117.3  378.88  5314.5  388.03
#Mann= 5 ,-1 , 0
  3806.3     .12       0  4787.9      .1       0  4992.6     .05       0
  5002.6      .1       0    5078     .07       0
Bank Sta=4992.6,5002.6
XS Rating Curve= 0 ,0
Exp/Cntr=0.3,0.1

Type RM Length L Ch R = 1 ,56749   ,432,432,432
BEGIN DESCRIPTION:
BRUSHY CREEK 63.0
END DESCRIPTION:
XS GIS Cut Line= 3
      2383911.92     13599777.95        2384725.       13599925.
      2385025.01     13600175.01
#Sta/Elev= 30
  4169.3  379.54  4349.8  377.64  4436.6  373.26  4461.9  371.29  4477.3  368.07
  4528.1   370.8  4609.4  369.83  4619.6  369.29  4632.6  366.16  4639.9  369.19
  4670.4  369.08  4691.2  365.33    4711   367.6    4734  367.96  4798.2  369.12
  4843.1  367.34  4975.2  369.74  4985.4  369.04    4993   364.4  4998.8   364.4
  5004.2  361.28  5004.7  360.78  5014.2  361.28  5023.6  362.44  5031.4  367.77
  5037.9  365.73  5052.2  365.02  5080.8  370.06  5203.7  372.43  5386.1  381.93
#Mann= 5 ,-1 , 0
  4169.3     .12       0    4734      .1       0  5004.2     .05       0
  5014.2      .1       0  5203.7     .07       0
Bank Sta=5004.2,5014.2
XS Rating Curve= 0 ,0
Exp/Cntr=0.3,0.1

Type RM Length L Ch R = 1 ,56317   ,455,455,455
BEGIN DESCRIPTION:
BRUSHY CREEK 62.0
END DESCRIPTION:
XS GIS Cut Line= 3
        2384125.       13600425.        2384575.       13600275.
      2384925.01       13600325.
#Sta/Elev= 30
  4520.8  375.17  4567.5  373.67  4690.9  369.15    4700  367.72  4742.2  366.62
  4752.7  365.32  4773.8  366.54  4794.9  366.03  4815.9  367.34    4894  368.14
  4910.8  368.28  4931.9  366.94  4963.5  366.26  4974.1  365.17  4984.6  362.36
  4986.9  357.76  4987.4  357.26  4997.6  357.26  4998.1  357.76  5015.3  365.09
  5025.4  366.84  5035.5  364.13  5045.6   366.5  5055.8  366.85  5065.9  369.16
    5076  367.36  5086.1  367.31    5177  368.93  5300.9  378.63  5348.7   381.1
#Mann= 7 ,-1 , 0
  4520.8     .12       0  4567.5     .07       0  4690.9     .12       0
    4894      .1       0  4986.9     .05       0  4998.1      .1       0
  5300.9     .07       0
Bank Sta=4986.9,4998.1
XS Rating Curve= 0 ,0
Exp/Cntr=0.3,0.1

Type RM Length L Ch R = 1 ,55862   ,481,481,481
BEGIN DESCRIPTION:
BRUSHY CREEK 61.0
END DESCRIPTION:
XS GIS Cut Line= 3
      2384074.96     13600574.99        2384725.       13600675.
      2384924.96     13600625.01
#Sta/Elev= 30
    4334  376.26  4590.8   367.3  4657.8  365.43  4728.6  365.81  4757.7  364.99
  4769.1  363.61  4799.5   365.3  4819.7  364.51  4889.2  366.51    4931  366.81
  4951.2  368.47  4957.5  366.77    4976  366.15  4994.3  364.41    5002   360.9
    5004  358.61  5004.5  358.11  5015.5  358.61  5022.6  364.54  5032.9  365.58
  5063.8  364.62  5084.5  365.56  5092.2  368.04  5097.3  368.08  5105.1  370.86
  5131.9  373.97  5138.6  373.62  5156.6  375.04  5174.7  378.15  5197.8  379.02
#Mann= 6 ,-1 , 0
    4334     .07       0  4590.8     .12       0    4976      .1       0
    5004     .05       0  5015.5      .1       0  5131.9     .07       0
Bank Sta=5004,5015.5
XS Rating Curve= 0 ,0
Exp/Cntr=0.3,0.1

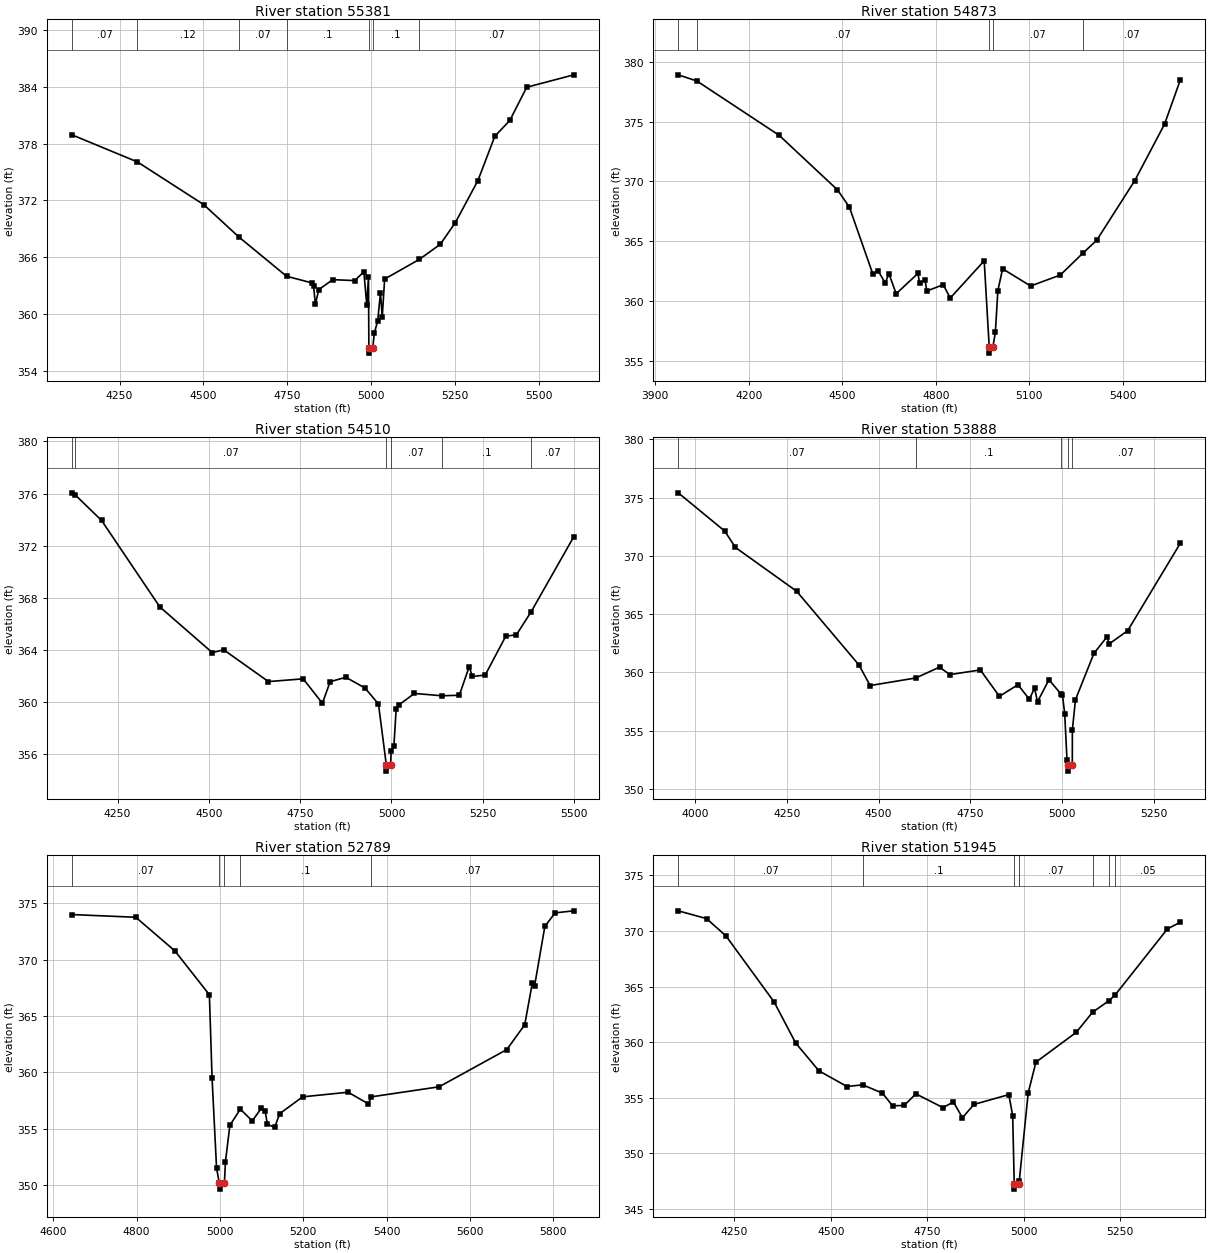
Type RM Length L Ch R = 1 ,55381   ,508,508,508
BEGIN DESCRIPTION:
BRUSHY CREEK 60.0
END DESCRIPTION:
XS GIS Cut Line= 3
      2383761.72     13600812.53      2384685.21     13601047.45
      2385170.61     13600804.75
#Sta/Elev= 30
  4107.7  378.93  4303.4  376.06  4500.5  371.56    4606  368.12  4747.5  363.99
  4822.7  363.29  4827.9  362.94  4833.4  361.05  4843.7  362.58    4885  363.63
  4950.6  363.53  4977.8  364.46  4986.4  360.96  4991.6  363.96  4992.7  356.37
  4993.2  355.87  5004.2  356.37  5008.8  357.95  5019.1  359.31  5027.3  362.26
  5032.5  359.68  5039.7  363.69    5143  365.77  5205.7  367.37  5250.4  369.66
  5317.5  374.09  5367.9  378.77  5412.5  380.44  5462.9  383.95  5603.3  385.26
#Mann= 7 ,-1 , 0
  4107.7     .07       0  4303.4     .12       0    4606     .07       0
  4747.5      .1       0  4992.7     .05       0  5004.2      .1       0
    5143     .07       0
Bank Sta=4992.7,5004.2
XS Rating Curve= 0 ,0
Exp/Cntr=0.3,0.1

Type RM Length L Ch R = 1 ,54873   ,363,363,363
BEGIN DESCRIPTION:
BRUSHY CREEK 59.0
END DESCRIPTION:
XS GIS Cut Line= 3
      2383818.46      13601873.7      2384798.61     13601436.27
      2385075.02     13600974.97
#Sta/Elev= 30
  3973.5  378.93  4033.5  378.41  4297.2  373.87  4484.4   369.3  4522.6  367.86
  4597.7  362.27  4615.4   362.5  4637.7   361.5  4649.6  362.28  4672.8   360.6
  4742.5   362.3    4748  361.52  4765.7  361.72  4771.2  360.83  4823.9  361.36
  4846.3  360.24  4955.3  363.36  4971.4  356.13  4971.9  355.63  4982.9  356.13
  4991.1  357.36  4999.1  360.85  5014.3  362.69  5104.3  361.25  5199.6  362.17
  5271.2  363.98  5316.3  365.08  5438.6  370.08    5534   374.8  5584.6   378.5
#Mann= 5 ,-1 , 0
  3973.5     .05       0  4033.5     .07       0  4971.4     .05       0
  4982.9     .07       0  5271.2     .07       0
Bank Sta=4971.4,4982.9
XS Rating Curve= 0 ,0
Exp/Cntr=0.3,0.1

Type RM Length L Ch R = 1 ,54510   ,622,622,622
BEGIN DESCRIPTION:
BRUSHY CREEK 58.0
END DESCRIPTION:
XS GIS Cut Line= 3
      2384224.99       13602125.        2384975.       13601675.
      2385374.96     13601375.03
#Sta/Elev= 30
  4124.8  376.06  4133.6  375.92  4206.4  373.94  4365.8  367.31  4509.6   363.8
  4540.7  364.02  4663.2  361.58  4758.4  361.79  4810.9  359.92  4832.3  361.57
  4875.1  361.91  4927.5  361.09  4964.5  359.86  4985.9  355.21  4986.4  354.71
  4997.5  355.21  4999.4  356.23  5006.7  356.62    5013  359.49  5021.3  359.81
    5063  360.67  5138.4  360.49  5185.9  360.53    5213  362.73  5221.3  361.97
  5256.7  362.08    5313  365.06  5342.2  365.17  5382.8  366.95  5499.4   372.7
#Mann= 6 ,-1 , 0
  4124.8     .05       0  4133.6     .07       0  4985.9     .05       0
  4997.5     .07       0  5138.4      .1       0  5382.8     .07       0
Bank Sta=4985.9,4997.5
XS Rating Curve= 0 ,0
Exp/Cntr=0.3,0.1

Type RM Length L Ch R = 1 ,53888   ,1099,1099,1099
BEGIN DESCRIPTION:
BRUSHY CREEK 57.0
END DESCRIPTION:
XS GIS Cut Line= 3
      2384525.03     13602424.99      2385454.75      13601970.9
      2385725.02     13601774.98
#Sta/Elev= 30
  3953.7  375.42  4080.3  372.14  4109.5  370.73  4276.4  366.97  4446.2  360.64
  4476.7  358.87  4601.2  359.52  4665.9  360.45    4694  359.81  4777.2  360.21
  4829.1  357.94  4879.7  358.94  4910.8  357.69  4924.8  358.65    4933  357.48
  4964.2  359.37  4997.2  358.13  5000.9  358.07  5007.1  356.45  5013.4  352.44
  5015.8  352.02  5016.3  351.52  5027.8  352.02    5028  355.08  5036.5  357.66
  5086.7  361.63  5122.3  363.05  5128.5  362.45  5178.7  363.58  5322.2  371.09
#Mann= 5 ,-1 , 0
  3953.7     .07       0  4601.2      .1       0  4997.2     .07       0
  5015.8     .05       0  5027.8     .07       0
Bank Sta=5015.8,5027.8
XS Rating Curve= 0 ,0
Exp/Cntr=0.3,0.1

Type RM Length L Ch R = 1 ,52789   ,844,844,844
BEGIN DESCRIPTION:
BRUSHY CREEK 56.0
END DESCRIPTION:
XS GIS Cut Line= 3
      2384822.93     13602853.84      2385082.13     13602699.94
      2385925.02     13602374.99
#Sta/Elev= 30
  4644.6  373.98  4798.2  373.74  4892.1  370.76  4974.8  366.88  4981.3  359.47
    4992  351.56  4998.7  350.17  4999.2  349.67  5010.8  350.17  5013.4  352.11
    5024  355.32  5049.1  356.75  5077.7  355.71  5099.2  356.81  5108.6  356.58
    5114  355.41  5131.3  355.15  5143.9  356.36  5198.5  357.84  5307.7  358.25
  5356.4  357.22  5363.3  357.84  5526.1  358.73  5688.6  362.03  5731.5  364.22
  5749.8  367.93  5755.2  367.66  5779.8  372.93  5804.4  374.13  5849.4  374.31
#Mann= 5 ,-1 , 0
  4644.6     .07       0  4998.7     .05       0  5010.8     .07       0
  5049.1      .1       0  5363.3     .07       0
Bank Sta=4998.7,5010.8
XS Rating Curve= 0 ,0
Exp/Cntr=0.3,0.1

Type RM Length L Ch R = 1 ,51945   ,566,566,566
BEGIN DESCRIPTION:
BRUSHY CREEK 55.0
END DESCRIPTION:
XS GIS Cut Line= 3
      2384912.05     13602983.46      2385665.36     13603064.46
      2386208.13     13603015.85
#Sta/Elev= 30
  4104.1  371.82  4177.5  371.12  4227.8  369.57  4352.9  363.62  4408.8  359.93
  4469.1  357.43    4542  356.02  4582.7  356.17    4634  355.42  4660.2  354.28
  4690.4  354.32  4720.6  355.36    4791  354.12  4818.1  354.63  4841.3  353.21
  4871.4  354.41  4961.8  355.29  4971.8  353.39  4975.8  347.29  4976.3  346.79
  4987.9  347.29  4988.8  347.49    5012  355.44  5032.1  358.21  5136.7  360.89
  5179.1   362.7  5221.6  363.74  5237.1  364.23  5373.4   370.2  5406.7  370.79
#Mann= 8 ,-1 , 0
  4104.1     .07       0  4582.7      .1       0  4975.8     .05       0
  4987.9      .1       0  4988.8     .07       0  5179.1     .05       0
  5221.6     .07       0  5237.1     .05       0
Bank Sta=4975.8,4987.9
XS Rating Curve= 0 ,0
Exp/Cntr=0.3,0.1

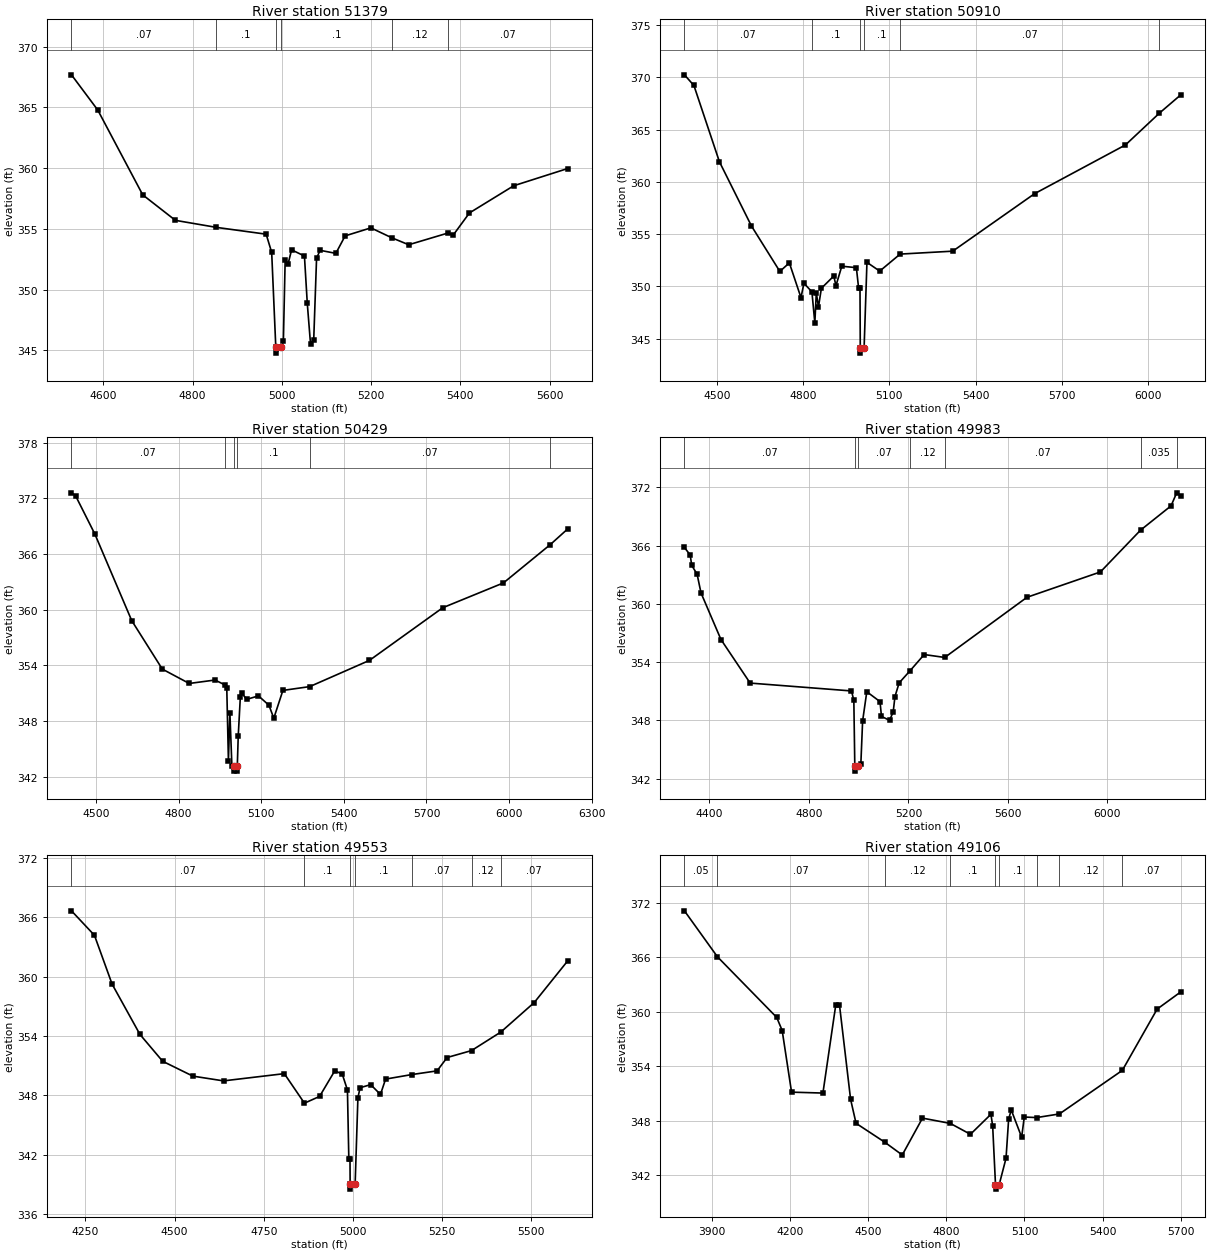
Type RM Length L Ch R = 1 ,51379   ,469,469,469
BEGIN DESCRIPTION:
BRUSHY CREEK 54.0
END DESCRIPTION:
XS GIS Cut Line= 3
      2385025.03     13603125.02        2385425.       13603375.
      2385925.02     13603775.02
#Sta/Elev= 30
  4528.4  367.69  4587.3  364.79  4688.1   357.8  4761.3   355.7  4853.3  355.12
  4964.7  354.56  4977.1  353.06  4986.3  345.26  4986.8  344.76  4998.4  345.26
  5003.3  345.75  5007.3  352.43  5013.7  352.09  5021.7  353.27  5050.5  352.76
  5056.9  348.85  5064.1  345.53  5071.3  345.85  5077.7  352.59  5085.7  353.23
  5120.9  352.98  5141.7  354.42  5199.4  355.08  5247.1  354.25  5284.2  353.69
  5371.7  354.65  5384.2   354.5  5420.3  356.31  5519.5  358.55  5640.4  359.97
#Mann= 6 ,-1 , 0
  4528.4     .07       0  4853.3      .1       0  4986.3     .05       0
  4998.4      .1       0  5247.1     .12       0  5371.7     .07       0
Bank Sta=4986.3,4998.4
XS Rating Curve= 0 ,0
Exp/Cntr=0.3,0.1

Type RM Length L Ch R = 1 ,50910   ,481,481,481
BEGIN DESCRIPTION:
BRUSHY CREEK 53.0
END DESCRIPTION:
XS GIS Cut Line= 3
      2384624.98       13603875.        2385225.       13603775.
      2386324.97     13603974.99
#Sta/Elev= 30
    4387  370.25    4420  369.23  4508.7  361.93  4620.2  355.78    4719  351.43
    4752  352.25  4792.5  348.92  4802.7   350.3  4830.5  349.48  4840.7   346.5
  4845.8  349.37  4853.4  348.04  4863.5  349.82  4906.6  350.99  4914.2  350.07
  4934.5  351.93  4985.2  351.79  4992.8  349.89  4997.8  349.89  4998.8  344.11
  4999.3  343.61  5012.1  344.11    5022   352.3  5066.4  351.46  5137.5  353.09
  5320.5  353.37  5605.1  358.87  5921.5  363.54  6039.8  366.59  6113.3  368.32
#Mann= 6 ,-1 , 0
    4387     .07       0  4830.5      .1       0  4998.8     .05       0
  5012.1      .1       0  5137.5     .07       0  6039.8    .035       0
Bank Sta=4998.8,5012.1
XS Rating Curve= 0 ,0
Exp/Cntr=0.3,0.1

Type RM Length L Ch R = 1 ,50429   ,446,446,446
BEGIN DESCRIPTION:
BRUSHY CREEK 52.0
END DESCRIPTION:
XS GIS Cut Line= 3
      2384575.04     13604025.01        2385125.       13604225.
      2386324.95     13604025.01
#Sta/Elev= 30
    4411  372.61  4426.3  372.27  4496.1  368.15  4629.8  358.82  4740.8  353.59
  4838.6  352.04  4932.4  352.41  4967.6  351.89  4974.9  351.58  4980.9   343.7
  4986.2  348.88  4993.5  343.16  4999.6  343.08  5000.1  342.58  5012.6  342.58
  5013.1  343.08  5016.5  346.35  5024.1  350.55  5029.1  351.02  5046.9  350.32
    5090   350.7    5128  349.69  5145.7  348.29  5178.7  351.29  5276.1   351.7
    5493  354.53  5759.1  360.21  5979.6  362.89  6149.5  367.02  6212.7  368.71
#Mann= 6 ,-1 , 0
    4411     .07       0  4967.6      .1       0  4999.6     .05       0
  5013.1      .1       0  5276.1     .07       0  6149.5    .035       0
Bank Sta=4999.6,5013.1
XS Rating Curve= 0 ,0
Exp/Cntr=0.3,0.1

Type RM Length L Ch R = 1 ,49983   ,430,430,430
BEGIN DESCRIPTION:
BRUSHY CREEK 51.0
END DESCRIPTION:
XS GIS Cut Line= 3
        2384625.       13604225.        2385225.       13604575.
      2386424.98     13604075.01
#Sta/Elev= 30
  4299.5  365.81  4322.6  365.04  4328.9  363.96  4350.4  363.06  4366.1  361.13
  4446.3  356.33  4563.7  351.84    4971  351.03  4980.5  350.06  4984.4  343.27
  4984.9  342.77    4998  343.27  5008.7  343.52  5015.8  347.94  5032.6  350.95
  5085.7  349.93  5091.6  348.41  5124.1     348  5138.7  348.87  5145.8  350.45
  5162.6  351.86  5206.5  353.11  5263.3  354.78  5345.9  354.48  5676.6  360.68
  5971.8  363.29  6132.9  367.59  6255.7   370.1  6278.3  371.44  6294.1  371.15
#Mann= 7 ,-1 , 0
  4299.5     .07       0  4984.4     .05       0    4998     .07       0
  5206.5     .12       0  5345.9     .07       0  6132.9    .035       0
  6278.3     .07       0
Bank Sta=4984.4,4998
XS Rating Curve= 0 ,0
Exp/Cntr=0.3,0.1

Type RM Length L Ch R = 1 ,49553   ,447,447,447
BEGIN DESCRIPTION:
BRUSHY CREEK 50.0
END DESCRIPTION:
XS GIS Cut Line= 3
      2384575.03     13604425.03        2385175.       13604925.
      2385674.99     13605274.99
#Sta/Elev= 30
  4210.7  366.64  4275.1  364.17  4324.6  359.24  4402.7  354.16  4466.4  351.45
  4551.1  349.95    4637  349.47  4807.5   350.2  4863.9  347.22  4906.4   347.9
  4949.4  350.51  4970.2  350.13  4984.5  348.55  4988.4  341.63  4991.7  341.63
  4992.1  339.04  4992.6  338.54  5006.1  339.04  5013.9  347.78    5020  348.78
  5049.7  349.09  5077.1   348.1  5091.5  349.65  5165.3  350.11  5235.8  350.48
  5264.1  351.83  5332.5  352.53  5414.6   354.4  5508.3  357.38    5602  361.58
#Mann= 7 ,-1 , 0
  4210.7     .07       0  4863.9      .1       0  4992.1     .05       0
  5006.1      .1       0  5165.3     .07       0  5332.5     .12       0
  5414.6     .07       0
Bank Sta=4992.1,5006.1
XS Rating Curve= 0 ,0
Exp/Cntr=0.3,0.1

Type RM Length L Ch R = 1 ,49106   ,897,897,897
BEGIN DESCRIPTION:
BRUSHY CREEK 49.0
END DESCRIPTION:
XS GIS Cut Line= 3
      2384124.96     13604524.97        2385025.       13605325.
      2385724.99       13605325.
#Sta/Elev= 30
  3795.1  371.12  3921.7  366.06  4149.3  359.38  4170.2  357.94  4206.2  351.15
  4326.6  351.05  4375.9  360.76  4390.1  360.77  4432.8  350.36  4453.7  347.72
  4563.3  345.65    4631  344.23  4708.7  348.29  4815.3  347.71  4892.7  346.51
  4971.3  348.71    4978  347.44  4988.9  340.97  4989.4  340.47  5003.1  340.97
  5029.3  343.87  5039.3  348.17  5049.3  349.19  5089.3  346.19  5099.3  348.41
  5146.7  348.35  5234.1  348.75  5475.7  353.55  5609.3   360.3  5699.3  362.18
#Mann= 9 ,-1 , 0
  3795.1     .05       0  3921.7     .07       0  4563.3     .12       0
  4815.3      .1       0  4988.9     .05       0  5003.1      .1       0
  5146.7     .07       0  5234.1     .12       0  5475.7     .07       0
Bank Sta=4988.9,5003.1
XS Rating Curve= 0 ,0
Exp/Cntr=0.3,0.1

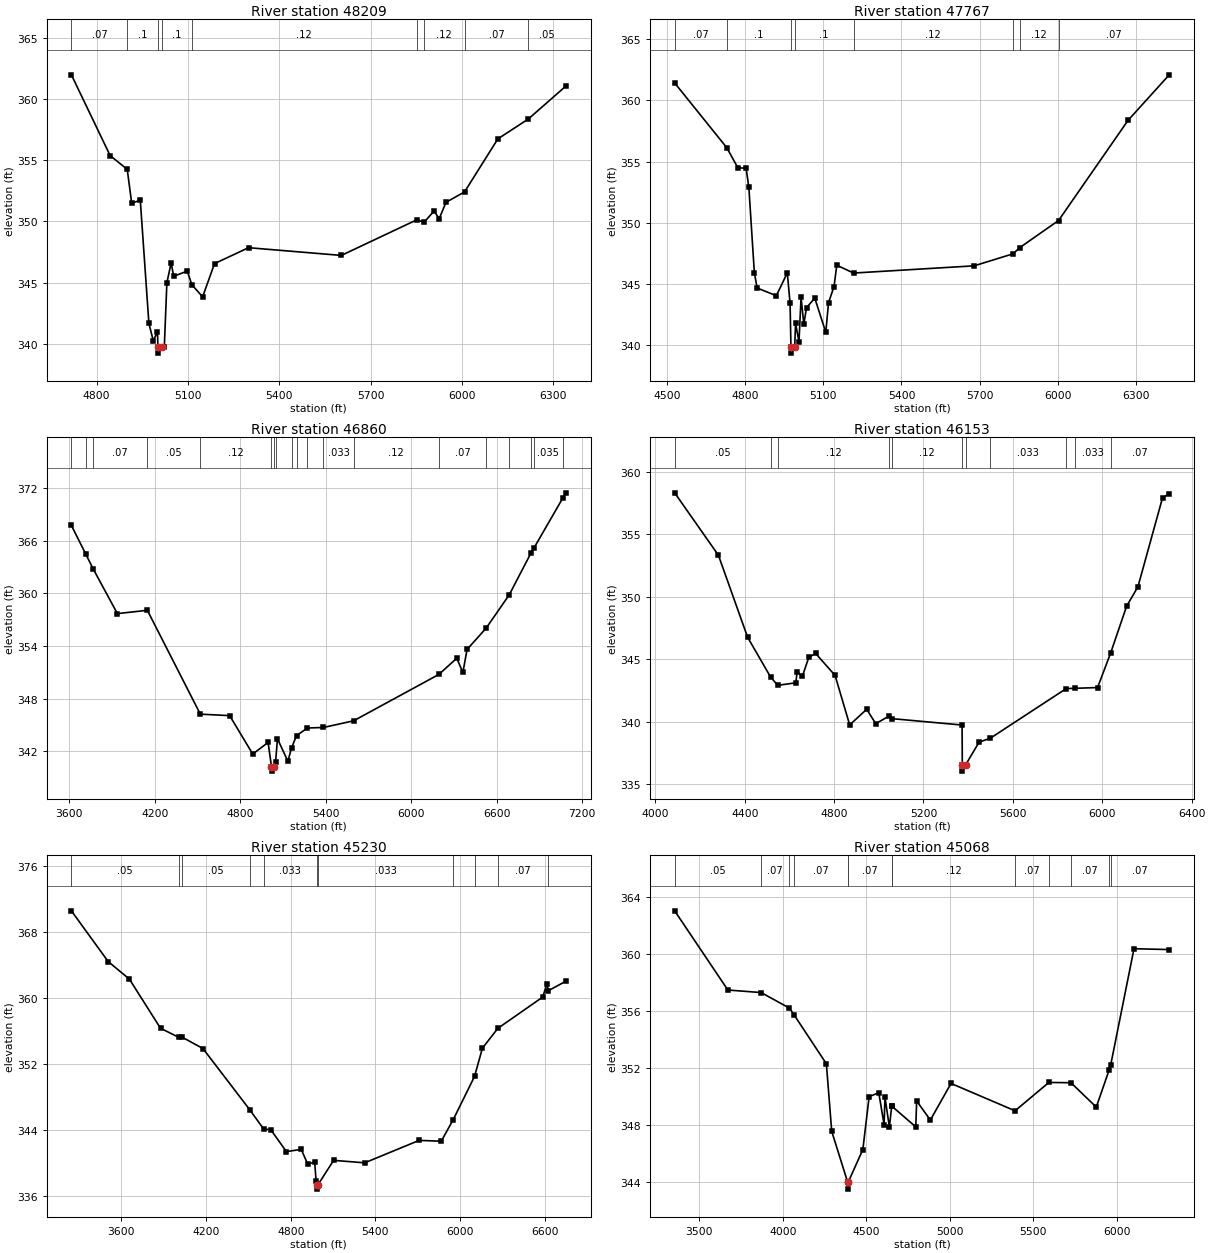
Type RM Length L Ch R = 1 ,48209   ,442,442,442
BEGIN DESCRIPTION:
BRUSHY CREEK 48.0
END DESCRIPTION:
XS GIS Cut Line= 3
      2384225.01     13605175.01        2384425.       13605375.
      2385625.02     13605975.01
#Sta/Elev= 30
  4717.3  361.96  4844.6  355.37  4900.7  354.25  4915.3   351.5  4943.6  351.72
  4971.8   341.7    4986  340.29  5000.1  340.97  5001.4  339.76  5001.9  339.26
  5015.7  339.76  5022.5  339.77  5030.9     345  5044.9  346.62  5053.2  345.53
    5098  345.95  5112.7  344.85  5148.3  343.85  5187.4  346.56  5299.2  347.86
  5603.9  347.23  5851.5  350.13  5875.9  349.94  5908.5  350.85  5925.3  350.22
  5947.7  351.56  6008.6  352.41  6118.2  356.74  6217.8  358.35  6341.8  361.05
#Mann= 9 ,-1 , 0
  4717.3     .07       0  4900.7      .1       0  5001.4     .05       0
  5015.7      .1       0  5112.7     .12       0  5851.5     .07       0
  5875.9     .12       0  6008.6     .07       0  6217.8     .05       0
Bank Sta=5001.4,5015.7
XS Rating Curve= 0 ,0
Exp/Cntr=0.3,0.1

Type RM Length L Ch R = 1 ,47767   ,907,907,907
BEGIN DESCRIPTION:
BRUSHY CREEK 47.0
END DESCRIPTION:
XS GIS Cut Line= 3
      2384124.99     13605224.96        2384275.       13605675.
        2385625.       13606125.
#Sta/Elev= 30
  4529.9  361.42  4729.8  356.13  4772.4  354.49    4804  354.45  4814.5   352.9
  4835.6  345.93  4846.2  344.67    4920  344.04  4962.1  345.91  4972.7  343.41
    4976  339.85  4976.5  339.35  4990.4  339.85  4993.7  341.77  5006.9  340.29
  5014.8   343.9  5025.4  341.72  5035.9  343.07  5067.5  343.84  5109.7  341.05
  5120.2  343.47  5141.3  344.79  5151.9  346.53  5216.2  345.89  5678.9  346.48
  5827.9  347.46    5854  347.97  6002.6  350.18  6269.2  358.36  6427.3  362.08
#Mann= 8 ,-1 , 0
  4529.9     .07       0  4729.8      .1       0    4976     .05       0
  4990.4      .1       0  5216.2     .12       0  5827.9     .07       0
    5854     .12       0  6002.6     .07       0
Bank Sta=4976,4990.4
XS Rating Curve= 0 ,0
Exp/Cntr=0.3,0.1

Type RM Length L Ch R = 1 ,46860   ,707,707,707
BEGIN DESCRIPTION:
BRUSHY CREEK 46.0
END DESCRIPTION:
XS GIS Cut Line= 3
      2383325.02     13605025.04        2384025.       13606225.
      2385825.03     13607275.02
#Sta/Elev= 30
  3614.2  367.75  3714.5   364.5  3767.5  362.78  3937.1  357.69  4147.5  358.07
  4519.5  346.22  4725.6  346.05  4887.6  341.67  4995.5  342.99  5019.3  340.22
  5019.8  339.72  5033.8  340.22    5048  340.75  5061.3  343.41  5134.5  340.84
    5160  342.37  5195.4  343.78    5272  344.64    5384   344.7  5595.8  345.46
  6194.5  350.75  6320.3   352.6  6363.3  350.98  6392.6   353.6  6527.4  356.05
  6688.3  359.82    6840  364.56  6861.3  365.14    7064  370.85  7087.3  371.47
#Mann= 19 ,-1 , 0
  3614.2     .07       0  3714.5     .05       0  3767.5     .07       0
  4147.5     .05       0  4519.5     .12       0  5019.3     .05       0
  5033.8     .12       0    5048     .07       0    5160    .033       0
  5195.4     .07       0    5272      .1       0    5384    .033       0
  5595.8     .12       0  6194.5     .07       0  6527.4     .12       0
  6688.3     .07       0    6840     .05       0  6861.3    .035       0
    7064     .05       0
Bank Sta=5019.3,5033.8
XS Rating Curve= 0 ,0
Exp/Cntr=0.3,0.1

Type RM Length L Ch R = 1 ,46153   ,923,923,923
BEGIN DESCRIPTION:
BRUSHY CREEK 45.0
END DESCRIPTION:
XS GIS Cut Line= 3
      2383024.99     13605474.98      2383567.35     13606742.05
        2383625.     13607574.99
#Sta/Elev= 30
  4086.5  358.32  4282.4  353.32  4412.9  346.76  4515.6  343.58  4547.8  342.91
  4628.9  343.11  4634.4     344    4658  343.63    4687  345.16  4717.4  345.46
  4804.4   343.7  4869.7  339.74  4945.9  340.99  4986.3  339.84  5047.1  340.46
    5060  340.24  5372.7  339.73  5373.7  336.54  5374.2  336.04  5388.3  336.54
  5448.9  338.36  5499.6  338.68  5838.8  342.65  5877.6  342.67  5978.9  342.73
  6037.5   345.5  6109.3  349.26  6159.4  350.79  6269.6  357.92  6299.7  358.25
#Mann= 11 ,-1 , 0
  4086.5     .05       0  4515.6     .07       0  4547.8     .12       0
  5047.1    .033       0    5060     .12       0  5373.7     .05       0
  5388.3     .12       0  5499.6    .033       0  5838.8     .12       0
  5877.6    .033       0  6037.5     .07       0
Bank Sta=5373.7,5388.3
XS Rating Curve= 0 ,0
Exp/Cntr=0.3,0.1

Type RM Length L Ch R = 1 ,45230   ,162,162,162
BEGIN DESCRIPTION:
BRUSHY CREEK 44.0
END DESCRIPTION:
XS GIS Cut Line= 3
        2382975.     13604925.04      2382846.41     13606742.05
      2383874.99     13608074.98
#Sta/Elev= 30
  3245.7  370.58  3506.3  364.43  3656.7   362.3  3877.2  356.34  4007.5  355.23
  4031.5  355.25    4178  353.88  4509.1  346.47  4607.7  344.13  4659.2  344.03
  4769.5  341.38  4874.7  341.65  4919.8  339.89    4970  340.08    4980  337.82
    4988  337.33  4988.3  336.83    4992  337.33  5104.2  340.32  5324.3  340.02
  5710.2  342.74  5866.7  342.64  5951.2  345.24  6102.8   350.5  6158.5  353.92
  6268.1  356.33  6586.7  360.13    6615  361.72  6626.6   360.9  6750.9  362.05
#Mann= 11 ,-1 , 0
  3245.7     .05       0  4007.5     .07       0  4031.5     .05       0
  4509.1     .12       0  4607.7    .033       0    4988    .033       0
    4992    .033       0  5951.2     .07       0  6102.8     .12       0
  6268.1     .07       0  6626.6     .05       0
Bank Sta=4988,4992
XS Rating Curve= 0 ,0
Exp/Cntr=0.3,0.1

Type RM Length L Ch R = 1 ,45068   ,477,477,477
BEGIN DESCRIPTION:
F21661
END DESCRIPTION:
XS GIS Cut Line= 5
      2382467.19     13605086.43      2382503.65     13606128.13
      2382618.23     13606477.08      2383024.48     13607628.13
      2383185.93     13607919.77
#Sta/Elev= 30
  3351.8  363.01  3670.6  357.45  3870.2  357.27  4039.5  356.18    4066  355.73
  4260.9  352.27  4292.9  347.53  4388.1  343.97  4388.3  343.47  4392.1  343.97
  4479.5  346.25  4517.1  349.96  4574.9  350.24  4606.7  347.99    4612  349.92
  4638.5  347.83  4652.4  349.31  4652.5   349.3  4796.6  347.84  4801.9  349.66
    4884  348.32  5007.8  350.89  5391.5  348.97  5594.2  350.96  5726.5  350.94
  5878.2  349.23  5955.7  351.85  5964.1  352.16  6104.2  360.35  6315.4  360.29
#Mann= 13 ,-1 , 0
  3351.8     .05       0  3870.2     .07       0  4039.5     .05       0
    4066     .07       0  4388.1     .05       0  4392.1     .07       0
  4652.4     .05       0  4652.5     .12       0  5391.5     .07       0
  5594.2      .1       0  5726.5     .07       0  5955.7     .05       0
  5964.1     .07       0
Bank Sta=4388.1,4392.1
XS Rating Curve= 0 ,0
Exp/Cntr=0.3,0.1

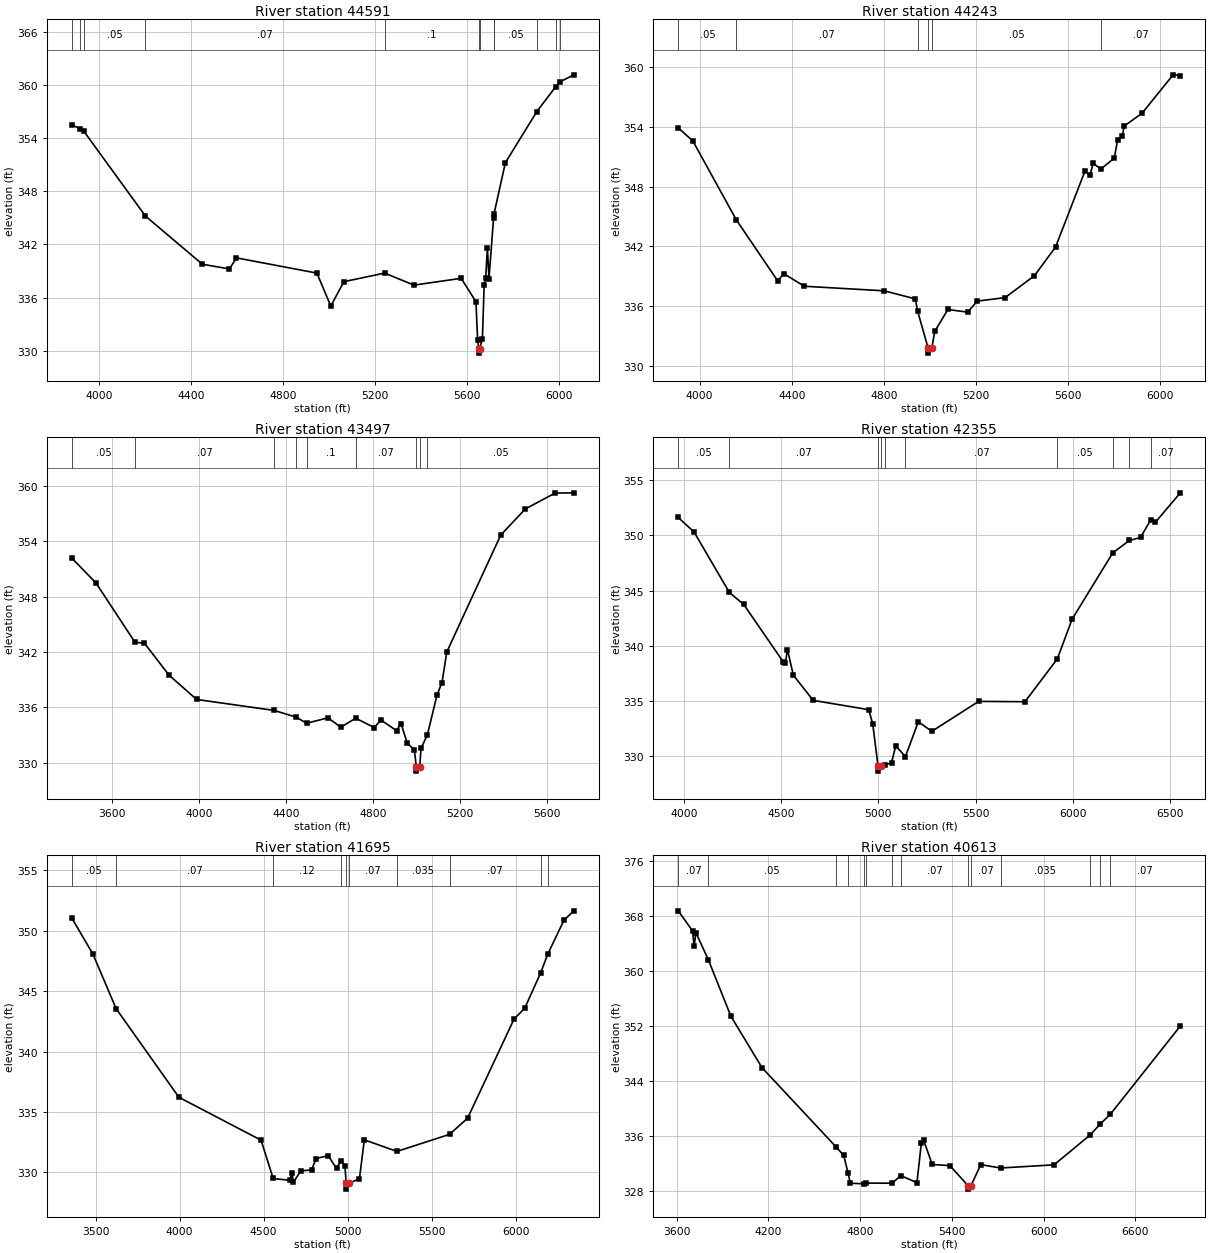
Type RM Length L Ch R = 1 ,44591   ,348,348,348
BEGIN DESCRIPTION:
BRUSHY CREEK 43.0
END DESCRIPTION:
XS GIS Cut Line= 3
      2381875.02     13606025.03        2382375.       13607025.
      2383074.99     13607824.99
#Sta/Elev= 30
    3882  355.53  3918.8  355.08    3935  354.78    4202  345.21  4449.4  339.76
  4566.8  339.23  4597.5  340.48  4946.9  338.76  5007.1  335.03  5064.1  337.79
    5241  338.76  5368.7   337.4  5573.7  338.17  5637.8  335.52  5644.9  331.22
  5649.6  330.21  5649.8  329.71  5653.6  330.21  5665.8  331.35  5673.4  337.38
    5680  338.22  5687.6  341.61  5694.3  338.13  5714.3  344.96  5716.1  345.44
  5765.5  351.24  5902.1  357.02  5984.3  359.84  6002.8  360.39    6063  361.18
#Mann= 12 ,-1 , 0
    3882     .05       0  3918.8     .07       0    3935     .05       0
    4202     .07       0    5241      .1       0  5649.6     .05       0
  5653.6      .1       0  5714.3     .07       0  5716.1     .05       0
  5902.1     .07       0  5984.3     .05       0  6002.8     .07       0
Bank Sta=5649.6,5653.6
XS Rating Curve= 0 ,0
Exp/Cntr=0.3,0.1

Type RM Length L Ch R = 1 ,44243   ,746,746,746
BEGIN DESCRIPTION:
BRUSHY CREEK 42.0
END DESCRIPTION:
XS GIS Cut Line= 3
        2381725.     13606224.99      2382036.37     13607155.17
      2382830.11      13608054.2
#Sta/Elev= 30
    3907   353.9  3970.3  352.59  4159.8  344.65  4339.4  338.53  4364.8  339.28
  4454.2  338.01  4801.5  337.55  4936.6  336.74  4946.1  335.55  4992.1   331.8
  4992.6   331.3  5008.1   331.8  5021.1  333.49  5077.9  335.68  5163.3  335.41
  5205.9  336.52  5326.4  336.87  5453.5  339.06  5545.6  341.95  5673.6  349.59
  5694.5  349.13  5708.7  350.33  5742.7  349.78  5800.7  350.87  5814.9  352.68
  5835.8  353.12  5843.4  354.08  5921.2  355.37  6055.9  359.22  6087.2  359.15
#Mann= 6 ,-1 , 0
    3907     .05       0  4159.8     .07       0  4946.1     .05       0
  4992.1     .05       0  5008.1     .05       0  5742.7     .07       0
Bank Sta=4992.1,5008.1
XS Rating Curve= 0 ,0
Exp/Cntr=0.3,0.1

Type RM Length L Ch R = 1 ,43497   ,1142,1142,1142
BEGIN DESCRIPTION:
X18325
END DESCRIPTION:
XS GIS Cut Line= 3
      2381566.55     13606328.95      2381922.96     13607940.91
      2382205.93     13608531.09
#Sta/Elev= 30
  3416.8  352.18    3528  349.48  3706.7  343.07  3750.7  342.95  3863.4   339.5
    3990  336.87  4346.4  335.68    4448  334.95  4494.8  334.29  4593.2  334.88
    4652  333.87  4720.7  334.84  4805.6  333.83  4836.3  334.65    4908  333.49
  4928.5  334.26  4957.7  332.12    4990  331.42  4998.5  329.61    4999  329.11
  5014.5  329.61  5020.7  331.57  5049.9  333.06  5094.4   337.4  5116.6  338.67
  5138.8  342.01  5386.5  354.67  5499.8   357.5  5635.7  359.21  5722.2  359.24
#Mann= 9 ,-1 , 0
  3416.8     .05       0  3706.7     .07       0  4346.4     .05       0
    4448     .07       0  4494.8      .1       0  4720.7     .07       0
  4998.5     .05       0  5014.5     .07       0  5049.9     .05       0
Bank Sta=4998.5,5014.5
XS Rating Curve= 0 ,0
Exp/Cntr=0.3,0.1

Type RM Length L Ch R = 1 ,42355   ,660,660,660
BEGIN DESCRIPTION:
BRUSHY CREEK 41.0
END DESCRIPTION:
XS GIS Cut Line= 3
        2381475.     13606325.01        2381275.       13607325.
      2381890.29     13608758.43
#Sta/Elev= 30
  3971.5  351.62  4053.1   350.3    4234  344.84    4308  343.75    4512  338.53
  4522.2  338.44  4532.4  339.67    4563  337.35    4665  335.07  4950.5  334.23
  4970.9  332.93  4997.7  329.17  4998.2  328.67  5013.8  329.17  5033.1  329.22
  5067.5  329.44  5089.2  330.96  5138.6  329.98  5205.1  333.14  5274.2  332.27
  5515.1  334.98  5753.1  334.95  5919.1  338.82  5995.3  342.42  6204.2  348.42
  6289.7  349.54  6346.9  349.81  6398.3  351.38    6423  351.18  6551.2  353.85
#Mann= 10 ,-1 , 0
  3971.5     .05       0    4234     .07       0  4997.7     .05       0
  5013.8     .07       0  5033.1      .1       0  5138.6     .07       0
  5919.1     .05       0  6204.2     .07       0  6289.7     .05       0
  6398.3     .07       0
Bank Sta=4997.7,5013.8
XS Rating Curve= 0 ,0
Exp/Cntr=0.3,0.1

Type RM Length L Ch R = 1 ,41695   ,1082,1082,1082
BEGIN DESCRIPTION:
X18324
END DESCRIPTION:
XS GIS Cut Line= 4
      2381428.82     13606337.07      2380780.81     13607560.19
      2381299.23     13608273.03      2381833.84     13608759.04
#Sta/Elev= 30
  3358.3  351.06    3485  348.05    3622  343.56    3996  336.22  4484.9  332.67
    4557   329.5  4655.2  329.35  4668.7  329.95  4677.2  329.18  4721.2  330.13
  4785.5  330.21  4812.8  331.15  4884.4  331.39  4934.1  330.33  4959.8  330.98
  4984.3  330.54    4991  329.12  4991.5  328.62  5007.1  329.12  5070.1  329.46
  5099.5   332.7  5293.3  331.74  5606.5  333.15  5714.1  334.49  5990.4  342.69
    6054  343.59  6148.9  346.52  6192.1   348.1  6287.8  350.88  6346.4  351.65
#Mann= 10 ,-1 , 0
  3358.3     .05       0    3622     .07       0    4557     .12       0
  4959.8     .07       0    4991     .05       0  5007.1     .07       0
  5293.3    .035       0  5606.5     .07       0  6148.9     .05       0
  6192.1     .07       0
Bank Sta=4991,5007.1
XS Rating Curve= 0 ,0
Exp/Cntr=0.3,0.1

Type RM Length L Ch R = 1 ,40613   ,463,463,463
BEGIN DESCRIPTION:
BRUSHY CREEK 40.0
END DESCRIPTION:
XS GIS Cut Line= 3
      2379575.02     13606525.03        2380275.       13607725.
      2381817.64     13608823.84
#Sta/Elev= 30
  3610.5  368.78  3704.3  365.86  3714.2  363.63  3726.2   365.6  3807.8  361.65
  3954.9  353.46  4158.3  345.99  4641.6   334.5  4692.5  333.24  4721.7  330.62
  4735.5   329.2  4827.6  329.11  4837.7  329.22  5008.5   329.2  5065.8   330.3
  5171.6  329.28  5200.1  335.03  5214.9  335.47  5271.4  331.92    5387  331.76
  5505.6  328.84  5506.1  328.34  5525.1  328.84  5588.6   331.9  5718.6  331.41
  6067.9  331.87  6303.3  336.19  6371.7  337.84  6435.3  339.19  6893.7  352.04
#Mann= 14 ,-1 , 0
  3610.5     .07       0  3807.8     .05       0  4641.6     .07       0
  4721.7    .033       0  4827.6     .07       0  4837.7    .033       0
  5008.5     .12       0  5065.8     .07       0  5505.6    .033       0
  5525.1     .07       0  5718.6    .035       0  6303.3     .07       0
  6371.7    .035       0  6435.3     .07       0
Bank Sta=5505.6,5525.1
XS Rating Curve= 0 ,0
Exp/Cntr=0.3,0.1