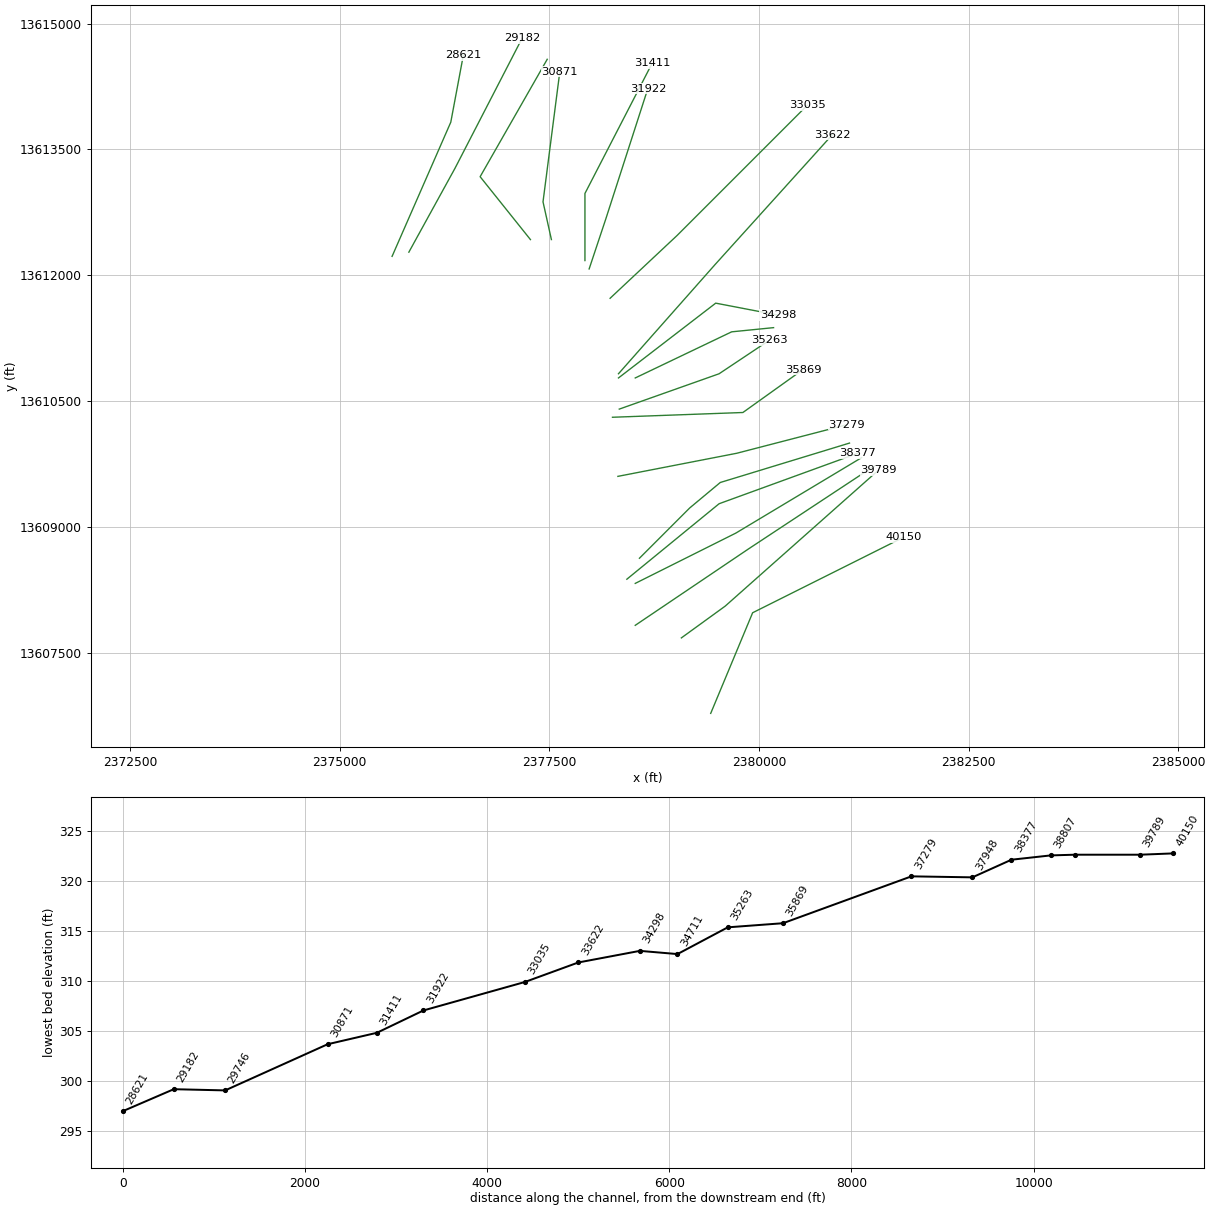
HEC-RAS study BRUSHY CREEK.prj: BRUSHY CREEK Base Level Engineering

--- BRUSHY CREEK.g01 (geometry) --- (continued)

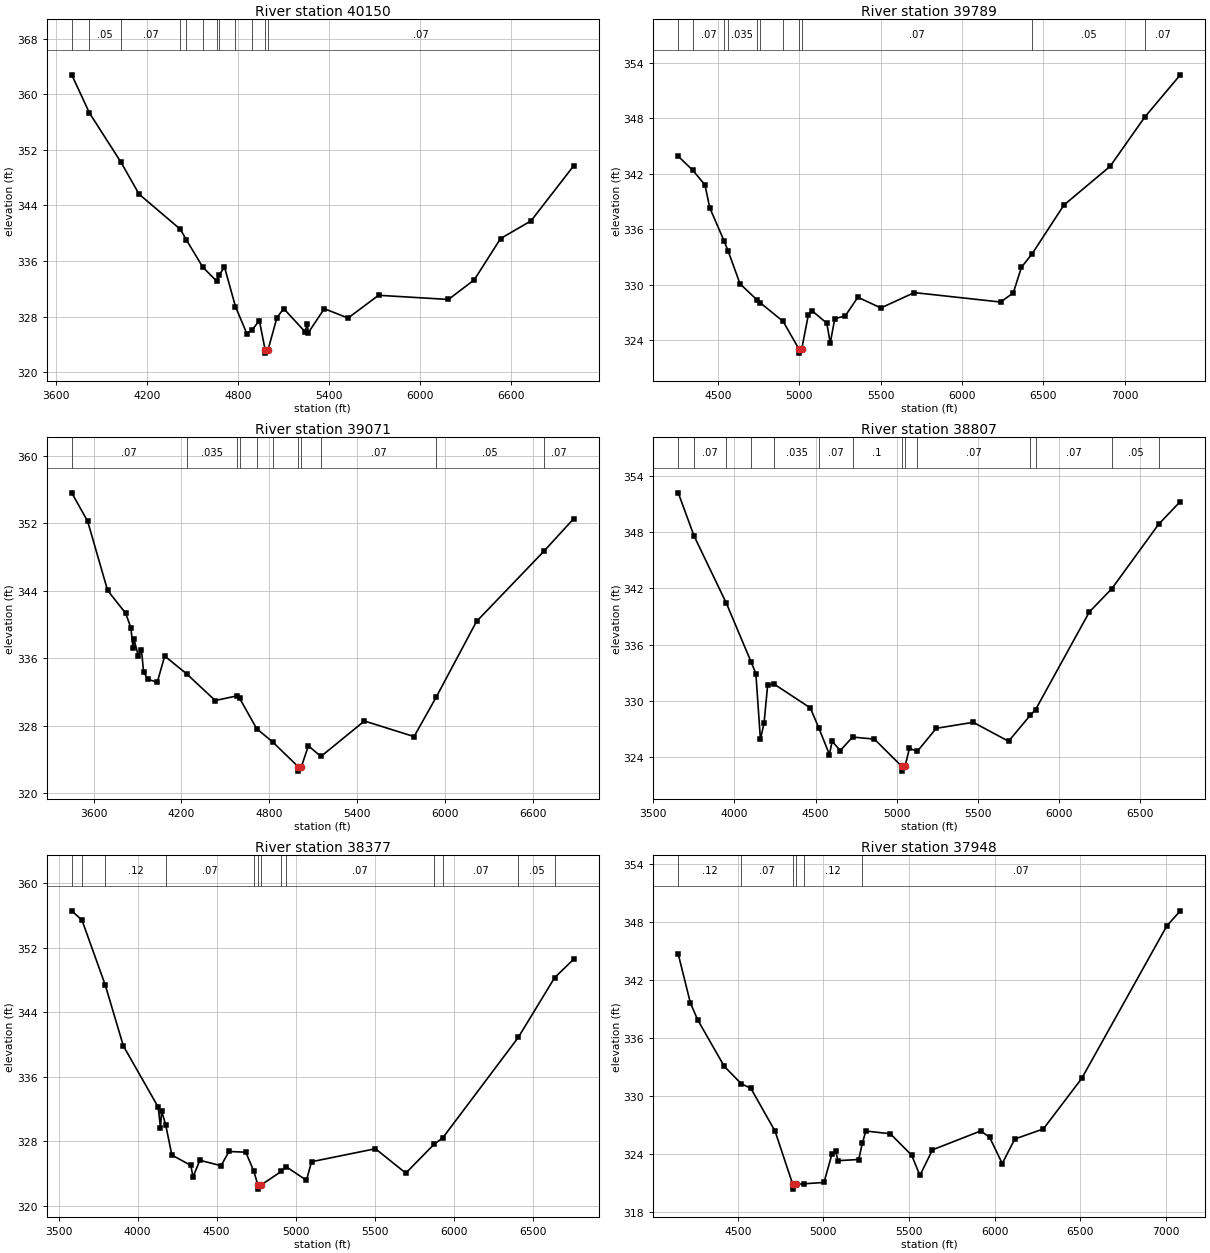
Type RM Length L Ch R = 1 ,40150   ,361,361,361
BEGIN DESCRIPTION:
BRUSHY CREEK 39.0
END DESCRIPTION:
XS GIS Cut Line= 3
      2379424.99     13606774.96        2379925.       13607975.
        2381725.       13608875.
#Sta/Elev= 30
    3704  362.81  3820.5  357.32  4027.6  350.26  4148.2  345.62  4420.2  340.57
  4459.8  339.05  4567.9  335.13  4659.3  333.11  4675.9  333.92  4711.5  335.14
    4784  329.43  4859.4  325.52    4892  326.02  4941.7  327.42  4979.6  323.23
  4980.1  322.73  4999.2  323.23  5057.1   327.8  5101.9  329.15  5241.6  325.84
  5258.4  326.92    5264  325.65  5370.2  329.13  5526.7  327.78    5728  331.06
  6189.2  330.46  6359.7  333.29    6533  339.23  6734.2  341.78  7016.5  349.74
#Mann= 12 ,-1 , 0
    3704     .07       0  3820.5     .05       0  4027.6     .07       0
  4420.2     .05       0  4459.8     .07       0  4567.9     .05       0
  4659.3    .033       0  4675.9    .035       0    4784    .033       0
    4892     .07       0  4979.6     .05       0  4999.2     .07       0
Bank Sta=4979.6,4999.2
XS Rating Curve= 0 ,0
Exp/Cntr=0.3,0.1

Type RM Length L Ch R = 1 ,39789   ,718,718,718
BEGIN DESCRIPTION:
BRUSHY CREEK 38.0
END DESCRIPTION:
XS GIS Cut Line= 3
      2379075.01       13607675.      2379598.14     13608054.32
      2381424.99     13609674.99
#Sta/Elev= 30
  4254.9  343.87  4344.2  342.36  4419.2  340.78  4448.6  338.31    4536  334.76
  4562.1  333.62  4634.9  330.09    4737  328.39    4758  328.06    4900  326.03
  4995.5   323.1    4996   322.6  5015.1   323.1  5055.5  326.76  5076.4   327.2
  5168.4  325.84  5190.1   323.7  5217.7  326.32  5282.1  326.62  5359.9  328.64
  5501.2  327.48    5707  329.14    6238  328.12  6315.8  329.11    6366  331.88
  6431.2  333.32  6627.7  338.61  6911.3  342.78  7123.5  348.08  7343.2  352.67
#Mann= 11 ,-1 , 0
  4254.9     .12       0  4344.2     .07       0    4536     .05       0
  4562.1    .035       0    4737     .07       0    4758    .035       0
    4900     .07       0  4995.5     .05       0  5015.1     .07       0
  6431.2     .05       0  7123.5     .07       0
Bank Sta=4995.5,5015.1
XS Rating Curve= 0 ,0
Exp/Cntr=0.3,0.1

Type RM Length L Ch R = 1 ,39071   ,264,264,264
BEGIN DESCRIPTION:
BRUSHY CREEK 37.0
END DESCRIPTION:
XS GIS Cut Line= 3
      2378524.99     13607824.99      2379873.56     13608734.75
      2381374.97     13609724.98
#Sta/Elev= 30
  3451.5  355.64  3560.1  352.25  3695.9  344.06  3818.7  341.35  3854.7  339.63
  3869.7  337.17  3875.7  338.25  3905.7  336.28  3926.7  337.03  3941.6  334.38
  3970.2  333.51  4034.6  333.15  4085.5  336.26  4235.8  334.14  4430.3  330.98
  4579.7  331.54  4596.1  331.27  4712.5  327.65  4822.6  326.05  4997.8   323.1
  4998.3   322.6  5017.4   323.1  5065.8   325.6  5151.4  324.34  5448.2  328.55
  5786.7   326.7  5937.6  331.38  6212.9  340.37  6673.8  348.73  6876.8  352.59
#Mann= 11 ,-1 , 0
  3451.5     .07       0  4235.8    .035       0  4579.7     .07       0
  4596.1    .035       0  4712.5     .07       0  4822.6      .1       0
  4997.8     .05       0  5017.4      .1       0  5151.4     .07       0
  5937.6     .05       0  6673.8     .07       0
Bank Sta=4997.8,5017.4
XS Rating Curve= 0 ,0
Exp/Cntr=0.3,0.1

Type RM Length L Ch R = 1 ,38807   ,430,430,430
BEGIN DESCRIPTION:
BRUSHY CREEK 36.0
END DESCRIPTION:
XS GIS Cut Line= 3
      2378525.02     13608325.01        2379725.       13608925.
        2381225.       13609825.
#Sta/Elev= 30
  3654.2  352.17  3751.8  347.57    3951  340.39    4104  334.11  4132.1  332.92
  4160.1  325.93  4182.4  327.63  4204.8  331.72  4245.2  331.79  4467.5  329.26
  4519.8  327.12  4584.9   324.3  4601.7   325.7    4652  324.72  4727.1  326.16
  4861.7  325.94  5030.7  323.03  5031.2  322.53  5050.3  323.03  5077.5  324.95
  5125.6  324.63  5242.7  327.09  5470.1  327.73  5687.8  325.71  5820.3  328.46
  5853.6  329.07  6185.3  339.49  6323.9  341.97  6612.4  348.84  6745.1  351.24
#Mann= 14 ,-1 , 0
  3654.2    .035       0  3751.8     .07       0    3951     .12       0
    4104     .07       0  4245.2    .035       0  4519.8     .07       0
  4727.1      .1       0  5030.7     .05       0  5050.3      .1       0
  5125.6     .07       0  5820.3     .05       0  5853.6     .07       0
  6323.9     .05       0  6612.4     .07       0
Bank Sta=5030.7,5050.3
XS Rating Curve= 0 ,0
Exp/Cntr=0.3,0.1

Type RM Length L Ch R = 1 ,38377   ,429,429,429
BEGIN DESCRIPTION:
BRUSHY CREEK 35.0
END DESCRIPTION:
XS GIS Cut Line= 3
      2378424.97     13608374.97        2379525.       13609275.
      2381174.98     13609874.99
#Sta/Elev= 30
  3583.7  356.55  3648.4  355.39  3795.6  347.36  3910.3  339.82  4130.7  332.25
  4145.1  329.69  4152.3  331.77    4178  330.06  4216.9  326.32  4336.7  325.04
  4351.1  323.61  4394.2  325.67  4528.4     325  4578.6  326.76  4684.9  326.67
  4735.6  324.32  4761.2   322.6  4761.7   322.1  4780.8   322.6  4910.8  324.31
  4939.2  324.89  5068.9  323.19  5100.8  325.49  5505.1   327.1  5697.3  324.08
    5875  327.63  5931.3  328.45  6409.1  340.88  6639.3  348.28  6760.7  350.58
#Mann= 13 ,-1 , 0
  3583.7    .035       0  3648.4     .07       0  3795.6     .12       0
    4178     .07       0  4735.6     .12       0  4761.2     .05       0
  4780.8     .12       0  4910.8      .1       0  4939.2     .07       0
    5875     .05       0  5931.3     .07       0  6409.1     .05       0
  6639.3     .07       0
Bank Sta=4761.2,4780.8
XS Rating Curve= 0 ,0
Exp/Cntr=0.3,0.1

Type RM Length L Ch R = 1 ,37948   ,669,669,669
BEGIN DESCRIPTION:
BRUSHY CREEK 34.0
END DESCRIPTION:
XS GIS Cut Line= 4
      2378575.01     13608625.01        2379175.       13609225.
      2379538.97     13609528.31       2381080.3     13609998.35
#Sta/Elev= 30
  4151.6   344.7  4222.3  339.65  4264.7   337.9  4420.3  333.07  4519.9  331.26
  4575.8  330.79  4717.3  326.35  4820.6  320.84  4821.1  320.34  4840.3  320.84
    4884  320.89  5003.4  321.03  5050.2  324.01  5071.1  324.27  5085.4  323.29
  5206.4  323.41  5226.9  325.09  5248.1  326.36  5390.6  326.08  5515.4  323.86
  5563.8  321.76    5637  324.41  5919.3  326.37  5971.6   325.7  6044.8  322.99
  6117.9  325.53  6285.2  326.58  6509.1  331.81  7006.6  347.62  7085.3  349.18
#Mann= 6 ,-1 , 0
  4151.6     .12       0  4519.9     .07       0  4820.6     .05       0
  4840.3     .07       0    4884     .12       0  5226.9     .07       0
Bank Sta=4820.6,4840.3
XS Rating Curve= 0 ,0
Exp/Cntr=0.3,0.1

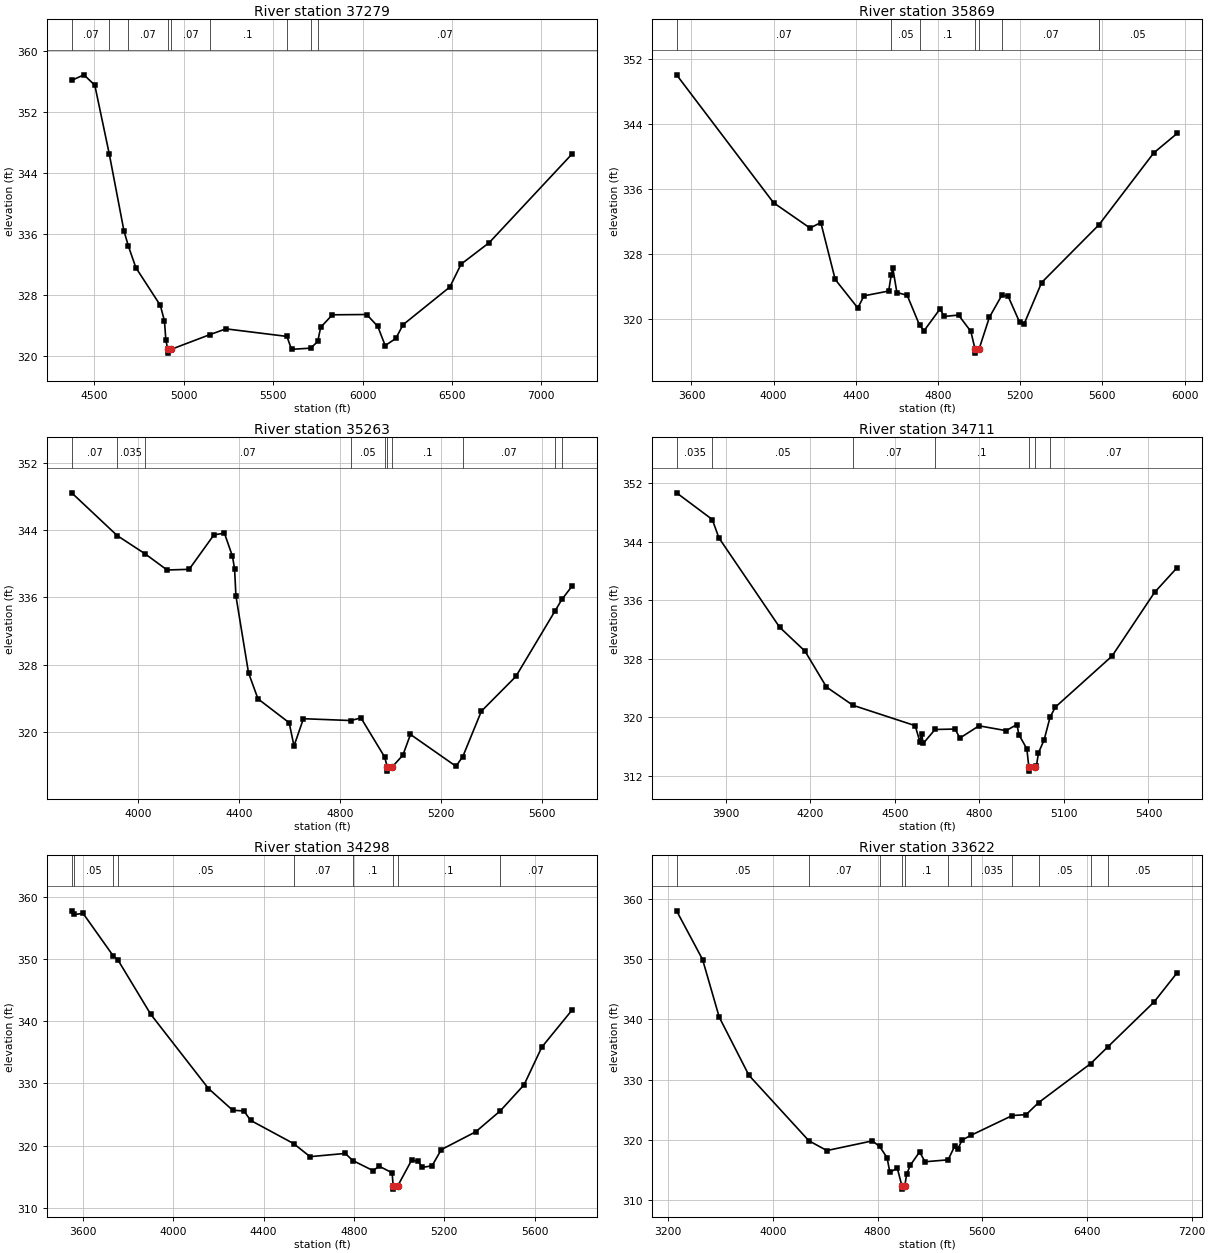
Type RM Length L Ch R = 1 ,37279   ,1410,1410,1410
BEGIN DESCRIPTION:
BRUSHY CREEK 33.0
END DESCRIPTION:
XS GIS Cut Line= 3
      2378318.25     13609601.49      2379735.85     13609876.91
      2381048.16     13610217.14
#Sta/Elev= 30
  4373.2  356.17  4441.2   356.9  4502.3  355.55  4583.4  346.52  4665.3  336.47
  4690.8  334.42    4732  331.64    4869  326.69  4892.1  324.64  4899.6   322.2
  4910.1  320.94  4910.6  320.44  4929.9  320.94  5144.3  322.85  5235.8  323.62
  5576.8  322.63  5602.5  320.94  5709.7  321.09  5749.2  321.97  5765.5  323.82
  5830.8  325.46    6023   325.5    6085  323.94  6126.3  321.43  6185.7  322.36
  6226.3  324.16  6487.9   329.1    6551   332.1  6708.1  334.91    7173  346.57
#Mann= 9 ,-1 , 0
  4373.2     .07       0  4583.4     .12       0  4690.8     .07       0
  4910.1     .05       0  4929.9     .07       0  5144.3      .1       0
  5576.8    .033       0  5709.7      .1       0  5749.2     .07       0
Bank Sta=4910.1,4929.9
XS Rating Curve= 0 ,0
Exp/Cntr=0.3,0.1

Type RM Length L Ch R = 1 ,35869   ,606,606,606
BEGIN DESCRIPTION:
BRUSHY CREEK 32.0
END DESCRIPTION:
XS GIS Cut Line= 3
      2378253.43     13610306.23      2379808.75     13610362.93
      2380524.98     13610874.98
#Sta/Elev= 30
  3527.7  350.05  3999.6  334.29  4177.4  331.17  4229.7  331.85  4299.8  324.84
  4409.9  321.32  4439.9  322.82    4560  323.41  4572.1  325.35    4580  326.27
    4600  323.23    4650  322.89  4710.1  319.22  4732.1  318.51  4810.1  321.21
  4830.1  320.28  4900.2  320.45  4960.2  318.43  4980.3  316.26  4980.8  315.76
  5000.1  316.26  5050.3  320.18  5110.4  322.87  5140.9   322.8  5197.8  319.55
  5218.7  319.32  5304.7  324.46  5583.9  331.58  5850.3  340.43  5964.5  342.84
#Mann= 7 ,-1 , 0
  3527.7     .07       0  4572.1     .05       0  4710.1      .1       0
  4980.3     .05       0  5000.1      .1       0  5110.4     .07       0
  5583.9     .05       0
Bank Sta=4980.3,5000.1
XS Rating Curve= 0 ,0
Exp/Cntr=0.3,0.1

Type RM Length L Ch R = 1 ,35263   ,552,552,552
BEGIN DESCRIPTION:
BRUSHY CREEK 31.0
END DESCRIPTION:
XS GIS Cut Line= 3
      2378334.52     13610403.45        2379525.       13610825.
      2380124.99     13611224.99
#Sta/Elev= 30
    3737  348.42  3917.2  343.34  4028.9  341.15  4115.1  339.25  4202.5  339.33
  4300.5  343.42  4342.2  343.63    4374  340.89  4382.5  339.39  4387.8  336.17
  4437.7  327.03  4475.2  323.94  4598.8   321.1    4618  318.34  4655.3  321.58
  4843.7  321.36  4883.2  321.68  4977.6  317.01  4987.4  315.85  4987.9  315.35
  5007.2  315.85  5049.5  317.25  5079.5  319.71  5259.8  315.93    5287  317.08
  5360.5  322.47  5497.2   326.6  5652.6  334.39  5679.6  335.75    5721  337.38
#Mann= 10 ,-1 , 0
    3737     .07       0  3917.2    .035       0  4028.9     .07       0
  4843.7     .05       0  4977.6      .1       0  4987.4     .05       0
  5007.2      .1       0    5287     .07       0  5652.6     .05       0
  5679.6     .07       0
Bank Sta=4987.4,5007.2
XS Rating Curve= 0 ,0
Exp/Cntr=0.3,0.1

Type RM Length L Ch R = 1 ,34711   ,413,413,413
BEGIN DESCRIPTION:
BRUSHY CREEK 30.0
END DESCRIPTION:
XS GIS Cut Line= 3
      2378524.99     13610774.99        2379675.       13611325.
      2380175.04       13611375.
#Sta/Elev= 30
  3724.8  350.64  3851.6     347    3875   344.5  4090.6  332.31  4180.8  329.04
  4256.9  324.15  4350.9  321.66  4571.8  318.88  4588.9  316.65  4594.5  317.74
  4600.5  316.46  4642.3  318.36  4713.4  318.42  4730.5  317.19  4798.5  318.86
  4894.8   318.2  4933.1  319.04  4940.1  317.65  4968.3  315.72  4975.5  313.18
    4976  312.68  4995.5  313.18  5002.1  313.34  5009.6  315.18  5029.7  316.95
  5050.8  320.05  5069.9  321.43  5270.9  328.38  5421.7  337.06  5502.1  340.45
#Mann= 7 ,-1 , 0
  3724.8    .035       0  3851.6     .05       0  4350.9     .07       0
  4642.3      .1       0  4975.5     .05       0  4995.5      .1       0
  5050.8     .07       0
Bank Sta=4975.5,4995.5
XS Rating Curve= 0 ,0
Exp/Cntr=0.3,0.1

Type RM Length L Ch R = 1 ,34298   ,676,676,676
BEGIN DESCRIPTION:
BRUSHY CREEK 29.0
END DESCRIPTION:
XS GIS Cut Line= 3
      2378325.03     13610775.02      2379484.74      13611667.1
        2380225.       13611525.
#Sta/Elev= 30
  3550.1  357.75  3562.3  357.16  3600.5  357.34  3733.7  350.52    3755  349.84
  3899.8  341.13  4155.6  329.18  4263.2  325.68    4313  325.57    4342  324.06
  4532.4  320.33  4605.7  318.22  4761.5  318.74  4794.6   317.6  4883.9  315.99
  4912.6  316.67  4969.1  315.62  4973.5   313.5    4974     313  4993.6   313.5
  5055.1  317.64  5084.8  317.48    5102  316.49  5145.9  316.75  5186.6  319.35
  5339.3  322.22  5447.8  325.58  5553.2  329.77    5632  335.84    5767  341.85
#Mann= 9 ,-1 , 0
  3550.1     .07       0  3562.3     .05       0  3733.7    .035       0
    3755     .05       0  4532.4     .07       0  4794.6      .1       0
  4973.5     .05       0  4993.6      .1       0  5447.8     .07       0
Bank Sta=4973.5,4993.6
XS Rating Curve= 0 ,0
Exp/Cntr=0.3,0.1

Type RM Length L Ch R = 1 ,33622   ,587,587,587
BEGIN DESCRIPTION:
BRUSHY CREEK 28.0
END DESCRIPTION:
XS GIS Cut Line= 3
        2378325.       13610825.        2379475.       13612125.
      2380874.99     13613674.99
#Sta/Elev= 30
    3265  358.01  3463.7  349.93  3590.8  340.37  3817.5  330.73  4275.8  319.86
  4413.1  318.24  4760.2  319.84    4816  318.92  4873.1  317.05    4894  314.63
  4950.9  315.32  4986.6  312.34  4987.1  311.84    5008  312.34    5022  314.27
  5050.3   315.8  5121.3  318.01  5163.2  316.38  5339.2   316.7  5390.4  319.01
  5411.3  318.42  5446.4  319.99  5516.9   320.8  5829.6  324.05  5935.1   324.2
  6029.7  326.18    6429  332.68  6560.6  335.47  6912.6  342.89  7089.3  347.75
#Mann= 11 ,-1 , 0
    3265     .05       0  4275.8     .07       0    4816      .1       0
  4986.6     .05       0    5008      .1       0  5339.2     .07       0
  5516.9    .035       0  5829.6     .07       0  6029.7     .05       0
    6429     .07       0  6560.6     .05       0
Bank Sta=4986.6,5008
XS Rating Curve= 0 ,0
Exp/Cntr=0.3,0.1

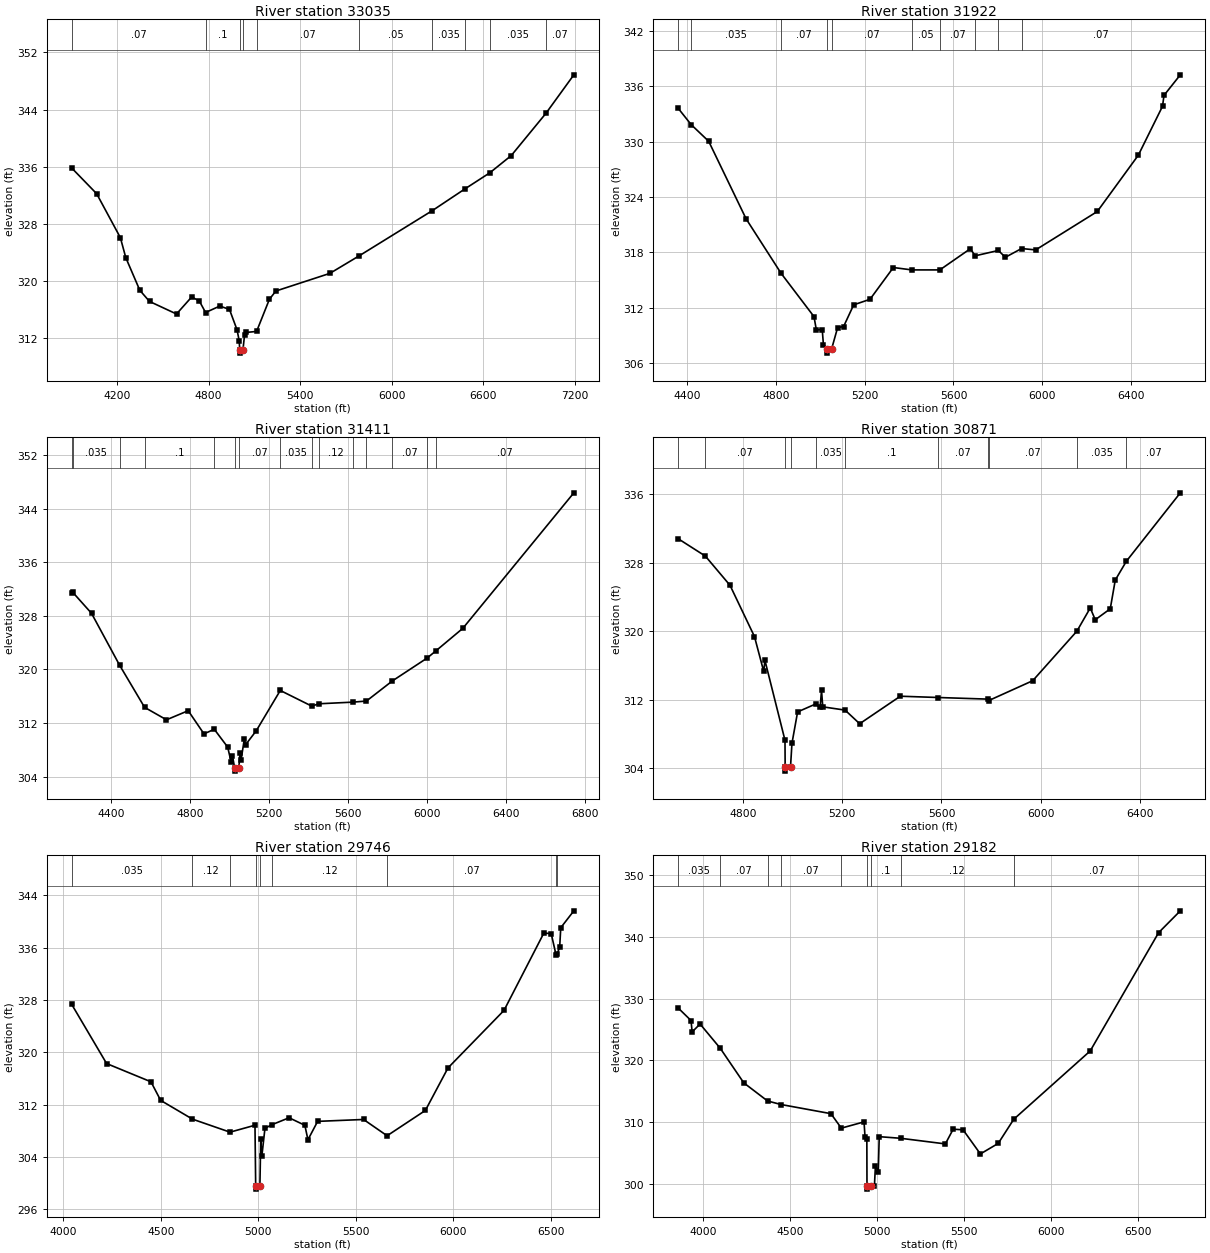
Type RM Length L Ch R = 1 ,33035   ,1113,1113,1113
BEGIN DESCRIPTION:
BRUSHY CREEK 27.0
END DESCRIPTION:
XS GIS Cut Line= 3
      2378225.01     13611725.01        2379025.       13612475.
      2380574.99     13614024.99
#Sta/Elev= 30
  3903.4  335.81  4066.3  332.22  4221.6  326.07  4257.3  323.26  4349.1  318.69
  4412.6  317.13  4589.4  315.37  4688.6  317.75  4738.4  317.21  4779.8  315.58
  4872.7  316.48  4936.2  316.02    4986  313.15    5000  311.62  5003.4  310.39
  5003.9  309.89  5024.8  310.39  5035.3  312.46  5042.4  312.78    5114  312.93
    5198  317.44  5240.4  318.59  5593.9  321.06  5787.6  323.54  6265.1  329.85
  6481.3  332.93  6641.8  335.15  6781.9  337.56  7009.3  343.48    7192  348.87
#Mann= 10 ,-1 , 0
  3903.4     .07       0  4779.8      .1       0  5003.4     .05       0
  5024.8      .1       0    5114     .07       0  5787.6     .05       0
  6265.1    .035       0  6481.3     .05       0  6641.8    .035       0
  7009.3     .07       0
Bank Sta=5003.4,5024.8
XS Rating Curve= 0 ,0
Exp/Cntr=0.3,0.1

Type RM Length L Ch R = 1 ,31922   ,511,511,511
BEGIN DESCRIPTION:
BRUSHY CREEK 26.0
END DESCRIPTION:
XS GIS Cut Line= 3
      2377974.99     13612074.97        2378175.       13612675.
      2378674.99     13614224.97
#Sta/Elev= 30
  4360.6  333.61  4419.1  331.84  4497.7  330.04  4666.3  321.62  4823.8  315.71
    4972  311.01  4982.5  309.58  5009.1   309.6  5014.4  307.98  5030.4  307.55
  5030.9  307.05  5051.9  307.55  5078.5  309.83  5105.2  309.93  5150.7  312.29
  5224.2  312.89  5329.3  316.34  5412.6  316.08  5538.7  316.08  5676.1  318.38
  5697.9  317.61  5802.4  318.19  5833.7  317.45  5906.9   318.4  5970.3  318.25
  6247.9  322.42  6432.6  328.53  6541.6  333.84  6548.2  335.02  6621.7  337.25
#Mann= 10 ,-1 , 0
  4360.6     .07       0  4419.1    .035       0  4823.8     .07       0
  5030.4     .05       0  5051.9     .07       0  5412.6     .05       0
  5538.7     .07       0  5697.9    .035       0  5802.4     .12       0
  5906.9     .07       0
Bank Sta=5030.4,5051.9
XS Rating Curve= 0 ,0
Exp/Cntr=0.3,0.1

Type RM Length L Ch R = 1 ,31411   ,540,540,540
BEGIN DESCRIPTION:
BRUSHY CREEK 25.0
END DESCRIPTION:
XS GIS Cut Line= 3
        2377925.       13612175.        2377925.       13612975.
      2378725.01     13614525.02
#Sta/Elev= 30
  4199.2  331.46  4204.8  331.49  4299.2  328.38  4441.4  320.64  4568.2  314.34
  4679.2  312.48  4789.2  313.84  4869.2  310.38  4921.3  311.07  4989.2  308.41
  5007.5  306.11  5013.1  307.15  5024.5  305.32    5025  304.82    5046  305.32
  5051.8  307.58  5057.4  306.54  5073.9  309.66  5079.6  308.74  5134.2  310.85
  5255.8  316.86  5415.6  314.52  5450.5  314.87  5624.9  315.12  5692.4  315.28
  5823.7  318.28  6000.2   321.7  6046.4  322.82  6180.8  326.13  6743.5  346.36
#Mann= 15 ,-1 , 0
  4199.2     .07       0  4204.8    .035       0  4441.4     .07       0
  4568.2      .1       0  4921.3     .07       0  5024.5     .05       0
    5046     .07       0  5255.8    .035       0  5415.6     .07       0
  5450.5     .12       0  5624.9     .07       0  5692.4     .12       0
  5823.7     .07       0  6000.2     .12       0  6046.4     .07       0
Bank Sta=5024.5,5046
XS Rating Curve= 0 ,0
Exp/Cntr=0.3,0.1

Type RM Length L Ch R = 1 ,30871   ,1125,1125,1125
BEGIN DESCRIPTION:
BRUSHY CREEK 24.0
END DESCRIPTION:
XS GIS Cut Line= 3
      2377525.01     13612424.97        2377425.       13612875.
      2377625.01     13614425.04
#Sta/Elev= 30
    4539  330.79  4648.3  328.77  4747.7  325.36  4846.3  319.38  4883.5  315.32
  4888.6  316.59  4969.3  307.28    4970  304.18  4970.5  303.68  4991.6  304.18
  4997.4  306.92  5020.2  310.59  5093.6  311.52  5110.9  311.11  5116.6  313.09
  5121.6  311.18  5211.5   310.8  5270.4  309.21  5434.2  312.42  5586.9  312.27
  5788.5  312.08  5790.5  311.91    5968  314.23    6146  320.01  6199.9  322.72
    6220  321.34  6280.5  322.62  6300.7  325.97  6345.5  328.17  6562.9  336.15
#Mann= 11 ,-1 , 0
    4539    .035       0  4648.3     .07       0    4970     .05       0
  4991.6     .07       0  5093.6    .035       0  5211.5      .1       0
  5586.9     .07       0  5788.5     .12       0  5790.5     .07       0
    6146    .035       0  6345.5     .07       0
Bank Sta=4970,4991.6
XS Rating Curve= 0 ,0
Exp/Cntr=0.3,0.1

Type RM Length L Ch R = 1 ,29746   ,564,564,564
BEGIN DESCRIPTION:
BRUSHY CREEK 23.0
END DESCRIPTION:
XS GIS Cut Line= 3
      2377275.03     13612424.96        2376675.       13613175.
      2377475.02     13614575.03
#Sta/Elev= 30
  4044.3   327.3  4222.8  318.27  4450.1  315.48  4499.8  312.64  4662.9  309.77
  4855.3  307.78  4983.2  308.84  4986.8  299.57  4987.3  299.07  5008.4  299.57
  5012.7  306.68  5018.5  304.15  5034.3  308.37  5069.8  308.92  5158.1  309.98
  5238.8  308.83  5254.6  306.62  5304.3  309.43  5539.7  309.72  5660.3  307.23
  5856.4   311.1  5972.3   317.6  6259.5   326.4  6463.9  338.24  6501.4  338.11
  6525.8  334.93  6531.1  335.02  6544.6  336.03  6550.3  339.04  6617.3  341.62
#Mann= 9 ,-1 , 0
  4044.3    .035       0  4662.9     .12       0  4855.3      .1       0
  4986.8     .05       0  5008.4      .1       0  5069.8     .12       0
  5660.3     .07       0  6525.8    .035       0  6531.1     .07       0
Bank Sta=4986.8,5008.4
XS Rating Curve= 0 ,0
Exp/Cntr=0.3,0.1

Type RM Length L Ch R = 1 ,29182   ,561,561,561
BEGIN DESCRIPTION:
BRUSHY CREEK 22.0
END DESCRIPTION:
XS GIS Cut Line= 3
      2375824.98     13612274.97        2376375.       13613275.
      2377175.01     13614825.02
#Sta/Elev= 30
  3858.5  328.46  3931.9  326.45  3938.4  324.61  3984.1  325.88  4099.7  321.97
  4235.2  316.37  4371.9  313.44  4449.1  312.87    4736  311.39  4795.8  309.05
  4926.4  310.06  4932.1  307.58  4942.5  307.23  4943.3  299.69  4943.8  299.19
    4965  299.69  4986.1  299.72  4991.8  302.97  5008.1  302.01  5013.7  307.67
  5136.6  307.41  5393.7   306.5  5438.7  308.88  5495.5  308.78    5595  304.88
  5697.5  306.58    5787  310.49  6226.3  321.53  6619.4  340.65  6744.1  344.18
#Mann= 9 ,-1 , 0
  3858.5    .035       0  4099.7     .07       0  4371.9    .035       0
  4449.1     .07       0  4795.8      .1       0  4943.3     .05       0
    4965      .1       0  5136.6     .12       0    5787     .07       0
Bank Sta=4943.3,4965
XS Rating Curve= 0 ,0
Exp/Cntr=0.3,0.1

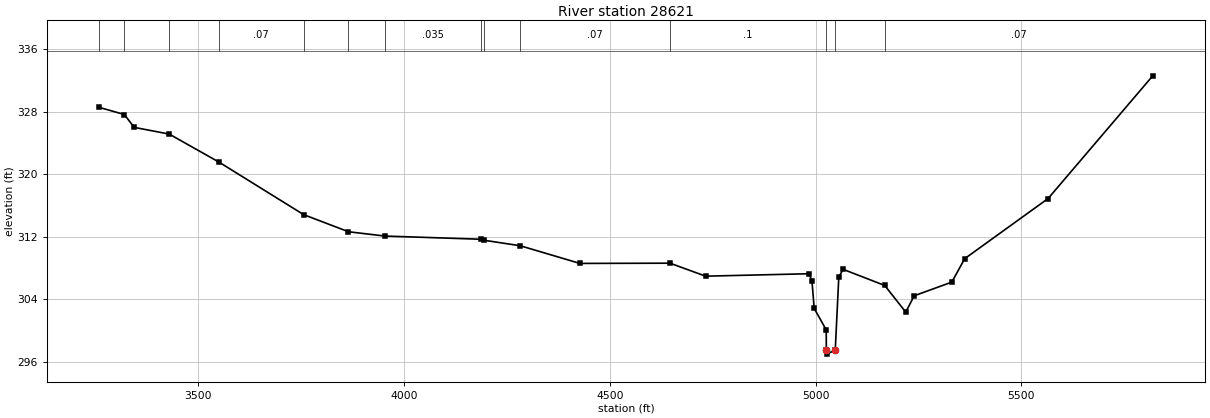
Type RM Length L Ch R = 1 ,28621   ,558,558,558
BEGIN DESCRIPTION:
BRUSHY CREEK 21.0
END DESCRIPTION:
XS GIS Cut Line= 3
      2375624.98     13612224.96        2376325.       13613825.
        2376475.     13614624.99
#Sta/Elev= 30
  3259.2  328.54  3320.1  327.63  3343.8  325.99  3429.1  325.13  3549.9  321.55
  3755.8  314.83  3864.8  312.64  3952.8  312.09  4186.7  311.68  4193.5  311.56
  4282.2  310.85  4427.2  308.59  4646.2  308.62  4732.8  306.96  4983.8  307.27
  4991.2   306.4  4996.7  302.84    5026  300.09  5026.2  297.49  5026.7  296.99
  5047.9  297.49  5056.5  306.81  5066.7  307.84  5168.2  305.77  5219.3  302.36
  5239.7  304.45  5331.2   306.2  5362.6   309.2  5565.3  316.89  5819.6  332.58
#Mann= 14 ,-1 , 0
  3259.2     .05       0  3320.1    .035       0  3429.1     .05       0
  3549.9     .07       0  3755.8    .035       0  3864.8     .05       0
  3952.8    .035       0  4186.7     .07       0  4193.5    .035       0
  4282.2     .07       0  4646.2      .1       0  5026.2     .05       0
  5047.9      .1       0  5168.2     .07       0
Bank Sta=5026.2,5047.9
XS Rating Curve= 0 ,0
Exp/Cntr=0.3,0.1