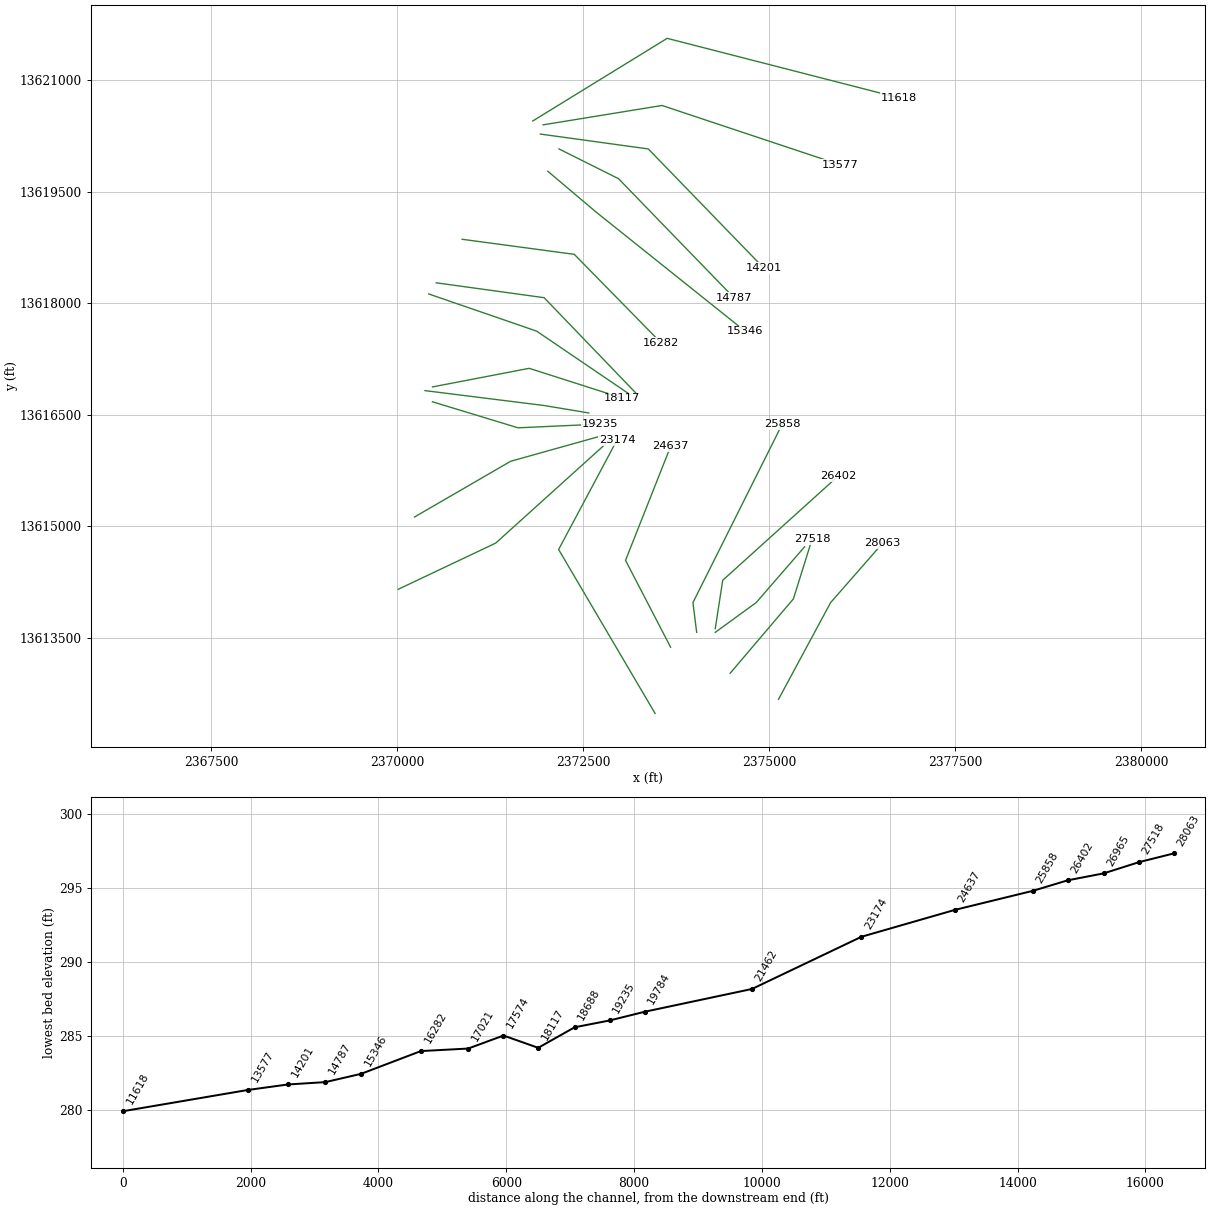
HEC-RAS study BRUSHY CREEK.prj: BRUSHY CREEK Base Level Engineering

--- BRUSHY CREEK.g01 (geometry) --- (continued)

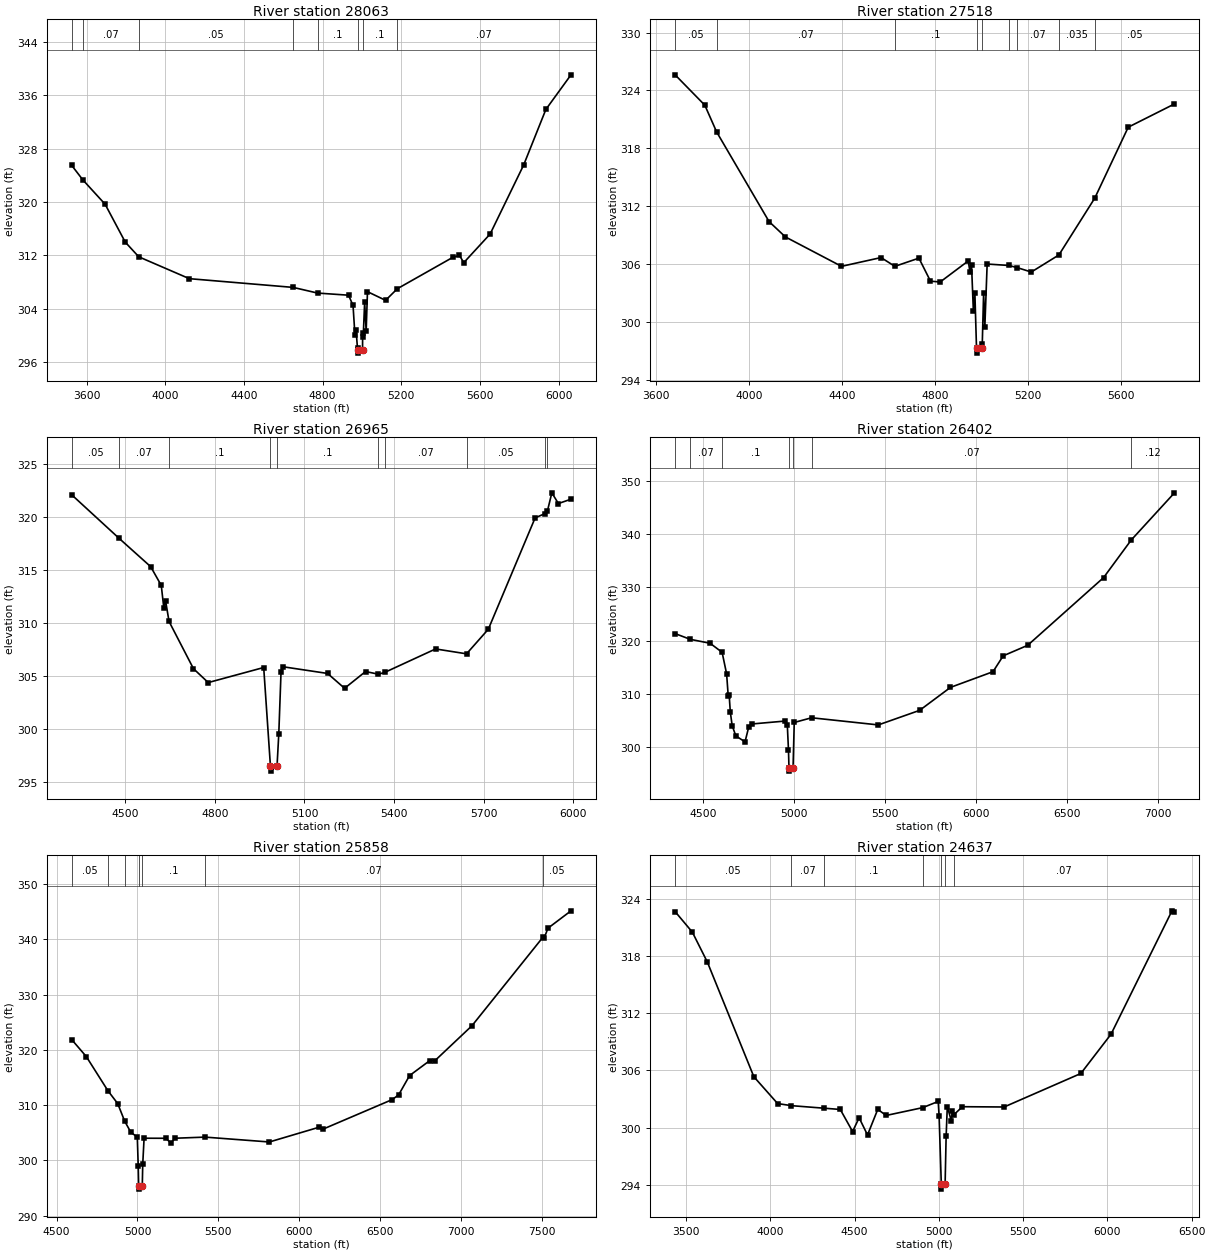
Type RM Length L Ch R = 1 ,28063   ,545,545,545
BEGIN DESCRIPTION:
BRUSHY CREEK 20.0
END DESCRIPTION:
XS GIS Cut Line= 3
        2375125.       13612675.        2375825.       13613975.
        2376525.       13614775.
#Sta/Elev= 30
  3523.4  325.53  3580.1  323.35  3693.8  319.68    3796  314.01  3864.7   311.8
  4122.1  308.52  4650.1  307.21    4774  306.36  4931.7  306.04  4954.5   304.5
  4964.2  300.03  4969.9  300.76  4977.2  298.06  4980.7  297.85  4981.2  297.35
  5002.8  297.85  5003.2  299.73    5007  300.31  5013.6  305.04  5021.2  300.64
  5027.9  306.57    5120  305.27  5179.7  307.01  5460.7   311.7  5495.8  312.01
  5517.6  310.92  5651.5  315.21  5822.3  325.58  5935.2  333.91  6062.9   339.1
#Mann= 8 ,-1 , 0
  3523.4     .12       0  3580.1     .07       0  3864.7     .05       0
  4650.1     .07       0    4774      .1       0  4980.7     .05       0
  5002.8      .1       0  5179.7     .07       0
Bank Sta=4980.7,5002.8
XS Rating Curve= 0 ,0
Exp/Cntr=0.3,0.1

Type RM Length L Ch R = 1 ,27518   ,553,553,553
BEGIN DESCRIPTION:
BRUSHY CREEK 19.0
END DESCRIPTION:
XS GIS Cut Line= 3
      2374474.99     13613024.99        2375325.       13614025.
        2375575.       13614825.
#Sta/Elev= 30
  3681.3  325.62  3809.3  322.47  3860.3  319.69    4086   310.4  4156.3  308.81
  4397.9  305.76  4568.2  306.67  4627.7  305.76  4731.3  306.61  4781.2  304.22
  4823.1  304.14  4943.8  306.32  4951.5  305.13    4958  305.86  4965.8  301.15
  4972.3  303.02  4979.4  297.26  4979.9  296.76  5001.6  297.26  5004.2  297.73
    5010  303.04  5015.2  299.46  5025.2     306  5118.9  305.85  5154.1  305.63
  5215.3  305.17  5334.2  306.94  5488.8  312.84  5632.8  320.19  5831.9   322.6
#Mann= 9 ,-1 , 0
  3681.3     .05       0  3860.3     .07       0  4627.7      .1       0
  4979.4     .05       0  5001.6      .1       0  5118.9     .12       0
  5154.1     .07       0  5334.2    .035       0  5488.8     .05       0
Bank Sta=4979.4,5001.6
XS Rating Curve= 0 ,0
Exp/Cntr=0.3,0.1

Type RM Length L Ch R = 1 ,26965   ,563,563,563
BEGIN DESCRIPTION:
BRUSHY CREEK 18.0
END DESCRIPTION:
XS GIS Cut Line= 3
      2374275.03     13613575.02        2374825.       13613975.
      2375474.99     13614724.99
#Sta/Elev= 30
  4320.2  322.06  4479.5  317.94  4584.9  315.28  4620.4  313.51  4628.9   311.4
  4635.1  312.01  4646.5  310.11  4728.2  305.66  4777.7  304.35  4963.5  305.77
    4986   296.5  4986.5     296  5008.2   296.5    5014  299.49  5021.6  305.39
  5028.2  305.84  5177.4  305.21  5234.4  303.81  5304.6  305.39  5347.8  305.14
  5368.2   305.3  5539.2  307.52  5642.9  307.06  5715.8  309.38  5872.6  319.88
  5905.5  320.28  5913.6  320.51  5928.6  322.24  5950.5  321.23  5992.7  321.64
#Mann= 10 ,-1 , 0
  4320.2     .05       0  4479.5     .07       0  4646.5      .1       0
    4986     .05       0  5008.2      .1       0  5347.8     .12       0
  5368.2     .07       0  5642.9     .05       0  5905.5     .07       0
  5913.6     .05       0
Bank Sta=4986,5008.2
XS Rating Curve= 0 ,0
Exp/Cntr=0.3,0.1

Type RM Length L Ch R = 1 ,26402   ,544,544,544
BEGIN DESCRIPTION:
BRUSHY CREEK 17.0
END DESCRIPTION:
XS GIS Cut Line= 3
      2374274.99     13613624.96        2374375.       13614275.
      2375924.97     13615674.97
#Sta/Elev= 30
    4346  321.33  4429.9  320.25  4538.3  319.52  4604.5  317.82  4629.3  313.77
  4638.2  309.58  4643.2  309.83  4649.6  306.63  4659.7  304.08  4679.9  302.14
  4730.5  301.02  4750.7  303.79  4769.7  304.38  4953.1  304.93  4963.2   304.1
  4969.5  299.49  4972.3  296.03  4972.8  295.53  4994.6  296.03  5001.2  304.66
  5096.6  305.54  5463.6   304.2  5690.8  306.93  5860.4  311.24  6094.3  314.18
  6150.4  317.16  6284.9  319.13  6702.6  331.84  6854.3  338.88  7092.3  347.74
#Mann= 7 ,-1 , 0
    4346     .05       0  4429.9     .07       0  4604.5      .1       0
  4972.3     .05       0  4994.6      .1       0  5096.6     .07       0
  6854.3     .12       0
Bank Sta=4972.3,4994.6
XS Rating Curve= 0 ,0
Exp/Cntr=0.3,0.1

Type RM Length L Ch R = 1 ,25858   ,1221,1221,1221
BEGIN DESCRIPTION:
BRUSHY CREEK 16.0
END DESCRIPTION:
XS GIS Cut Line= 3
        2374025.       13613575.        2373975.       13613975.
        2375175.       13616375.
#Sta/Elev= 30
  4593.1  321.89  4683.8   318.8  4817.6  312.61  4877.8   310.3  4920.9  307.12
  4958.4  305.14    4999  304.21  5004.6  299.06  5007.4  295.32  5007.9  294.82
  5029.7  295.32  5032.6  299.35  5040.9  304.03  5175.1  304.02  5205.8  303.19
  5233.8  304.03  5418.2  304.23  5815.2  303.35  6122.6  306.02    6145  305.65
  6575.4  311.03  6614.6  311.89  6681.7  315.36  6807.4  318.09  6838.2  318.05
  7067.4  324.38  7505.4  340.37  7514.6  340.29  7536.9  342.02  7679.5  345.17
#Mann= 7 ,-1 , 0
  4593.1     .05       0  4817.6     .07       0  4920.9      .1       0
  5007.4     .05       0  5029.7      .1       0  5418.2     .07       0
  7505.4     .05       0
Bank Sta=5007.4,5029.7
XS Rating Curve= 0 ,0
Exp/Cntr=0.3,0.1

Type RM Length L Ch R = 1 ,24637   ,1463,1463,1463
BEGIN DESCRIPTION:
BRUSHY CREEK 15.0
END DESCRIPTION:
XS GIS Cut Line= 3
      2373674.98     13613375.04      2373069.21     13614542.75
      2373674.98     13616074.96
#Sta/Elev= 30
  3434.9  322.69  3537.2  320.53  3626.4  317.38  3902.1  305.34  4043.2  302.52
  4124.9   302.3  4320.8  302.03    4415   301.9  4488.1  299.58  4526.7  301.03
  4576.6  299.22  4637.4  301.91  4687.2  301.27  4903.7  302.09    4996  302.74
  5001.4  301.23  5014.5  294.03    5015  293.53    5037  294.03  5043.1  299.06
  5050.1  302.21  5074.5  300.67  5079.9   301.7  5089.7  301.36  5139.9  302.19
  5387.2  302.16  5842.4  305.68  6021.7  309.81  6383.2  322.77    6398   322.6
#Mann= 7 ,-1 , 0
  3434.9     .05       0  4124.9     .07       0  4320.8      .1       0
  4903.7     .12       0  5014.5     .05       0    5037     .12       0
  5089.7     .07       0
Bank Sta=5014.5,5037
XS Rating Curve= 0 ,0
Exp/Cntr=0.3,0.1

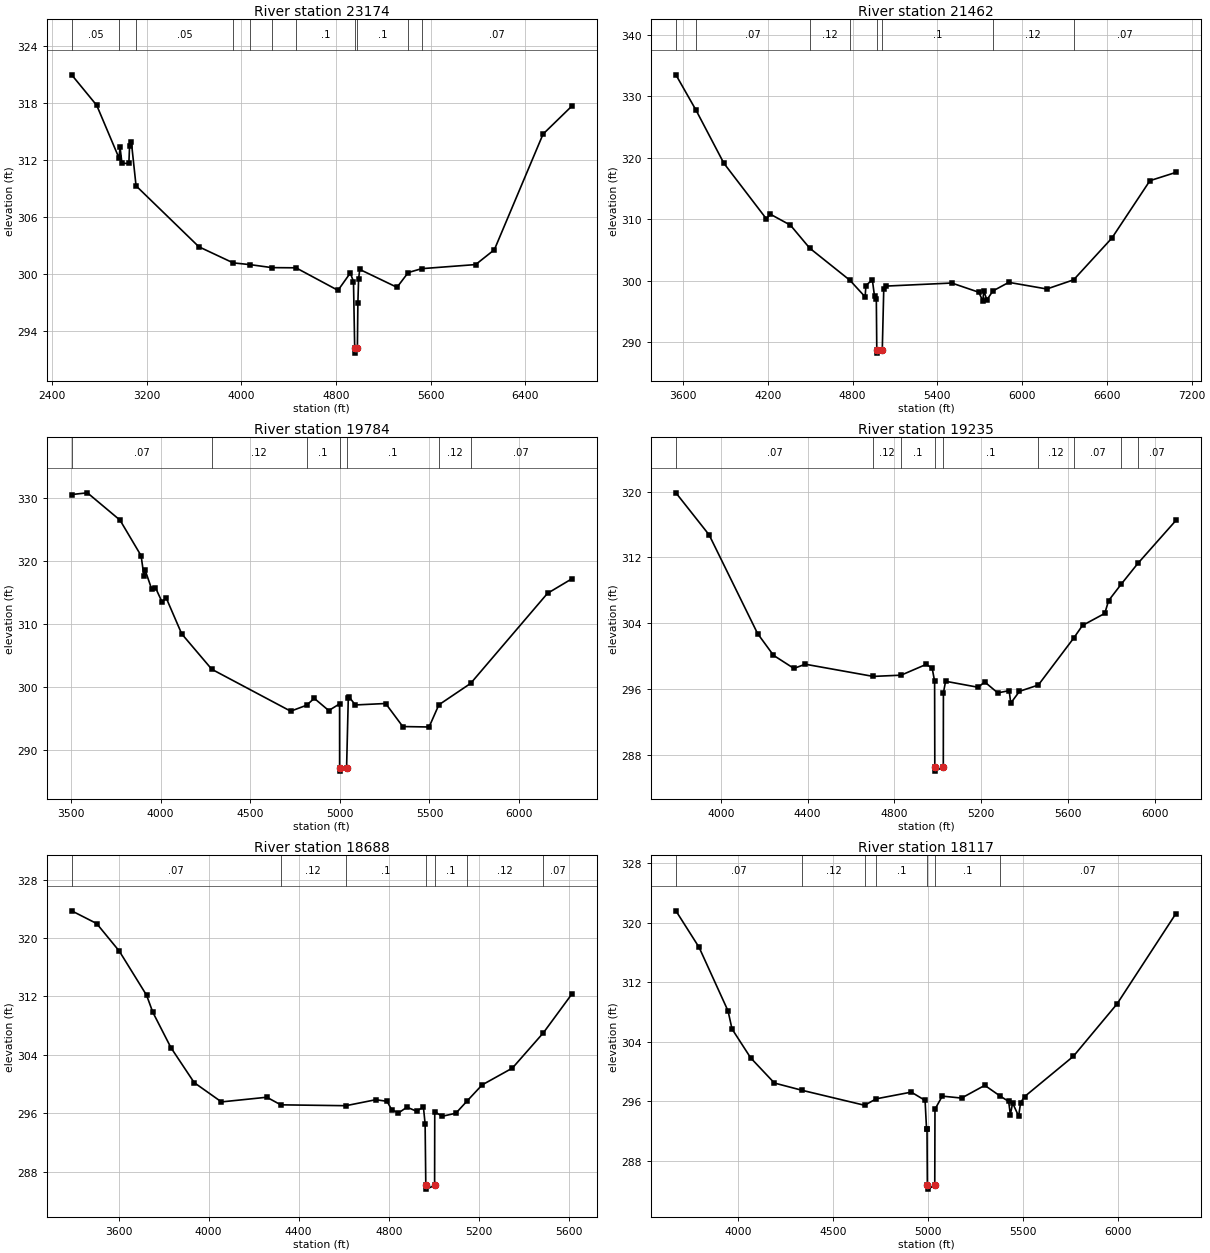
Type RM Length L Ch R = 1 ,23174   ,1712,1712,1712
BEGIN DESCRIPTION:
BRUSHY CREEK 14.0
END DESCRIPTION:
XS GIS Cut Line= 3
       2373466.1     13612485.29      2372170.06     13614688.56
      2372955.05     13616161.43
#Sta/Elev= 30
  2566.9  320.97  2778.7  317.76  2966.6  312.23  2975.9  313.35  2991.6  311.67
  3050.2  311.65    3056  313.46  3071.6  313.88  3110.9   309.3  3641.9  302.89
  3931.3   301.2  4077.2  301.01  4258.5   300.7  4462.3  300.68  4817.3  298.31
    4921  300.13  4948.2  299.24  4958.4  292.21  4958.9  291.71    4981  292.21
  4985.3     297  4991.3   299.5    5001  300.51  5315.8  298.63  5410.5  300.18
  5523.9  300.59  5980.3  301.02  6138.4  302.58    6550  314.74  6792.1  317.67
#Mann= 11 ,-1 , 0
  2566.9     .05       0  2966.6     .07       0  3110.9     .05       0
  3931.3     .07       0  4077.2     .05       0  4258.5     .07       0
  4462.3      .1       0  4958.4     .05       0    4981      .1       0
  5410.5     .12       0  5523.9     .07       0
Bank Sta=4958.4,4981
XS Rating Curve= 0 ,0
Exp/Cntr=0.3,0.1

Type RM Length L Ch R = 1 ,21462   ,1678,1678,1678
BEGIN DESCRIPTION:
BRUSHY CREEK 13.0
END DESCRIPTION:
XS GIS Cut Line= 3
      2370015.37     13614153.94        2371325.       13614775.
        2372875.       13616175.
#Sta/Elev= 30
  3550.4  333.48  3693.6  327.69  3889.4   319.1  4190.5  310.04  4218.8  310.79
  4360.7  309.01  4496.9  305.27  4781.5  300.04  4889.2  297.34  4894.8  299.18
  4940.2  300.13  4955.6  297.45  4968.5  296.92  4971.8  288.68  4972.8  288.18
  5010.6  288.68  5021.1  298.64  5035.3  299.09  5502.4  299.59  5693.7  298.09
  5722.1  296.64  5728.8  298.34  5750.5  296.84  5793.8  298.31  5905.9   299.7
  6174.9  298.62  6364.4  300.11  6635.3  306.91  6904.3  316.25  7088.5   317.6
#Mann= 8 ,-1 , 0
  3550.4     .05       0  3693.6     .07       0  4496.9     .12       0
  4781.5      .1       0  4971.8     .05       0  5010.6      .1       0
  5793.8     .12       0  6364.4     .07       0
Bank Sta=4971.8,5010.6
XS Rating Curve= 0 ,0
Exp/Cntr=0.3,0.1

Type RM Length L Ch R = 1 ,19784   ,549,549,549
BEGIN DESCRIPTION:
BRUSHY CREEK 12.0
END DESCRIPTION:
XS GIS Cut Line= 3
      2370234.03     13615125.96        2371525.       13615875.
      2372774.99       13616225.
#Sta/Elev= 30
  3503.3  330.57  3591.1  330.84  3773.2   326.5  3890.8  320.85  3906.6  317.63
  3912.4  318.63  3949.6  315.57  3971.1  315.77  4008.4  313.46  4029.9  314.21
  4117.2  308.45  4285.1  302.82  4725.5  296.16    4814   297.1  4857.1   298.2
    4938  296.26  4998.4  297.32  4998.7  287.14  4999.7  286.64  5037.5  287.14
    5047  298.21  5052.2  298.39  5086.3  297.15  5255.5  297.38  5351.1  293.72
    5498  293.65  5552.4  297.17  5729.7  300.57  6158.9  314.88  6293.9  317.17
#Mann= 7 ,-1 , 0
  3503.3     .07       0  4285.1     .12       0    4814      .1       0
  4998.7     .05       0  5037.5      .1       0  5552.4     .12       0
  5729.7     .07       0
Bank Sta=4998.7,5037.5
XS Rating Curve= 0 ,0
Exp/Cntr=0.3,0.1

Type RM Length L Ch R = 1 ,19235   ,547,547,547
BEGIN DESCRIPTION:
BRUSHY CREEK 11.0
END DESCRIPTION:
XS GIS Cut Line= 3
      2370475.01       13616675.        2371625.       13616325.
      2372724.99       13616375.
#Sta/Elev= 30
  3793.2  319.84  3946.3  314.73  4169.5  302.75  4242.7  300.11  4336.7  298.52
    4389  299.03  4702.1  297.55  4830.4   297.7    4946  299.01  4973.6  298.55
  4984.8  296.96  4985.7  286.55  4986.7  286.05  5024.8  286.55  5025.3  295.55
  5035.3  296.96  5185.5  296.23  5215.5  296.88  5275.6  295.55  5328.1  295.82
  5335.6  294.31  5375.7  295.74  5462.4   296.5  5624.8  302.18    5666  303.74
  5768.6   305.2  5786.1  306.75  5844.6  308.76    5921  311.27  6096.4  316.49
#Mann= 9 ,-1 , 0
  3793.2     .07       0  4702.1     .12       0  4830.4      .1       0
  4985.7     .05       0  5024.8      .1       0  5462.4     .12       0
  5624.8     .07       0  5844.6     .12       0    5921     .07       0
Bank Sta=4985.7,5024.8
XS Rating Curve= 0 ,0
Exp/Cntr=0.3,0.1

Type RM Length L Ch R = 1 ,18688   ,571,571,571
BEGIN DESCRIPTION:
BRUSHY CREEK 10.0
END DESCRIPTION:
XS GIS Cut Line= 3
      2370374.96     13616825.01        2371975.       13616625.
      2372575.03       13616525.
#Sta/Elev= 30
  3391.8  323.72  3502.7  321.98  3603.5  318.19  3724.4  312.16  3752.1  309.83
  3832.7  304.97    3936  300.18    4057  297.54  4258.5  298.18  4320.5  297.14
  4609.6  297.02  4742.3  297.84  4792.7  297.62  4812.8  296.47    4843  296.02
  4880.8  296.82  4923.7  296.26  4953.9  296.86  4961.5  294.54  4964.6  286.09
  4965.6  285.59  5003.7  286.09  5004.3  296.19  5037.2  295.57  5098.1  295.99
  5147.2  297.64  5214.7  299.87    5349  302.17  5486.8  307.01  5612.6  312.29
#Mann= 7 ,-1 , 0
  3391.8     .07       0  4320.5     .12       0  4609.6      .1       0
  4964.6     .05       0  5003.7      .1       0  5147.2     .12       0
  5486.8     .07       0
Bank Sta=4964.6,5003.7
XS Rating Curve= 0 ,0
Exp/Cntr=0.3,0.1

Type RM Length L Ch R = 1 ,18117   ,543,543,543
BEGIN DESCRIPTION:
BRUSHY CREEK 9.0
END DESCRIPTION:
XS GIS Cut Line= 3
      2370475.02       13616875.        2371775.       13617125.
      2373024.96     13616725.01
#Sta/Elev= 30
  3670.6  321.61  3792.8   316.7  3945.5  308.15  3966.4  305.73  4065.2  301.83
  4189.9  298.46  4336.4  297.48  4665.6  295.47  4726.6  296.34  4911.4  297.24
  4984.2  296.13  4991.9   292.3  4994.4   292.3  4996.2   284.7  4997.2   284.2
  5035.3   284.7  5036.4  294.94  5074.8   296.7  5176.5  296.44  5298.9  298.15
  5380.1  296.71  5424.9  295.98  5433.7  294.23  5445.9  295.76  5477.4  294.01
  5487.9  295.84  5508.9  296.64  5765.8  302.05  5996.1  309.09  6306.8  321.25
#Mann= 7 ,-1 , 0
  3670.6     .07       0  4336.4     .12       0  4665.6     .07       0
  4726.6      .1       0  4996.2     .05       0  5035.3      .1       0
  5380.1     .07       0
Bank Sta=4996.2,5035.3
XS Rating Curve= 0 ,0
Exp/Cntr=0.3,0.1

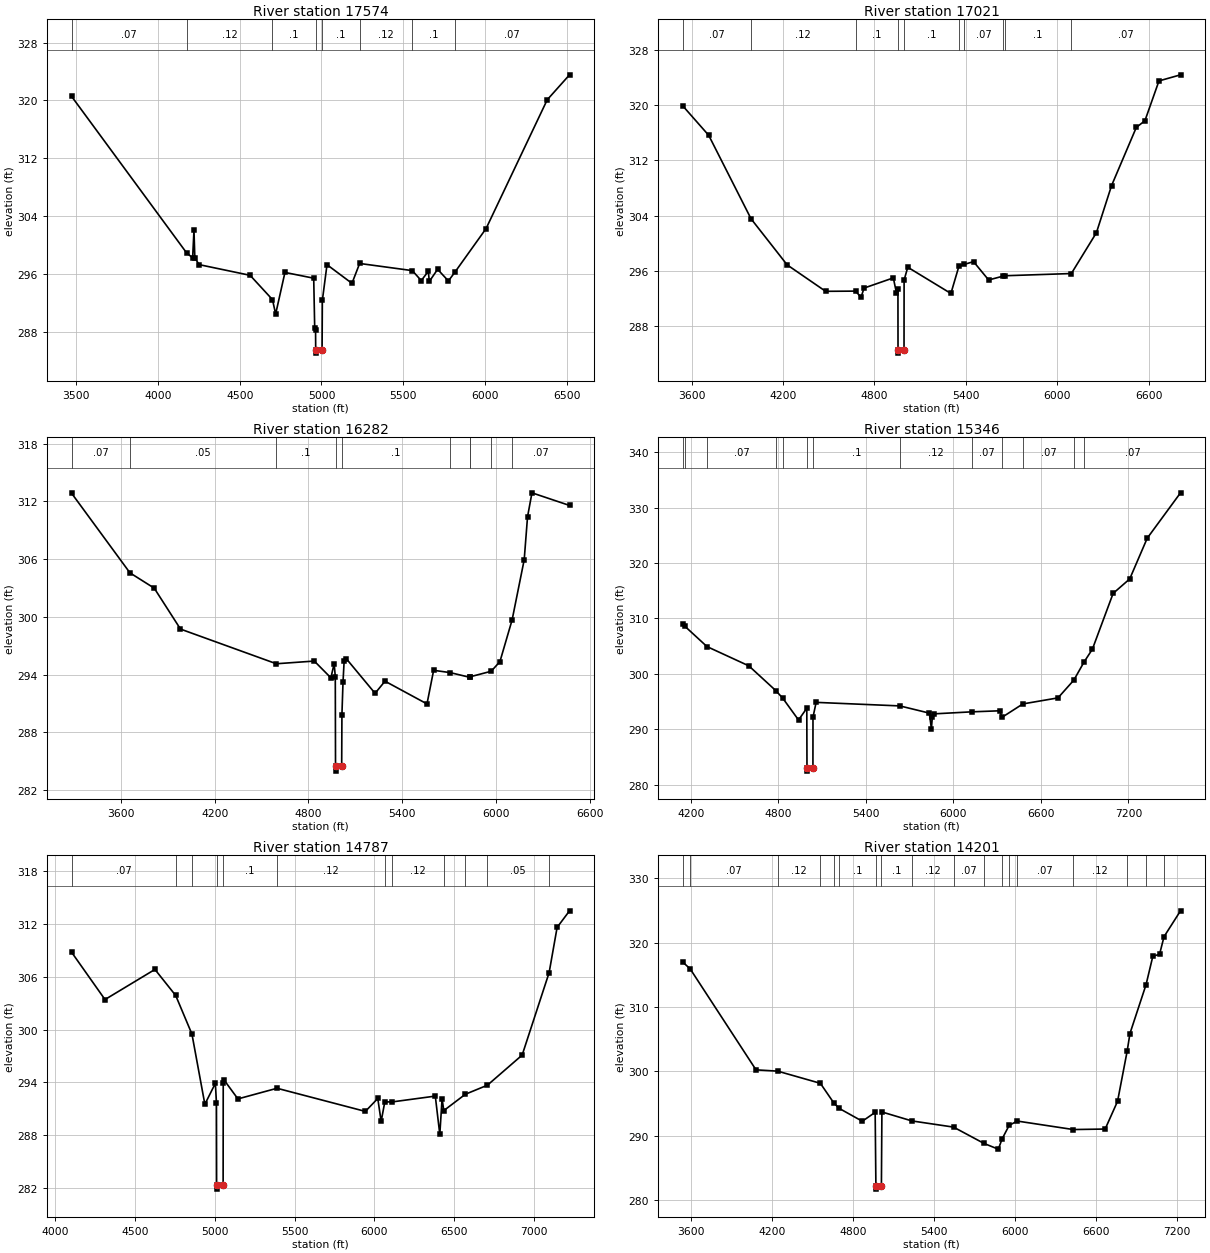
Type RM Length L Ch R = 1 ,17574   ,553,553,553
BEGIN DESCRIPTION:
BRUSHY CREEK 8.0
END DESCRIPTION:
XS GIS Cut Line= 3
      2370425.04     13618124.99        2371875.       13617625.
      2373125.03     13616774.98
#Sta/Elev= 30
  3471.7  320.57  4174.7  298.92  4212.1  298.21  4220.3  302.04  4225.6  298.22
  4251.5  297.28  4563.6   295.8  4700.3  292.44  4719.8  290.44  4776.7   296.2
  4952.6   295.4  4958.6  288.56  4963.9  288.24  4964.7  285.53  4965.7  285.03
  5003.8  285.53  5005.4  292.32  5033.9  297.27  5186.5  294.69  5233.5  297.44
  5555.9  296.45  5610.1  295.07  5653.5  296.35  5659.5  294.95  5710.4  296.63
  5776.2  295.02  5815.3  296.21  6006.7  302.27  6380.8   320.1  6517.1  323.55
#Mann= 8 ,-1 , 0
  3471.7     .07       0  4174.7     .12       0  4700.3      .1       0
  4964.7     .05       0  5003.8      .1       0  5233.5     .12       0
  5555.9      .1       0  5815.3     .07       0
Bank Sta=4964.7,5003.8
XS Rating Curve= 0 ,0
Exp/Cntr=0.3,0.1

Type RM Length L Ch R = 1 ,17021   ,739,739,739
BEGIN DESCRIPTION:
BRUSHY CREEK 7.0
END DESCRIPTION:
XS GIS Cut Line= 3
      2370525.04     13618274.99        2371975.       13618075.
      2373225.03     13616774.97
#Sta/Elev= 30
  3541.1  319.91  3712.7  315.62  3990.4  303.56  4227.5   296.9  4479.9  293.08
  4676.3  293.11    4712  292.22  4732.2  293.55    4924  295.02  4944.2  292.89
  4954.3   293.4  4954.8  284.65  4955.8  284.15  4994.2  284.65  4994.7  294.71
  5018.8  296.56  5301.8  292.77    5354  296.68  5389.7  296.97  5450.2  297.37
  5549.3  294.72  5646.8  295.29  5655.7  295.33  6092.1  295.65  6256.5  301.55
  6355.6  308.34  6518.2  316.76  6574.8  317.73  6666.9  323.48  6808.3  324.36
#Mann= 10 ,-1 , 0
  3541.1     .07       0  3990.4     .12       0  4676.3      .1       0
  4954.8     .05       0  4994.2      .1       0    5354     .12       0
  5389.7     .07       0  5646.8     .12       0  5655.7      .1       0
  6092.1     .07       0
Bank Sta=4954.8,4994.2
XS Rating Curve= 0 ,0
Exp/Cntr=0.3,0.1

Type RM Length L Ch R = 1 ,16282   ,936,936,936
BEGIN DESCRIPTION:
BRUSHY CREEK 6.0
END DESCRIPTION:
XS GIS Cut Line= 3
      2370873.99     13618860.28      2372380.67     13618657.76
      2373547.11     13617467.02
#Sta/Elev= 30
  3283.7  312.84  3657.4  304.57  3812.8  302.98  3980.9  298.73  4594.3  295.13
  4837.2  295.41  4943.3  293.67  4964.5  295.15  4971.6  293.77  4973.1  284.48
  4974.1  283.98  5012.5  284.48  5014.1  289.86  5021.1  293.26  5028.2  295.39
  5042.3  295.65  5226.2  292.06  5289.8  293.32  5558.5  290.96    5601  294.45
  5707.1  294.21    5833  293.72  5835.2  293.78  5969.3  294.35  6025.3  295.35
  6103.4  299.69  6180.7  305.93    6202  310.39  6230.3  312.88  6470.8  311.57
#Mann= 10 ,-1 , 0
  3283.7     .07       0  3657.4     .05       0  4594.3      .1       0
  4973.1     .05       0  5012.5      .1       0  5707.1     .07       0
    5833     .12       0  5835.2      .1       0  5969.3     .12       0
  6103.4     .07       0
Bank Sta=4973.1,5012.5
XS Rating Curve= 0 ,0
Exp/Cntr=0.3,0.1

Type RM Length L Ch R = 1 ,15346   ,559,559,559
BEGIN DESCRIPTION:
BRUSHY CREEK 5.0
END DESCRIPTION:
XS GIS Cut Line= 3
      2372024.98     13619775.02        2372675.       13619225.
      2374675.04     13617624.97
#Sta/Elev= 30
  4144.2  308.94  4158.3  308.63  4311.5  304.92  4598.5  301.44  4784.2  296.95
  4831.9  295.57  4939.1  291.67  4995.7  293.79    4997  282.94    4998  282.44
  5037.7  282.94  5038.1  292.17  5059.7  294.85  5633.7  294.21  5835.3  292.91
  5849.7  290.12  5856.1  292.21  5870.5  292.78  6125.3  293.14  6318.7  293.33
  6333.5  292.15  6476.5  294.57  6717.3  295.66    6826  298.87  6896.9  302.18
  6952.7  304.43  7095.1  314.52  7208.8  317.13  7328.8  324.48    7557  332.67
#Mann= 13 ,-1 , 0
  4144.2     .07       0  4158.3     .05       0  4311.5     .07       0
  4784.2     .12       0  4831.9      .1       0    4997     .05       0
  5037.7      .1       0  5633.7     .12       0  6125.3     .07       0
  6333.5     .12       0  6476.5     .07       0    6826     .05       0
  6896.9     .07       0
Bank Sta=4997,5037.7
XS Rating Curve= 0 ,0
Exp/Cntr=0.3,0.1

Type RM Length L Ch R = 1 ,14787   ,586,586,586
BEGIN DESCRIPTION:
BRUSHY CREEK 4.0
END DESCRIPTION:
XS GIS Cut Line= 3
      2372175.02     13620074.99        2372975.       13619675.
      2374525.02     13618074.98
#Sta/Elev= 30
  4100.9   308.8  4310.5  303.42  4623.6  306.84  4753.8  303.88  4855.7  299.49
  4936.6  291.52  5002.4   293.9  5009.3  291.72  5010.3  282.38  5011.3  281.88
  5051.1  282.38  5051.8  293.98    5059  294.23  5143.9  292.13    5389  293.34
  5942.9  290.71  6020.8  292.18  6041.9  289.57  6064.8  291.79  6111.4  291.79
  6381.4  292.45  6409.7  288.09  6423.9  292.17  6434.5   290.8    6570  292.66
  6708.3  293.69    6926  297.11  7095.1  306.48  7145.2  311.62    7223   313.5
#Mann= 12 ,-1 , 0
  4100.9     .07       0  4753.8     .12       0  4855.7      .1       0
  5010.3     .05       0  5051.1      .1       0    5389     .12       0
  6064.8     .07       0  6111.4     .12       0  6434.5     .07       0
    6570     .12       0  6708.3     .05       0  7095.1     .07       0
Bank Sta=5010.3,5051.1
XS Rating Curve= 0 ,0
Exp/Cntr=0.3,0.1

Type RM Length L Ch R = 1 ,14201   ,624,624,624
BEGIN DESCRIPTION:
BRUSHY CREEK 3.0
END DESCRIPTION:
XS GIS Cut Line= 3
      2371924.97       13620275.        2373375.       13620075.
      2374924.98     13618475.02
#Sta/Elev= 30
    3536     317  3592.4  315.92  4080.5  300.24  4240.7  300.04  4557.6  298.15
  4657.3   295.1  4697.6  294.25  4868.5  292.26  4963.8  293.64  4969.3  282.22
  4970.3  281.72  5010.1  282.22  5013.8   293.7  5235.9  292.31  5544.7  291.35
  5771.1  288.81  5876.8  287.92  5904.5   289.5  5956.8  291.61  6016.6  292.29
    6433  290.97  6668.8  291.05  6760.7  295.36  6831.4  303.09  6852.5  305.88
  6971.8  313.46  7022.3  317.89  7071.9  318.17  7105.2  320.92  7227.4  324.93
#Mann= 18 ,-1 , 0
    3536     .05       0  3592.4     .07       0  4240.7     .12       0
  4557.6     .07       0  4657.3     .12       0  4697.6      .1       0
  4969.3     .05       0  5010.1      .1       0  5235.9     .12       0
  5544.7     .07       0  5771.1     .12       0  5904.5     .07       0
  5956.8     .12       0  6016.6     .07       0    6433     .12       0
  6831.4     .07       0  6971.8    .035       0  7105.2     .05       0
Bank Sta=4969.3,5010.1
XS Rating Curve= 0 ,0
Exp/Cntr=0.3,0.1

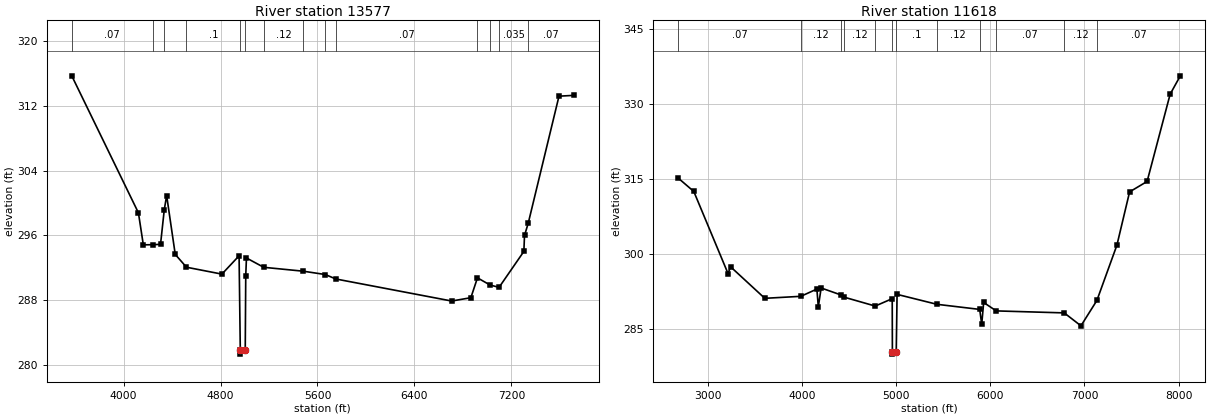
Type RM Length L Ch R = 1 ,13577   ,1959,1959,1959
BEGIN DESCRIPTION:
BRUSHY CREEK 2.0
END DESCRIPTION:
XS GIS Cut Line= 3
      2371962.08     13620399.05      2373559.31     13620659.47
      2375955.19     13619860.84
#Sta/Elev= 30
    3572  315.68  4122.1  298.78  4162.6  294.83  4239.7  294.85  4304.5  294.89
  4335.6  299.18  4355.1  300.91    4426  293.65  4518.7  292.07  4811.1  291.22
  4952.9  293.48  4962.9  281.85  4963.9  281.35  5003.7  281.85  5007.9  291.03
  5013.7  293.21  5156.4  292.06  5482.2  291.58  5664.2  291.17  5751.2  290.62
  6707.7   287.9  6865.9  288.31  6920.3  290.76    7025  289.87  7098.7  289.59
  7303.3  294.02  7308.6  295.99  7339.2  297.49  7593.2  313.17  7715.8  313.27
#Mann= 14 ,-1 , 0
    3572     .07       0  4239.7    .033       0  4335.6     .07       0
  4518.7      .1       0  4962.9     .05       0  5003.7      .1       0
  5156.4     .12       0  5482.2     .07       0  5664.2     .12       0
  5751.2     .07       0  6920.3    .035       0    7025     .12       0
  7098.7    .035       0  7339.2     .07       0
Bank Sta=4962.9,5003.7
XS Rating Curve= 0 ,0
Exp/Cntr=0.3,0.1

Type RM Length L Ch R = 1 ,11618   ,0,0,0
BEGIN DESCRIPTION:
BRUSHY CREEK 1.0
END DESCRIPTION:
XS GIS Cut Line= 3
      2371823.24     13620451.16      2373628.76     13621562.25
      2376736.38     13620763.64
#Sta/Elev= 30
  2689.2  315.17  2854.2   312.5  3217.5  296.06  3244.7  297.41  3607.9  291.09
  3989.9  291.49  4160.5  292.94  4175.9   289.4    4206  293.16  4417.3  291.76
  4453.5   291.3  4779.9  289.54  4960.2  291.02    4962  280.41    4963  279.91
    5003  280.41  5011.8  291.88  5434.9  289.89  5888.7  288.87  5910.1  285.87
  5930.7  290.26    6064  288.57  6785.9  288.17  6963.2  285.58  7132.4  290.66
  7344.8  301.73  7479.5  312.41  7665.3   314.5  7909.9  331.98  8017.8  335.66
#Mann= 12 ,-1 , 0
  2689.2     .07       0  3989.9     .12       0  4417.3     .07       0
  4453.5     .12       0  4779.9      .1       0    4962     .05       0
    5003      .1       0  5434.9     .12       0  5888.7    .035       0
    6064     .07       0  6785.9     .12       0  7132.4     .07       0
Bank Sta=4962,5003
XS Rating Curve= 0 ,0
Exp/Cntr=0.3,0.1

Chan Stop Cuts=-1
Use User Specified Reach Order=0
Composite Channel Slope=5