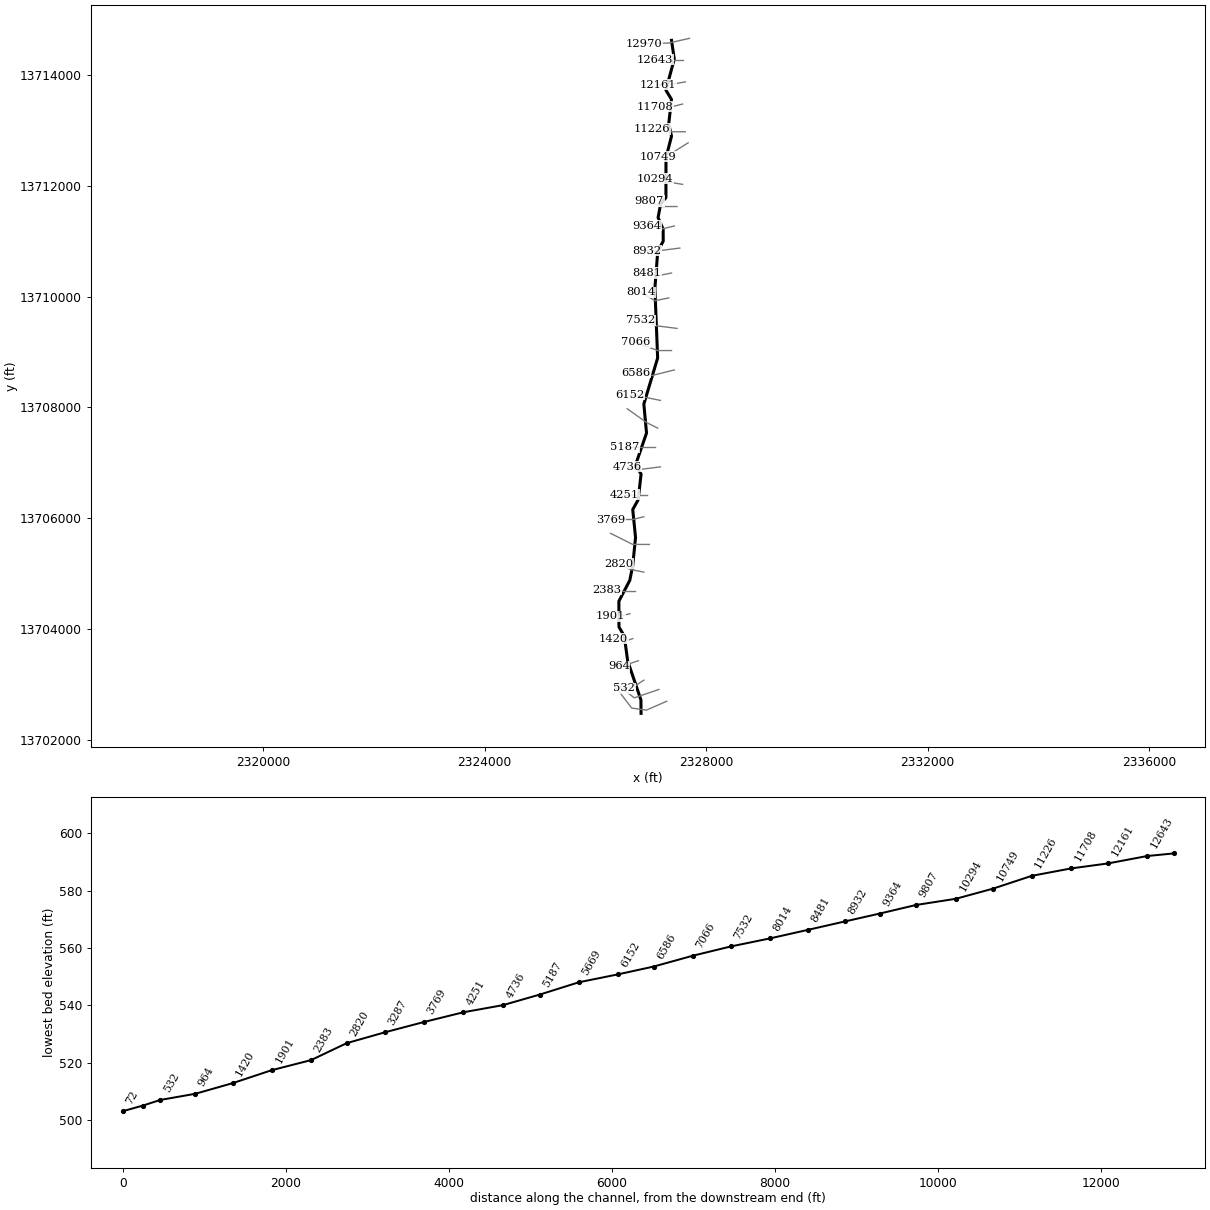
--- CARDELL CREEK.prj (project) ---

Proj Title=CARDELL CREEK Base Level Engineering
Current Plan=p01
Default Exp/Contr=0.3,0.1
English Units
Geom File=g01
Flow File=f01
Plan File=p01
BEGIN DESCRIPTION:
CARDELL CREEK
END DESCRIPTION:

--- CARDELL CREEK.p01 (plan) ---

Plan Title=Multiple Run
Short Identifier=Multiple
Geom File=g01
Flow File=f01
Subcritical Flow
K Sum by GR= 0
Std Step Tol= 0.01
Critical Tol= 0.01
Num of Std Step Trials= 20
Max Error Tol= 0.3
Flow Tol Ratio= 0.001
Split Flow NTrial= 30
Split Flow Tol= 0.02
Split Flow Ratio= 0.02
Log Output Level= 0
Friction Slope Method= 1
Unsteady Friction Slope Method= 2
Unsteady Bridges Friction Slope Method= 1
Parabolic Critical Depth
Global Vel Dist=  1 , 1 , 1
Global Log Level= 0
CheckData=True
Encroach Param= -1, 0, 0, 0
BEGIN DESCRIPTION:
Multiple Run
END DESCRIPTION:

--- CARDELL CREEK.f01 (steady flow) ---

Flow Title=Multiple
Number of Profiles=7
Profile Names=10-year,25-year,50-year,1pct_min,100-year,1pct_plu,500-year
River Rch & RM= CARDELL CREEK,Reach-1,12970
    1010    1703    2356    1579    3151    6288    5587
River Rch & RM= CARDELL CREEK,Reach-1,10294
    1303    2229    3115    2106    4202    8384    7585
River Rch & RM= CARDELL CREEK,Reach-1,5669
    1435    2459    3441    2327    4644    9265    8392
Boundary for River Rch & Prof#=CARDELL CREEK,Reach-1,1
Up Type=0
Dn Type=3
Dn Slope=0.005
Boundary for River Rch & Prof#=CARDELL CREEK,Reach-1,2
Up Type=0
Dn Type=3
Dn Slope=0.005
Boundary for River Rch & Prof#=CARDELL CREEK,Reach-1,3
Up Type=0
Dn Type=3
Dn Slope=0.005
Boundary for River Rch & Prof#=CARDELL CREEK,Reach-1,4
Up Type=0
Dn Type=3
Dn Slope=0.005
Boundary for River Rch & Prof#=CARDELL CREEK,Reach-1,5
Up Type=0
Dn Type=3
Dn Slope=0.005
Boundary for River Rch & Prof#=CARDELL CREEK,Reach-1,6
Up Type=0
Dn Type=3
Dn Slope=0.005
Boundary for River Rch & Prof#=CARDELL CREEK,Reach-1,7
Up Type=0
Dn Type=3
Dn Slope=0.005

--- CARDELL CREEK.g01 (geometry) ---

Geom Title=Existing Conditions

River Reach=CARDELL CREEK,Reach-1
Reach XY= 30
      2327375.00     13714625.00      2327424.48     13714290.22
      2327274.15     13713724.99      2327374.61     13713559.84
      2327324.54     13713114.82      2327374.95     13712895.04
      2327275.07     13712504.97      2327273.94     13711785.44
      2327178.55     13711673.53      2327132.56     13711425.00
      2327223.78     13711214.50      2327225.21     13710999.91
      2327126.20     13710814.50      2327074.80     13710150.08
      2327124.48     13708890.22      2326875.52     13708059.78
      2326923.78     13707535.50      2326725.03     13706959.58
      2326825.36     13706795.21      2326772.76     13706330.93
      2326675.06     13706154.97      2326725.40     13705650.00
      2326673.78     13705135.50      2326621.45     13704876.47
      2326424.79     13704500.09      2326426.20     13704035.50
      2326522.76     13703869.07      2326583.28     13703421.78
      2326822.74     13702719.06      2326825.00     13702475.00

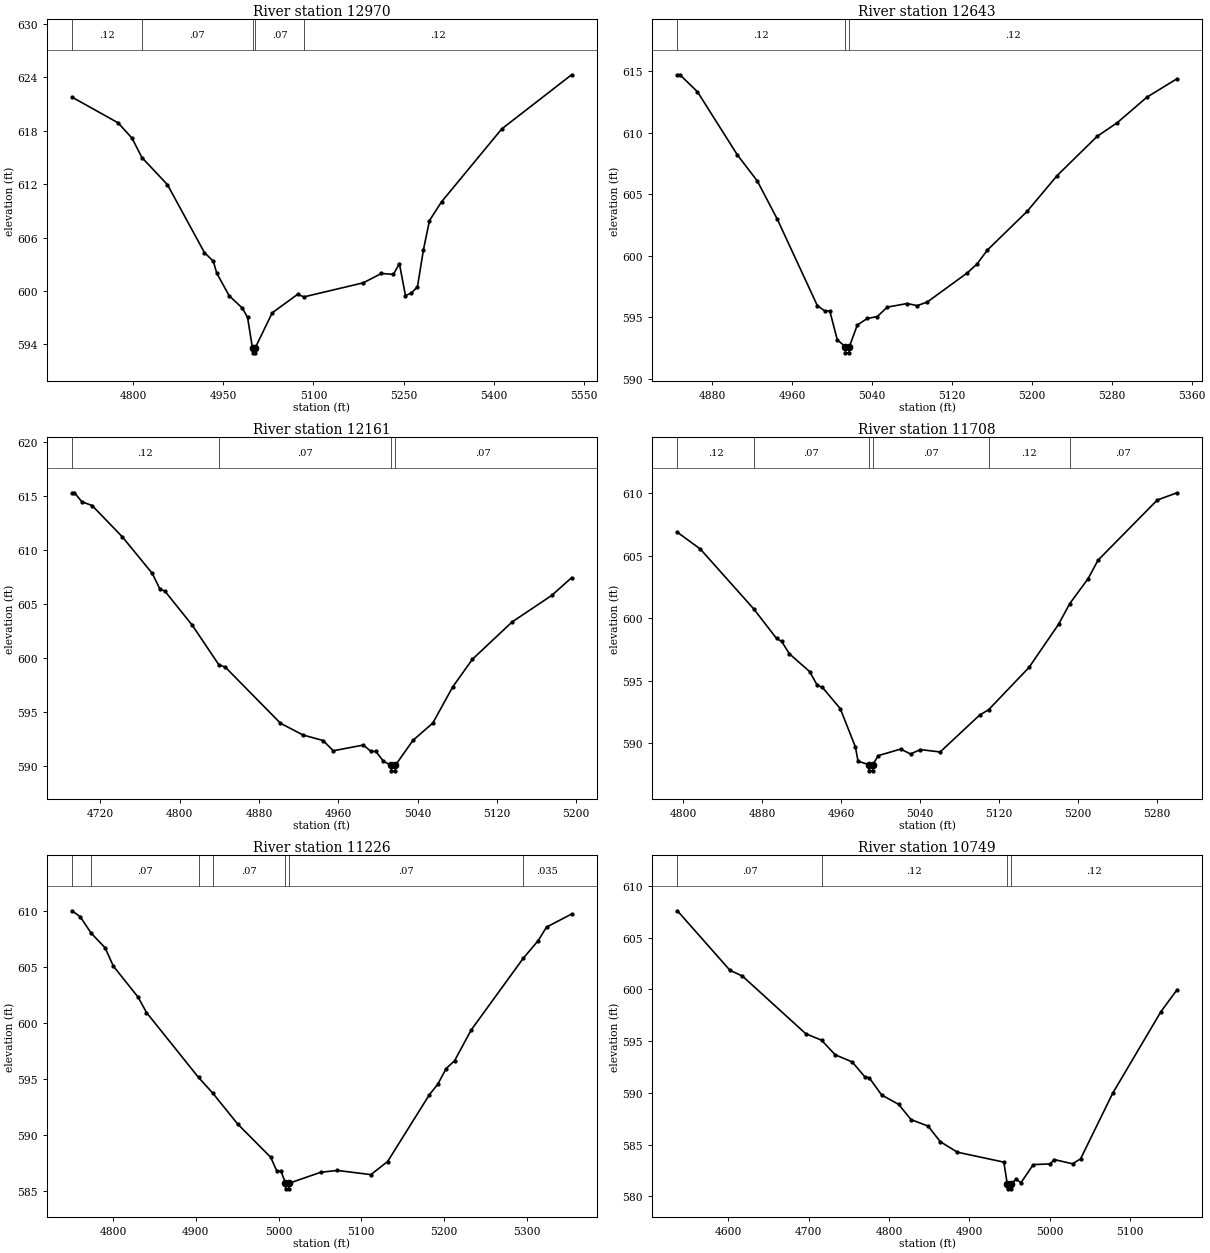
Type RM Length L Ch R = 1,12970,327,327,327
BEGIN DESCRIPTION:
X18416
END DESCRIPTION:
XS GIS Cut Line= 3
      2327699.80     13714661.42      2327321.85     13714576.38
      2326878.85     13714566.95
#Sta/Elev= 30
  4698.7  621.78  4775.4  618.89  4798.6  617.16  4815.0  614.99  4857.4  611.94
  4918.9  604.31  4933.6  603.34  4939.4  601.99  4959.9  599.47  4982.0  598.06
  4990.6  597.02  4998.8  593.54  4999.1  593.04  5002.7  593.04  5002.9  593.54
  5031.6  597.54  5073.7  599.61  5084.4  599.33  5183.0  600.91  5213.0  601.96
  5233.0  601.86  5243.0  603.07  5253.0  599.48  5263.0  599.76  5273.0  600.47
  5283.0  604.65  5293.0  607.91  5313.0  610.01  5413.0  618.20  5529.2  624.29
#Mann=5,-1,0
  4698.7    0.12       0  4815.0    0.07       0  4998.8    0.05       0
  5002.9    0.07       0  5084.4    0.12       0
Bank Sta=4998.8,5002.9
Exp/Cntr=0.3,0.1

Type RM Length L Ch R = 1,12643,482,482,482
BEGIN DESCRIPTION:
CARDELL CREEK 27.0
END DESCRIPTION:
XS GIS Cut Line= 3
      2327575.03     13714275.00      2327425.00     13714275.00
      2327075.03     13714275.00
#Sta/Elev= 30
  4845.4  614.69  4847.9  614.69  4865.4  613.32  4905.4  608.19  4925.4  606.07
  4945.4  602.97  4985.4  595.97  4992.9  595.53  4997.9  595.53  5005.4  593.19
  5013.4  592.63  5013.6  592.13  5017.2  592.13  5017.5  592.63  5025.4  594.38
  5035.4  594.92  5045.4  595.07  5055.4  595.84  5075.4  596.13  5085.4  595.96
  5095.4  596.25  5135.4  598.61  5145.4  599.35  5155.4  600.45  5195.4  603.61
  5225.4  606.51  5265.4  609.69  5285.4  610.79  5315.4  612.88  5345.4  614.37
#Mann=3,-1,0
  4845.4    0.12       0  5013.4    0.05       0  5017.5    0.12       0
Bank Sta=5013.4,5017.5
Exp/Cntr=0.3,0.1

Type RM Length L Ch R = 1,12161,453,453,453
BEGIN DESCRIPTION:
CARDELL CREEK 26.0
END DESCRIPTION:
XS GIS Cut Line= 3
      2327624.99     13713875.00      2327325.00     13713825.00
      2327125.03     13713825.00
#Sta/Elev= 30
  4691.3  615.31  4693.8  615.31  4701.4  614.47  4711.6  614.13  4742.0  611.24
  4772.4  607.83  4780.0  606.39  4785.1  606.19  4812.9  603.01  4839.5  599.37
  4845.9  599.16  4901.7  593.95  4924.5  592.86  4944.7  592.35  4954.9  591.40
  4985.3  591.93  4992.9  591.34  4997.9  591.34  5005.4  590.45  5013.3  590.04
  5013.6  589.54  5017.3  589.54  5017.5  590.04  5035.4  592.37  5055.4  593.97
  5075.4  597.31  5095.4  599.89  5135.4  603.34  5175.4  605.80  5195.4  607.44
#Mann=4,-1,0
  4691.3    0.12       0  4839.5    0.07       0  5013.3    0.05       0
  5017.5    0.07       0
Bank Sta=5013.3,5017.5
Exp/Cntr=0.3,0.1

Type RM Length L Ch R = 1,11708,482,482,482
BEGIN DESCRIPTION:
CARDELL CREEK 25.0
END DESCRIPTION:
XS GIS Cut Line= 3
      2327575.05     13713475.01      2327375.00     13713425.00
      2327075.00     13713425.00
#Sta/Elev= 30
  4793.9  606.89  4817.1  605.55  4871.1  600.77  4894.4  598.39  4899.6  598.15
  4907.3  597.17  4927.9  595.74  4935.7  594.63  4940.8  594.48  4958.9  592.78
  4974.3  589.70  4976.9  588.57  4987.7  588.30  4987.9  587.80  4991.6  587.80
  4991.9  588.30  4997.5  589.02  5020.1  589.54  5030.1  589.15  5040.1  589.50
  5060.1  589.31  5100.1  592.26  5109.2  592.69  5150.1  596.07  5180.1  599.53
  5191.4  601.18  5210.1  603.19  5220.1  604.66  5280.1  609.47  5300.1  610.05
#Mann=6,-1,0
  4793.9    0.12       0  4871.1    0.07       0  4987.7    0.05       0
  4991.9    0.07       0  5109.2    0.12       0  5191.4    0.07       0
Bank Sta=4987.7,4991.9
Exp/Cntr=0.3,0.1

Type RM Length L Ch R = 1,11226,477,477,477
BEGIN DESCRIPTION:
CARDELL CREEK 24.0
END DESCRIPTION:
XS GIS Cut Line= 3
      2327624.97     13712975.00      2327375.00     13712975.00
      2327025.03     13713025.00
#Sta/Elev= 30
  4750.5  610.03  4760.5  609.50  4773.7  608.03  4790.5  606.73  4800.5  605.09
  4830.5  602.31  4840.5  600.95  4903.4  595.15  4920.4  593.77  4950.5  591.01
  4990.5  588.03  4998.0  586.80  5003.0  586.80  5008.4  585.71  5008.7  585.21
  5012.5  585.21  5012.8  585.71  5051.0  586.69  5071.2  586.85  5111.6  586.48
  5131.8  587.65  5182.3  593.62  5192.4  594.55  5202.5  595.95  5212.6  596.64
  5232.8  599.40  5295.7  605.80  5313.6  607.36  5323.7  608.57  5354.0  609.74
#Mann=7,-1,0
  4750.5    0.12       0  4773.7    0.07       0  4903.4    0.12       0
  4920.4    0.07       0  5008.4    0.05       0  5012.8    0.07       0
  5295.7   0.035       0
Bank Sta=5008.4,5012.8
Exp/Cntr=0.3,0.1

Type RM Length L Ch R = 1,10749,455,455,455
BEGIN DESCRIPTION:
CARDELL CREEK 23.0
END DESCRIPTION:
XS GIS Cut Line= 3
      2327674.98     13712774.99      2327275.00     13712525.00
      2327124.97     13712525.00
#Sta/Elev= 30
  4536.7  607.59  4602.1  601.84  4617.5  601.29  4696.5  595.71  4716.1  595.09
  4733.0  593.68  4754.2  592.99  4769.6  591.58  4775.5  591.45  4790.8  589.80
  4812.0  588.89  4827.4  587.42  4848.6  586.79  4863.9  585.28  4885.1  584.27
  4942.9  583.31  4947.1  581.23  4947.5  580.73  4951.4  580.73  4951.7  581.23
  4958.3  581.65  4964.2  581.32  4979.5  583.07  5000.7  583.14  5005.4  583.56
  5028.4  583.15  5038.4  583.63  5078.4  589.97  5138.4  597.85  5158.4  599.96
#Mann=4,-1,0
  4536.7    0.07       0  4716.1    0.12       0  4947.1    0.05       0
  4951.7    0.12       0
Bank Sta=4947.1,4951.7
Exp/Cntr=0.3,0.1

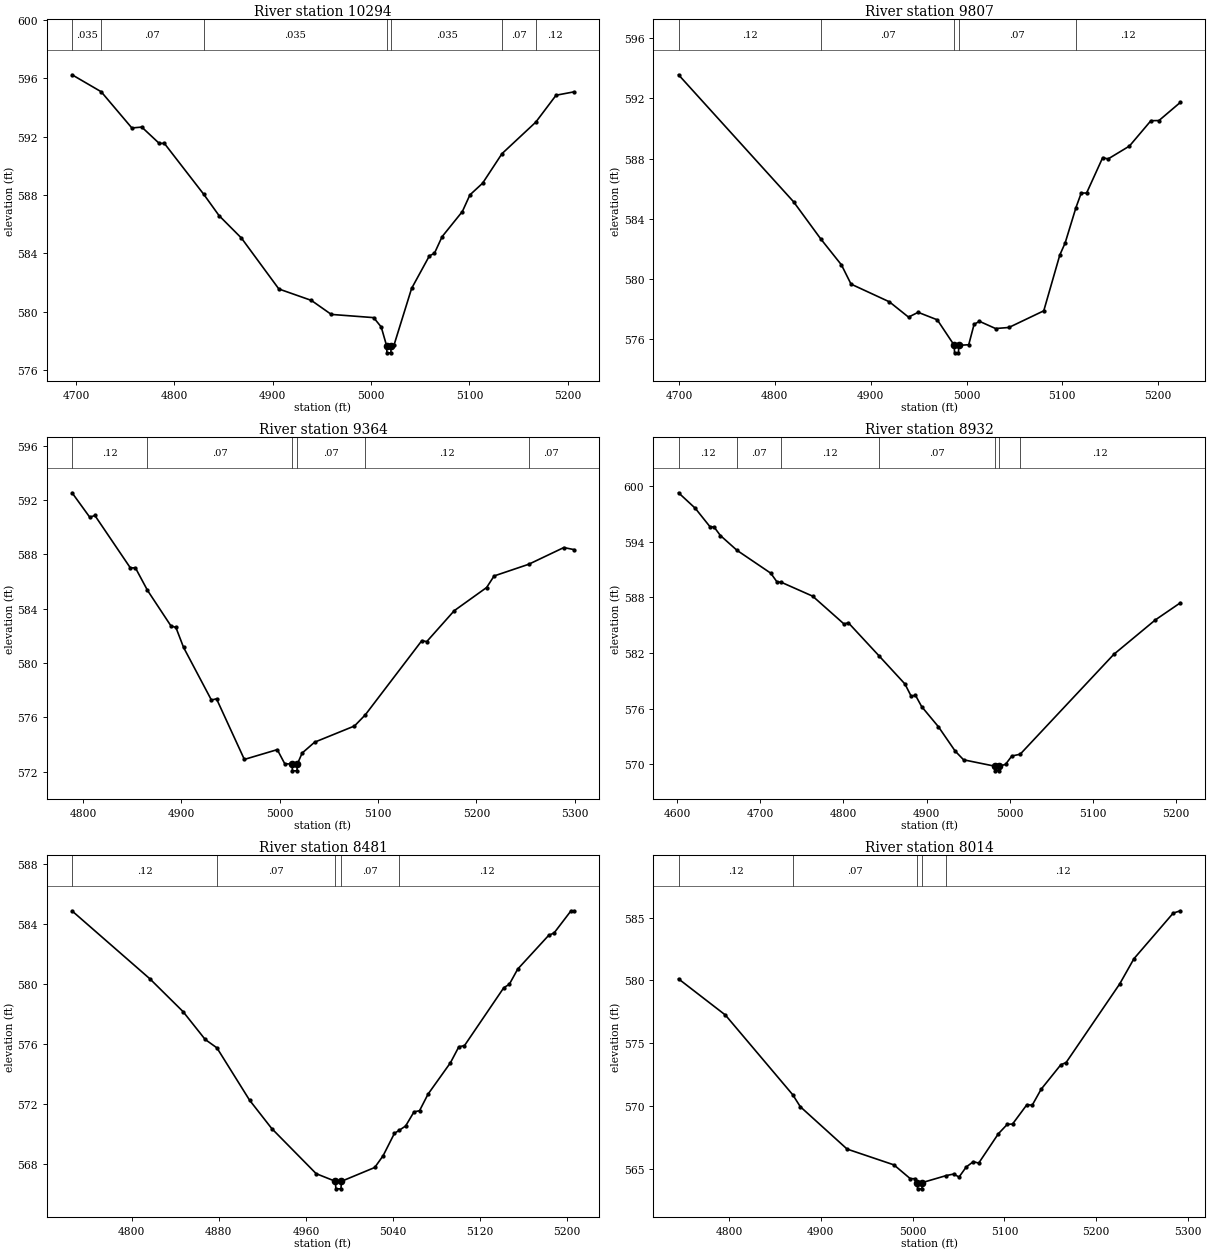
Type RM Length L Ch R = 1,10294,487,487,487
BEGIN DESCRIPTION:
CARDELL CREEK 22.0
END DESCRIPTION:
XS GIS Cut Line= 3
      2327574.98     13712025.00      2327275.00     13712075.00
      2327074.97     13712125.01
#Sta/Elev= 30
  4695.9  596.23  4725.5  595.07  4756.7  592.59  4766.8  592.65  4784.6  591.53
  4789.7  591.54  4829.7  588.06  4845.4  586.59  4868.2  585.05  4906.2  581.57
  4939.2  580.79  4959.5  579.83  5002.6  579.61  5010.3  578.97  5015.7  577.70
  5016.1  577.20  5020.1  577.20  5020.4  577.70  5023.2  577.71  5041.2  581.61
  5059.3  583.84  5064.4  584.01  5072.2  585.15  5092.8  586.87  5100.5  588.01
  5113.4  588.81  5133.1  590.83  5167.5  592.99  5188.1  594.83  5206.2  595.06
#Mann=7,-1,0
  4695.9   0.035       0  4725.5    0.07       0  4829.7   0.035       0
  5015.7   0.035       0  5020.4   0.035       0  5133.1    0.07       0
  5167.5    0.12       0
Bank Sta=5015.7,5020.4
Exp/Cntr=0.3,0.1

Type RM Length L Ch R = 1,9807,443,443,443
BEGIN DESCRIPTION:
CARDELL CREEK 21.0
END DESCRIPTION:
XS GIS Cut Line= 3
      2327475.02     13711625.00      2327175.00     13711625.00
      2326975.03     13711724.99
#Sta/Elev= 30
  4699.5  593.58  4819.5  585.12  4847.8  582.65  4869.5  580.91  4879.5  579.63
  4919.5  578.45  4939.5  577.43  4949.5  577.75  4969.5  577.25  4987.2  575.55
  4987.5  575.05  4991.6  575.05  4991.9  575.55  5002.3  575.59  5007.9  576.95
  5013.5  577.15  5030.3  576.67  5044.2  576.74  5080.6  577.85  5097.4  581.58
  5102.9  582.37  5114.2  584.73  5119.7  585.70  5125.3  585.70  5142.1  588.06
  5147.7  587.97  5170.0  588.83  5192.4  590.52  5200.8  590.53  5223.1  591.74
#Mann=5,-1,0
  4699.5    0.12       0  4847.8    0.07       0  4987.2    0.05       0
  4991.9    0.07       0  5114.2    0.12       0
Bank Sta=4987.2,4991.9
Exp/Cntr=0.3,0.1

Type RM Length L Ch R = 1,9364,432,432,432
BEGIN DESCRIPTION:
CARDELL CREEK 20.0
END DESCRIPTION:
XS GIS Cut Line= 3
      2327424.99     13711275.00      2327225.00     13711225.00
      2326924.98     13711275.00
#Sta/Elev= 30
  4788.8  592.53  4806.8  590.73  4812.0  590.86  4848.1  587.00  4853.2  587.01
  4865.5  585.35  4889.3  582.74  4894.4  582.62  4902.2  581.15  4930.5  577.28
  4935.7  577.37  4964.0  572.91  4997.5  573.63  5005.1  572.59  5012.5  572.57
  5012.9  572.07  5017.5  572.07  5017.9  572.57  5022.8  573.38  5035.5  574.18
  5076.0  575.37  5087.0  576.19  5144.5  581.65  5149.5  581.58  5177.4  583.85
  5210.4  585.56  5218.0  586.41  5253.2  587.27  5288.9  588.50  5299.1  588.35
#Mann=6,-1,0
  4788.8    0.12       0  4865.5    0.07       0  5012.5    0.05       0
  5017.9    0.07       0  5087.0    0.12       0  5253.2    0.07       0
Bank Sta=5012.5,5017.9
Exp/Cntr=0.3,0.1

Type RM Length L Ch R = 1,8932,451,451,451
BEGIN DESCRIPTION:
CARDELL CREEK 19.0
END DESCRIPTION:
XS GIS Cut Line= 3
      2327524.96     13710874.99      2327125.00     13710825.00
      2326924.97     13710825.00
#Sta/Elev= 30
  4601.8  599.28  4621.9  597.61  4639.5  595.63  4644.6  595.58  4652.1  594.67
  4672.1  593.07  4712.6  590.61  4720.2  589.66  4725.0  589.64  4763.0  588.13
  4800.8  585.12  4805.8  585.27  4842.9  581.68  4873.9  578.66  4881.4  577.34
  4886.5  577.45  4894.0  576.22  4914.2  574.04  4934.3  571.42  4944.4  570.48
  4982.0  569.79  4982.4  569.29  4987.0  569.29  4987.5  569.79  4994.8  569.99
  5002.4  570.89  5012.4  571.08  5124.9  581.85  5174.9  585.57  5204.9  587.41
#Mann=7,-1,0
  4601.8    0.12       0  4672.1    0.07       0  4725.0    0.12       0
  4842.9    0.07       0  4982.0    0.05       0  4987.5    0.07       0
  5012.4    0.12       0
Bank Sta=4982,4987.5
Exp/Cntr=0.3,0.1

Type RM Length L Ch R = 1,8481,467,467,467
BEGIN DESCRIPTION:
CARDELL CREEK 18.0
END DESCRIPTION:
XS GIS Cut Line= 3
      2327374.97     13710424.99      2327125.00     13710375.00
      2326924.98     13710425.01
#Sta/Elev= 30
  4745.1  584.86  4816.5  580.35  4847.1  578.16  4867.4  576.31  4878.2  575.75
  4908.2  572.27  4928.6  570.38  4969.4  567.38  4987.1  566.87  4987.5  566.37
  4992.2  566.37  4992.6  566.87  5023.2  567.79  5030.9  568.57  5041.3  570.06
  5045.8  570.27  5051.6  570.55  5059.3  571.49  5064.4  571.57  5072.2  572.67
  5092.8  574.76  5100.5  575.82  5105.7  575.90  5141.8  579.75  5146.9  579.98
  5154.6  580.99  5183.0  583.23  5188.1  583.40  5203.6  584.87  5206.2  584.87
#Mann=5,-1,0
  4745.1    0.12       0  4878.2    0.07       0  4987.1    0.05       0
  4992.6    0.07       0  5045.8    0.12       0
Bank Sta=4987.1,4992.6
Exp/Cntr=0.3,0.1

Type RM Length L Ch R = 1,8014,482,482,482
BEGIN DESCRIPTION:
CARDELL CREEK 17.0
END DESCRIPTION:
XS GIS Cut Line= 3
      2327325.02     13709975.00      2327075.00     13709925.00
      2326825.02     13710074.99
#Sta/Elev= 30
  4745.0  580.12  4796.0  577.24  4869.4  570.88  4877.6  569.93  4928.6  566.55
  4979.6  565.29  4997.4  564.19  5002.9  564.19  5004.9  563.88  5005.4  563.38
  5010.1  563.38  5010.5  563.88  5036.7  564.44  5044.7  564.56  5050.5  564.32
  5058.3  565.12  5066.1  565.55  5071.9  565.43  5093.3  567.77  5103.0  568.52
  5108.8  568.55  5124.4  570.09  5130.2  570.05  5139.9  571.32  5161.3  573.27
  5167.1  573.45  5225.4  579.71  5241.0  581.73  5283.7  585.36  5291.5  585.55
#Mann=5,-1,0
  4745.0    0.12       0  4869.4    0.07       0  5004.9    0.05       0
  5010.5    0.07       0  5036.7    0.12       0
Bank Sta=5004.9,5010.5
Exp/Cntr=0.3,0.1

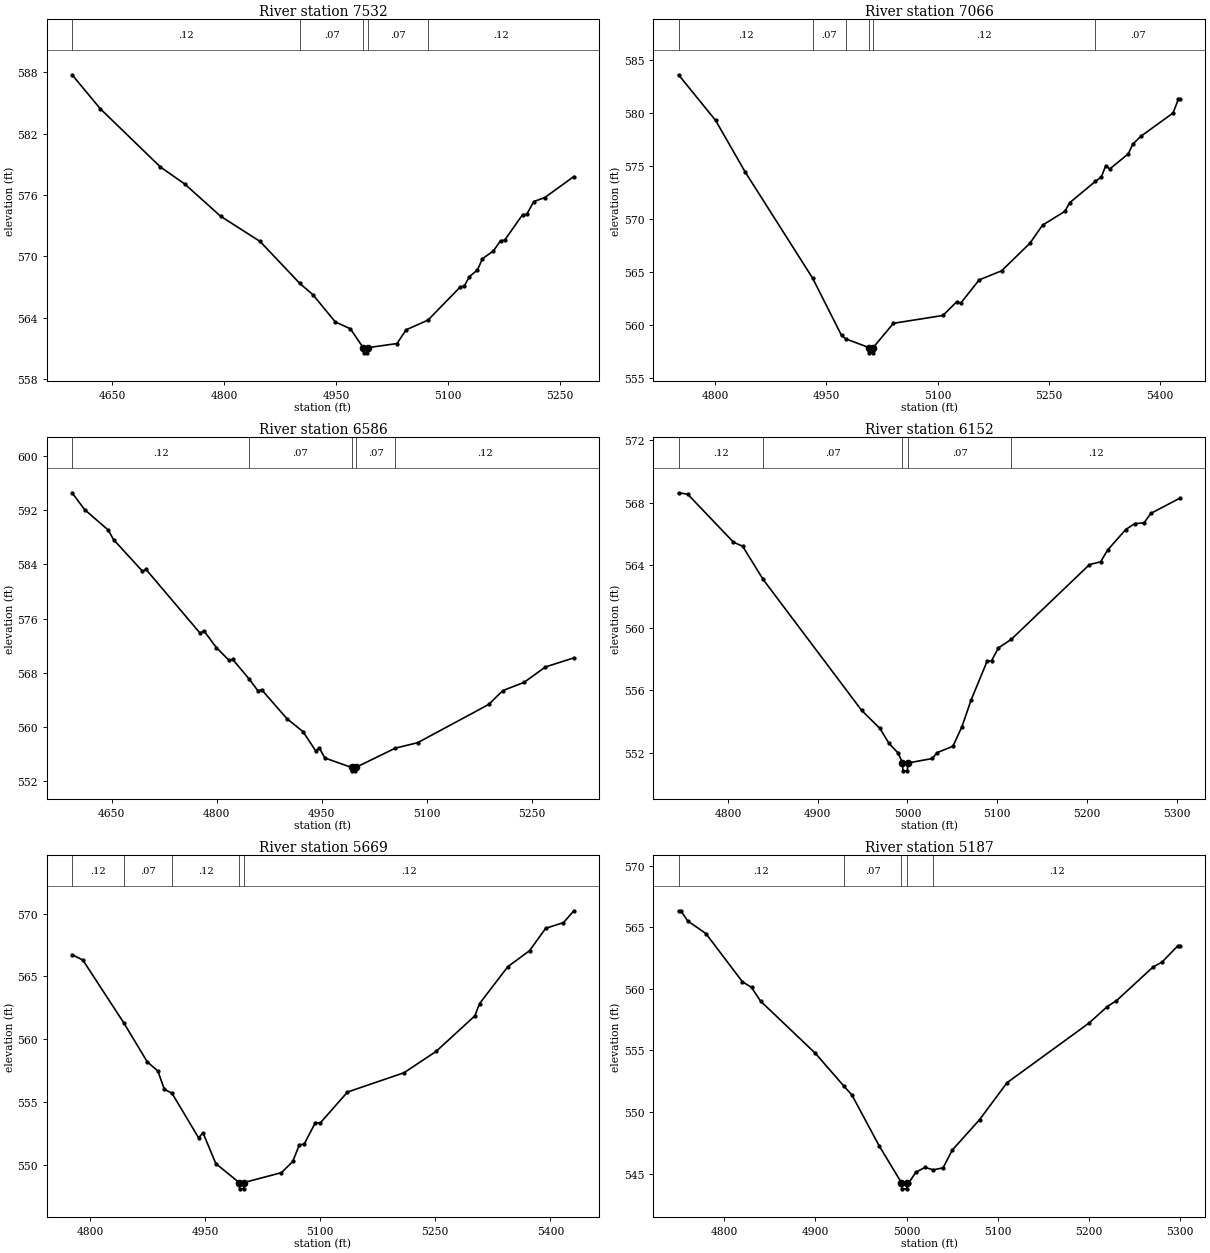
Type RM Length L Ch R = 1,7532,466,466,466
BEGIN DESCRIPTION:
CARDELL CREEK 16.0
END DESCRIPTION:
XS GIS Cut Line= 3
      2327474.98     13709425.00      2327075.00     13709475.00
      2326825.05     13709574.98
#Sta/Elev= 30
  4596.5  587.75  4634.3  584.43  4714.9  578.73  4747.6  577.06  4795.5  573.92
  4848.4  571.45  4901.6  567.35  4919.0  566.26  4949.2  563.58  4969.4  562.91
  4986.6  561.06  4987.1  560.56  4991.9  560.56  4992.4  561.06  5031.9  561.47
  5044.0  562.81  5073.4  563.76  5116.7  567.01  5122.1  567.10  5128.8  568.01
  5139.6  568.66  5146.3  569.76  5161.1  570.53  5170.6  571.53  5176.0  571.57
  5200.2  574.08  5205.6  574.09  5215.0  575.35  5229.8  575.74  5268.8  577.80
#Mann=5,-1,0
  4596.5    0.12       0  4901.6    0.07       0  4986.6    0.05       0
  4992.4    0.07       0  5073.4    0.12       0
Bank Sta=4986.6,4992.4
Exp/Cntr=0.3,0.1

Type RM Length L Ch R = 1,7066,480,480,480
BEGIN DESCRIPTION:
CARDELL CREEK 15.0
END DESCRIPTION:
XS GIS Cut Line= 3
      2327374.99     13709025.00      2327125.00     13709025.00
      2326724.99     13709175.00
#Sta/Elev= 30
  4750.4  583.60  4800.4  579.29  4840.4  574.41  4931.4  564.38  4970.4  558.97
  4976.1  558.65  5007.3  557.83  5007.7  557.33  5012.6  557.33  5013.1  557.83
  5040.4  560.12  5107.2  560.86  5125.9  562.16  5131.2  562.02  5156.1  564.22
  5186.4  565.08  5224.7  567.69  5241.6  569.39  5271.8  570.70  5278.1  571.50
  5313.1  573.54  5320.8  573.92  5327.0  575.01  5332.4  574.70  5357.3  576.13
  5363.5  577.05  5374.2  577.78  5417.8  579.99  5424.9  581.28  5427.6  581.28
#Mann=6,-1,0
  4750.4    0.12       0  4931.4    0.07       0  4976.1    0.12       0
  5007.3    0.05       0  5013.1    0.12       0  5313.1    0.07       0
Bank Sta=5007.3,5013.1
Exp/Cntr=0.3,0.1

Type RM Length L Ch R = 1,6586,434,434,434
BEGIN DESCRIPTION:
CARDELL CREEK 14.0
END DESCRIPTION:
XS GIS Cut Line= 3
      2327425.02     13708675.00      2327025.00     13708575.00
      2326724.97     13708625.01
#Sta/Elev= 30
  4593.6  594.58  4611.7  592.08  4645.2  589.08  4652.9  587.66  4694.1  583.01
  4699.3  583.26  4776.6  573.84  4781.7  574.23  4799.8  571.72  4817.8  569.85
  4823.0  569.99  4846.5  567.09  4859.0  565.36  4864.2  565.53  4900.3  561.26
  4923.5  559.32  4941.5  556.49  4946.7  556.94  4954.4  555.45  4992.7  554.05
  4993.2  553.55  4998.1  553.55  4998.6  554.05  5055.2  556.90  5087.0  557.70
  5188.4  563.34  5208.7  565.39  5239.1  566.61  5269.5  568.88  5310.1  570.22
#Mann=5,-1,0
  4593.6    0.12       0  4846.5    0.07       0  4992.7    0.05       0
  4998.6    0.07       0  5055.2    0.12       0
Bank Sta=4992.7,4998.6
Exp/Cntr=0.3,0.1

Type RM Length L Ch R = 1,6152,483,483,483
BEGIN DESCRIPTION:
CARDELL CREEK 13.0
END DESCRIPTION:
XS GIS Cut Line= 3
      2327175.05     13708124.99      2326925.00     13708175.00
      2326625.04     13708224.99
#Sta/Elev= 30
  4745.0  568.64  4755.2  568.55  4806.2  565.48  4816.4  565.22  4839.2  563.10
  4949.0  554.72  4969.4  553.56  4979.6  552.60  4989.8  551.98  4994.5  551.35
  4995.0  550.85  5000.0  550.85  5000.5  551.35  5027.9  551.64  5032.9  552.01
  5050.7  552.42  5060.8  553.68  5071.0  555.38  5088.7  557.85  5093.8  557.90
  5101.4  558.71  5115.9  559.27  5202.8  564.04  5215.4  564.23  5223.0  564.97
  5243.3  566.29  5253.4  566.67  5263.6  566.71  5271.2  567.32  5304.1  568.31
#Mann=5,-1,0
  4745.0    0.12       0  4839.2    0.07       0  4994.5    0.05       0
  5000.5    0.07       0  5115.9    0.12       0
Bank Sta=4994.5,5000.5
Exp/Cntr=0.3,0.1

Type RM Length L Ch R = 1,5669,482,482,482
BEGIN DESCRIPTION:
CARDELL CREEK 12.0
END DESCRIPTION:
XS GIS Cut Line= 3
      2327125.02     13707624.99      2326925.00     13707725.00
      2326575.04     13707974.97
#Sta/Elev= 30
  4776.8  566.72  4790.8  566.30  4844.5  561.26  4874.6  558.20  4888.6  557.45
  4897.0  556.00  4907.0  555.68  4941.7  552.13  4947.3  552.54  4964.1  550.08
  4994.5  548.57  4995.0  548.07  5000.2  548.07  5000.7  548.57  5049.6  549.36
  5064.3  550.25  5072.9  551.58  5079.1  551.62  5093.8  553.35  5100.0  553.31
  5135.6  555.78  5209.3  557.32  5251.1  559.02  5301.5  561.85  5307.7  562.83
  5344.5  565.77  5372.8  567.04  5393.7  568.82  5417.0  569.28  5430.5  570.22
#Mann=5,-1,0
  4776.8    0.12       0  4844.5    0.07       0  4907.0    0.12       0
  4994.5    0.05       0  5000.7    0.12       0
Bank Sta=4994.5,5000.7
Exp/Cntr=0.3,0.1

Type RM Length L Ch R = 1,5187,451,451,451
BEGIN DESCRIPTION:
CARDELL CREEK 11.0
END DESCRIPTION:
XS GIS Cut Line= 3
      2327075.00     13707275.00      2326825.00     13707275.00
      2326525.00     13707275.00
#Sta/Elev= 30
  4750.0  566.33  4752.5  566.33  4760.0  565.51  4780.0  564.48  4820.0  560.57
  4830.0  560.11  4840.0  558.99  4900.0  554.76  4931.0  552.12  4940.0  551.38
  4970.0  547.24  4994.3  544.26  4994.8  543.76  5000.1  543.76  5000.6  544.26
  5002.5  544.26  5010.0  545.10  5020.0  545.50  5029.4  545.30  5040.0  545.47
  5050.0  546.90  5080.0  549.38  5110.0  552.37  5200.0  557.22  5220.0  558.56
  5230.0  559.03  5270.0  561.76  5280.0  562.17  5297.5  563.50  5300.0  563.50
#Mann=5,-1,0
  4750.0    0.12       0  4931.0    0.07       0  4994.3    0.05       0
  5000.6    0.07       0  5029.4    0.12       0
Bank Sta=4994.3,5000.6
Exp/Cntr=0.3,0.1

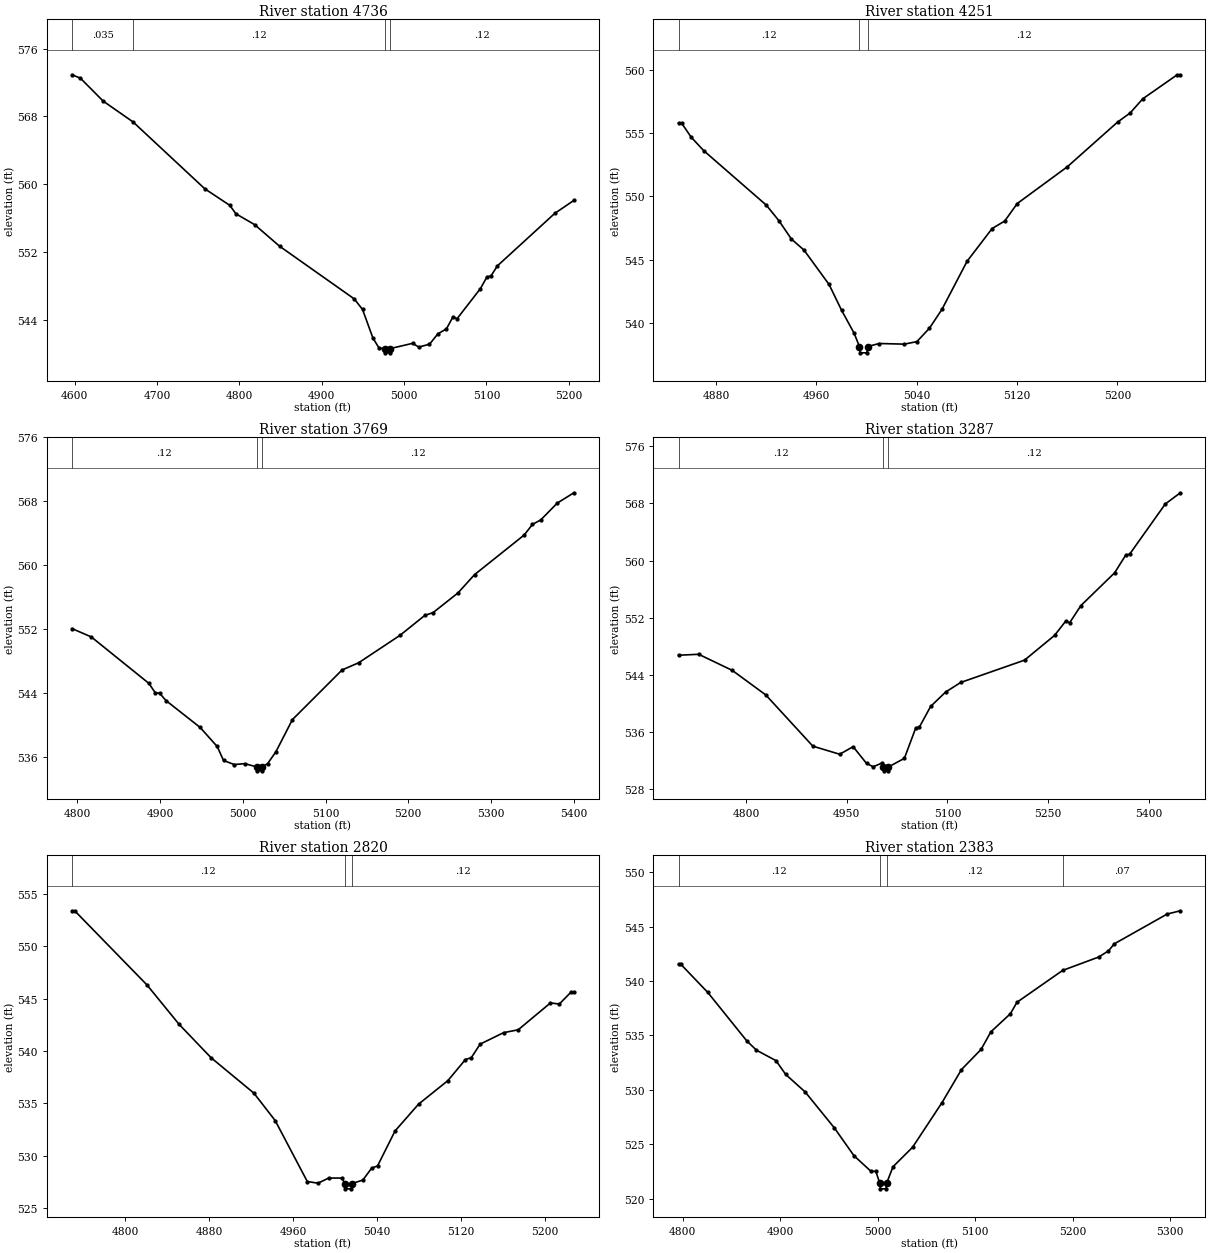
Type RM Length L Ch R = 1,4736,485,485,485
BEGIN DESCRIPTION:
CARDELL CREEK 10.0
END DESCRIPTION:
XS GIS Cut Line= 3
      2327174.99     13706925.00      2326775.00     13706875.00
      2326574.96     13706925.01
#Sta/Elev= 30
  4596.9  572.90  4607.0  572.50  4634.7  569.79  4671.0  567.33  4758.1  559.44
  4788.4  557.49  4795.9  556.49  4818.6  555.21  4848.8  552.67  4939.5  546.45
  4949.6  545.20  4962.2  541.83  4969.8  540.62  4976.7  540.58  4977.2  540.08
  4982.6  540.08  4983.1  540.58  5010.3  541.20  5018.0  540.76  5030.9  541.10
  5041.2  542.33  5051.5  542.91  5059.3  544.31  5064.4  544.11  5092.8  547.67
  5100.5  549.01  5105.7  549.18  5113.4  550.35  5183.0  556.54  5206.2  558.07
#Mann=4,-1,0
  4596.9   0.035       0  4671.0    0.12       0  4976.7    0.05       0
  4983.1    0.12       0
Bank Sta=4976.7,4983.1
Exp/Cntr=0.3,0.1

Type RM Length L Ch R = 1,4251,482,482,482
BEGIN DESCRIPTION:
CARDELL CREEK 9.0
END DESCRIPTION:
XS GIS Cut Line= 3
      2326924.99     13706425.00      2326775.00     13706425.00
      2326524.99     13706425.00
#Sta/Elev= 30
  4850.1  555.81  4852.6  555.81  4860.1  554.71  4870.1  553.64  4920.1  549.31
  4930.1  548.08  4940.1  546.62  4950.1  545.75  4970.1  543.02  4980.1  540.97
  4990.1  539.15  4994.3  538.10  4994.8  537.60  5000.3  537.60  5000.8  538.10
  5010.1  538.34  5030.1  538.29  5040.1  538.49  5050.1  539.55  5060.1  541.05
  5080.1  544.86  5100.1  547.46  5110.1  548.05  5120.1  549.44  5160.1  552.36
  5200.1  555.90  5210.1  556.62  5220.1  557.74  5247.6  559.65  5250.1  559.65
#Mann=3,-1,0
  4850.1    0.12       0  4994.3    0.05       0  5000.8    0.12       0
Bank Sta=4994.3,5000.8
Exp/Cntr=0.3,0.1

Type RM Length L Ch R = 1,3769,482,482,482
BEGIN DESCRIPTION:
CARDELL CREEK 8.0
END DESCRIPTION:
XS GIS Cut Line= 3
      2326875.04     13706025.01      2326675.00     13705975.00
      2326275.00     13705975.00
#Sta/Elev= 30
  4793.8  552.03  4817.0  550.99  4886.6  545.17  4894.3  543.99  4899.5  543.94
  4907.2  543.02  4948.5  539.65  4969.1  537.26  4976.8  535.51  4989.7  535.00
  5002.5  535.11  5016.7  534.71  5017.2  534.21  5022.8  534.21  5023.3  534.71
  5030.0  535.11  5040.0  536.59  5060.0  540.63  5120.0  546.85  5140.0  547.75
  5190.0  551.19  5220.0  553.69  5230.0  554.04  5260.0  556.50  5280.0  558.79
  5340.0  563.76  5350.0  565.09  5360.0  565.65  5380.0  567.76  5400.0  569.05
#Mann=3,-1,0
  4793.8    0.12       0  5016.7    0.05       0  5023.3    0.12       0
Bank Sta=5016.7,5023.3
Exp/Cntr=0.3,0.1

Type RM Length L Ch R = 1,3287,467,467,467
BEGIN DESCRIPTION:
CARDELL CREEK 7.0
END DESCRIPTION:
XS GIS Cut Line= 3
      2326974.98     13705525.00      2326675.00     13705525.00
      2326274.99     13705725.00
#Sta/Elev= 30
  4699.6  546.77  4729.6  546.90  4779.6  544.65  4829.6  541.21  4899.6  534.05
  4939.6  532.92  4959.6  533.98  4979.6  531.63  4989.6  531.17  5002.4  531.69
  5004.7  531.10  5005.2  530.60  5010.8  530.60  5011.3  531.10  5035.9  532.35
  5052.7  536.57  5058.3  536.73  5075.0  539.61  5097.4  541.63  5119.8  542.96
  5214.8  546.08  5259.5  549.54  5276.3  551.56  5281.9  551.29  5298.7  553.71
  5349.0  558.30  5365.7  560.80  5371.3  560.90  5424.4  567.92  5446.8  569.49
#Mann=3,-1,0
  4699.6    0.12       0  5004.7    0.05       0  5011.3    0.12       0
Bank Sta=5004.7,5011.3
Exp/Cntr=0.3,0.1

Type RM Length L Ch R = 1,2820,437,437,437
BEGIN DESCRIPTION:
CARDELL CREEK 6.0
END DESCRIPTION:
XS GIS Cut Line= 3
      2326874.98     13705025.00      2326625.00     13705075.00
      2326425.04     13705174.98
#Sta/Elev= 30
  4749.3  553.38  4751.8  553.38  4820.7  546.30  4851.3  542.54  4881.9  539.34
  4922.7  535.96  4943.0  533.34  4973.6  527.52  4983.8  527.36  4994.0  527.85
  5007.0  527.85  5009.2  527.32  5009.7  526.82  5015.6  526.82  5016.1  527.32
  5026.6  527.66  5035.0  528.80  5040.6  529.01  5057.3  532.35  5079.7  534.91
  5107.7  537.16  5124.4  539.17  5130.0  539.35  5138.4  540.64  5160.8  541.74
  5174.7  542.01  5205.5  544.58  5213.9  544.47  5225.0  545.60  5227.8  545.60
#Mann=3,-1,0
  4749.3    0.12       0  5009.2    0.05       0  5016.1    0.12       0
Bank Sta=5009.2,5016.1
Exp/Cntr=0.3,0.1

Type RM Length L Ch R = 1,2383,482,482,482
BEGIN DESCRIPTION:
CARDELL CREEK 5.0
END DESCRIPTION:
XS GIS Cut Line= 3
      2326724.98     13704675.00      2326525.00     13704675.00
      2326211.58     13704706.74
#Sta/Elev= 30
  4795.6  541.53  4798.1  541.53  4825.6  538.96  4865.6  534.51  4875.6  533.65
  4895.6  532.69  4905.6  531.42  4925.6  529.81  4955.6  526.50  4975.6  523.96
  4993.1  522.52  4998.1  522.52  5002.2  521.41  5002.7  520.91  5008.6  520.91
  5009.1  521.41  5015.7  522.94  5035.8  524.73  5065.9  528.82  5086.0  531.87
  5106.1  533.72  5116.2  535.34  5136.3  537.01  5142.9  538.05  5189.8  540.98
  5226.8  542.21  5236.8  542.77  5242.8  543.42  5297.1  546.16  5310.6  546.46
#Mann=4,-1,0
  4795.6    0.12       0  5002.2    0.05       0  5009.1    0.12       0
  5189.8    0.07       0
Bank Sta=5002.2,5009.1
Exp/Cntr=0.3,0.1

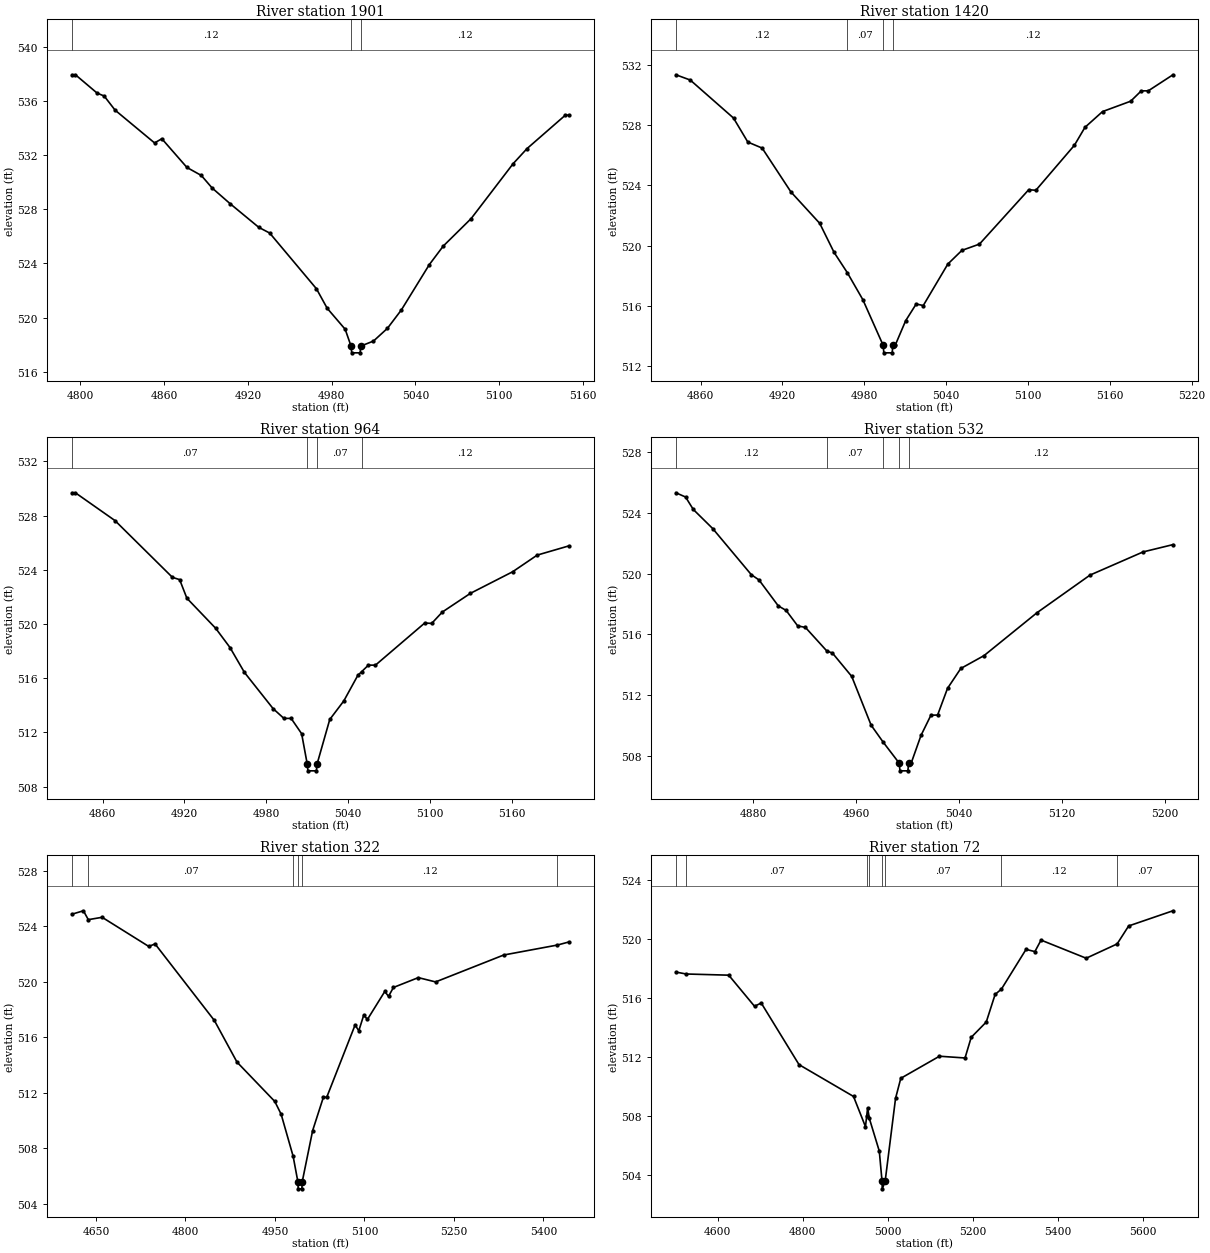
Type RM Length L Ch R = 1,1901,481,481,481
BEGIN DESCRIPTION:
CARDELL CREEK 4.0
END DESCRIPTION:
XS GIS Cut Line= 3
      2326625.03     13704275.01      2326425.00     13704225.00
      2326274.98     13704225.00
#Sta/Elev= 30
  4793.8  537.92  4796.4  537.92  4811.9  536.57  4817.0  536.35  4824.8  535.31
  4853.1  532.89  4858.3  533.20  4876.3  531.08  4886.6  530.49  4894.3  529.57
  4907.2  528.41  4927.8  526.66  4935.6  526.24  4969.1  522.13  4976.8  520.69
  4989.7  519.14  4993.9  517.90  4994.4  517.40  5000.4  517.40  5000.9  517.90
  5010.0  518.27  5020.0  519.21  5030.0  520.57  5050.0  523.91  5060.0  525.28
  5080.0  527.31  5110.0  531.35  5120.0  532.47  5147.5  534.94  5150.0  534.94
#Mann=3,-1,0
  4793.8    0.12       0  4993.9    0.05       0  5000.9    0.12       0
Bank Sta=4993.9,5000.9
Exp/Cntr=0.3,0.1

Type RM Length L Ch R = 1,1420,456,456,456
BEGIN DESCRIPTION:
CARDELL CREEK 3.0
END DESCRIPTION:
XS GIS Cut Line= 3
      2326674.99     13703825.00      2326525.00     13703775.00
      2326324.96     13703825.01
#Sta/Elev= 30
  4841.9  531.37  4852.4  531.02  4884.1  528.49  4894.6  526.89  4905.1  526.49
  4926.2  523.57  4947.3  521.48  4957.8  519.55  4967.5  518.20  4978.9  516.40
  4993.8  513.36  4994.3  512.86  5000.4  512.86  5000.9  513.36  5002.6  513.36
  5010.3  515.00  5018.0  516.11  5023.2  516.01  5041.2  518.77  5051.5  519.68
  5064.4  520.10  5100.5  523.72  5105.7  523.68  5134.0  526.68  5141.7  527.87
  5154.6  528.92  5175.2  529.61  5183.0  530.30  5188.1  530.30  5206.2  531.37
#Mann=4,-1,0
  4841.9    0.12       0  4967.5    0.07       0  4993.8    0.05       0
  5000.9    0.12       0
Bank Sta=4993.8,5000.9
Exp/Cntr=0.3,0.1

Type RM Length L Ch R = 1,964,432,432,432
BEGIN DESCRIPTION:
CARDELL CREEK 2.0
END DESCRIPTION:
XS GIS Cut Line= 3
      2326774.96     13703424.99      2326625.00     13703375.00
      2326425.03     13703325.01
#Sta/Elev= 30
  4837.5  529.69  4840.1  529.69  4869.1  527.64  4911.2  523.45  4916.5  523.28
  4921.8  521.91  4942.9  519.69  4953.4  518.27  4964.0  516.43  4985.0  513.76
  4992.9  513.04  4998.2  513.04  5005.9  511.91  5010.0  509.67  5010.5  509.17
  5016.7  509.17  5017.2  509.67  5026.5  512.96  5036.8  514.33  5047.1  516.22
  5050.0  516.50  5054.8  516.97  5060.0  516.97  5096.1  520.08  5101.2  520.05
  5109.0  520.89  5129.6  522.27  5160.5  523.86  5178.5  525.09  5201.7  525.77
#Mann=4,-1,0
  4837.5    0.07       0  5010.0    0.05       0  5017.2    0.07       0
  5050.0    0.12       0
Bank Sta=5010,5017.2
Exp/Cntr=0.3,0.1

Type RM Length L Ch R = 1,532,210,210,210
BEGIN DESCRIPTION:
CARDELL CREEK 1.0
END DESCRIPTION:
XS GIS Cut Line= 3
      2326875.02     13703075.01      2326725.00     13702975.00
      2326524.96     13702924.99
#Sta/Elev= 30
  4819.7  525.34  4827.2  525.06  4833.2  524.24  4848.3  522.98  4878.3  519.94
  4884.3  519.59  4899.3  517.88  4905.4  517.58  4914.4  516.56  4920.4  516.46
  4937.1  514.90  4941.4  514.77  4956.4  513.23  4971.5  510.01  4980.8  508.90
  4993.4  507.50  4993.9  507.00  5000.1  507.00  5000.6  507.50  5002.6  507.50
  5010.3  509.34  5018.0  510.67  5023.2  510.68  5030.9  512.44  5041.2  513.75
  5059.3  514.60  5100.5  517.43  5141.7  519.91  5183.0  521.44  5206.2  521.92
#Mann=5,-1,0
  4819.7    0.12       0  4937.1    0.07       0  4980.8    0.12       0
  4993.4    0.05       0  5000.6    0.12       0
Bank Sta=4993.4,5000.6
Exp/Cntr=0.3,0.1

Type RM Length L Ch R = 1,322,250,250,250
BEGIN DESCRIPTION:
X18415
END DESCRIPTION:
XS GIS Cut Line= 3
      2327147.07     13702906.69      2326702.93     13702755.49
      2326414.72     13702977.56
#Sta/Elev= 30
  4609.5  524.87  4628.9  525.12  4637.1  524.48  4660.3  524.65  4738.4  522.55
  4749.0  522.73  4848.4  517.21  4886.3  514.21  4949.7  511.37  4960.3  510.45
  4980.4  507.42  4988.4  505.57  4988.9  505.07  4995.1  505.07  4995.6  505.57
  5013.1  509.27  5031.3  511.70  5036.6  511.66  5084.2  516.88  5090.5  516.47
  5098.7  517.59  5105.0  517.29  5134.0  519.30  5140.3  518.95  5148.5  519.59
  5190.2  520.30  5219.2  519.99  5333.3  521.93  5423.4  522.65  5442.5  522.87
#Mann=6,-1,0
  4609.5   0.035       0  4637.1    0.07       0  4980.4    0.12       0
  4988.4    0.05       0  4995.6    0.12       0  5423.4    0.07       0
Bank Sta=4988.4,4995.6
Exp/Cntr=0.3,0.1

Type RM Length L Ch R = 1,72,0,0,0
BEGIN DESCRIPTION:
X18414
END DESCRIPTION:
XS GIS Cut Line= 4
      2327288.77     13702694.07      2326920.26     13702533.44
      2326655.69     13702571.24      2326353.31     13702968.11
#Sta/Elev= 30
  4501.8  517.78  4525.9  517.65  4625.9  517.57  4686.5  515.46  4702.3  515.68
  4791.1  511.50  4919.2  509.34  4947.3  507.29  4950.3  508.04  4952.4  508.57
  4956.4  507.85  4979.8  505.63  4986.3  503.57  4986.8  503.07  4993.5  503.57
  5018.0  509.21  5030.3  510.57  5121.2  512.07  5181.3  511.95  5195.8  513.35
  5231.2  514.39  5252.0  516.26  5267.0  516.63  5324.7  519.32  5345.5  519.17
  5360.0  519.95  5466.1  518.72  5538.8  519.69  5565.9  520.91  5670.0  521.94
#Mann=8,-1,0
  4501.8   0.035       0  4525.9    0.07       0  4950.3    0.12       0
  4956.4    0.07       0  4986.3    0.05       0  4993.5    0.07       0
  5267.0    0.12       0  5538.8    0.07       0
Bank Sta=4986.3,4993.5
Exp/Cntr=0.3,0.1

Chan Stop Cuts=-1