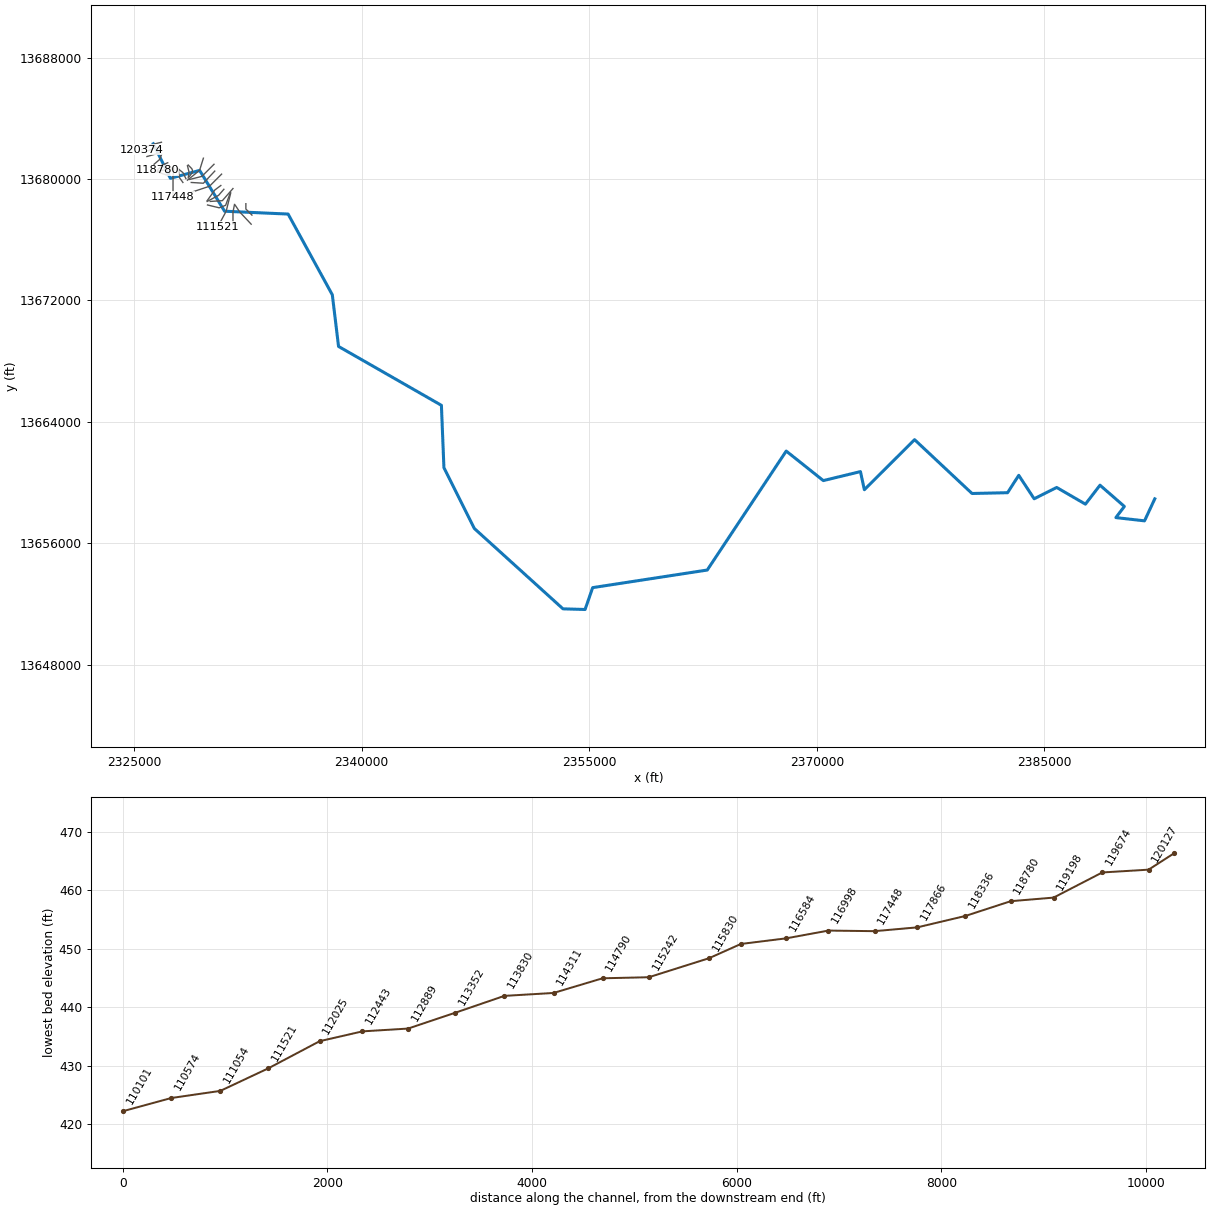
--- CLEAR FORK SANDIES CREEK.prj (project) ---

Proj Title=CLEAR FORK SANDIES CREEK Base Level Engineering
Current Plan=p01
Default Exp/Contr=0.3,0.1
English Units
Geom File=g01
Flow File=f01
Plan File=p01
Y Axis Title=Elevation
X Axis Title(PF)=Main Channel Distance
X Axis Title(XS)=Station
BEGIN DESCRIPTION:
CLEAR FORK SANDIES CREEK
END DESCRIPTION:
DSS Export Rating Curves= 0
DSS Export Rating Curve Sorted= 0
DSS Export Volume Flow Curves= 0
DXF OffsetX= 0
DXF OffsetY= 0
DXF ScaleX= 1
DXF ScaleY= 10

--- CLEAR FORK SANDIES CREEK.p01 (plan) ---

Plan Title=Multiple Run
Short Identifier=Multiple
Geom File=g01
Flow File=f01
Subcritical Flow
K Sum by GR= 0
Std Step Tol= 0.01
Critical Tol= 0.01
Num of Std Step Trials= 20
Max Error Tol= 0.3
Flow Tol Ratio= 0.001
Split Flow NTrial= 30
Split Flow Tol= 0.02
Split Flow Ratio= 0.02
Log Output Level= 0
Friction Slope Method= 1
Unsteady Friction Slope Method= 2
Unsteady Bridges Friction Slope Method= 1
Parabolic Critical Depth
Global Vel Dist=  1 , 1 , 1
Global Log Level= 0
CheckData=True
Encroach Param= -1, 0, 0, 0
BEGIN DESCRIPTION:
Multiple Run
END DESCRIPTION:

--- CLEAR FORK SANDIES CREEK.f01 (steady flow) ---

Flow Title=Multiple
Number of Profiles=7
Profile Names=10-year,25-year,50-year,1pct_min,100-year,1pct_plu,500-year
River Rch & RM= CLEAR FORK SANDI,Reach-1,120374
     811    1343    1834    1213    2420    4829    4179
River Rch & RM= CLEAR FORK SANDI,Reach-1,116998
    1016    1705    2351    1567    3126    6236    5485
River Rch & RM= CLEAR FORK SANDI,Reach-1,115242
    1185    1988    2739    1824    3640    7263    6377
River Rch & RM= CLEAR FORK SANDI,Reach-1,111521
    1908    3268    4565    3077    6138   12248   11016
River Rch & RM= CLEAR FORK SANDI,Reach-1,105149
    2795    4855    6848    4654    9285   18526   16946
River Rch & RM= CLEAR FORK SANDI,Reach-1,102962
    2725    4700    6597    4460    8898   17754   16069
River Rch & RM= CLEAR FORK SANDI,Reach-1,97324
    2864    4944    6943    4695    9367   18691   16927
River Rch & RM= CLEAR FORK SANDI,Reach-1,95131
    2835    4884    6850    4625    9229   18414   16629
River Rch & RM= CLEAR FORK SANDI,Reach-1,92950
    3883    6756    9540    6480   12929   25797   23571
River Rch & RM= CLEAR FORK SANDI,Reach-1,90185
    3992    6946    9808    6662   13292   26521   24228
River Rch & RM= CLEAR FORK SANDI,Reach-1,87452
    3873    6700    9422    6371   12713   25365   22968
River Rch & RM= CLEAR FORK SANDI,Reach-1,80921
    3855    6664    9367    6332   12634   25208   22807
River Rch & RM= CLEAR FORK SANDI,Reach-1,80383
    4386    7631   10775    7315   14595   29121   26576
River Rch & RM= CLEAR FORK SANDI,Reach-1,77470
    4433    7705   10871    7374   14713   29356   26742
River Rch & RM= CLEAR FORK SANDI,Reach-1,75388
    4440    7704   10857    7355   14674   29279   26602
River Rch & RM= CLEAR FORK SANDI,Reach-1,69790
    4468    7745   10907    7383   14732   29394   26669
River Rch & RM= CLEAR FORK SANDI,Reach-1,67439
    5327    9283   13122    8912   17783   35481   32402
River Rch & RM= CLEAR FORK SANDI,Reach-1,62434
    5429    9464   13382    9092   18140   36194   33071
River Rch & RM= CLEAR FORK SANDI,Reach-1,60844
    5428    9453   13355    9066   18088   36091   32919
River Rch & RM= CLEAR FORK SANDI,Reach-1,57341
    5532    9638   13621    9249   18455   36822   33607
River Rch & RM= CLEAR FORK SANDI,Reach-1,54967
    5591    9745   13776    9356   18668   37248   34011
River Rch & RM= CLEAR FORK SANDI,Reach-1,53845
    5629    9812   13870    9420   18795   37501   34239
River Rch & RM= CLEAR FORK SANDI,Reach-1,52709
    5622    9794   13841    9397   18750   37412   34137
River Rch & RM= CLEAR FORK SANDI,Reach-1,51084
    5603    9746   13757    9329   18613   37137   33802
River Rch & RM= CLEAR FORK SANDI,Reach-1,47201
    6573   11468   16222   11021   21990   43876   40075
River Rch & RM= CLEAR FORK SANDI,Reach-1,41473
    6982   12210   17302   11774   23493   46875   42955
River Rch & RM= CLEAR FORK SANDI,Reach-1,40762
    6926   12084   17096   11613   23171   46233   42218
River Rch & RM= CLEAR FORK SANDI,Reach-1,34433
    7040   12271   17348   11776   23496   46880   42742
River Rch & RM= CLEAR FORK SANDI,Reach-1,28356
    7036   12250   17304   11735   23415   46720   42520
River Rch & RM= CLEAR FORK SANDI,Reach-1,22771
    7144   12428   17547   11894   23732   47352   43048
River Rch & RM= CLEAR FORK SANDI,Reach-1,18374
    7415   12837   18071   12210   24363   48611   43892
River Rch & RM= CLEAR FORK SANDI,Reach-1,10007
    7422   12823   18024   12160   24262   48408   43571
Boundary for River Rch & Prof#=CLEAR FORK SANDI,Reach-1,1
Up Type=0
Dn Type=3
Dn Slope=0.001
Boundary for River Rch & Prof#=CLEAR FORK SANDI,Reach-1,2
Up Type=0
Dn Type=3
Dn Slope=0.001
Boundary for River Rch & Prof#=CLEAR FORK SANDI,Reach-1,3
Up Type=0
Dn Type=3
Dn Slope=0.001
Boundary for River Rch & Prof#=CLEAR FORK SANDI,Reach-1,4
Up Type=0
Dn Type=3
Dn Slope=0.001
Boundary for River Rch & Prof#=CLEAR FORK SANDI,Reach-1,5
Up Type=0
Dn Type=3
Dn Slope=0.001
Boundary for River Rch & Prof#=CLEAR FORK SANDI,Reach-1,6
Up Type=0
Dn Type=3
Dn Slope=0.001
Boundary for River Rch & Prof#=CLEAR FORK SANDI,Reach-1,7
Up Type=0
Dn Type=3
Dn Slope=0.001

--- CLEAR FORK SANDIES CREEK.g01 (geometry) ---

Geom Title=Existing Conditions
Program Version=4.10

River Reach=CLEAR FORK SANDI,Reach-1
Reach XY= 30
        2326275.       13682325.      2327401.59     13680047.43
      2329327.71      13680569.6      2330972.52      13677880.4
      2335158.99     13677692.14      2338071.64     13672373.75
      2338482.74     13668968.54       2345261.6     13665088.31
      2345426.95     13660981.26      2347430.73     13656972.45
        2353275.       13651675.      2354731.06     13651633.14
       2355230.9     13653073.03       2362781.4     13654232.99
       2367985.5     13662073.78      2370430.86     13660127.05
       2372877.7     13660719.64      2373135.41     13659525.95
      2376445.44     13662825.54      2380230.93     13659277.23
      2382573.44     13659328.74      2383309.84     13660474.64
      2384326.47     13658928.54      2385809.61     13659674.92
      2387705.01     13658574.94      2388664.56     13659823.96
      2390271.33     13658423.41      2389711.36     13657688.44
      2391599.96     13657474.49        2392275.       13658925.

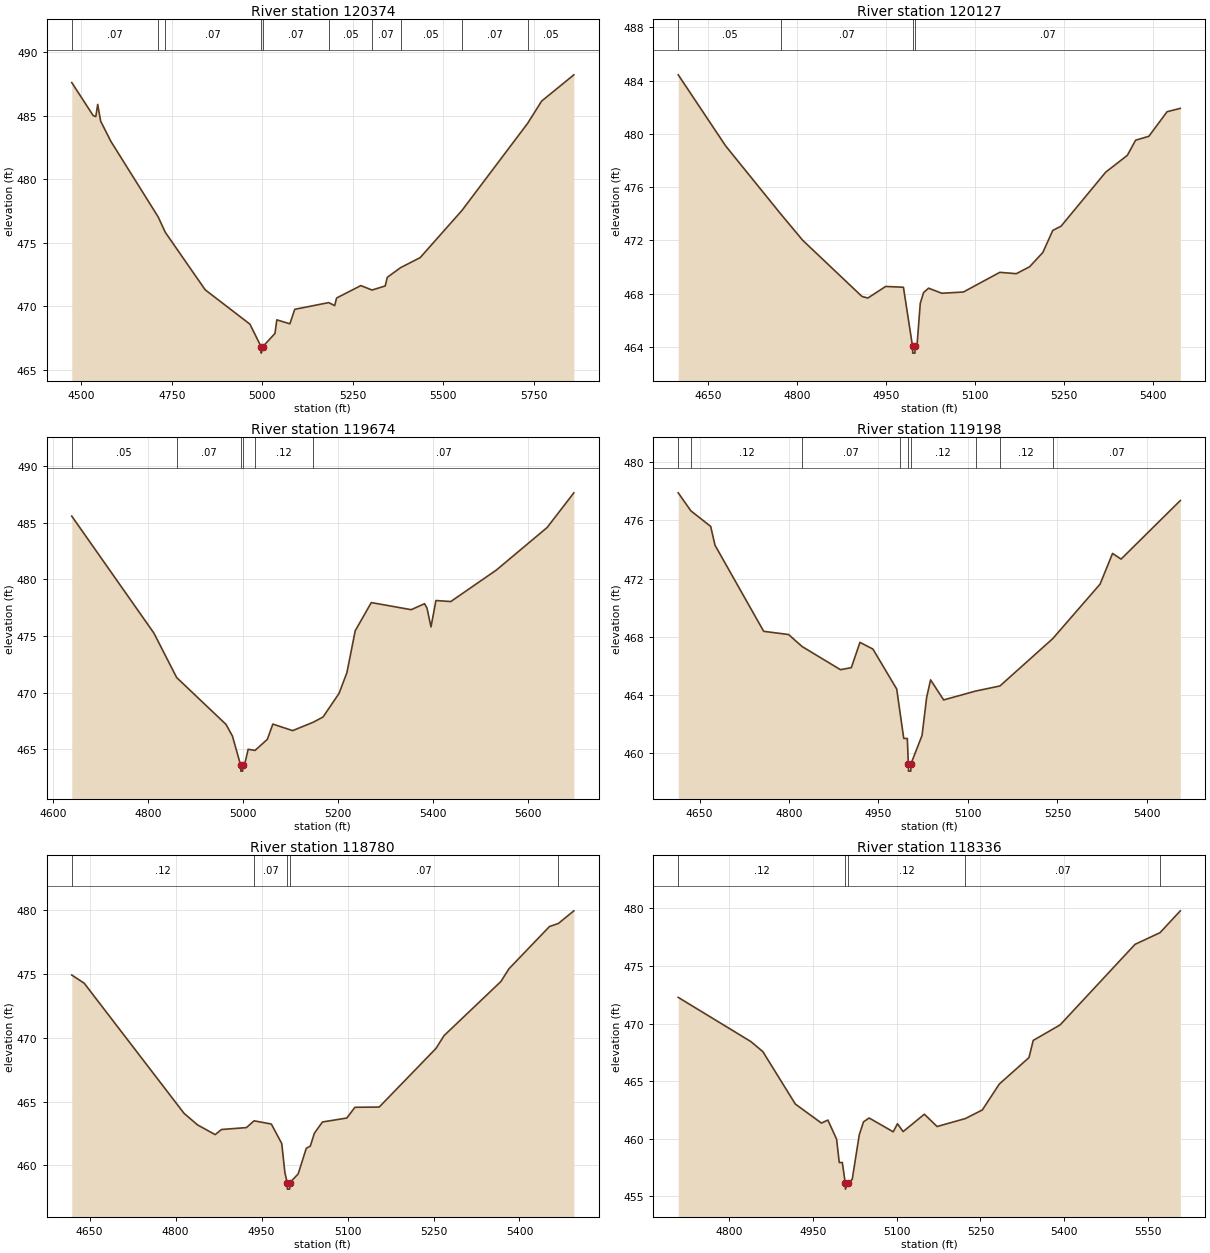
Type RM Length L Ch R = 1 ,120374  ,247,247,247
BEGIN DESCRIPTION:
X18506
END DESCRIPTION:
XS GIS Cut Line= 3
      2326812.42     13682426.61      2326035.75     13682232.44
      2325525.18     13681944.79
#Sta/Elev= 30
  4473.7  487.62  4532.9  485.02  4540.1  484.94  4545.3   485.9  4553.5  484.58
  4581.3  483.01  4712.3  477.04  4731.9  475.83  4842.1   471.3  4965.8  468.59
  4996.7  466.81    4997  466.31    5001  466.81  5034.9  467.86    5040  468.93
  5076.1  468.62  5089.5  469.76  5183.4  470.29  5199.8  470.05    5205  470.65
  5272.1  471.63    5303  471.28  5339.3   471.6  5345.1  472.28  5381.6  473.04
  5435.8  473.83  5551.1  477.54  5732.7  484.41  5771.3  486.16  5860.3  488.23
#Mann= 10 ,-1 , 0
  4473.7     .07       0  4712.3     .05       0  4731.9     .07       0
  4996.7     .05       0    5001     .07       0  5183.4     .05       0
    5303     .07       0  5381.6     .05       0  5551.1     .07       0
  5732.7     .05       0
Bank Sta=4996.7,5001
XS Rating Curve= 0 ,0
Exp/Cntr=0.3,0.1

Type RM Length L Ch R = 1 ,120127  ,453,453,453
BEGIN DESCRIPTION:
CLEAR FORK SANDIES CREEK 153.0
END DESCRIPTION:
XS GIS Cut Line= 3
      2326775.01       13682075.        2326375.       13682075.
      2325975.02     13681875.01
#Sta/Elev= 30
  4599.6  484.44  4679.6   479.1  4773.2  473.95  4809.6  472.01  4909.6  467.79
  4919.6  467.67  4949.6  468.54  4979.6  468.48    4995  464.03  4995.3  463.53
    4999  463.53  4999.3  464.03  5002.4  464.03    5008  467.27  5013.6  468.08
    5022  468.41  5044.3  468.03  5080.7  468.12  5142.2   469.6  5170.1   469.5
  5192.5  470.02  5214.8  471.09  5231.6  472.75  5245.6  473.07    5321  477.13
  5357.4  478.39  5371.4  479.53  5393.7  479.82  5424.5  481.67  5446.8  481.92
#Mann= 4 ,-1 , 0
  4599.6     .05       0  4773.2     .07       0    4995     .05       0
  4999.3     .07       0
Bank Sta=4995,4999.3
XS Rating Curve= 0 ,0
Exp/Cntr=0.3,0.1

Type RM Length L Ch R = 1 ,119674  ,476,476,476
BEGIN DESCRIPTION:
CLEAR FORK SANDIES CREEK 152.0
END DESCRIPTION:
XS GIS Cut Line= 3
      2326825.02     13681875.01        2326525.       13681675.
      2325855.96     13681484.54
#Sta/Elev= 30
  4639.4  485.59  4812.2  475.25  4860.1  471.32  4963.9  467.18  4977.4  466.15
  4994.8  463.55  4995.1  463.05  4998.9  463.05  4999.1  463.55  5002.6  463.55
  5010.4  464.98  5024.9  464.88  5050.8  465.86  5062.4  467.21    5104  466.63
  5146.7  467.36  5167.9  467.83  5201.8  469.93  5218.3  471.77  5235.7  475.46
  5269.5  477.95  5353.5  477.32  5381.5  477.85  5386.7  477.46  5395.1   475.8
  5405.5  478.13  5436.7  478.04  5532.5  480.82  5639.3  484.58  5695.6  487.65
#Mann= 6 ,-1 , 0
  4639.4     .05       0  4860.1     .07       0  4994.8     .05       0
  4999.1     .07       0  5024.9     .12       0  5146.7     .07       0
Bank Sta=4994.8,4999.1
XS Rating Curve= 0 ,0
Exp/Cntr=0.3,0.1

Type RM Length L Ch R = 1 ,119198  ,418,418,418
BEGIN DESCRIPTION:
CLEAR FORK SANDIES CREEK 151.0
END DESCRIPTION:
XS GIS Cut Line= 3
      2326825.01     13681625.03        2326675.       13681275.
        2326325.       13680975.
#Sta/Elev= 30
  4614.3   477.9  4635.5  476.66  4668.7  475.59    4676  474.29  4757.6  468.37
  4799.3  468.15  4822.1  467.32  4886.3  465.73  4904.5  465.87    4919  467.61
  4940.7  467.15  4980.6   464.4  4986.3  462.76  4992.4     461  4998.4     461
  5000.1  459.25  5000.4  458.75  5004.2  458.75  5004.5  459.25  5023.1  461.21
  5030.8  463.82  5037.4  465.03  5059.3  463.65    5113  464.26  5153.7  464.61
  5242.3  467.87  5321.6  471.62  5342.5  473.73  5356.8  473.34  5456.1  477.37
#Mann= 9 ,-1 , 0
  4614.3     .07       0  4635.5     .12       0  4822.1     .07       0
  4986.3     .12       0  5000.1     .05       0  5004.5     .12       0
    5113     .07       0  5153.7     .12       0  5242.3     .07       0
Bank Sta=5000.1,5004.5
XS Rating Curve= 0 ,0
Exp/Cntr=0.3,0.1

Type RM Length L Ch R = 1 ,118780  ,444,444,444
BEGIN DESCRIPTION:
CLEAR FORK SANDIES CREEK 150.0
END DESCRIPTION:
XS GIS Cut Line= 3
      2327224.99       13681075.        2326875.       13680925.
      2326524.97     13680574.97
#Sta/Elev= 30
    4619  474.91  4640.7  474.27  4814.8  464.08  4838.4  463.17  4869.2  462.41
  4880.1  462.81  4923.6  462.96    4937  463.49  4967.1  463.24  4985.3  461.71
  4990.7  459.46  4994.8  458.64  4995.1  458.14    4999  458.14  4999.3  458.64
  5013.9  459.33  5028.1  461.34  5035.1  461.51  5042.2  462.52  5056.3   463.4
  5098.8  463.71  5112.9  464.55  5155.3  464.57  5254.3  469.16  5268.5  470.17
  5367.5   474.4  5381.6   475.4  5452.3  478.71  5467.8  478.95  5494.8  479.94
#Mann= 5 ,-1 , 0
    4619     .12       0    4937     .07       0  4994.8     .05       0
  4999.3     .07       0  5467.8     .12       0
Bank Sta=4994.8,4999.3
XS Rating Curve= 0 ,0
Exp/Cntr=0.3,0.1

Type RM Length L Ch R = 1 ,118336  ,470,470,470
BEGIN DESCRIPTION:
CLEAR FORK SANDIES CREEK 149.0
END DESCRIPTION:
XS GIS Cut Line= 3
        2327325.       13680875.        2327175.       13680625.
      2326575.03       13680525.
#Sta/Elev= 30
  4708.5  472.27  4838.7  468.43  4860.1  467.56  4918.4     463  4965.1  461.35
  4976.7  461.61  4992.3  459.95  4997.1  457.92  5002.6  457.92  5007.9  456.11
  5008.2  455.61  5012.5  456.11  5020.3  456.46    5033  460.34  5040.6  461.46
  5050.7  461.79  5093.8  460.59  5101.4  461.29  5111.6  460.61  5149.6  462.12
  5172.4  461.05    5223  461.74  5253.5  462.49  5283.9  464.74  5337.1  467.04
  5344.7  468.53  5392.9  469.88  5527.2  476.88  5571.9  477.89  5608.3  479.79
#Mann= 5 ,-1 , 0
  4708.5     .12       0  5007.9     .05       0  5012.5     .12       0
    5223     .07       0  5571.9     .12       0
Bank Sta=5007.9,5012.5
XS Rating Curve= 0 ,0
Exp/Cntr=0.3,0.1

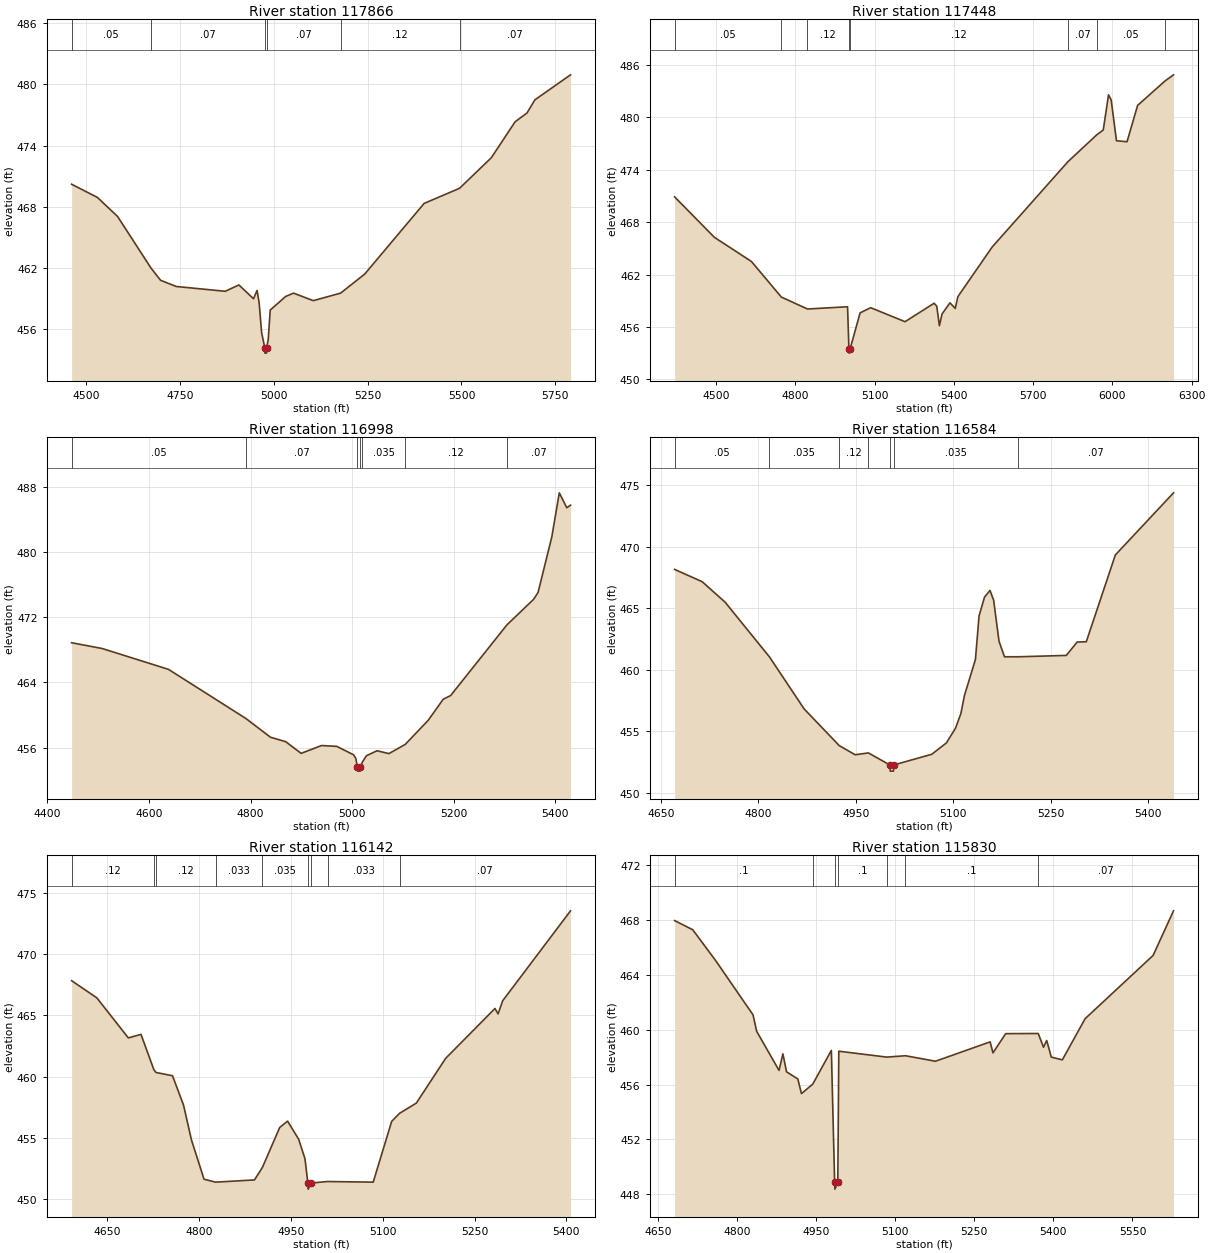
Type RM Length L Ch R = 1 ,117866  ,418,418,418
BEGIN DESCRIPTION:
CLEAR FORK SANDIES CREEK 148.0
END DESCRIPTION:
XS GIS Cut Line= 3
      2327474.99     13680724.98        2327275.       13680225.
      2326524.97     13680475.01
#Sta/Elev= 30
  4461.5  470.21  4530.1  468.92    4584  467.05  4672.7  462.01  4698.4   460.8
  4740.2  460.19  4870.8  459.72  4907.1  460.34  4946.1  458.99  4955.6   459.8
    4961  458.61  4967.7  455.67  4976.2  454.16  4976.5  453.66  4980.4  453.66
  4980.8  454.16  4985.2  454.96  4990.6  457.88  5031.6  459.21  5052.7  459.54
  5105.4   458.8  5178.1  459.54  5242.4  461.41  5400.6  468.33  5494.9  469.81
  5579.7  472.81    5643  476.33  5674.6  477.19  5695.7  478.48  5790.6  480.93
#Mann= 6 ,-1 , 0
  4461.5     .05       0  4672.7     .07       0  4976.2     .05       0
  4980.8     .07       0  5178.1     .12       0  5494.9     .07       0
Bank Sta=4976.2,4980.8
XS Rating Curve= 0 ,0
Exp/Cntr=0.3,0.1

Type RM Length L Ch R = 1 ,117448  ,450,450,450
BEGIN DESCRIPTION:
CLEAR FORK SANDIES CREEK 147.0
END DESCRIPTION:
XS GIS Cut Line= 3
        2327625.     13680724.96        2327575.       13680075.
      2327574.69     13678839.08
#Sta/Elev= 30
  4343.6   470.9    4494  466.27  4634.4   463.5  4747.4  459.43  4846.4  458.06
    4998  458.32  5003.2  453.51  5003.5  453.01  5007.8  453.51  5045.5  457.62
  5085.5  458.21  5215.5  456.61  5325.5  458.72  5335.5  458.39  5345.5  456.15
  5355.5  457.49  5385.5  458.77  5405.5  458.13  5415.5  459.48  5545.5  465.17
    5832  474.93  5940.9     478  5965.5  478.55  5985.5  482.58  5995.5     482
  6015.5  477.32  6055.5  477.21  6095.5  481.37    6199  484.16  6231.4  484.87
#Mann= 8 ,-1 , 0
  4343.6     .05       0  4747.4     .07       0  4846.4     .12       0
  5003.2     .05       0  5007.8     .12       0    5832     .07       0
  5940.9     .05       0    6199     .07       0
Bank Sta=5003.2,5007.8
XS Rating Curve= 0 ,0
Exp/Cntr=0.3,0.1

Type RM Length L Ch R = 1 ,116998  ,414,414,414
BEGIN DESCRIPTION:
CLEAR FORK SANDIES CREEK 146.0
END DESCRIPTION:
XS GIS Cut Line= 3
        2327925.       13680675.        2327975.       13680125.
      2328225.01     13679774.98
#Sta/Elev= 30
  4447.5  468.87  4507.7  468.16  4638.3   465.6  4790.9  459.56  4839.1  457.27
  4869.2  456.72  4899.4  455.29  4939.5  456.25  4969.6  456.15  5002.8  455.11
  5007.1  454.66  5010.3  453.61  5010.8  453.11  5015.7  453.11  5016.2  453.61
  5019.5  454.16    5028     455  5048.9  455.61  5072.3  455.26  5104.4  456.39
  5149.7  459.35  5179.2  461.93  5193.9  462.39  5304.6  471.06  5357.4  474.21
    5366  475.05    5393  481.85  5407.8  487.27  5422.5  485.44  5429.9  485.75
#Mann= 7 ,-1 , 0
  4447.5     .05       0  4790.9     .07       0  5010.3     .05       0
  5016.2     .07       0  5019.5    .035       0  5104.4     .12       0
  5304.6     .07       0
Bank Sta=5010.3,5016.2
XS Rating Curve= 0 ,0
Exp/Cntr=0.3,0.1

Type RM Length L Ch R = 1 ,116584  ,442,442,442
BEGIN DESCRIPTION:
CLEAR FORK SANDIES CREEK 145.0
END DESCRIPTION:
XS GIS Cut Line= 3
        2327975.       13680625.        2328225.       13680425.
      2328425.01     13680024.97
#Sta/Elev= 30
  4671.3  468.17  4713.7  467.17  4748.9  465.51  4817.2  461.06  4870.6  456.83
  4924.6  453.85    4949  453.11  4969.3  453.26  5002.5  452.28    5003  451.78
  5007.9  451.78  5008.4  452.28  5066.9  453.15  5089.3  454.07  5103.3  455.26
  5111.6  456.45  5117.2  457.94    5134  460.85  5139.6  464.39    5148  465.92
  5156.4  466.46    5162  465.67  5170.3  462.33  5178.7  461.07  5200.1  461.07
  5273.8  461.18  5290.5  462.27  5304.5  462.29  5349.2  469.34  5438.7  474.39
#Mann= 7 ,-1 , 0
  4671.3     .05       0  4817.2    .035       0  4924.6     .12       0
  4969.3    .035       0  5002.5    .035       0  5008.4    .035       0
  5200.1     .07       0
Bank Sta=5002.5,5008.4
XS Rating Curve= 0 ,0
Exp/Cntr=0.3,0.1

Type RM Length L Ch R = 1 ,116142  ,312,312,312
BEGIN DESCRIPTION:
CLEAR FORK SANDIES CREEK 144.0
END DESCRIPTION:
XS GIS Cut Line= 3
      2328525.01     13680874.97        2328625.       13680475.
        2328575.       13680075.
#Sta/Elev= 30
  4591.5  467.83  4632.7  466.43  4684.2  463.16  4704.9  463.45  4725.9  460.57
  4729.4  460.34  4756.4  460.07  4774.4  457.68  4787.3  454.85  4807.9  451.63
  4826.7  451.39  4890.4  451.57  4903.4   452.6  4931.6  455.85  4944.5  456.37
  4962.6  454.89  4972.9   453.3  4977.6  451.32  4978.1  450.82  4983.5  451.32
  5009.8  451.44  5084.4  451.39  5114.6  456.35  5127.6  457.01  5154.9  457.84
  5202.8  461.49  5283.4  465.56  5288.5  465.12    5296  466.19  5406.9  473.53
#Mann= 9 ,-1 , 0
  4591.5     .12       0  4725.9    .035       0  4729.4     .12       0
  4826.7    .033       0  4903.4    .035       0  4977.6    .035       0
  4983.5    .035       0  5009.8    .033       0  5127.6     .07       0
Bank Sta=4977.6,4983.5
XS Rating Curve= 0 ,0
Exp/Cntr=0.3,0.1

Type RM Length L Ch R = 1 ,115830  ,588,588,588
BEGIN DESCRIPTION:
CLEAR FORK SANDIES CREEK 143.0
END DESCRIPTION:
XS GIS Cut Line= 6
      2328574.99     13680925.01      2328810.74     13680683.63
      2328851.94      13680587.5      2328854.05     13680490.32
      2328817.64     13680401.35      2328637.51      13680148.5
#Sta/Elev= 30
  4681.9  467.95  4716.3  467.28  4759.8  465.03  4830.6  461.08  4837.5  459.88
  4879.9  457.03  4887.2  458.24  4894.1  456.93  4915.5  456.41  4922.4  455.34
  4943.8  456.03  4979.1  458.49  4985.3  448.88  4985.8  448.38  4991.3  448.88
  4993.2  458.43  5084.3     458  5119.6   458.1  5176.5   457.7  5280.1  459.11
  5285.5  458.31  5309.6  459.71  5371.3  459.72  5381.3  458.72  5387.4  459.21
  5396.1     458    5417   457.8  5460.2   460.8  5589.1  465.41  5627.8  468.66
#Mann= 7 ,-1 , 0
  4681.9      .1       0  4943.8      .1       0  4985.3     .05       0
  4991.3      .1       0  5084.3      .1       0  5119.6      .1       0
  5371.3     .07       0
Bank Sta=4985.3,4991.3
XS Rating Curve= 0 ,0
Exp/Cntr=0.3,0.1

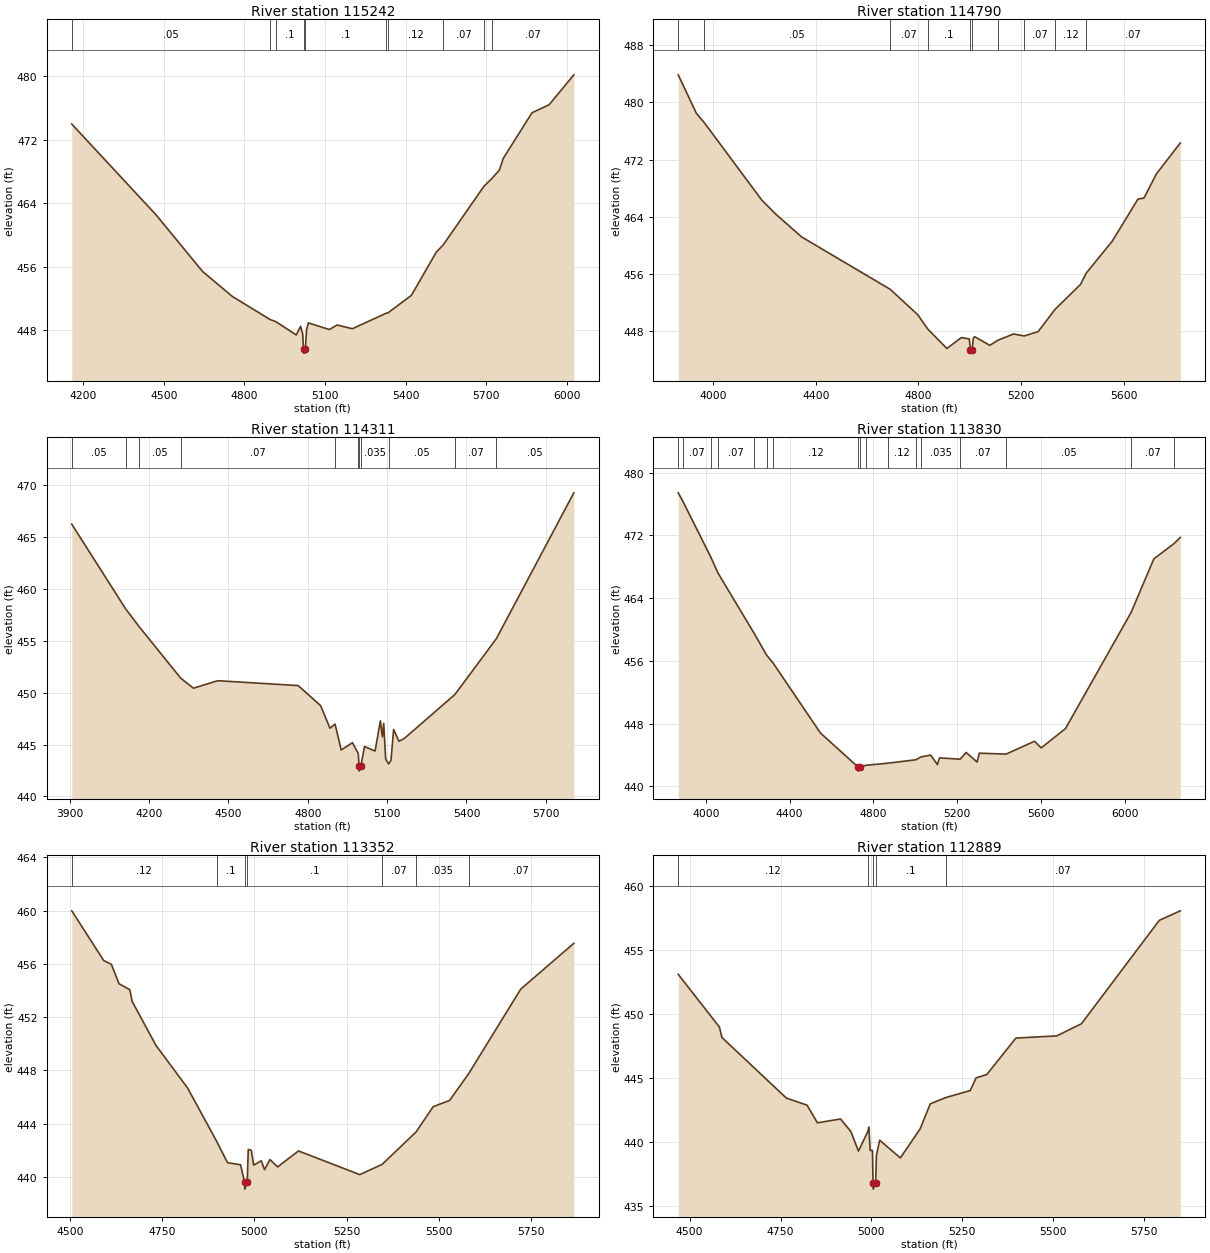
Type RM Length L Ch R = 1 ,115242  ,452,452,452
BEGIN DESCRIPTION:
CLEAR FORK SANDIES CREEK 142.0
END DESCRIPTION:
XS GIS Cut Line= 3
        2329575.     13681375.01        2329325.       13680575.
      2328525.03     13679925.03
#Sta/Elev= 30
  4157.4  473.97  4471.2  462.54  4644.1  455.42  4754.6  452.28  4896.6  449.34
  4916.8   449.1  4992.9  447.42  5009.2   448.5  5017.1  447.53  5020.2  445.63
  5020.7  445.13  5026.4  445.13  5026.9  445.63  5031.5  448.12  5037.9  448.94
  5116.2   448.1    5145  448.67  5201.7   448.2  5327.6  450.15  5334.8  450.21
  5421.5   452.4  5514.2  457.84  5539.7  458.74  5691.8  466.14  5722.1  467.15
  5749.1  468.18  5763.4  469.64  5870.5  475.39  5934.4  476.41  6026.3  480.17
#Mann= 10 ,-1 , 0
  4157.4     .05       0  4896.6     .07       0  4916.8      .1       0
  5020.2     .05       0  5026.9      .1       0  5327.6    .035       0
  5334.8     .12       0  5539.7     .07       0  5691.8     .12       0
  5722.1     .07       0
Bank Sta=5020.2,5026.9
XS Rating Curve= 0 ,0
Exp/Cntr=0.3,0.1

Type RM Length L Ch R = 1 ,114790  ,479,479,479
BEGIN DESCRIPTION:
CLEAR FORK SANDIES CREEK 141.0
END DESCRIPTION:
XS GIS Cut Line= 3
        2330275.       13680975.        2329475.       13680175.
        2328675.       13679975.
#Sta/Elev= 30
    3864  483.85  3934.7  478.47  3965.2  477.18  4189.3  466.35  4245.8  464.32
  4344.8  461.19  4689.8  453.87  4797.4  450.31  4836.3  448.31  4910.5   445.6
  4967.1  447.12    4998  446.93  5002.3  445.45  5002.8  444.95  5009.1  445.45
  5013.4  447.01  5018.6  447.25  5077.8  446.04  5110.5  446.77  5170.6  447.63
  5211.3  447.35    5266  447.95  5332.4  451.08  5430.9  454.54  5453.6  456.14
  5554.6  460.59  5655.1  466.49  5678.3  466.62  5727.2  470.02    5820  474.33
#Mann= 10 ,-1 , 0
    3864    .035       0  3965.2     .05       0  4689.8     .07       0
  4836.3      .1       0  5002.3     .05       0  5009.1      .1       0
  5110.5    .035       0  5211.3     .07       0  5332.4     .12       0
  5453.6     .07       0
Bank Sta=5002.3,5009.1
XS Rating Curve= 0 ,0
Exp/Cntr=0.3,0.1

Type RM Length L Ch R = 1 ,114311  ,481,481,481
BEGIN DESCRIPTION:
CLEAR FORK SANDIES CREEK 140.0
END DESCRIPTION:
XS GIS Cut Line= 3
      2330325.03     13680525.04        2329575.       13679725.
        2328775.       13679775.
#Sta/Elev= 30
  3907.8  466.26    4111  458.11  4161.4  456.41    4320   451.4  4367.7  450.44
  4459.6  451.16  4763.9  450.69  4848.9  448.75    4884  446.58  4903.2  446.98
  4926.5  444.48    4969  445.18  4991.1  444.13  4993.9  442.94  4994.4  442.44
  5000.8  442.94  5014.5  444.81  5054.5  444.38  5074.6  447.29  5082.1  445.75
  5087.1  447.04  5094.6  443.61  5105.7  443.13  5114.6  443.47  5124.7  446.46
  5144.7  445.32  5164.7  445.58  5356.3  449.83  5512.7   455.2    5806  469.28
#Mann= 11 ,-1 , 0
  3907.8     .05       0    4111    .035       0  4161.4     .05       0
    4320     .07       0  4903.2      .1       0  4991.1    .035       0
  4993.9    .035       0  5000.8    .035       0  5105.7     .05       0
  5356.3     .07       0  5512.7     .05       0
Bank Sta=4993.9,5000.8
XS Rating Curve= 0 ,0
Exp/Cntr=0.3,0.1

Type RM Length L Ch R = 1 ,113830  ,478,478,478
BEGIN DESCRIPTION:
CLEAR FORK SANDIES CREEK 139.0
END DESCRIPTION:
XS GIS Cut Line= 3
      2330774.98     13680324.98        2329975.       13679525.
      2328774.96     13679124.99
#Sta/Elev= 30
  3868.7  477.43    3890  476.39  4023.4  469.28  4057.5  467.25  4230.8  459.52
  4290.1  456.75  4321.1  455.74  4547.5   446.8  4727.9  442.44  4728.4  441.94
  4734.8  442.44  4763.5  442.68  4868.9  442.95  5003.1  443.39  5026.8  443.75
  5073.8  443.98  5105.5  442.78    5116  443.63  5214.1  443.46  5242.5  444.32
  5295.2   443.1  5305.7  444.23  5433.3  444.11  5569.3  445.75  5600.9   444.9
  5716.8  447.36  6030.5  462.19  6138.5     469    6236  470.98    6265  471.74
#Mann= 17 ,-1 , 0
  3868.7    .035       0    3890     .07       0  4023.4     .05       0
  4057.5     .07       0  4230.8    .035       0  4290.1     .07       0
  4321.1     .12       0  4727.9     .05       0  4734.8     .12       0
  4763.5      .1       0  4868.9     .12       0  5003.1     .07       0
  5026.8    .035       0  5214.1     .07       0  5433.3     .05       0
  6030.5     .07       0    6236     .05       0
Bank Sta=4727.9,4734.8
XS Rating Curve= 0 ,0
Exp/Cntr=0.3,0.1

Type RM Length L Ch R = 1 ,113352  ,463,463,463
BEGIN DESCRIPTION:
CLEAR FORK SANDIES CREEK 138.0
END DESCRIPTION:
XS GIS Cut Line= 3
        2330725.       13679575.        2330325.       13679275.
      2329825.02     13678575.02
#Sta/Elev= 30
  4505.4  459.98  4591.9  456.25  4612.7  455.96  4633.5   454.5  4662.7  454.05
  4668.9  453.18  4733.5  449.87  4818.9  446.68  4897.6  442.68  4927.3  441.06
  4962.7   440.9  4973.7  439.57  4974.2  439.07  4980.8  439.57  4983.5  442.05
  4991.9  441.99  4998.1  440.87  5018.9   441.2  5027.5  440.53  5042.3  441.29
  5063.2  440.74  5119.7  441.94  5285.6  440.16  5346.3  440.93  5438.3  443.37
  5484.7  445.27  5528.9  445.73  5580.8  447.75  5721.8   454.1  5865.6  457.54
#Mann= 7 ,-1 , 0
  4505.4     .12       0  4897.6      .1       0  4973.7     .05       0
  4980.8      .1       0  5346.3     .07       0  5438.3    .035       0
  5580.8     .07       0
Bank Sta=4973.7,4980.8
XS Rating Curve= 0 ,0
Exp/Cntr=0.3,0.1

Type RM Length L Ch R = 1 ,112889  ,446,446,446
BEGIN DESCRIPTION:
CLEAR FORK SANDIES CREEK 137.0
END DESCRIPTION:
XS GIS Cut Line= 3
      2330925.01     13679325.01        2330575.       13678925.
      2329825.02     13678525.01
#Sta/Elev= 30
  4468.5  453.13  4581.9  449.01  4588.6   448.2  4766.1  443.46    4823  442.91
  4851.5  441.53  4915.1  441.83  4943.5  440.85  4964.4  439.32  4990.5  440.87
  4992.9   441.2  4996.7  439.37  5002.9  439.37  5004.5  436.85    5005  436.35
  5011.8  436.85  5013.8  438.99  5022.7  440.17  5079.7  438.79  5134.2  441.06
  5161.9  443.01  5204.4   443.5    5272  444.05    5288  445.04  5317.4   445.3
  5397.7  448.15    5510  448.32    5578  449.27  5792.3  457.35    5850  458.09
#Mann= 5 ,-1 , 0
  4468.5     .12       0  4990.5      .1       0  5004.5     .05       0
  5011.8      .1       0  5204.4     .07       0
Bank Sta=5004.5,5011.8
XS Rating Curve= 0 ,0
Exp/Cntr=0.3,0.1

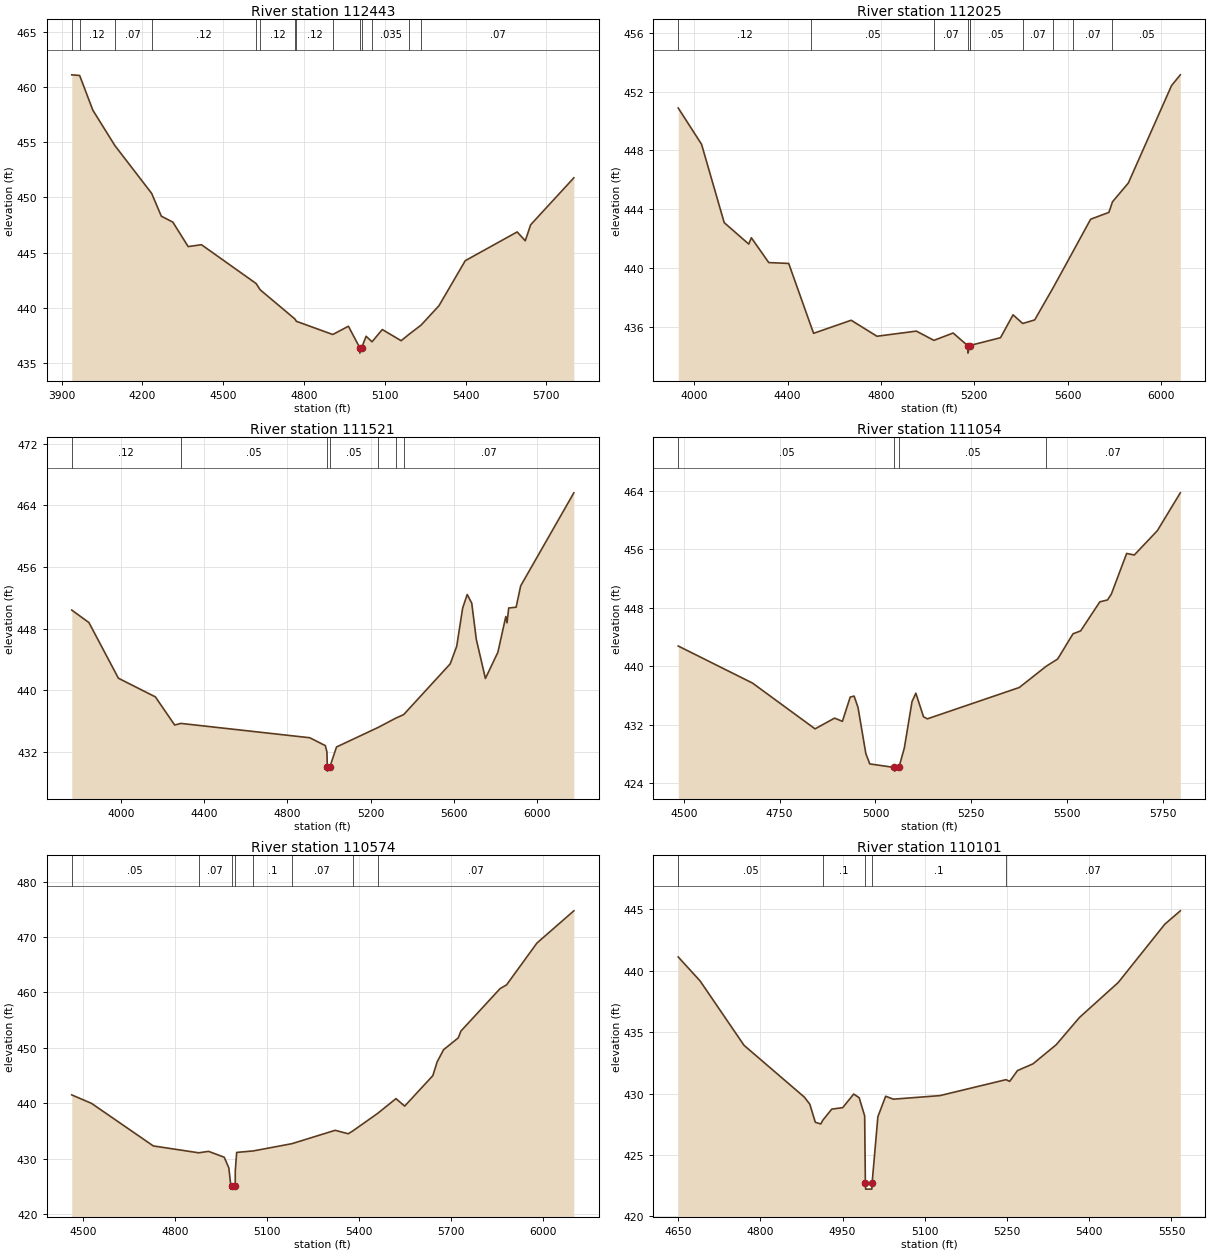
Type RM Length L Ch R = 1 ,112443  ,418,418,418
BEGIN DESCRIPTION:
CLEAR FORK SANDIES CREEK 136.0
END DESCRIPTION:
XS GIS Cut Line= 3
      2331524.99     13679374.98        2330825.       13678575.
      2330024.95       13678525.
#Sta/Elev= 30
  3937.5  461.13  3966.8  461.07  4015.8  457.92  4097.6  454.71  4234.2  450.37
  4270.1   448.3  4312.9  447.76  4369.8  445.54  4419.2  445.71  4622.1  442.19
  4637.1  441.62  4766.7  438.96  4771.4  438.76  4906.8  437.56  4964.9  438.31
  5006.9  436.37  5007.4  435.87  5014.2  436.37  5030.6   437.4  5052.6   436.9
  5090.7  438.01  5160.8     437  5189.6  437.57  5235.1  438.42  5301.1  440.17
  5398.8  444.26  5591.6  446.87  5621.7  446.07  5641.7  447.52  5802.1  451.78
#Mann= 14 ,-1 , 0
  3937.5     .07       0  3966.8     .12       0  4097.6     .07       0
  4234.2     .12       0  4622.1     .07       0  4637.1     .12       0
  4766.7     .07       0  4771.4     .12       0  4906.8     .05       0
  5006.9     .05       0  5014.2     .05       0  5052.6    .035       0
  5189.6      .1       0  5235.1     .07       0
Bank Sta=5006.9,5014.2
XS Rating Curve= 0 ,0
Exp/Cntr=0.3,0.1

Type RM Length L Ch R = 1 ,112025  ,504,504,504
BEGIN DESCRIPTION:
X18505
END DESCRIPTION:
XS GIS Cut Line= 4
      2331357.31     13679118.59       2331040.9     13678270.04
      2330616.61     13678104.64      2329848.58     13678291.26
#Sta/Elev= 30
  3931.8  450.89  4031.7  448.42  4128.8  443.08    4234  441.62  4245.1  442.05
  4319.7  440.36  4405.2   440.3  4500.3  436.05    4512  435.54  4672.8  436.43
  4783.4  435.34  4952.1  435.69  5027.4  435.06  5109.8  435.56  5172.8  434.69
  5173.3  434.19  5180.1  434.69  5181.4  434.71  5312.7  435.24  5366.5   436.8
  5407.7  436.21  5459.1  436.45  5539.5  438.68  5622.6  441.09  5698.8  443.31
  5777.2  443.78  5792.6   444.5  5860.5  445.78  6045.7  452.42  6083.2  453.15
#Mann= 10 ,-1 , 0
  3931.8     .12       0  4500.3     .05       0  5027.4     .07       0
  5172.8     .05       0  5180.1     .07       0  5181.4     .05       0
  5407.7     .07       0  5539.5     .05       0  5622.6     .07       0
  5792.6     .05       0
Bank Sta=5172.8,5180.1
XS Rating Curve= 0 ,0
Exp/Cntr=0.3,0.1

Type RM Length L Ch R = 1 ,111521  ,467,467,467
BEGIN DESCRIPTION:
CLEAR FORK SANDIES CREEK 135.0
END DESCRIPTION:
XS GIS Cut Line= 3
        2331375.     13679075.01        2331075.       13677875.
      2330516.22     13676839.49
#Sta/Elev= 30
  3763.4  450.42  3845.9   448.8  3987.6  441.58  4165.4  439.16  4258.2  435.51
  4287.7  435.72  4907.6  433.86  4982.3  432.84    4990  432.02    4992  430.03
  4992.5  429.53  5003.5  430.03    5036  432.66  5235.6  435.19  5321.5  436.41
  5358.9  436.86  5582.5  443.44  5613.9  445.72  5642.5  450.68  5664.4  452.44
  5686.3  451.31  5708.1  446.63  5751.9  441.55  5811.9  444.95    5850  449.59
  5855.7  448.77  5863.9  450.69  5899.5  450.79  5921.4  453.56    6177  465.63
#Mann= 7 ,-1 , 0
  3763.4     .12       0  4287.7     .05       0    4992     .05       0
  5003.5     .05       0  5235.6     .07       0  5321.5     .05       0
  5358.9     .07       0
Bank Sta=4992,5003.5
XS Rating Curve= 0 ,0
Exp/Cntr=0.3,0.1

Type RM Length L Ch R = 1 ,111054  ,480,480,480
BEGIN DESCRIPTION:
CLEAR FORK SANDIES CREEK 134.0
END DESCRIPTION:
XS GIS Cut Line= 3
      2331625.01     13678325.03        2331525.       13677825.
        2331525.     13677025.03
#Sta/Elev= 30
  4485.5   442.8  4679.3  437.73  4842.5  431.47  4893.4  432.94  4913.8   432.5
  4934.2  435.82  4944.4  435.95  4954.6  434.39    4975  428.08  4985.2  426.68
  5049.6  426.19  5050.1  425.69  5061.2  426.19  5075.4  428.86  5095.4  435.19
  5105.4  436.35  5125.4  433.13  5135.4  432.84  5375.4  437.13  5445.7  440.04
  5475.4  441.02  5515.4  444.47  5535.4  444.87  5585.4  448.84  5605.4   449.1
  5615.4  449.89  5655.4  455.46  5675.4  455.25  5735.4  458.57  5795.4  463.75
#Mann= 4 ,-1 , 0
  4485.5     .05       0  5049.6     .05       0  5061.2     .05       0
  5445.7     .07       0
Bank Sta=5049.6,5061.2
XS Rating Curve= 0 ,0
Exp/Cntr=0.3,0.1

Type RM Length L Ch R = 1 ,110574  ,473,473,473
BEGIN DESCRIPTION:
CLEAR FORK SANDIES CREEK 133.0
END DESCRIPTION:
XS GIS Cut Line= 3
      2331675.02     13678274.97        2331975.       13677825.
      2332725.01     13677024.99
#Sta/Elev= 30
  4463.4  441.48    4528  439.95  4729.3  432.27  4877.3  431.03  4909.6  431.29
  4960.6  430.23  4975.7   428.3  4981.7   425.3  4984.8  424.97  4985.3  424.47
  4996.5  424.97  4996.7  427.83  5001.2   431.1  5055.7  431.37  5180.9  432.67
  5322.4  435.09  5364.9  434.47  5379.3  434.95  5461.8  438.18  5520.7  440.81
  5549.1  439.46  5640.9  444.96  5655.1  447.46  5676.1  449.65  5723.8  451.78
  5732.7  453.02  5860.2  460.67  5881.5  461.36  5980.4   468.9  6100.8  474.72
#Mann= 8 ,-1 , 0
  4463.4     .05       0  4877.3     .07       0  4984.8     .05       0
  4996.5     .07       0  5055.7      .1       0  5180.9     .07       0
  5379.3      .1       0  5461.8     .07       0
Bank Sta=4984.8,4996.5
XS Rating Curve= 0 ,0
Exp/Cntr=0.3,0.1

Type RM Length L Ch R = 1 ,110101  ,438,438,438
BEGIN DESCRIPTION:
CLEAR FORK SANDIES CREEK 132.0
END DESCRIPTION:
XS GIS Cut Line= 3
        2332375.     13678374.97        2332375.       13678025.
      2332775.03     13677624.97
#Sta/Elev= 30
  4650.4  441.13  4690.4  439.17  4770.4  433.93  4880.4  429.71  4890.4  429.13
  4900.4  427.66  4910.4  427.52    4914  427.82  4930.4  428.73  4950.4  428.85
  4970.4  429.96  4980.4  429.66  4990.4  428.18  4991.7  422.71  4992.2  422.21
  5003.5  422.21    5004  422.71  5014.5  428.11  5028.7  429.78  5042.8  429.54
  5127.6  429.83  5248.1  431.13  5254.9  430.99  5269.1  431.87  5297.4  432.42
  5339.8  433.98  5382.2   436.2  5452.9  439.05  5537.8   443.8  5566.1  444.89
#Mann= 5 ,-1 , 0
  4650.4     .05       0    4914      .1       0  4991.7     .05       0
    5004      .1       0  5248.1     .07       0
Bank Sta=4991.7,5004
XS Rating Curve= 0 ,0
Exp/Cntr=0.3,0.1