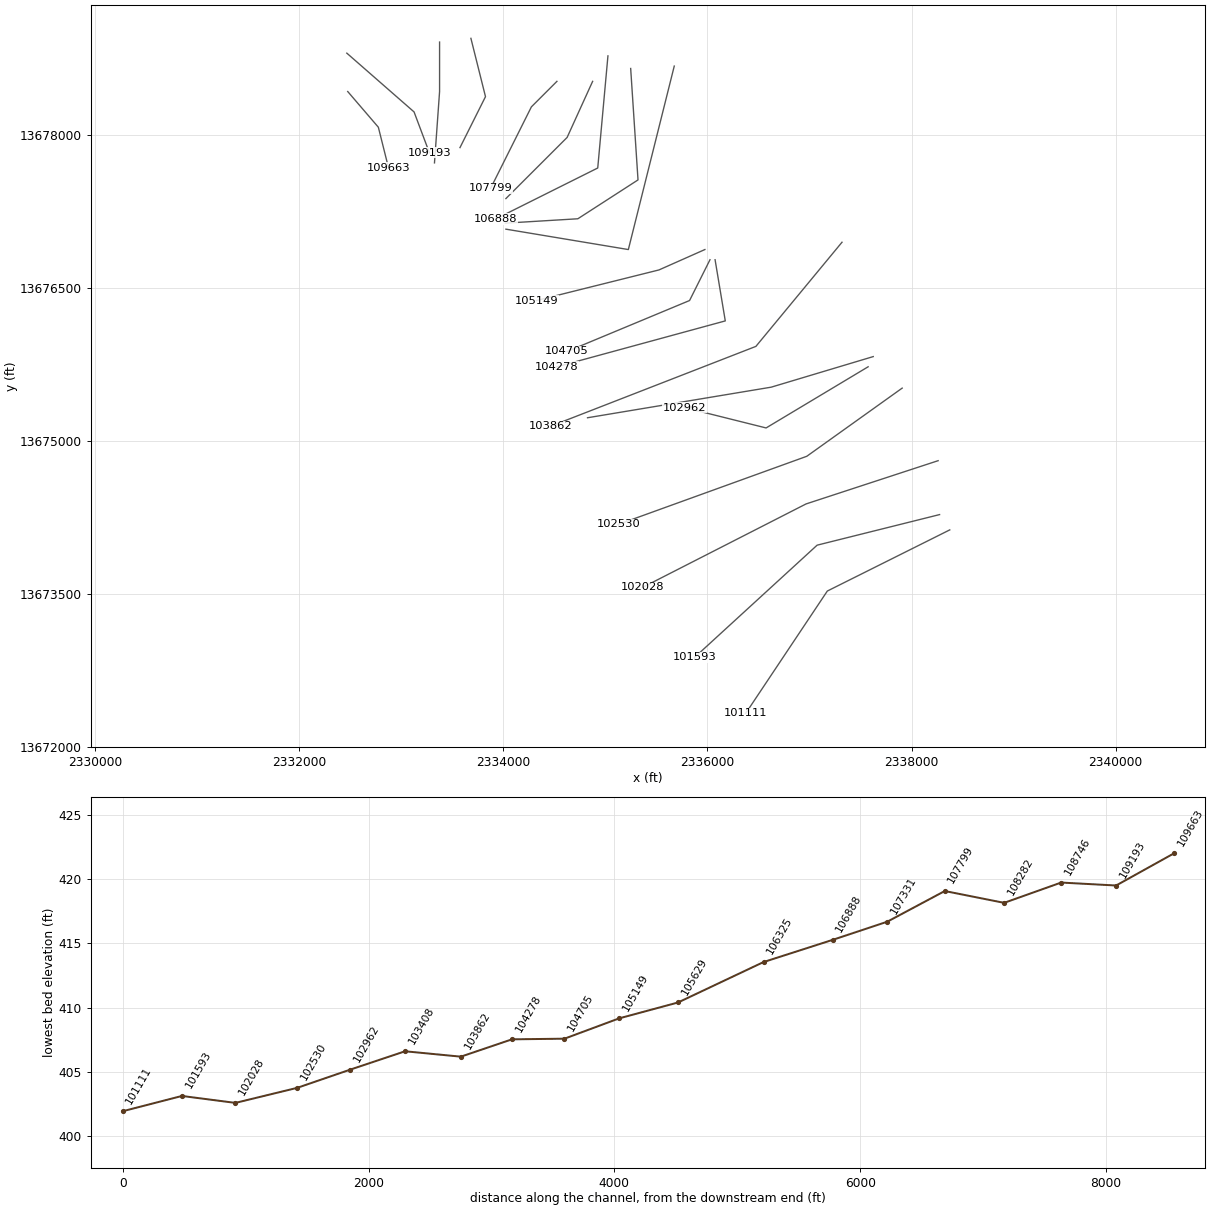
HEC-RAS study CLEAR FORK SANDIES CREEK.prj: CLEAR FORK SANDIES CREEK Base Level Engineering

--- CLEAR FORK SANDIES CREEK.g01 (geometry) --- (continued)

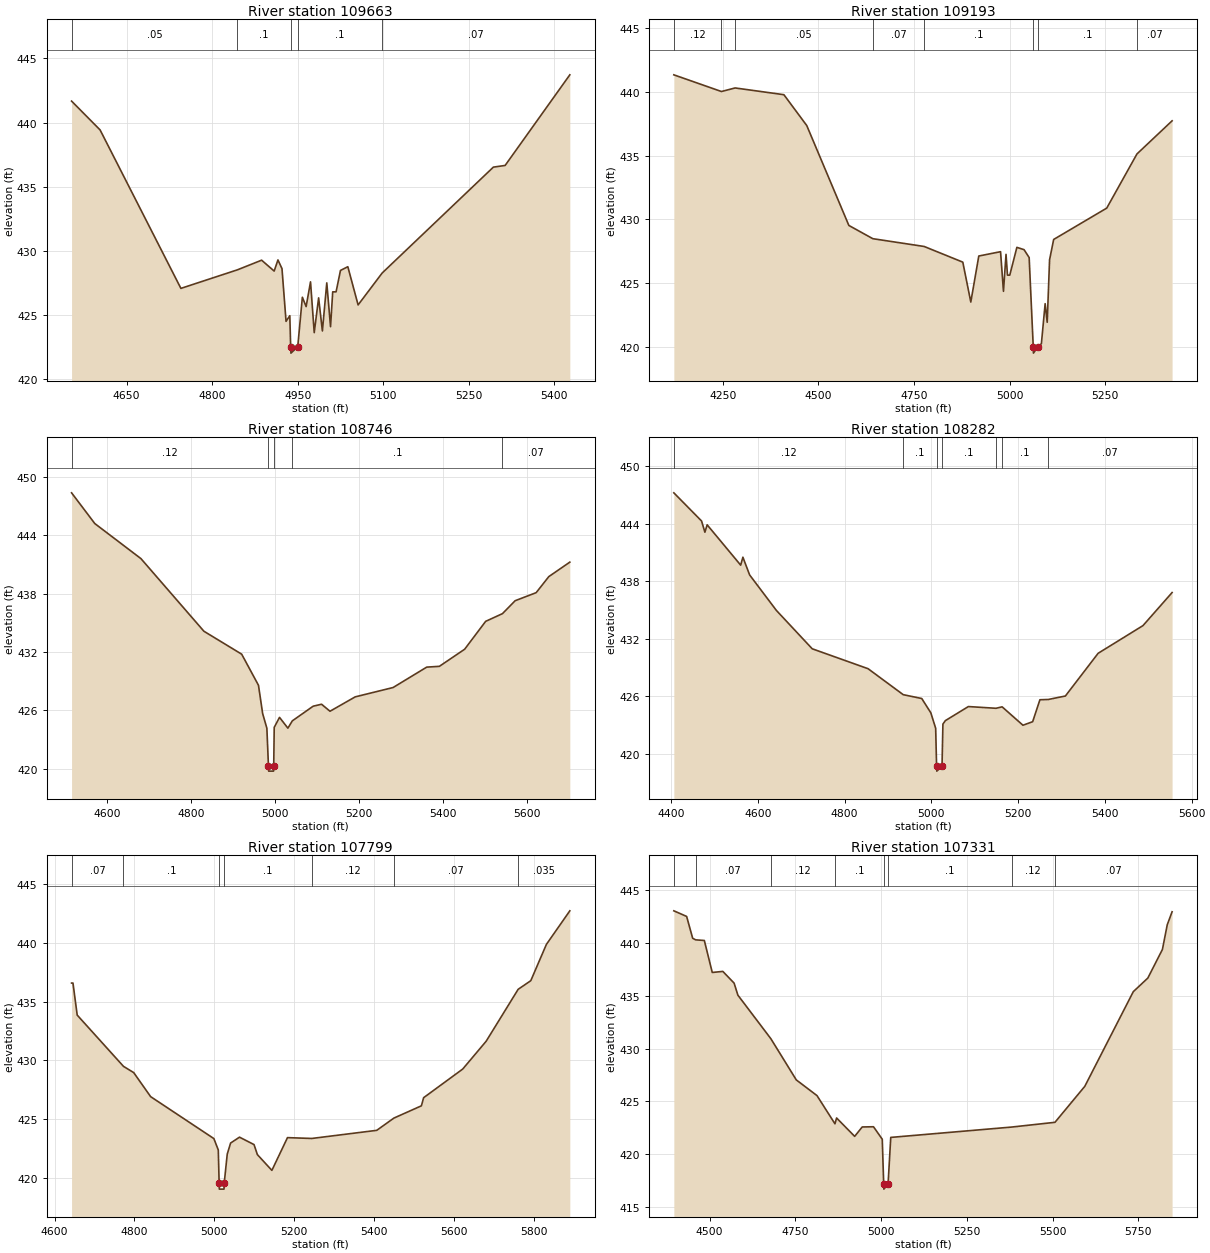
Type RM Length L Ch R = 1 ,109663  ,470,470,470
BEGIN DESCRIPTION:
CLEAR FORK SANDIES CREEK 131.0
END DESCRIPTION:
XS GIS Cut Line= 3
      2332474.98     13678425.02        2332775.       13678075.
        2332875.     13677675.02
#Sta/Elev= 30
  4553.7  441.67  4603.7  439.42  4745.3  427.06  4844.5  428.51  4886.8  429.26
  4908.8  428.41  4915.4  429.28  4922.5   428.6  4929.6  424.49  4936.2  424.93
  4937.7  422.51  4938.2  422.01  4950.1  422.51  4958.2  426.37  4964.8  425.64
  4972.5  427.57    4979  423.61  4986.7  426.32  4993.3  423.74    5001  427.49
  5007.6  424.07  5011.4  426.79  5017.3  426.79    5025  428.46  5037.9  428.75
  5055.9  425.77  5098.1  428.26    5293  436.52  5313.6  436.65    5427  443.72
#Mann= 5 ,-1 , 0
  4553.7     .05       0  4844.5      .1       0  4937.7     .05       0
  4950.1      .1       0  5098.1     .07       0
Bank Sta=4937.7,4950.1
XS Rating Curve= 0 ,0
Exp/Cntr=0.3,0.1

Type RM Length L Ch R = 1 ,109193  ,447,447,447
BEGIN DESCRIPTION:
CLEAR FORK SANDIES CREEK 130.0
END DESCRIPTION:
XS GIS Cut Line= 4
       2332465.9     13678801.71        2332725.       13678575.
        2333125.       13678225.        2333275.     13677824.99
#Sta/Elev= 30
  4121.9  441.35  4246.4  440.04  4282.2  440.32  4409.7  439.79  4469.5  437.37
  4579.6  429.53  4642.3  428.49  4776.5  427.88  4877.6  426.65  4898.5  423.52
  4919.4  427.13  4976.3  427.47  4983.9  424.36  4990.6  427.26  4994.4  425.63
  5000.4  425.63    5019  427.81  5037.7  427.63  5051.1  427.01  5061.8  420.01
  5062.3  419.51  5074.2  420.01  5083.1  420.25  5092.9  423.39  5098.3  421.93
  5104.5  426.84  5115.2  428.43    5254  430.89    5333  435.14  5424.9  437.74
#Mann= 8 ,-1 , 0
  4121.9     .12       0  4246.4     .07       0  4282.2     .05       0
  4642.3     .07       0  4776.5      .1       0  5061.8     .05       0
  5074.2      .1       0    5333     .07       0
Bank Sta=5061.8,5074.2
XS Rating Curve= 0 ,0
Exp/Cntr=0.3,0.1

Type RM Length L Ch R = 1 ,108746  ,464,464,464
BEGIN DESCRIPTION:
CLEAR FORK SANDIES CREEK 129.0
END DESCRIPTION:
XS GIS Cut Line= 4
        2333375.     13678910.33        2333375.       13678625.
        2333375.       13678425.        2333325.     13677725.01
#Sta/Elev= 30
  4514.7  448.37    4570  445.21    4680   441.6    4830  434.13    4920  431.77
    4960  428.57    4970  425.65    4980  424.15  4983.8  420.24  4984.3  419.74
  4995.8  419.74  4996.3  420.24  4997.5  424.24  5010.1  425.27  5030.1  424.16
  5040.6  424.91  5090.3  426.42  5110.3  426.62  5130.4   425.9  5190.5  427.38
  5280.7  428.34  5360.9  430.44    5391  430.52  5451.2  432.28  5501.3  435.15
  5541.3  435.94  5571.5  437.27  5621.6   438.1  5651.7  439.75  5701.8  441.24
#Mann= 5 ,-1 , 0
  4514.7     .12       0  4983.8     .05       0  4996.3     .12       0
  5040.6      .1       0  5541.3     .07       0
Bank Sta=4983.8,4996.3
XS Rating Curve= 0 ,0
Exp/Cntr=0.3,0.1

Type RM Length L Ch R = 1 ,108282  ,483,483,483
BEGIN DESCRIPTION:
CLEAR FORK SANDIES CREEK 128.0
END DESCRIPTION:
XS GIS Cut Line= 4
      2333682.01     13678946.98        2333725.       13678775.
        2333825.       13678375.        2333575.       13677875.
#Sta/Elev= 30
  4406.3  447.21  4470.2  444.27  4477.9   443.1  4483.1  443.87  4560.4  439.66
  4565.5  440.49    4581  438.64  4642.8  434.93  4725.3  430.93  4854.1  428.85
  4935.1  426.14  4977.8  425.74  4998.7  424.25  5009.9  422.63    5012  418.66
  5012.5  418.16  5024.5  418.66  5026.6  423.07  5032.2  423.43  5085.3   424.9
    5149  424.72  5163.1  424.87  5211.1  422.95  5233.5  423.32  5250.2  425.61
  5269.5  425.64  5308.9     426  5384.4  430.46  5487.8  433.35  5554.9   436.8
#Mann= 7 ,-1 , 0
  4406.3     .12       0  4935.1      .1       0    5012     .05       0
  5024.5      .1       0    5149    .035       0  5163.1      .1       0
  5269.5     .07       0
Bank Sta=5012,5024.5
XS Rating Curve= 0 ,0
Exp/Cntr=0.3,0.1

Type RM Length L Ch R = 1 ,107799  ,468,468,468
BEGIN DESCRIPTION:
CLEAR FORK SANDIES CREEK 127.0
END DESCRIPTION:
XS GIS Cut Line= 3
      2334525.01     13678525.01        2334275.       13678275.
      2333874.99     13677474.99
#Sta/Elev= 30
  4642.5  436.57    4646  436.57  4656.6  433.85  4772.5   429.5  4798.1  428.97
  4840.5  426.93  4998.9  423.37    5010   422.4  5012.1  419.58  5012.6  419.08
  5024.3  419.08  5024.8  419.58  5032.4  422.05  5040.8  422.99  5063.1  423.49
  5099.5  422.86  5107.9  422.01  5144.2  420.67  5183.3  423.45  5244.2  423.38
  5406.9  424.07  5449.9  425.11  5518.7  426.15  5524.3  426.84  5622.2  429.27
  5680.9  431.63  5761.1  436.04  5792.7  436.77  5831.8  439.85  5890.5   442.7
#Mann= 7 ,-1 , 0
  4642.5     .07       0  4772.5      .1       0  5012.1     .05       0
  5024.8      .1       0  5244.2     .12       0  5449.9     .07       0
  5761.1    .035       0
Bank Sta=5012.1,5024.8
XS Rating Curve= 0 ,0
Exp/Cntr=0.3,0.1

Type RM Length L Ch R = 1 ,107331  ,443,443,443
BEGIN DESCRIPTION:
CLEAR FORK SANDIES CREEK 126.0
END DESCRIPTION:
XS GIS Cut Line= 3
      2334874.98     13678524.96        2334625.       13677975.
      2334025.02     13677375.02
#Sta/Elev= 30
  4395.9  443.06  4433.2  442.53  4450.8  440.46  4459.5  440.31  4484.8  440.25
  4507.9  437.22  4538.7  437.32  4571.6  436.21  4582.6  435.07  4678.8  430.94
  4752.9  427.04  4813.3  425.55  4865.6  422.88  4870.4  423.43  4923.1  421.69
  4945.1  422.58    4978   422.6  5003.5  421.42  5007.7  417.19  5008.2  416.69
  5020.5  417.19  5028.3  421.59  5380.5  422.57    5507  423.02    5594  426.43
  5735.4   435.4  5777.8  436.69  5820.3   439.4  5834.4  441.74  5848.5  442.97
#Mann= 8 ,-1 , 0
  4395.9    .035       0  4459.5     .07       0  4678.8     .12       0
  4865.6      .1       0  5007.7     .05       0  5020.5      .1       0
  5380.5     .12       0    5507     .07       0
Bank Sta=5007.7,5020.5
XS Rating Curve= 0 ,0
Exp/Cntr=0.3,0.1

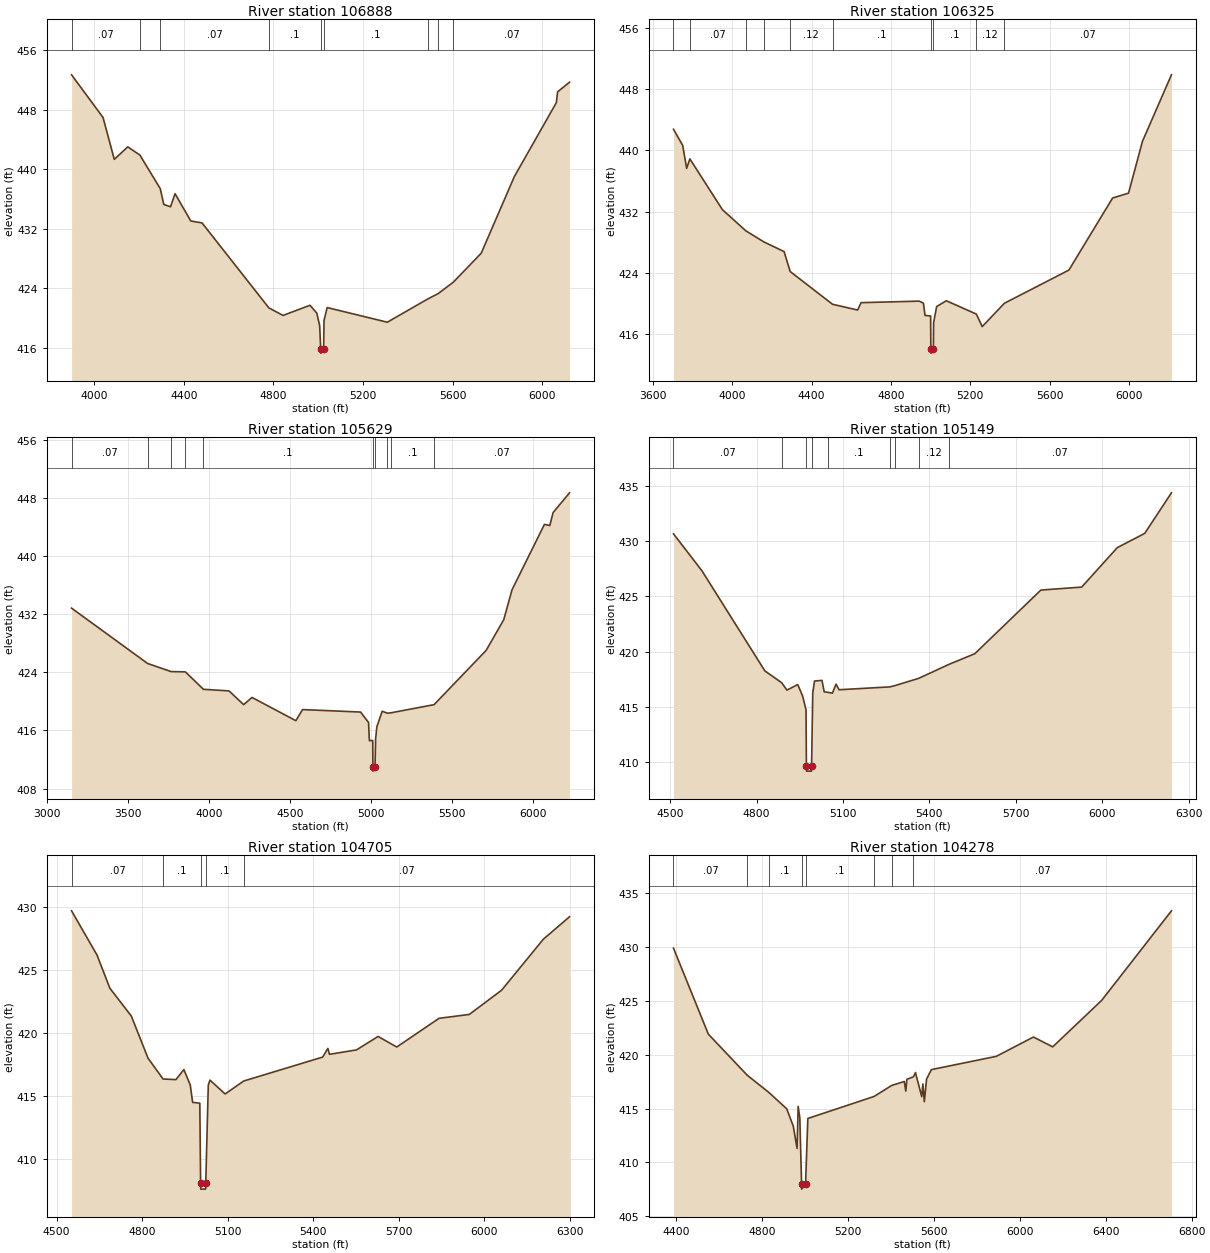
Type RM Length L Ch R = 1 ,106888  ,563,563,563
BEGIN DESCRIPTION:
CLEAR FORK SANDIES CREEK 125.0
END DESCRIPTION:
XS GIS Cut Line= 3
        2335025.     13678774.96        2334925.       13677675.
      2333925.02     13677175.01
#Sta/Elev= 30
  3899.1  452.72  4039.6  446.98  4089.8  441.35  4150.1  443.03  4203.9  441.93
    4295  437.41  4310.7  435.28  4340.9  434.97    4361  436.73  4431.2  433.06
  4481.4   432.8  4779.7  421.37  4842.9  420.35  4963.4  421.72  4993.6  420.66
  5006.4  418.99  5011.2  415.78  5011.7  415.28    5024  415.78    5026  419.68
  5039.9  421.41  5308.3  419.44  5489.9  422.58  5535.5  423.29  5603.1  424.83
  5727.5  428.72  5875.7  439.05  6062.9  448.98  6068.5  450.43  6121.6  451.73
#Mann= 9 ,-1 , 0
  3899.1     .07       0  4203.9    .035       0    4295     .07       0
  4779.7      .1       0  5011.2     .05       0    5024      .1       0
  5489.9     .07       0  5535.5     .12       0  5603.1     .07       0
Bank Sta=5011.2,5024
XS Rating Curve= 0 ,0
Exp/Cntr=0.3,0.1

Type RM Length L Ch R = 1 ,106325  ,696,696,696
BEGIN DESCRIPTION:
X18504
END DESCRIPTION:
XS GIS Cut Line= 4
      2335247.81      13678651.2      2335319.73      13677558.1
      2334730.04     13677176.96      2334019.05     13677133.87
#Sta/Elev= 30
  3703.7  442.74    3750  440.64    3770  437.64  3786.2  438.88  3950.4  432.25
  4068.9  429.49  4159.4  428.05  4261.1  426.79  4291.9  424.19  4505.4  419.92
  4631.9  419.17    4649  420.13  4942.4  420.33  4963.5  420.07  4971.5  418.47
  4999.8  418.39  5000.8  414.05  5001.3  413.55  5013.6  414.05  5014.9  417.52
  5030.1  419.62  5078.7  420.38  5230.3  418.64  5259.7  417.01  5371.4  420.05
  5696.7  424.38  5917.1  433.78  5997.3  434.41  6067.4  441.16  6213.6  449.84
#Mann= 10 ,-1 , 0
  3703.7    .035       0  3786.2     .07       0  4068.9    .035       0
  4159.4     .07       0  4291.9     .12       0  4505.4      .1       0
  5000.8     .05       0  5013.6      .1       0  5230.3     .12       0
  5371.4     .07       0
Bank Sta=5000.8,5013.6
XS Rating Curve= 0 ,0
Exp/Cntr=0.3,0.1

Type RM Length L Ch R = 1 ,105629  ,480,480,480
BEGIN DESCRIPTION:
CLEAR FORK SANDIES CREEK 124.0
END DESCRIPTION:
XS GIS Cut Line= 3
        2335675.     13678674.99        2335225.       13676875.
      2334025.04     13677074.99
#Sta/Elev= 30
  3151.7  432.83  3620.4  425.22  3765.7   424.1  3853.8  424.06  3965.3  421.66
  4123.2  421.44  4213.4  419.55  4264.9  420.54  4535.5  417.34  4576.7  418.87
  4934.9  418.53  4983.9  417.09    4989  414.59  5009.6  414.62  5010.7   410.9
  5011.2   410.4  5023.7   410.9  5027.4  414.81    5035   416.5  5067.9  418.64
  5100.4  418.37  5123.2  418.43  5388.1  419.55  5709.1  427.01  5818.1  431.25
  5868.8  435.35    6069  444.36    6102   444.2  6122.3  445.98  6223.6   448.7
#Mann= 10 ,-1 , 0
  3151.7     .07       0  3620.4     .12       0  3765.7    .035       0
  3853.8     .12       0  3965.3      .1       0  5010.7     .05       0
  5023.7      .1       0  5100.4     .12       0  5123.2      .1       0
  5388.1     .07       0
Bank Sta=5010.7,5023.7
XS Rating Curve= 0 ,0
Exp/Cntr=0.3,0.1

Type RM Length L Ch R = 1 ,105149  ,444,444,444
BEGIN DESCRIPTION:
CLEAR FORK SANDIES CREEK 123.0
END DESCRIPTION:
XS GIS Cut Line= 3
      2335975.02     13676875.01        2335525.       13676675.
        2334325.       13676375.
#Sta/Elev= 30
  4511.3  430.68  4609.8  427.34  4828.7  418.25  4886.9  417.18  4905.3  416.51
  4942.9  417.01    4960  415.95  4971.6  414.71  4972.9  409.66  4973.4  409.16
  4990.4  409.16  4990.9  409.66  4994.9  416.23    5001  417.33    5027  417.39
  5034.7  416.35  5046.9  416.31    5063  416.23  5075.9  417.05  5086.2  416.54
  5262.7   416.8    5281  416.92  5363.4  417.58  5468.7  418.85  5557.8  419.81
  5787.2  425.58  5928.9  425.85  6052.6  429.43  6147.9  430.72  6240.7   434.4
#Mann= 9 ,-1 , 0
  4511.3     .07       0  4886.9      .1       0  4972.9     .05       0
  4990.9      .1       0  5046.9      .1       0  5262.7     .12       0
    5281     .07       0  5363.4     .12       0  5468.7     .07       0
Bank Sta=4972.9,4990.9
XS Rating Curve= 0 ,0
Exp/Cntr=0.3,0.1

Type RM Length L Ch R = 1 ,104705  ,427,427,427
BEGIN DESCRIPTION:
CLEAR FORK SANDIES CREEK 122.0
END DESCRIPTION:
XS GIS Cut Line= 3
      2336025.02     13676775.03        2335825.       13676375.
      2334624.96     13675874.98
#Sta/Elev= 30
  4552.7  429.69  4642.2  426.17  4686.9  423.55  4762.4  421.33  4821.1  417.98
  4873.8  416.33  4918.9  416.28  4946.8  417.08  4969.2  415.85  4977.6  414.47
  5002.7  414.41  5005.5  408.08    5006  407.58  5023.1  407.58  5023.6  408.08
  5032.5  415.84  5038.4  416.24  5091.5  415.14  5156.9  416.17  5433.8  418.07
  5452.2  418.76  5457.7  418.29  5552.5  418.64  5628.3  419.71  5693.8  418.87
  5842.2  421.15  5948.4  421.46  6061.6  423.38  6208.4  427.44    6300  429.22
#Mann= 5 ,-1 , 0
  4552.7     .07       0  4873.8      .1       0  5005.5     .05       0
  5023.6      .1       0  5156.9     .07       0
Bank Sta=5005.5,5023.6
XS Rating Curve= 0 ,0
Exp/Cntr=0.3,0.1

Type RM Length L Ch R = 1 ,104278  ,416,416,416
BEGIN DESCRIPTION:
CLEAR FORK SANDIES CREEK 121.0
END DESCRIPTION:
XS GIS Cut Line= 3
      2336075.01     13676774.97        2336175.       13676175.
      2334525.01       13675725.
#Sta/Elev= 30
  4387.4  429.87  4549.6   421.9  4730.6  418.09  4829.9  416.52  4914.5  414.98
    4945  413.38  4962.7   411.3  4967.8   415.2  4975.4  414.18  4983.8  408.03
  4984.3  407.53  5002.4  408.03  5012.9  414.08  5321.2  416.12  5403.2  417.14
  5462.1  417.51    5469  416.62  5474.2  417.71  5504.4  417.94  5513.9  418.34
  5543.3   416.1  5548.5  417.28  5555.4  415.63  5565.7  417.73  5588.2  418.61
  5890.5  419.84  6063.3  421.63  6153.1  420.72  6381.1  425.03  6705.9  433.33
#Mann= 8 ,-1 , 0
  4387.4     .07       0  4730.6     .12       0  4829.9      .1       0
  4983.8     .05       0  5002.4      .1       0  5321.2     .12       0
  5403.2      .1       0  5504.4     .07       0
Bank Sta=4983.8,5002.4
XS Rating Curve= 0 ,0
Exp/Cntr=0.3,0.1

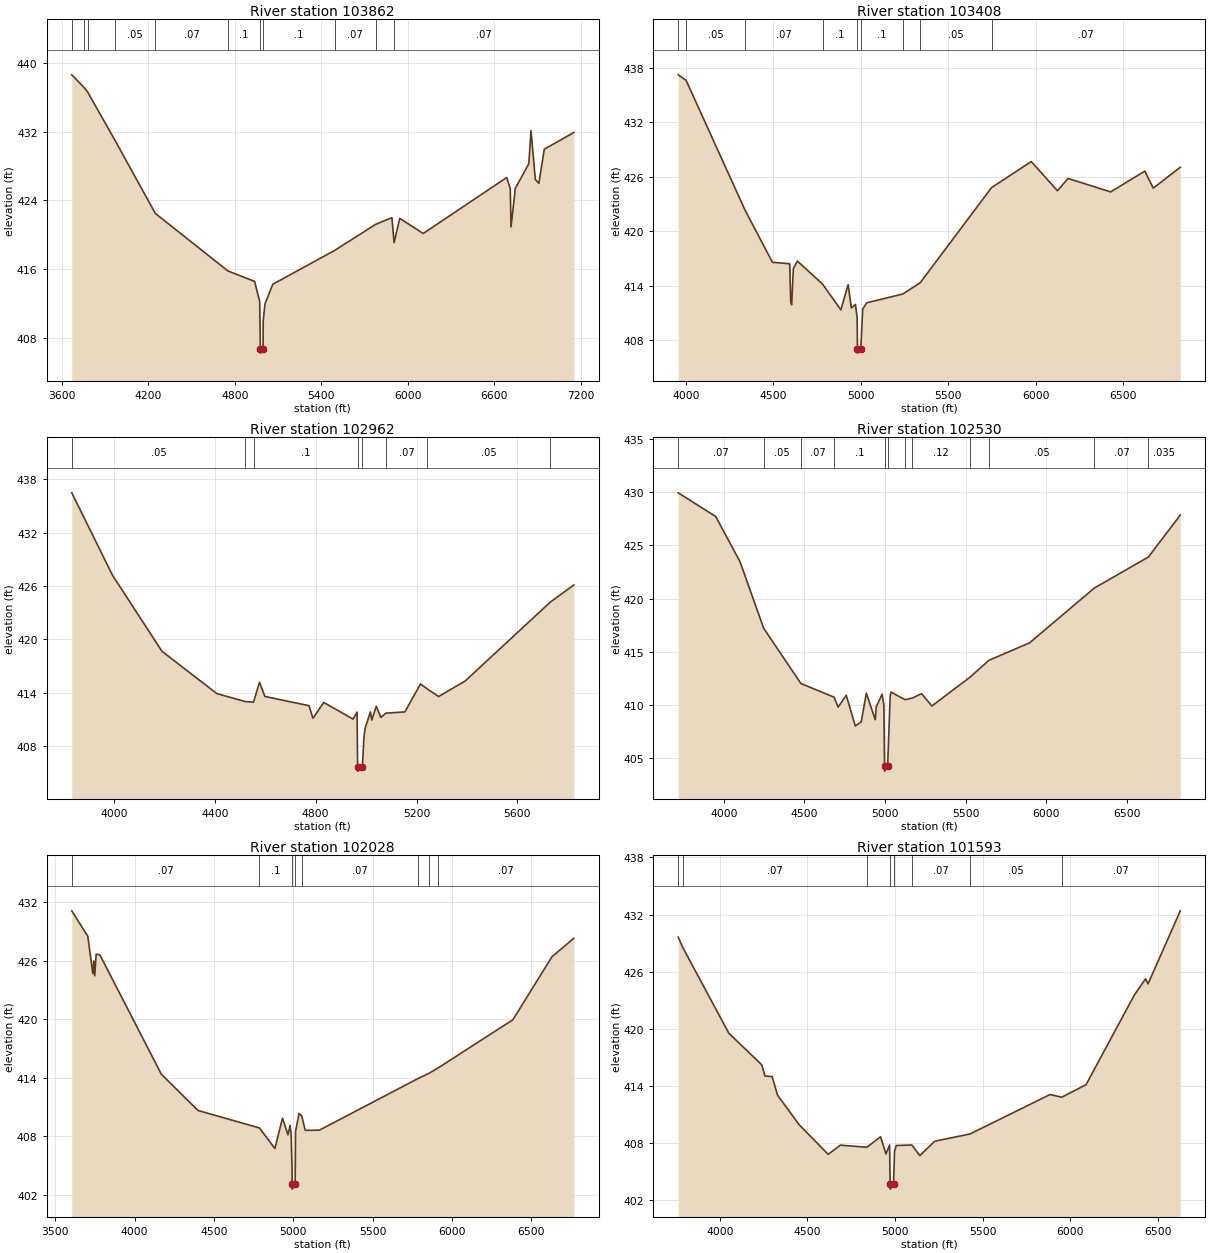
Type RM Length L Ch R = 1 ,103862  ,454,454,454
BEGIN DESCRIPTION:
CLEAR FORK SANDIES CREEK 120.0
END DESCRIPTION:
XS GIS Cut Line= 3
      2337318.92     13676946.85        2336475.       13675925.
      2334464.01     13675141.83
#Sta/Elev= 30
  3668.2  438.63  3751.9  437.19  3778.9  436.61  3965.5  431.07  4247.9  422.47
  4751.9  415.76  4936.8  414.54    4972  412.19  4976.8  406.68  4977.3  406.18
  4995.8  406.68  4996.2  409.91  5008.4   411.9  5062.8  414.21  5493.8  418.17
    5777   421.2  5889.3  421.98  5904.4  419.06  5943.7  421.89  6106.9  420.13
    6686  426.66  6710.5  425.35  6715.8   420.9  6745.7   425.4  6839.3  428.27
  6854.5  432.13  6884.4  426.42  6908.9  425.98  6946.6  429.96  7151.6   431.9
#Mann= 11 ,-1 , 0
  3668.2    .035       0  3751.9     .05       0  3778.9    .035       0
  3965.5     .05       0  4247.9     .07       0  4751.9      .1       0
  4976.8     .05       0  4995.8      .1       0  5493.8     .07       0
    5777     .12       0  5904.4     .07       0
Bank Sta=4976.8,4995.8
XS Rating Curve= 0 ,0
Exp/Cntr=0.3,0.1

Type RM Length L Ch R = 1 ,103408  ,446,446,446
BEGIN DESCRIPTION:
CLEAR FORK SANDIES CREEK 119.0
END DESCRIPTION:
XS GIS Cut Line= 3
      2337624.99       13675825.        2336625.       13675525.
      2334824.95     13675224.99
#Sta/Elev= 30
  3956.4  437.24  4001.1  436.64  4339.4  422.29  4494.9   416.6  4593.3  416.44
  4599.3  412.22  4604.6  411.93  4614.1   415.9  4637.6  416.73  4780.8  414.21
  4885.6  411.36  4927.3  414.14  4945.6  411.57  4969.1  411.95  4978.7  410.48
  4980.5   407.1    4981   406.6  4999.5   407.1  5010.6  411.45  5033.4  412.14
  5239.3  413.11  5338.6  414.34  5746.6  424.82  5973.7  427.69  6123.2  424.48
    6184  425.83  6427.3  424.35  6622.5  426.64  6670.6  424.76  6825.3  427.07
#Mann= 9 ,-1 , 0
  3956.4     .07       0  4001.1     .05       0  4339.4     .07       0
  4780.8      .1       0  4980.5     .05       0  4999.5      .1       0
  5239.3     .07       0  5338.6     .05       0  5746.6     .07       0
Bank Sta=4980.5,4999.5
XS Rating Curve= 0 ,0
Exp/Cntr=0.3,0.1

Type RM Length L Ch R = 1 ,102962  ,432,432,432
BEGIN DESCRIPTION:
CLEAR FORK SANDIES CREEK 118.0
END DESCRIPTION:
XS GIS Cut Line= 3
      2337575.02     13675725.01        2336575.       13675125.
      2335775.03     13675324.99
#Sta/Elev= 30
  3833.1  436.47  3994.4  427.21  4190.7  418.65  4408.4  413.89  4521.7  412.99
  4553.8  412.93  4577.5  415.16  4598.9  413.57  4773.8  412.53  4789.4  411.12
  4832.2  412.89  4948.8  411.02  4964.3  411.81  4966.5  405.67    4967  405.17
  4985.5  405.67  4991.5  408.91  4996.4  410.01  5017.3  411.84  5022.5  410.91
  5040.5  412.47  5058.6  411.21  5078.9  411.69  5153.9  411.83  5215.8  414.97
  5243.3   414.4  5287.9  413.56  5393.6  415.32  5729.8  424.16  5823.9  426.11
#Mann= 8 ,-1 , 0
  3833.1     .05       0  4521.7     .07       0  4553.8      .1       0
  4966.5     .05       0  4985.5      .1       0  5078.9     .07       0
  5243.3     .05       0  5729.8     .07       0
Bank Sta=4966.5,4985.5
XS Rating Curve= 0 ,0
Exp/Cntr=0.3,0.1

Type RM Length L Ch R = 1 ,102530  ,502,502,502
BEGIN DESCRIPTION:
X18503
END DESCRIPTION:
XS GIS Cut Line= 3
      2337908.59     13675515.76      2336973.73     13674846.97
      2335125.57     13674178.18
#Sta/Elev= 30
  3717.3  429.96  3949.9  427.73    4101  423.46  4247.2  417.21  4478.4     412
  4683.8  410.72  4709.2  409.78  4759.6  410.89  4816.1     408  4852.9   408.4
  4884.3  411.09  4939.8  408.59  4945.6   409.8  4982.4     411    4993  409.95
  4997.3  404.25  4997.8  403.75  5016.4  404.25  5032.2  410.81  5037.5  411.19
  5124.4  410.48  5169.7  410.63    5227  411.05  5290.8  409.88  5529.3  412.62
  5643.9  414.18    5897  415.83  6298.7  420.99  6633.8  423.91  6832.2  427.87
#Mann= 12 ,-1 , 0
  3717.3     .07       0  4247.2     .05       0  4478.4     .07       0
  4683.8      .1       0  4997.3     .05       0  5016.4      .1       0
  5124.4     .07       0  5169.7     .12       0  5529.3     .07       0
  5643.9     .05       0  6298.7     .07       0  6633.8    .035       0
Bank Sta=4997.3,5016.4
XS Rating Curve= 0 ,0
Exp/Cntr=0.3,0.1

Type RM Length L Ch R = 1 ,102028  ,435,435,435
BEGIN DESCRIPTION:
CLEAR FORK SANDIES CREEK 117.0
END DESCRIPTION:
XS GIS Cut Line= 3
      2338260.97     13674803.83      2336966.54     13674379.54
      2335363.11     13673559.85
#Sta/Elev= 30
  3603.8  431.14  3704.8  428.53  3736.4   424.7  3743.1  425.99  3748.3  424.47
  3757.4  426.69  3780.2  426.64  4167.8  414.38  4399.3  410.65    4786  408.86
  4883.4  406.75  4931.6  409.87    4966  408.15    4979  409.12  4985.8  408.24
  4991.4  404.69  4991.8  403.08  4992.3  402.58  5011.1  403.08  5013.6   408.5
  5035.8  410.35  5052.7  410.08  5074.6  408.61  5163.5  408.63  5786.6  413.94
  5853.5  414.46  5908.4  414.98  6382.8  419.96  6629.5  426.44  6766.8  428.32
#Mann= 8 ,-1 , 0
  3603.8     .07       0    4786      .1       0  4991.8     .05       0
  5011.1      .1       0  5052.7     .07       0  5786.6    .035       0
  5853.5     .05       0  5908.4     .07       0
Bank Sta=4991.8,5011.1
XS Rating Curve= 0 ,0
Exp/Cntr=0.3,0.1

Type RM Length L Ch R = 1 ,101593  ,482,482,482
BEGIN DESCRIPTION:
CLEAR FORK SANDIES CREEK 116.0
END DESCRIPTION:
XS GIS Cut Line= 3
      2338275.04     13674275.01        2337075.       13673975.
      2335874.97     13672874.97
#Sta/Elev= 30
  3762.6  429.61  3789.1  428.51  4051.3  419.52  4239.4  416.19  4257.4  415.02
  4298.6  414.95  4329.6  412.99  4453.3  409.88  4618.2  406.78  4687.8  407.75
    4839  407.52  4917.1  408.63    4948  406.82  4968.6  407.76  4971.8  403.62
  4972.3  403.12  4991.2  403.62    4997  407.12  5006.7  407.71  5095.7  407.76
  5141.1  406.64  5226.2  408.16  5427.4  408.92  5884.1  413.07  5951.2  412.79
  6089.5   414.1  6365.7  423.55  6429.2  425.23  6443.4  424.71  6627.5  432.39
#Mann= 8 ,-1 , 0
  3762.6     .05       0  3789.1     .07       0    4839      .1       0
  4971.8     .05       0  4991.2      .1       0  5095.7     .07       0
  5427.4     .05       0  5951.2     .07       0
Bank Sta=4971.8,4991.2
XS Rating Curve= 0 ,0
Exp/Cntr=0.3,0.1

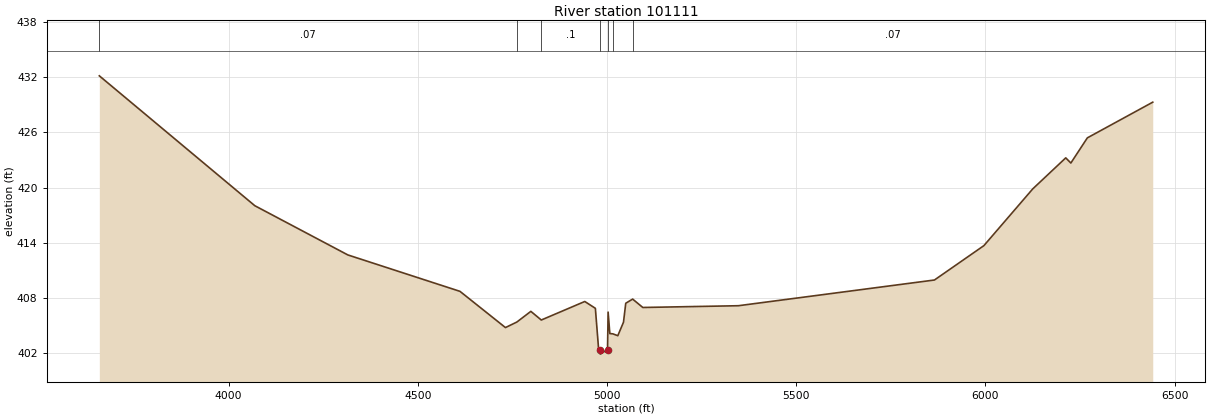
Type RM Length L Ch R = 1 ,101111  ,471,471,471
BEGIN DESCRIPTION:
CLEAR FORK SANDIES CREEK 115.0
END DESCRIPTION:
XS GIS Cut Line= 3
      2338374.99       13674125.        2337175.       13673525.
      2336374.98     13672324.96
#Sta/Elev= 30
  3658.2  432.12  4069.1  418.03    4315  412.69  4611.3  408.74  4731.5  404.81
  4761.6  405.41  4798.6  406.57  4826.2  405.63  4941.1  407.64  4969.1   406.9
  4977.5  402.55  4981.7  402.43  4982.2  401.93  5001.2  402.43  5002.8  406.49
  5007.3  404.16  5015.3  404.13  5028.4  403.93  5043.4  405.39  5049.4  407.45
  5067.6   407.9  5094.5  406.99  5346.9  407.18  5865.2  409.97  5995.9   413.7
  6125.1  419.86  6212.2  423.22  6225.7  422.66  6269.3  425.39  6442.1  429.26
#Mann= 7 ,-1 , 0
  3658.2     .07       0  4761.6    .035       0  4826.2      .1       0
  4981.7     .05       0  5001.2      .1       0  5015.3    .035       0
  5067.6     .07       0
Bank Sta=4981.7,5001.2
XS Rating Curve= 0 ,0
Exp/Cntr=0.3,0.1