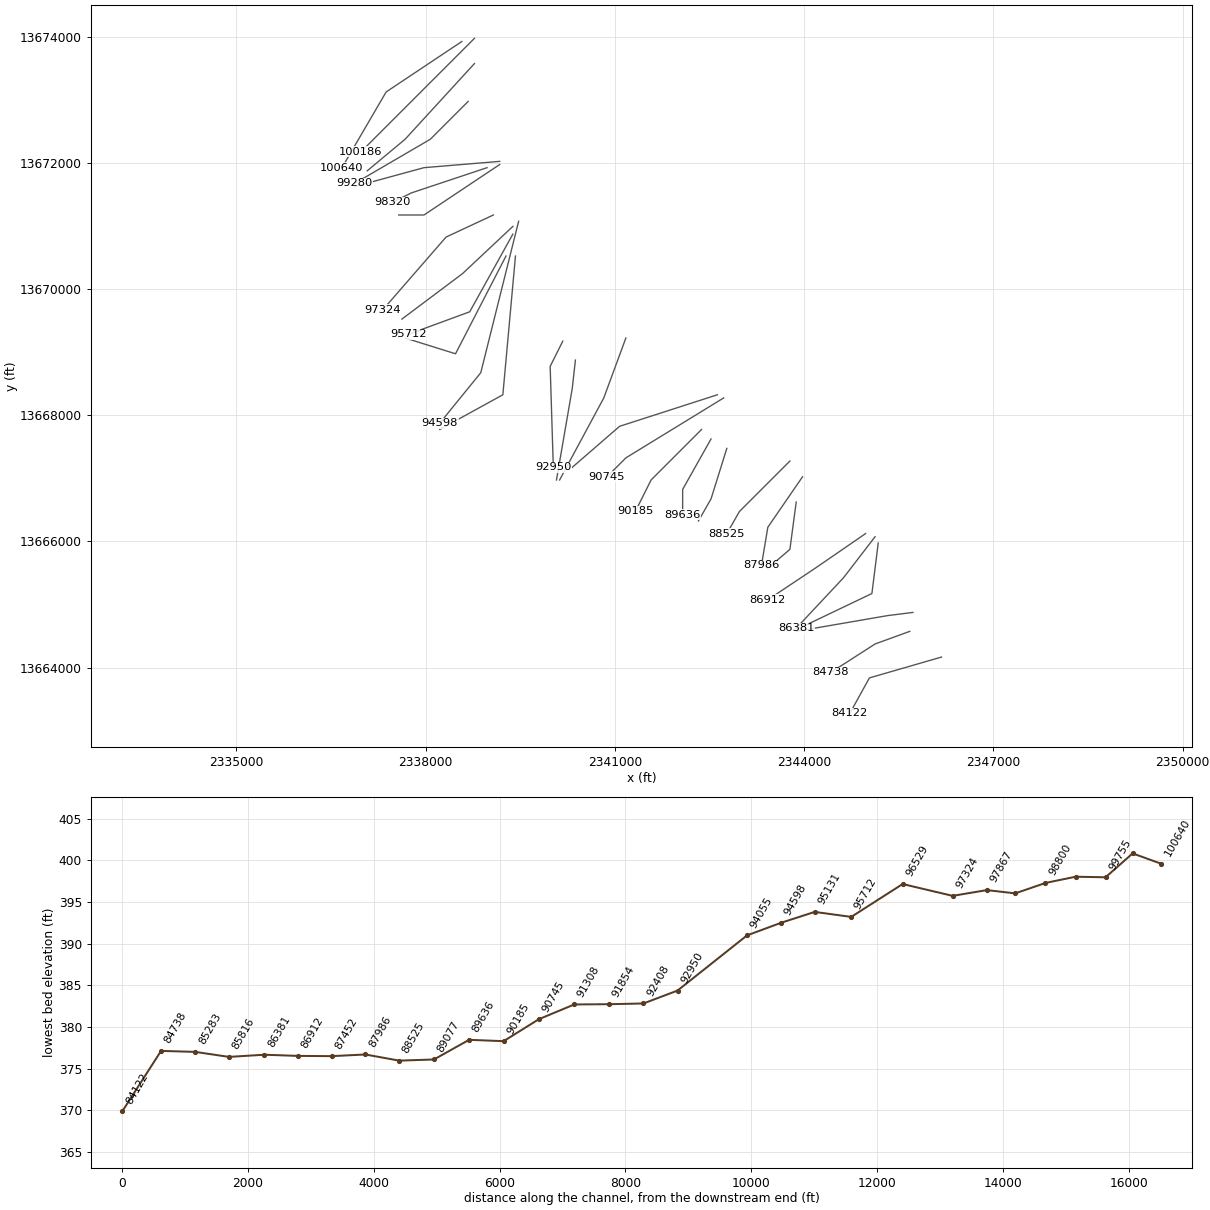
HEC-RAS study CLEAR FORK SANDIES CREEK.prj: CLEAR FORK SANDIES CREEK Base Level Engineering

--- CLEAR FORK SANDIES CREEK.g01 (geometry) --- (continued)

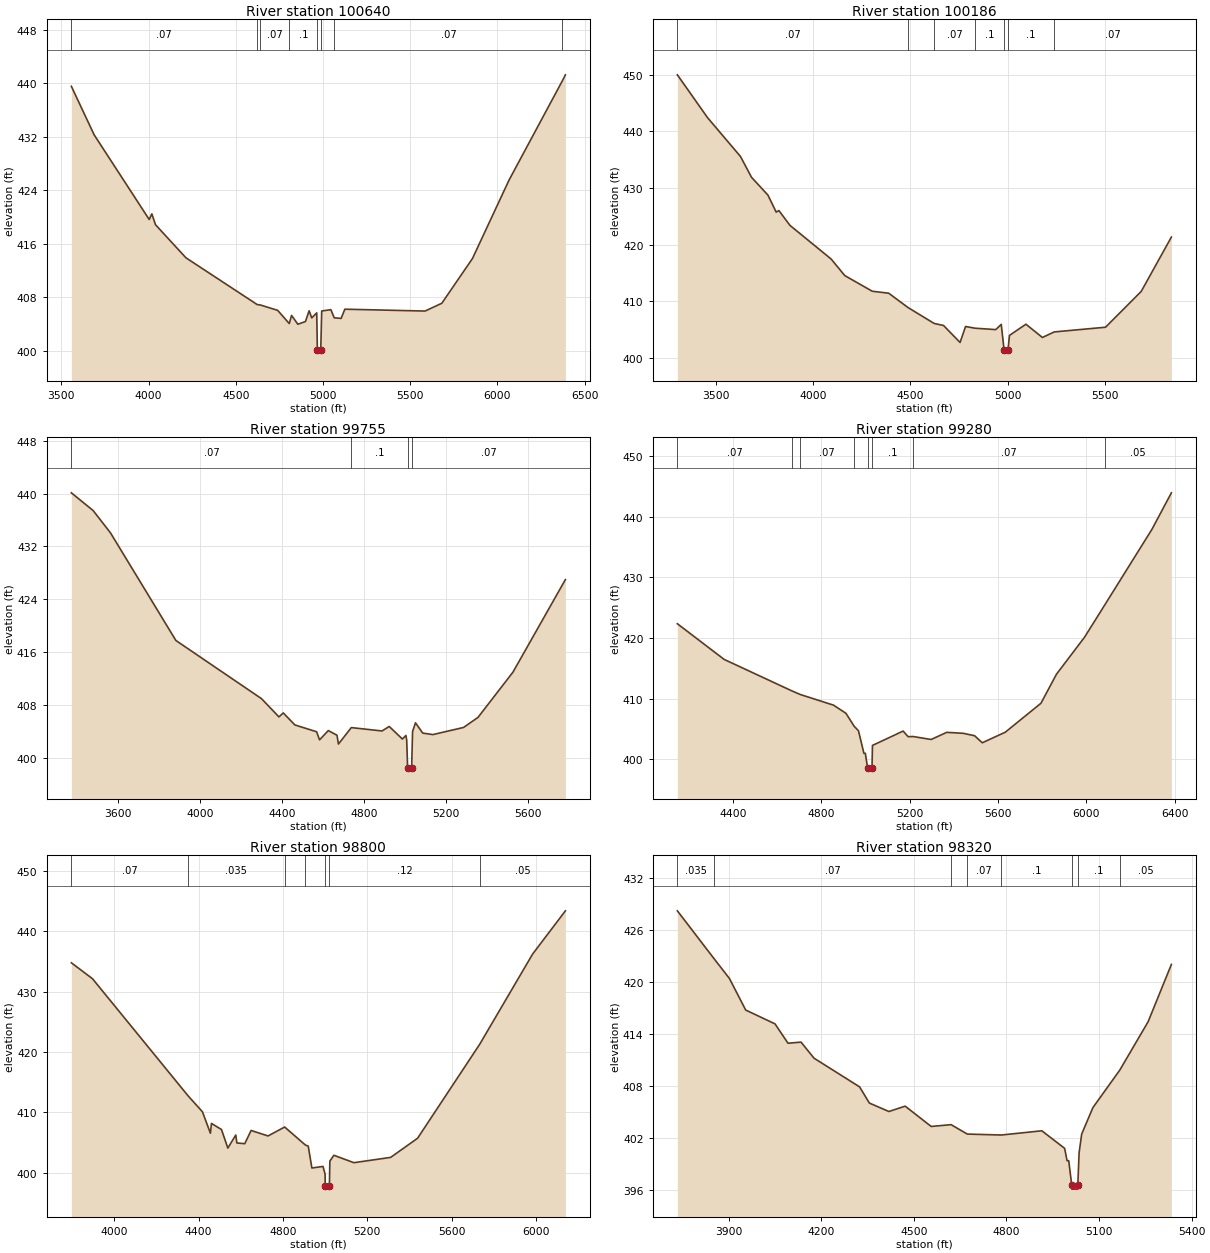
Type RM Length L Ch R = 1 ,100640  ,454,454,454
BEGIN DESCRIPTION:
CLEAR FORK SANDIES CREEK 114.0
END DESCRIPTION:
XS GIS Cut Line= 3
      2338575.01       13673925.        2337375.       13673125.
      2336674.99     13671924.98
#Sta/Elev= 30
  3557.8  439.57  3688.5   432.3    4004  419.62    4019  420.47  4040.1  418.84
  4214.3  413.89    4623  406.88  4639.5  406.83  4740.1  406.02  4806.6  404.04
  4819.8  405.26  4855.8  403.94  4899.4  404.34  4920.4  405.95  4935.4  404.89
    4964  405.64  4967.7  400.11  4968.2  399.61  4987.2  400.11  4992.5  405.92
  5045.1  406.12  5064.5   404.9  5103.8  404.81  5125.3  406.19  5585.1  405.91
    5681  407.08  5856.7  413.78  6066.4  425.53  6372.6  440.43  6389.3  441.29
#Mann= 8 ,-1 , 0
  3557.8     .07       0    4623    .035       0  4639.5     .07       0
  4806.6      .1       0  4967.7     .05       0  4987.2      .1       0
  5064.5     .07       0  6372.6     .05       0
Bank Sta=4967.7,4987.2
XS Rating Curve= 0 ,0
Exp/Cntr=0.3,0.1

Type RM Length L Ch R = 1 ,100186  ,431,431,431
BEGIN DESCRIPTION:
CLEAR FORK SANDIES CREEK 113.0
END DESCRIPTION:
XS GIS Cut Line= 3
      2338775.03     13673975.03        2337575.       13672775.
      2336975.02     13672175.02
#Sta/Elev= 30
  3298.8  449.95  3454.4  442.39  3624.1  435.54  3680.7  431.88  3765.5  428.73
    3808  425.73  3822.1     426  3878.7   423.4  4090.8  417.46  4161.5  414.53
  4302.9  411.77  4387.8  411.42  4487.4  408.89  4621.9  406.09  4670.6  405.72
  4755.5  402.73  4783.8  405.55  4832.4  405.25  4939.3     405  4967.6  405.92
  4982.6  401.35  4983.1  400.85  5002.1  401.35    5010  403.98  5094.9  405.95
  5179.7  403.61  5240.6  404.59    5505  405.42  5688.9  411.74  5844.4  421.33
#Mann= 7 ,-1 , 0
  3298.8     .07       0  4487.4    .035       0  4621.9     .07       0
  4832.4      .1       0  4982.6     .05       0  5002.1      .1       0
  5240.6     .07       0
Bank Sta=4982.6,5002.1
XS Rating Curve= 0 ,0
Exp/Cntr=0.3,0.1

Type RM Length L Ch R = 1 ,99755   ,475,475,475
BEGIN DESCRIPTION:
CLEAR FORK SANDIES CREEK 112.0
END DESCRIPTION:
XS GIS Cut Line= 3
      2338775.01     13673575.01        2337675.       13672375.
      2337075.01     13671875.01
#Sta/Elev= 30
  3371.6  440.11    3478  437.42  3562.5  434.04  3881.2  417.76  4298.7  408.95
  4383.8  406.19  4404.8  406.79  4461.5  404.97  4567.5  403.94  4581.7  402.71
  4624.3  404.12  4666.8  403.41  4673.9  402.08  4736.6  404.57  4886.3  404.06
  4921.5  404.74  4985.6  402.84  5002.7  403.38  5006.7  402.68  5011.1  398.48
  5011.6  397.98  5030.8  398.48  5035.3  403.98  5049.6  405.29  5084.8  403.74
  5134.2  403.51  5283.9  404.59  5354.2  406.11  5524.7  412.96  5780.5  426.98
#Mann= 4 ,-1 , 0
  3371.6     .07       0  4736.6      .1       0  5011.1     .05       0
  5030.8     .07       0
Bank Sta=5011.1,5030.8
XS Rating Curve= 0 ,0
Exp/Cntr=0.3,0.1

Type RM Length L Ch R = 1 ,99280   ,480,480,480
BEGIN DESCRIPTION:
CLEAR FORK SANDIES CREEK 111.0
END DESCRIPTION:
XS GIS Cut Line= 3
      2338675.01     13672975.01        2338075.       13672375.
      2336874.99     13671674.99
#Sta/Elev= 30
  4147.8  422.37  4359.9  416.48  4667.1  411.28  4704.8  410.69  4854.9  408.94
  4911.5  407.59  4948.5  405.46  4968.1  404.71  4992.8  400.99  4999.2  400.99
  5009.6  398.55  5010.1  398.05  5028.9  398.05  5029.4  398.55  5031.5  402.29
  5170.4  404.66  5193.2  403.73  5215.5  403.76  5297.3  403.27    5368  404.45
  5442.5  404.29  5494.2  403.89  5528.9  402.73  5633.1  404.47  5794.7  409.25
    5865  414.04    5992  420.14  6085.3  425.56  6297.5  437.95  6385.6  443.97
#Mann= 8 ,-1 , 0
  4147.8     .07       0  4667.1    .035       0  4704.8     .07       0
  4948.5      .1       0  5009.6     .05       0  5029.4      .1       0
  5215.5     .07       0  6085.3     .05       0
Bank Sta=5009.6,5029.4
XS Rating Curve= 0 ,0
Exp/Cntr=0.3,0.1

Type RM Length L Ch R = 1 ,98800   ,480,480,480
BEGIN DESCRIPTION:
CLEAR FORK SANDIES CREEK 110.0
END DESCRIPTION:
XS GIS Cut Line= 3
      2339174.97       13672025.        2337975.       13671925.
      2336875.01       13671625.
#Sta/Elev= 30
  3795.9   434.8  3896.2  432.16  4349.5  412.77    4418  410.11  4455.7  406.56
  4460.7  408.19  4508.3  407.17  4538.4   404.1  4576.1  406.27  4581.1  404.95
  4618.7  404.83  4648.8  407.02  4729.1  406.11    4808  407.59  4906.6   404.6
  4919.8  404.43  4937.3   400.8    4990  401.06    5000  399.76  5000.5   397.8
    5001   397.3  5020.3   397.8  5022.5  401.94  5041.5  402.91  5136.5  401.68
    5311  402.56  5438.8  405.73  5733.7  421.31  5984.7  436.25  6140.2  443.41
#Mann= 7 ,-1 , 0
  3795.9     .07       0  4349.5    .035       0    4808     .07       0
  4906.6     .12       0  5000.5     .05       0  5020.3     .12       0
  5733.7     .05       0
Bank Sta=5000.5,5020.3
XS Rating Curve= 0 ,0
Exp/Cntr=0.3,0.1

Type RM Length L Ch R = 1 ,98320   ,453,453,453
BEGIN DESCRIPTION:
CLEAR FORK SANDIES CREEK 109.0
END DESCRIPTION:
XS GIS Cut Line= 3
      2338975.02     13671925.01        2337775.       13671525.
      2337475.04     13671375.02
#Sta/Elev= 30
  3734.1  428.25  3852.6  422.73  3902.8  420.42  3955.5  416.77  4050.4  415.17
  4092.5  412.93  4134.7  413.06  4176.8   411.2  4324.4  407.88    4356  406.01
  4419.3  405.03    4472  405.65  4556.3   403.3  4620.7  403.51  4673.3  402.42
  4783.3  402.31  4914.7   402.8  4988.5  400.77  4996.4  399.34  5001.8  399.34
  5011.5  396.55    5012  396.05  5030.8  396.05  5031.3  396.55  5035.4  400.25
  5043.8  402.42  5080.1  405.48  5167.2  409.82    5259  415.42  5334.4  422.05
#Mann= 8 ,-1 , 0
  3734.1    .035       0  3852.6     .07       0  4620.7      .1       0
  4673.3     .07       0  4783.3      .1       0  5011.5     .05       0
  5031.3      .1       0  5167.2     .05       0
Bank Sta=5011.5,5031.3
XS Rating Curve= 0 ,0
Exp/Cntr=0.3,0.1

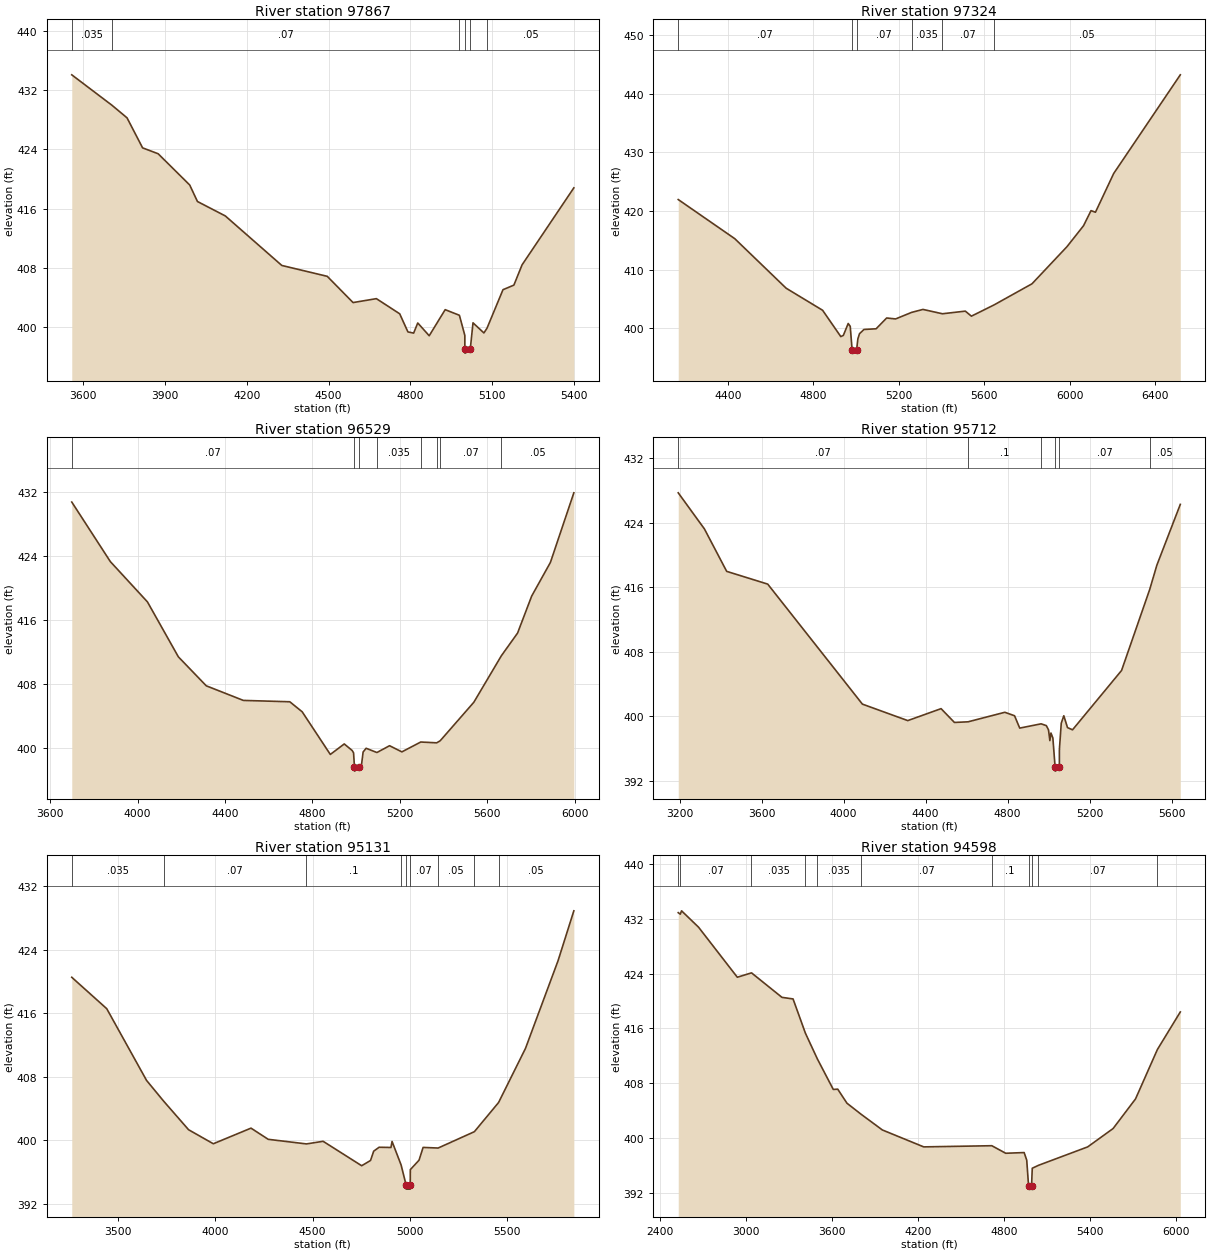
Type RM Length L Ch R = 1 ,97867   ,543,543,543
BEGIN DESCRIPTION:
CLEAR FORK SANDIES CREEK 108.0
END DESCRIPTION:
XS GIS Cut Line= 3
        2339175.       13671975.        2337975.       13671175.
      2337575.02       13671175.
#Sta/Elev= 30
  3557.7  434.09  3705.3  429.97  3760.5  428.27  3817.6  424.21  3874.7  423.41
  3990.4  419.19  4018.9  416.95  4121.1     415  4328.4   408.3  4495.1  406.83
  4589.8  403.28  4675.4  403.81    4761  401.76  4791.1  399.31  4812.1  399.15
  4827.2  400.52  4869.2  398.79  4927.8  402.32    4980  401.56  4999.9  398.84
    5000  396.94  5000.5  396.44  5019.8  396.94  5029.9  400.54  5069.9  399.17
  5081.4  399.82  5139.9  405.02  5179.9  405.64  5209.9  408.38  5399.9   418.8
#Mann= 6 ,-1 , 0
  3557.7    .035       0  3705.3     .07       0    4980      .1       0
    5000     .05       0  5019.8      .1       0  5081.4     .05       0
Bank Sta=5000,5019.8
XS Rating Curve= 0 ,0
Exp/Cntr=0.3,0.1

Type RM Length L Ch R = 1 ,97324   ,795,795,795
BEGIN DESCRIPTION:
CLEAR FORK SANDIES CREEK 107.0
END DESCRIPTION:
XS GIS Cut Line= 3
        2339075.       13671175.        2338325.       13670825.
      2337325.01     13669675.01
#Sta/Elev= 30
  4167.4  421.93  4432.2  415.26  4672.7  406.82  4843.7  403.05  4928.8  398.57
  4940.7  398.77  4963.5   400.8    4973  400.32  4981.9  396.25  4982.4  395.75
  5002.7  396.25  5008.8  398.18  5016.4  399.06  5037.3  399.78  5094.3   399.9
  5143.6  401.74  5185.5  401.58  5260.2  402.69  5313.6   403.2  5404.8  402.46
    5512  402.91  5540.5  402.05  5646.7  403.97  5824.4  407.57  5987.8  413.88
  6065.6  417.46  6100.8  420.04  6121.6  419.77  6207.1  426.38    6519  443.19
#Mann= 6 ,-1 , 0
  4167.4     .07       0  4981.9     .05       0  5002.7     .07       0
  5260.2    .035       0  5404.8     .07       0  5646.7     .05       0
Bank Sta=4981.9,5002.7
XS Rating Curve= 0 ,0
Exp/Cntr=0.3,0.1

Type RM Length L Ch R = 1 ,96529   ,817,817,817
BEGIN DESCRIPTION:
CLEAR FORK SANDIES CREEK 106.0
END DESCRIPTION:
XS GIS Cut Line= 3
       2339384.6     13670994.56      2338584.58     13670244.54
        2337625.       13669525.
#Sta/Elev= 30
  3699.4  430.73  3875.9   423.3  4045.4  418.28    4187  411.42  4314.5  407.81
    4484  405.99  4696.5  405.82  4753.1  404.57  4881.8  399.25  4945.5  400.56
  4981.8  399.74  4988.1  399.44  4992.2  397.67  4992.7  397.17  5013.1  397.67
  5023.5  397.77  5031.8  399.56  5045.5  400.02  5094.9  399.49  5152.7  400.34
  5208.9  399.57  5295.3   400.8  5368.1   400.7    5384  400.95  5538.1  405.76
  5664.2  411.57  5738.1  414.39  5802.7  419.01  5888.1  423.19  5995.4  431.88
#Mann= 8 ,-1 , 0
  3699.4     .07       0  4992.2     .05       0  5013.1     .07       0
  5094.9    .035       0  5295.3     .07       0  5368.1     .05       0
    5384     .07       0  5664.2     .05       0
Bank Sta=4992.2,5013.1
XS Rating Curve= 0 ,0
Exp/Cntr=0.3,0.1

Type RM Length L Ch R = 1 ,95712   ,581,581,581
BEGIN DESCRIPTION:
X18502
END DESCRIPTION:
XS GIS Cut Line= 3
       2339382.8     13670870.16      2338699.64     13669640.47
      2337721.66     13669280.92
#Sta/Elev= 30
  3193.7   427.7  3321.4  423.23    3430  417.97  3630.2  416.39  4091.9  401.52
  4313.2  399.48  4475.6  400.96  4540.8  399.25  4607.3  399.33  4786.5  400.51
    4834  400.08  4859.2  398.55  4963.5  399.08  4988.9  398.86  4999.6  398.33
  5006.2     397  5011.5  397.94  5020.9  397.32  5031.7  393.72  5032.2  393.22
  5052.6  393.72  5052.8  395.93  5061.8  399.16  5074.2  400.08  5092.3  398.61
  5116.8  398.34  5355.9  405.69  5493.2  415.73  5528.1  418.74  5642.4  426.27
#Mann= 6 ,-1 , 0
  3193.7     .07       0  4607.3      .1       0  4963.5     .07       0
  5031.7     .05       0  5052.6     .07       0  5493.2     .05       0
Bank Sta=5031.7,5052.6
XS Rating Curve= 0 ,0
Exp/Cntr=0.3,0.1

Type RM Length L Ch R = 1 ,95131   ,533,533,533
BEGIN DESCRIPTION:
CLEAR FORK SANDIES CREEK 105.0
END DESCRIPTION:
XS GIS Cut Line= 3
      2339274.99     13670524.99        2338475.       13668975.
      2337675.01       13669225.
#Sta/Elev= 30
  3260.9  420.53  3440.8  416.57  3645.8  407.52  3732.9  404.93  3861.7  401.31
    3989  399.54  4182.8  401.51  4271.4   400.1  4467.9  399.52  4553.8  399.85
    4752  396.77  4797.5  397.43  4813.9  398.61  4841.8   399.1  4902.6  399.07
  4908.3  399.83  4954.8  396.87  4980.8  394.32  4981.3  393.82  5001.3  393.82
  5001.8  394.32  5002.3  396.28  5047.1  397.47    5068  399.08  5145.1     399
  5331.6  401.06  5456.2  404.74  5594.5  411.56  5762.1  422.62  5843.3  428.91
#Mann= 9 ,-1 , 0
  3260.9    .035       0  3732.9     .07       0  4467.9      .1       0
  4954.8     .07       0  4980.8     .05       0  5001.8     .07       0
  5145.1     .05       0  5331.6     .07       0  5456.2     .05       0
Bank Sta=4980.8,5001.8
XS Rating Curve= 0 ,0
Exp/Cntr=0.3,0.1

Type RM Length L Ch R = 1 ,94598   ,543,543,543
BEGIN DESCRIPTION:
CLEAR FORK SANDIES CREEK 104.0
END DESCRIPTION:
XS GIS Cut Line= 3
      2339475.01     13671075.05        2338875.       13668675.
      2338224.99     13667874.99
#Sta/Elev= 30
  2526.4   432.9  2540.8  432.68  2549.6  433.17  2668.2  430.78  2938.8  423.47
  3037.8  424.11  3250.6  420.53  3327.9   420.3  3414.3  415.29  3497.6  411.54
  3608.8  407.08  3639.7  407.12  3704.1  405.07  3805.2  403.42  3951.5  401.16
  4240.1  398.69  4715.3  398.86  4812.2  397.76    4941  397.86  4959.1  396.75
  4971.8  393.02  4972.3  392.52  4992.8  393.02  4997.7  395.57  5040.3  395.99
  5384.6  398.69    5562  401.37  5718.6   405.7  5871.1  412.91  6031.1   418.4
#Mann= 11 ,-1 , 0
  2526.4    .035       0  2540.8     .07       0  3037.8    .035       0
  3414.3     .07       0  3497.6    .035       0  3805.2     .07       0
  4715.3      .1       0  4971.8     .05       0  4992.8      .1       0
  5040.3     .07       0  5871.1     .05       0
Bank Sta=4971.8,4992.8
XS Rating Curve= 0 ,0
Exp/Cntr=0.3,0.1

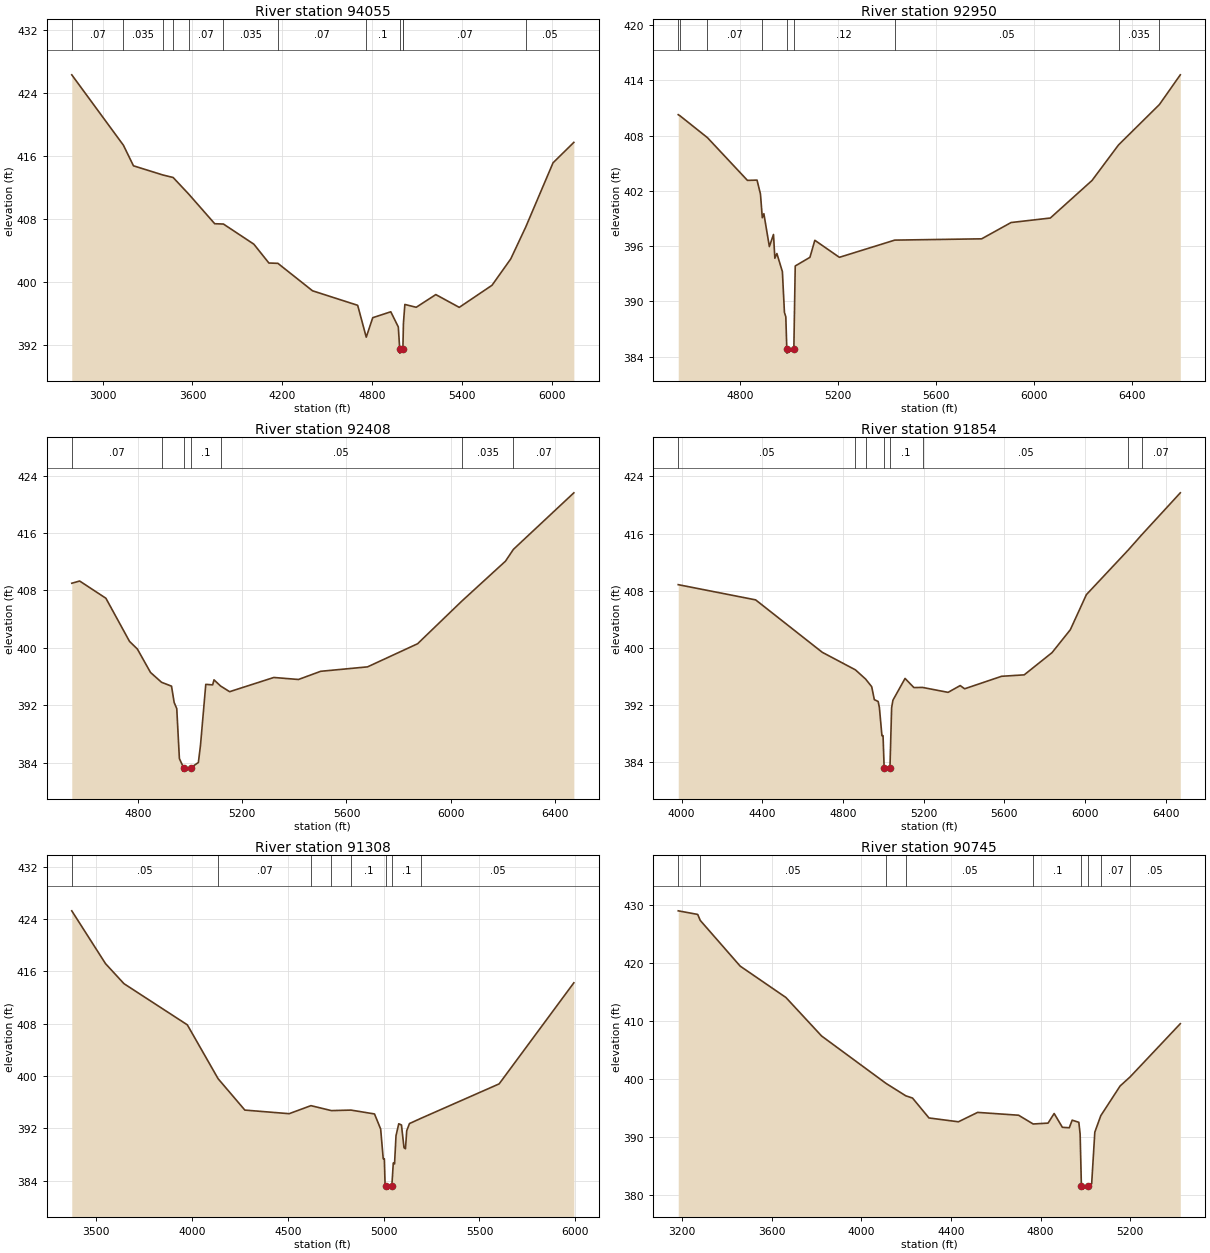
Type RM Length L Ch R = 1 ,94055   ,1105,1105,1105
BEGIN DESCRIPTION:
CLEAR FORK SANDIES CREEK 103.0
END DESCRIPTION:
XS GIS Cut Line= 3
        2339425.     13670525.03        2339225.       13668325.
      2338224.97     13667774.99
#Sta/Elev= 30
  2794.7  426.27  3139.6  417.34  3206.4  414.74    3404  413.57  3471.1  413.26
  3575.4  411.15  3748.6   407.4  3806.8  407.36  4009.7  404.81  4110.1  402.42
  4170.1  402.38  4401.3   398.9  4702.6  397.06  4759.8  393.02    4803  395.49
  4923.5  396.24  4973.7  394.32  4983.2   391.5  4983.7     391  5004.3   391.5
  5007.9  394.77  5017.5  397.17  5093.3  396.81    5224  398.42  5380.4   396.8
  5599.1   399.6  5724.1  402.94    5824  406.98  6006.3  415.12  6145.1  417.71
#Mann= 12 ,-1 , 0
  2794.7     .07       0  3139.6    .035       0    3404     .07       0
  3471.1    .035       0  3575.4     .07       0  3806.8    .035       0
  4170.1     .07       0  4759.8      .1       0  4983.2     .05       0
  5004.3      .1       0  5007.9     .07       0    5824     .05       0
Bank Sta=4983.2,5004.3
XS Rating Curve= 0 ,0
Exp/Cntr=0.3,0.1

Type RM Length L Ch R = 1 ,92950   ,542,542,542
BEGIN DESCRIPTION:
CLEAR FORK SANDIES CREEK 102.0
END DESCRIPTION:
XS GIS Cut Line= 3
      2340174.98     13669174.96        2339975.       13668775.
        2340025.     13667175.05
#Sta/Elev= 30
  4548.7  410.28  4556.3  410.15    4668  407.78    4831  403.14  4870.1  403.17
  4884.1  401.66  4891.6  399.08    4898  399.52  4920.4  395.95  4937.2  397.26
  4942.8  394.68  4951.1  395.19  4973.5  393.23  4981.9  388.79  4987.5  388.32
  4991.5  384.87    4992  384.37  5020.3  384.87  5025.9  393.84  5085.9  394.78
  5105.9  396.63    5206  394.78  5431.8  396.65  5786.3  396.79  5906.3  398.56
  6066.4  399.05  6236.5  403.13  6344.5  406.99  6511.3  411.38  6596.6  414.61
#Mann= 9 ,-1 , 0
  4548.7     .07       0  4556.3     .05       0    4668     .07       0
  4891.6     .12       0  4991.5     .05       0  5020.3     .12       0
  5431.8     .05       0  6344.5    .035       0  6511.3     .07       0
Bank Sta=4991.5,5020.3
XS Rating Curve= 0 ,0
Exp/Cntr=0.3,0.1

Type RM Length L Ch R = 1 ,92408   ,554,554,554
BEGIN DESCRIPTION:
CLEAR FORK SANDIES CREEK 101.0
END DESCRIPTION:
XS GIS Cut Line= 3
        2340375.     13668874.99        2340325.       13668425.
      2340074.99     13666974.95
#Sta/Elev= 30
  4547.2     409  4577.4  409.31    4678  406.91  4768.5   400.9  4798.7  399.83
    4849  396.57  4891.2   395.2  4929.5  394.66  4939.6  392.39  4949.6  391.53
  4959.7  384.56  4975.5  383.32    4976  382.82  5004.3  383.32  5032.4  384.02
  5040.5   386.4  5060.8  394.91  5087.2  394.84  5092.3  395.54  5117.5  394.68
  5152.2  393.89  5321.6  395.87    5416  395.59  5501.2  396.73  5680.9  397.35
  5872.6  400.57  6042.6  406.53  6209.5  412.08  6239.7  413.72  6471.4   421.6
#Mann= 7 ,-1 , 0
  4547.2     .07       0  4891.2      .1       0  4975.5     .05       0
  5004.3      .1       0  5117.5     .05       0  6042.6    .035       0
  6239.7     .07       0
Bank Sta=4975.5,5004.3
XS Rating Curve= 0 ,0
Exp/Cntr=0.3,0.1

Type RM Length L Ch R = 1 ,91854   ,546,546,546
BEGIN DESCRIPTION:
CLEAR FORK SANDIES CREEK 100.0
END DESCRIPTION:
XS GIS Cut Line= 3
        2341175.       13669225.        2340825.       13668275.
        2340125.       13666975.
#Sta/Elev= 30
  3983.7  408.84  4367.4  406.71  4697.7  399.37  4862.1  396.91  4912.6  395.62
  4942.8  394.55  4955.8  392.74  4974.8  392.48  4980.9  391.64  4993.5  387.69
    4999  387.69  5004.4  383.23  5004.9  382.73  5033.3  383.23  5041.5   391.6
    5048  392.66  5108.1  395.71  5151.9  394.43  5194.7  394.45  5321.4  393.76
  5381.5  394.71  5403.4  394.26  5586.7  396.01  5698.7  396.21  5836.6  399.32
  5927.4  402.53  6006.9  407.44  6214.1  413.68  6283.8   415.9  6472.6   421.7
#Mann= 8 ,-1 , 0
  3983.7     .05       0  4862.1    .035       0  4912.6      .1       0
  5004.4     .05       0  5033.3      .1       0  5194.7     .05       0
  6214.1    .035       0  6283.8     .07       0
Bank Sta=5004.4,5033.3
XS Rating Curve= 0 ,0
Exp/Cntr=0.3,0.1

Type RM Length L Ch R = 1 ,91308   ,563,563,563
BEGIN DESCRIPTION:
CLEAR FORK SANDIES CREEK 99.0
END DESCRIPTION:
XS GIS Cut Line= 3
      2342624.96     13668324.99        2341075.       13667825.
      2340324.98     13667174.98
#Sta/Elev= 30
  3371.5  425.27  3547.7  417.19  3643.9  414.13  3974.8  407.83  4135.2   399.6
  4275.1  394.79  4506.3  394.24  4620.1  395.47  4726.7  394.71  4829.1  394.79
    4952   394.2  4984.1  391.89  4997.5  387.34  5003.4  387.34  5007.2  383.27
  5013.6   383.2  5014.1   382.7  5042.5   383.2    5050   386.7  5056.6  386.56
  5064.2  390.87  5078.5   392.7  5092.7  392.51    5106  389.03  5113.6  388.88
  5120.2  391.64  5134.5  392.73  5193.7  393.52  5602.7   398.8  5992.6  414.26
#Mann= 8 ,-1 , 0
  3371.5     .05       0  4135.2     .07       0  4620.1     .05       0
  4726.7     .07       0  4829.1      .1       0  5013.6     .05       0
  5042.5      .1       0  5193.7     .05       0
Bank Sta=5013.6,5042.5
XS Rating Curve= 0 ,0
Exp/Cntr=0.3,0.1

Type RM Length L Ch R = 1 ,90745   ,560,560,560
BEGIN DESCRIPTION:
CLEAR FORK SANDIES CREEK 98.0
END DESCRIPTION:
XS GIS Cut Line= 3
      2342725.01       13668275.        2341175.       13667325.
      2340875.03     13667025.03
#Sta/Elev= 30
  3181.8  428.91  3268.8  428.29  3280.1  427.26  3458.4  419.38  3662.7  413.97
    3822  407.33  4110.1  399.15  4197.9  397.02  4228.1  396.63  4301.6   393.2
  4433.1  392.54  4518.9  394.16  4701.9  393.67  4766.9  392.16  4833.4  392.31
  4860.6  393.97  4897.3  391.59  4928.2  391.51  4941.1  392.82  4970.8  392.45
  4976.6  390.44  4982.3  381.43  4982.8  380.93  5011.3  381.43  5028.1  381.84
  5042.2  390.75  5068.8  393.59  5155.3  398.72  5199.6  400.27    5424  409.45
#Mann= 9 ,-1 , 0
  3181.8    .035       0  3280.1     .05       0  4110.1     .07       0
  4197.9     .05       0  4766.9      .1       0  4982.3     .05       0
  5011.3      .1       0  5068.8     .07       0  5199.6     .05       0
Bank Sta=4982.3,5011.3
XS Rating Curve= 0 ,0
Exp/Cntr=0.3,0.1

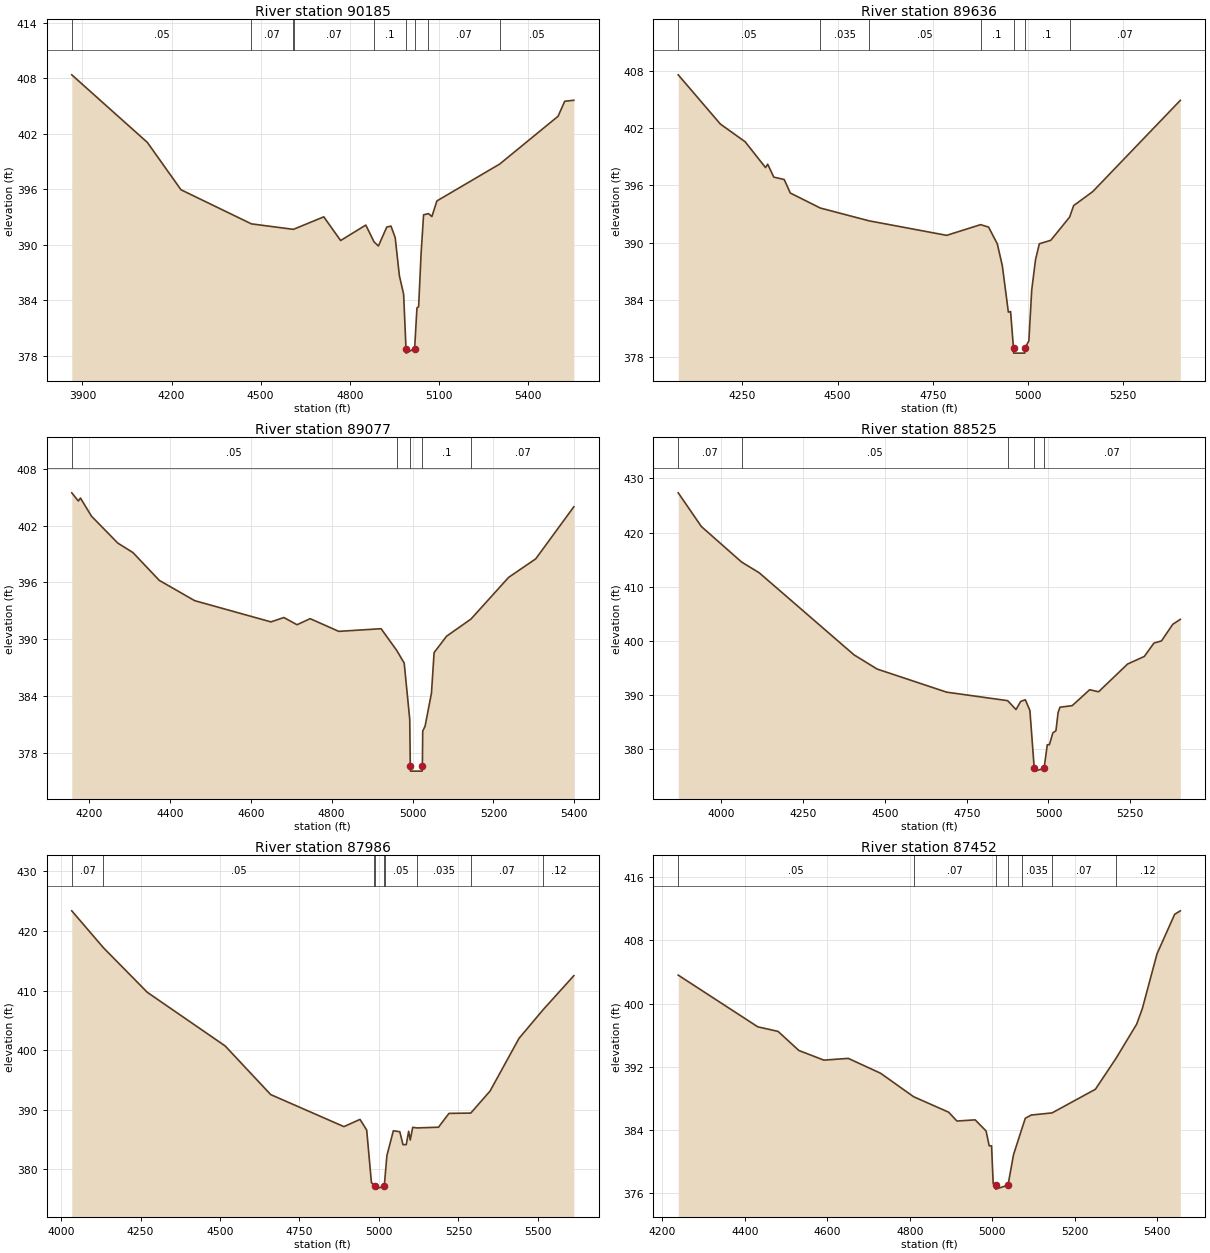
Type RM Length L Ch R = 1 ,90185   ,549,549,549
BEGIN DESCRIPTION:
CLEAR FORK SANDIES CREEK 97.0
END DESCRIPTION:
XS GIS Cut Line= 3
      2342374.97     13667774.97        2341575.       13666975.
      2341325.02     13666475.04
#Sta/Elev= 30
  3864.1  408.39  4118.6  401.08  4231.8  395.96  4468.9  392.27  4609.3  391.68
  4611.2  391.69  4712.6  393.03  4769.2  390.47    4854  392.14  4881.7  390.33
  4896.4  389.88  4924.7  391.93  4938.9  392.03    4953  390.77  4967.1  386.66
  4981.3  384.67  4989.3  378.79  4989.8  378.29  5018.4  378.79  5026.2  383.19
  5031.8  383.31  5040.2  389.08  5048.5  393.25    5065  393.38  5076.5  393.06
  5093.3  394.75  5304.8  398.74  5501.3  403.91  5523.7  405.53  5554.4  405.64
#Mann= 9 ,-1 , 0
  3864.1     .05       0  4468.9     .07       0  4609.3     .05       0
  4611.2     .07       0  4881.7      .1       0  4989.3     .05       0
  5018.4      .1       0    5065     .07       0  5304.8     .05       0
Bank Sta=4989.3,5018.4
XS Rating Curve= 0 ,0
Exp/Cntr=0.3,0.1

Type RM Length L Ch R = 1 ,89636   ,559,559,559
BEGIN DESCRIPTION:
CLEAR FORK SANDIES CREEK 96.0
END DESCRIPTION:
XS GIS Cut Line= 3
      2342524.98     13667624.96        2342075.       13666825.
        2342075.     13666425.04
#Sta/Elev= 30
  4081.8  407.56  4192.4  402.41  4257.4  400.56  4310.9  397.86  4316.6  398.21
  4332.6  396.86    4360  396.61  4375.9   395.2  4454.5  393.63  4582.4  392.29
  4786.4  390.77  4875.4  391.89  4896.4  391.63  4919.3  389.88  4932.4   387.6
  4948.3  382.74  4954.1   382.8  4961.8  378.95  4962.3  378.45  4991.1  378.45
  4991.6  378.95  5002.1  379.74  5009.6  385.05  5019.6  388.23  5029.6  389.89
  5059.6  390.25  5109.1  392.68  5119.6  393.88  5169.6  395.34  5399.6  404.89
#Mann= 7 ,-1 , 0
  4081.8     .05       0  4454.5    .035       0  4582.4     .05       0
  4875.4      .1       0  4961.8     .05       0  4991.6      .1       0
  5109.1     .07       0
Bank Sta=4961.8,4991.6
XS Rating Curve= 0 ,0
Exp/Cntr=0.3,0.1

Type RM Length L Ch R = 1 ,89077   ,552,552,552
BEGIN DESCRIPTION:
CLEAR FORK SANDIES CREEK 95.0
END DESCRIPTION:
XS GIS Cut Line= 3
      2342775.01     13667475.03        2342525.       13666675.
        2342325.       13666325.
#Sta/Elev= 30
  4157.4  405.46  4173.7   404.6  4178.9  404.91  4206.1     403  4271.1  400.16
  4308.8  399.15  4373.8  396.22  4461.3  394.08  4649.8  391.84  4681.8   392.3
  4714.3  391.54  4746.8  392.18  4817.5  390.84  4922.2  391.12  4960.8  388.83
  4979.3  387.49    4993  381.55  4994.4  376.59  4994.9  376.09  5023.7  376.09
  5024.2  376.59  5025.1  380.32  5030.9  380.83  5046.7  384.33  5053.2   388.6
  5084.1  390.33  5144.4  392.14  5237.5  396.54  5304.4  398.49  5398.7  403.99
#Mann= 5 ,-1 , 0
  4157.4     .05       0  4960.8      .1       0  4994.4     .05       0
  5024.2      .1       0  5144.4     .07       0
Bank Sta=4994.4,5024.2
XS Rating Curve= 0 ,0
Exp/Cntr=0.3,0.1

Type RM Length L Ch R = 1 ,88525   ,539,539,539
BEGIN DESCRIPTION:
CLEAR FORK SANDIES CREEK 94.0
END DESCRIPTION:
XS GIS Cut Line= 3
      2343775.02     13667275.02        2342975.       13666475.
        2342775.     13666125.01
#Sta/Elev= 30
  3868.4  427.33  3939.1  421.11  4062.1  414.55  4115.9  412.57  4405.8  397.41
  4476.5  394.79  4688.7  390.53  4875.2  388.96  4900.8  387.32  4914.9  388.81
  4929.1  389.13  4943.2  387.16  4956.5  376.45    4957  375.95  4986.5  376.45
  4996.3  380.82  5002.7  380.82  5013.5  383.03  5022.8  383.41  5029.3  386.76
  5035.1  387.75  5072.5  388.04  5125.8  390.98  5153.1   390.6  5241.7  395.72
  5292.8  397.12  5322.3  399.59  5345.3  399.99  5379.9  403.06  5402.9  403.97
#Mann= 5 ,-1 , 0
  3868.4     .07       0  4062.1     .05       0  4875.2     .07       0
  4956.5     .05       0  4986.5     .07       0
Bank Sta=4956.5,4986.5
XS Rating Curve= 0 ,0
Exp/Cntr=0.3,0.1

Type RM Length L Ch R = 1 ,87986   ,534,534,534
BEGIN DESCRIPTION:
CLEAR FORK SANDIES CREEK 93.0
END DESCRIPTION:
XS GIS Cut Line= 3
      2343975.03     13667025.04        2343425.       13666225.
      2343325.01     13665625.05
#Sta/Elev= 30
  4033.8  423.39  4133.5  417.19  4271.3  409.72  4516.2  400.72  4659.6  392.55
  4889.7  387.18  4940.4  388.39  4961.4   386.6  4976.3  377.78  4985.9  377.35
  4986.6  377.19  4987.1  376.69  5016.7  377.19  5019.8  379.13  5024.9  382.31
  5045.2  386.48  5065.5  386.32  5075.6  384.15  5085.8  384.16  5093.4   386.4
  5098.4  384.93  5106.1  387.06  5120.1  386.96  5187.2  387.08  5220.1   389.4
  5288.7  389.45  5349.4  393.15  5440.6     402  5516.8  406.83  5612.9  412.51
#Mann= 9 ,-1 , 0
  4033.8     .07       0  4133.5     .05       0  4985.9     .07       0
  4986.6     .05       0  5016.7     .07       0  5019.8     .05       0
  5120.1    .035       0  5288.7     .07       0  5516.8     .12       0
Bank Sta=4986.6,5016.7
XS Rating Curve= 0 ,0
Exp/Cntr=0.3,0.1

Type RM Length L Ch R = 1 ,87452   ,540,540,540
BEGIN DESCRIPTION:
CLEAR FORK SANDIES CREEK 92.0
END DESCRIPTION:
XS GIS Cut Line= 3
        2343875.     13666625.01        2343775.       13665875.
      2343425.02     13665575.01
#Sta/Elev= 30
  4238.7  403.61  4431.6  397.06  4480.8  396.48  4531.3  394.06  4591.8  392.84
  4651.1  393.06  4729.3  391.18  4809.6   388.2  4894.5  386.24  4914.6  385.12
  4958.8  385.27  4985.3  383.86  4992.8  381.98  4998.6  381.98  5002.5  377.18
  5008.2  376.99  5008.7  376.49  5038.4  376.99  5051.9  380.87  5072.6  384.23
  5080.4  385.47  5094.7  385.88  5145.3  386.15  5250.5  389.15  5300.3  393.06
  5350.4  397.39  5364.1  399.35  5399.8  406.31  5442.6  411.32  5456.3  411.76
#Mann= 7 ,-1 , 0
  4238.7     .05       0  4809.6     .07       0  5008.2     .05       0
  5038.4     .07       0  5072.6    .035       0  5145.3     .07       0
  5300.3     .12       0
Bank Sta=5008.2,5038.4
XS Rating Curve= 0 ,0
Exp/Cntr=0.3,0.1

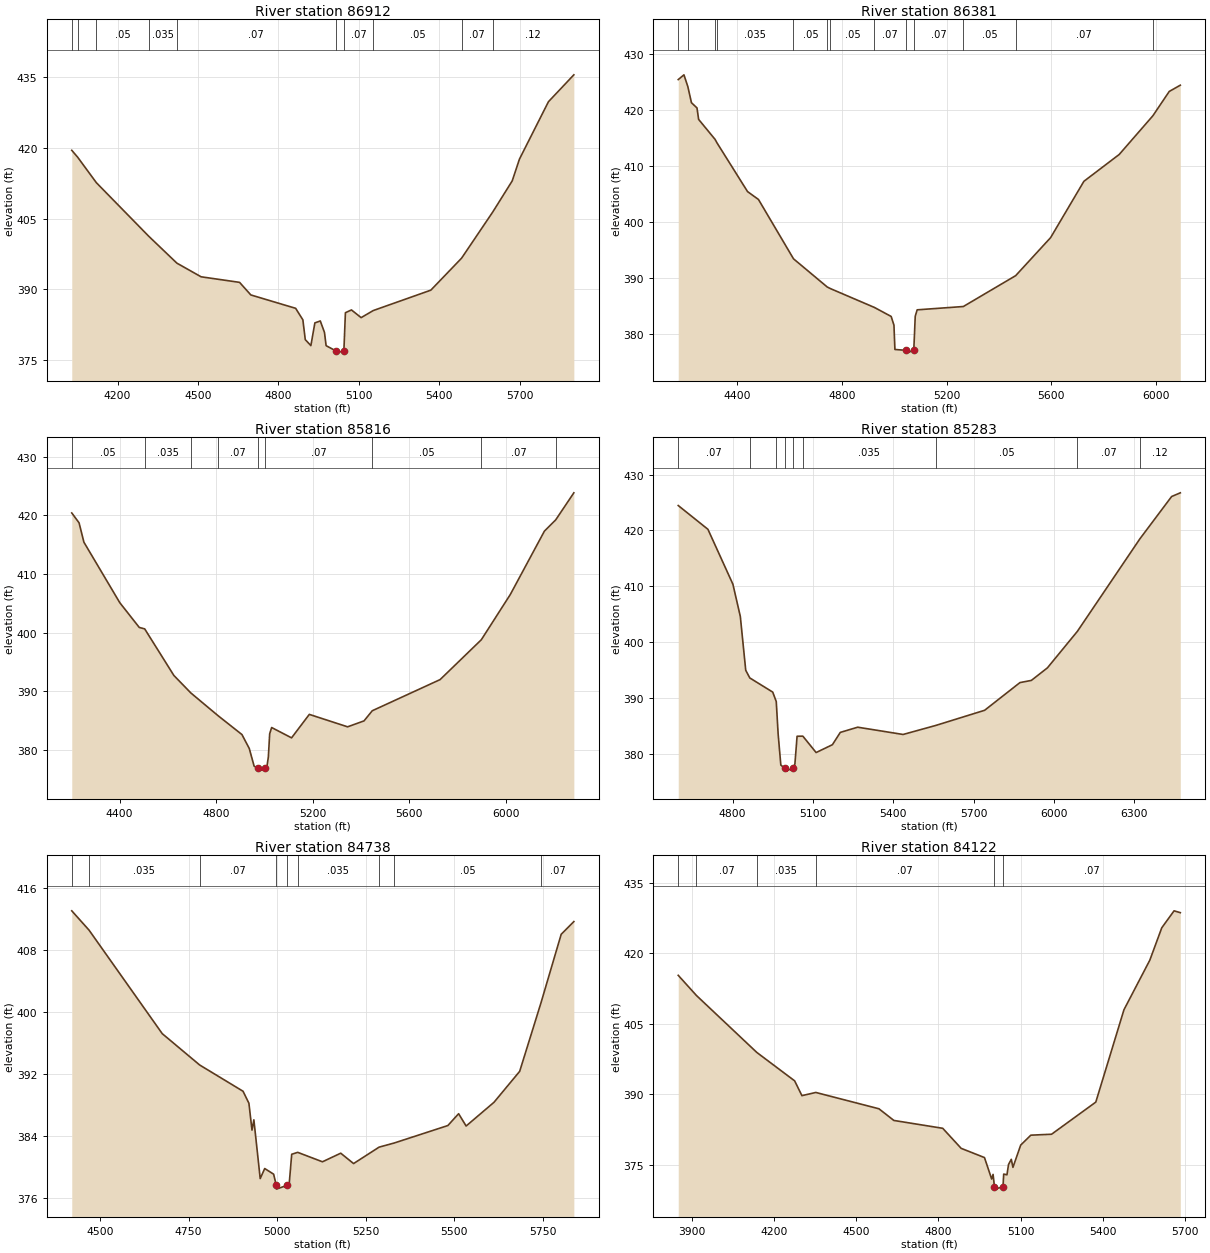
Type RM Length L Ch R = 1 ,86912   ,531,531,531
BEGIN DESCRIPTION:
CLEAR FORK SANDIES CREEK 91.0
END DESCRIPTION:
XS GIS Cut Line= 3
      2344974.97     13666124.98        2344175.       13665575.
      2343424.98     13665074.99
#Sta/Elev= 30
  4029.2  419.43  4050.8     418  4120.9  412.58  4316.4  401.24  4421.1  395.56
  4511.5  392.67    4655  391.49  4696.9  388.83    4864     386    4891  383.56
  4899.9  379.38  4920.8  378.11  4935.7  382.91  4955.9  383.33  4971.6  380.89
  4977.6   378.1  5013.1  377.02  5013.6  376.52  5043.9  377.02  5049.6  385.07
  5072.1  385.66  5108.2  384.03  5153.5  385.53  5368.1  389.84  5482.8  396.61
  5598.8  406.36  5671.5  412.95  5698.6  417.57  5806.7  429.71  5901.4   435.4
#Mann= 10 ,-1 , 0
  4029.2     .05       0  4050.8     .07       0  4120.9     .05       0
  4316.4    .035       0  4421.1     .07       0  5013.1     .05       0
  5043.9     .07       0  5153.5     .05       0  5482.8     .07       0
  5598.8     .12       0
Bank Sta=5013.1,5043.9
XS Rating Curve= 0 ,0
Exp/Cntr=0.3,0.1

Type RM Length L Ch R = 1 ,86381   ,565,565,565
BEGIN DESCRIPTION:
CLEAR FORK SANDIES CREEK 90.0
END DESCRIPTION:
XS GIS Cut Line= 3
      2345125.02     13666075.02        2344625.       13665425.
      2343874.98     13664624.98
#Sta/Elev= 30
  4175.8  425.49  4197.6  426.34  4212.5  424.23  4226.3  421.36  4247.4  420.43
  4253.7  418.38  4316.4  414.82  4324.2  414.16  4440.5  405.49  4482.1  404.09
  4615.8   393.5  4744.5  388.47  4756.7  388.18  4924.5  384.82  4988.6  383.21
  4999.3  381.66    5003  377.31  5044.2  377.16  5044.7  376.66    5075  377.16
  5080.6  383.26    5088  384.39  5264.2  384.98    5464  390.49  5597.4  397.28
  5724.4  407.33  5859.2  412.12  5987.6  419.02  6050.2  423.37  6092.5  424.49
#Mann= 13 ,-1 , 0
  4175.8     .05       0  4212.5    .035       0  4316.4     .05       0
  4324.2    .035       0  4615.8     .05       0  4744.5     .07       0
  4756.7     .05       0  4924.5     .07       0  5044.2     .05       0
    5075     .07       0  5264.2     .05       0    5464     .07       0
  5987.6     .12       0
Bank Sta=5044.2,5075
XS Rating Curve= 0 ,0
Exp/Cntr=0.3,0.1

Type RM Length L Ch R = 1 ,85816   ,533,533,533
BEGIN DESCRIPTION:
CLEAR FORK SANDIES CREEK 89.0
END DESCRIPTION:
XS GIS Cut Line= 3
        2345175.     13665974.99        2345075.       13665175.
      2343924.98     13664624.99
#Sta/Elev= 30
  4201.6   420.4  4231.8  418.72    4252  415.41  4400.6  405.11  4481.3  400.89
  4503.9  400.64  4624.9   392.7  4695.3  389.72  4808.5  385.83    4907  382.63
  4937.3  380.26  4957.4  377.25  4972.3   376.9  4972.8   376.4  5003.1   376.9
  5010.6  377.22  5016.4  378.81  5021.9  382.76    5030  383.83  5112.6  382.07
  5186.2  386.07  5344.9  383.95  5412.9  384.96  5447.1  386.69  5728.3     392
  5899.1  398.79  6019.1  406.49  6160.6   417.3  6207.4  419.22  6282.6  423.83
#Mann= 9 ,-1 , 0
  4201.6     .05       0  4503.9    .035       0  4695.3     .05       0
  4808.5     .07       0  4972.3     .05       0  5003.1     .07       0
  5447.1     .05       0  5899.1     .07       0  6207.4     .12       0
Bank Sta=4972.3,5003.1
XS Rating Curve= 0 ,0
Exp/Cntr=0.3,0.1

Type RM Length L Ch R = 1 ,85283   ,545,545,545
BEGIN DESCRIPTION:
CLEAR FORK SANDIES CREEK 88.0
END DESCRIPTION:
XS GIS Cut Line= 3
      2345725.03       13664875.        2345325.       13664825.
      2343875.03     13664575.01
#Sta/Elev= 30
  4597.3  424.46  4708.2  420.21  4801.4   410.4  4829.1  404.64  4849.3  395.02
  4864.5  393.65  4950.1  391.12  4963.3  389.43  4970.2   383.7  4980.3  378.09
  4995.1   377.5  4995.6     377  5026.1   377.5  5032.9  378.28    5041  383.23
  5062.5  383.25  5112.1  380.32  5172.9  381.72  5202.4  383.92  5267.3  384.85
  5436.8  383.55  5559.3  385.17  5741.2  387.87  5873.1  392.82  5915.7  393.21
  5975.6  395.45  6087.7  401.99  6320.6  418.49  6439.4  426.07  6471.8  426.73
#Mann= 9 ,-1 , 0
  4597.3     .07       0  4864.5    .035       0  4963.3     .12       0
  4995.1     .05       0  5026.1     .12       0  5062.5    .035       0
  5559.3     .05       0  6087.7     .07       0  6320.6     .12       0
Bank Sta=4995.1,5026.1
XS Rating Curve= 0 ,0
Exp/Cntr=0.3,0.1

Type RM Length L Ch R = 1 ,84738   ,616,616,616
BEGIN DESCRIPTION:
CLEAR FORK SANDIES CREEK 87.0
END DESCRIPTION:
XS GIS Cut Line= 3
        2345675.       13664575.        2345125.       13664375.
        2344425.       13663925.
#Sta/Elev= 30
  4420.4  413.06  4469.3  410.56  4675.8   397.2  4781.5  393.15  4903.9  389.76
  4920.5  388.21  4929.2  384.74  4934.5  386.07  4952.4  378.48  4965.1  379.78
  4990.3  379.05  4997.7  377.62  4998.2  377.12  5028.7  377.62  5034.4  377.88
  5041.3  381.62  5058.2  381.87  5128.1  380.65  5179.7  381.76    5216  380.42
  5287.9  382.54    5331  383.08  5482.1  385.33  5512.5  386.86  5533.7  385.27
  5612.3  388.33  5684.9  392.33  5745.1  401.19  5802.1  410.03  5837.8  411.67
#Mann= 9 ,-1 , 0
  4420.4     .07       0  4469.3    .035       0  4781.5     .07       0
  4997.7     .05       0  5028.7     .07       0  5058.2    .035       0
  5287.9     .07       0    5331     .05       0  5745.1     .07       0
Bank Sta=4997.7,5028.7
XS Rating Curve= 0 ,0
Exp/Cntr=0.3,0.1

Type RM Length L Ch R = 1 ,84122   ,485,485,485
BEGIN DESCRIPTION:
CLEAR FORK SANDIES CREEK 86.0
END DESCRIPTION:
XS GIS Cut Line= 3
      2346178.61     13664167.89      2345035.18     13663837.09
      2344725.01     13663275.01
#Sta/Elev= 30
  3850.7  415.32    3917  411.04  4137.4  398.93  4275.5  392.89  4302.1  389.74
  4352.8  390.42  4583.2  386.95  4637.6  384.47    4816   382.8  4883.2  378.54
  4968.3  376.58  4994.5  372.02  4999.7     373  5004.8  370.37  5005.3  369.87
  5035.9  370.37  5038.5  373.07  5050.4  372.91  5056.1  375.11  5066.2   376.2
  5072.2   374.5  5100.5  379.23  5137.5  381.34  5213.2  381.54  5374.6  388.37
  5477.4  408.01  5571.8  418.55  5615.4  425.43  5660.2  429.03    5683  428.64
#Mann= 6 ,-1 , 0
  3850.7    .035       0    3917     .07       0  4137.4    .035       0
  4352.8     .07       0  5004.8     .05       0  5035.9     .07       0
Bank Sta=5004.8,5035.9
XS Rating Curve= 0 ,0
Exp/Cntr=0.3,0.1