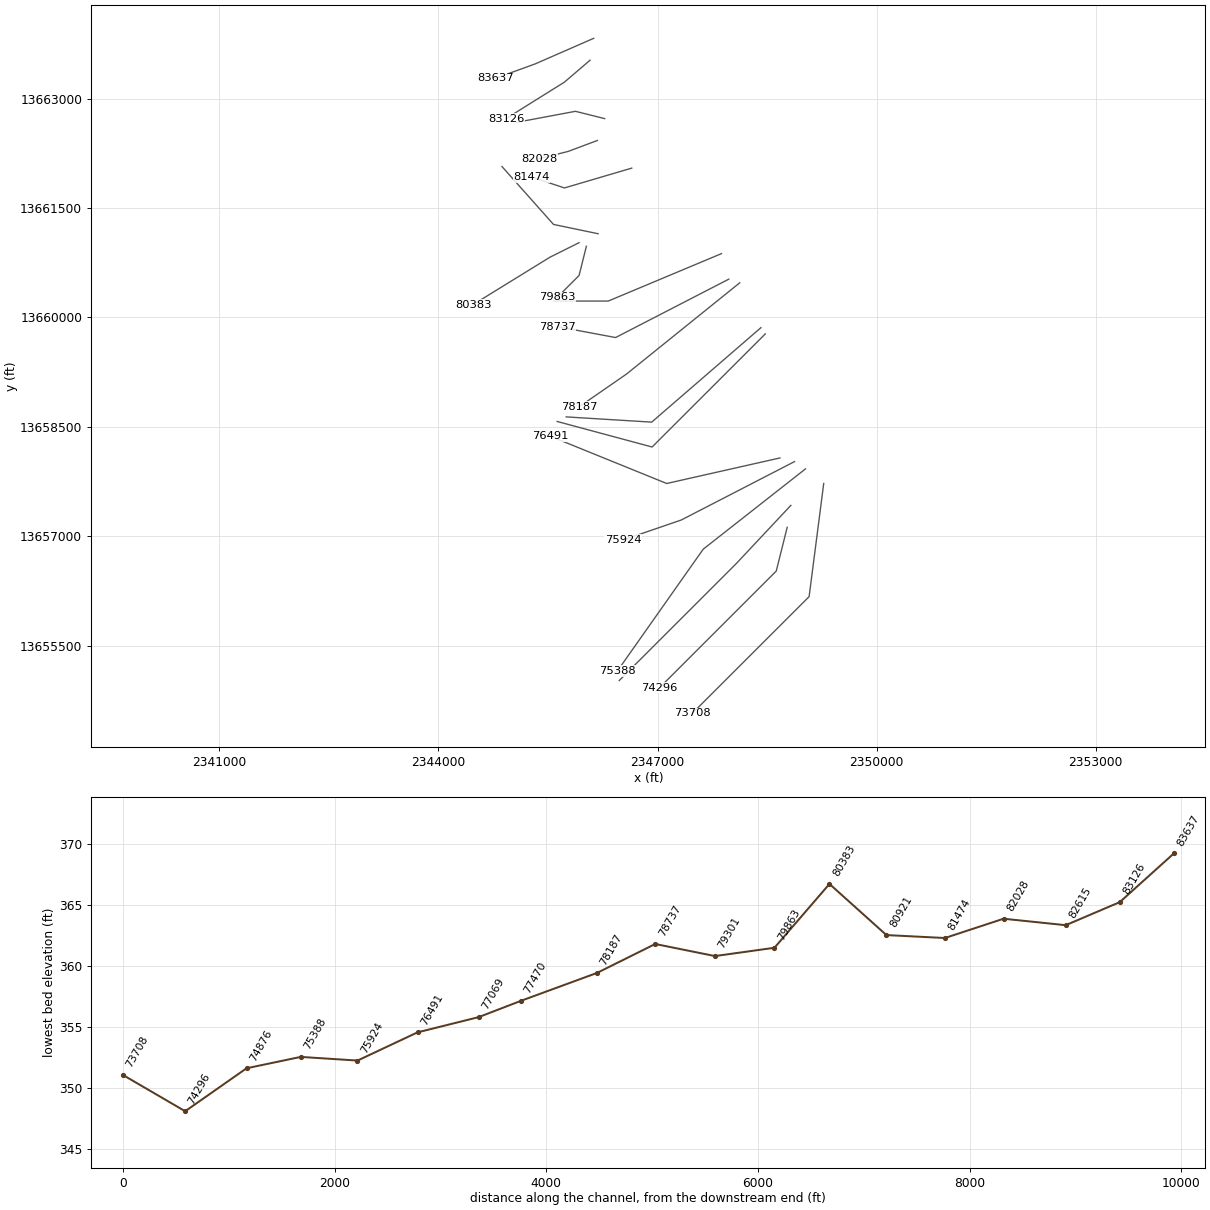
HEC-RAS study CLEAR FORK SANDIES CREEK.prj: CLEAR FORK SANDIES CREEK Base Level Engineering

--- CLEAR FORK SANDIES CREEK.g01 (geometry) --- (continued)

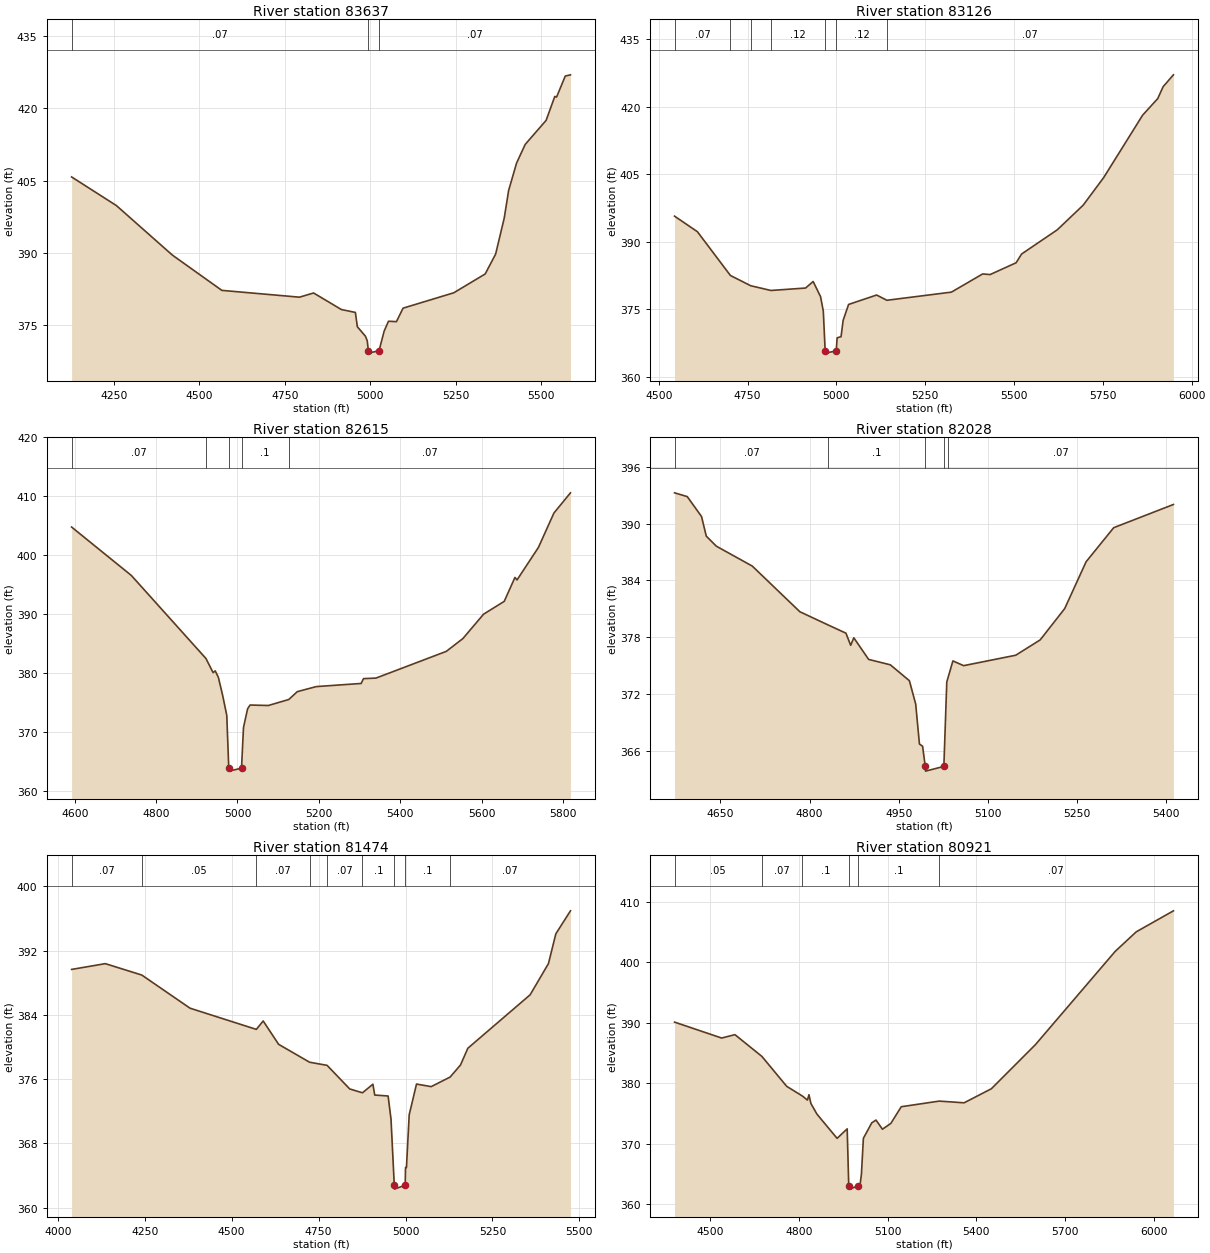
Type RM Length L Ch R = 1 ,83637   ,511,511,511
BEGIN DESCRIPTION:
CLEAR FORK SANDIES CREEK 85.0
END DESCRIPTION:
XS GIS Cut Line= 3
      2346125.01       13663825.        2345325.       13663475.
      2344774.96     13663274.99
#Sta/Elev= 30
  4126.5  405.75  4257.5  399.81  4421.2  389.54  4565.8  382.23  4792.7  380.82
    4834  381.69  4915.1  378.26  4956.1  377.66  4961.9  374.69  4985.3  372.75
  4990.8   371.8  4994.1  369.72  4994.6  369.22  5025.3  369.72  5040.3  373.79
  5052.9  375.83  5076.2  375.75  5095.5  378.54  5243.8  381.73  5335.6  385.63
  5366.2  389.76  5391.4  397.25  5404.1  402.92  5427.3  408.61  5452.6  412.49
  5513.8  417.48  5539.1  422.43  5544.4  422.31  5569.7  426.66    5585  426.92
#Mann= 3 ,-1 , 0
  4126.5     .07       0  4994.1     .05       0  5025.3     .07       0
Bank Sta=4994.1,5025.3
XS Rating Curve= 0 ,0
Exp/Cntr=0.3,0.1

Type RM Length L Ch R = 1 ,83126   ,511,511,511
BEGIN DESCRIPTION:
CLEAR FORK SANDIES CREEK 84.0
END DESCRIPTION:
XS GIS Cut Line= 3
      2346075.04     13663525.03        2345725.       13663225.
      2344925.02     13662725.01
#Sta/Elev= 30
  4544.3  395.68  4608.6  392.23  4701.6  382.49  4758.8  380.21  4815.5  379.16
  4913.1   379.7  4934.5  381.15  4955.4  377.78  4963.1  374.54  4968.3  365.73
  4968.8  365.23  4999.5  365.73    5002  368.64    5013  368.88  5018.9  372.51
  5034.2  376.05  5113.2  378.15    5142  376.98  5323.7  378.79  5411.6  382.83
  5432.8   382.7  5505.9  385.32  5521.2  387.26  5621.5  392.63  5694.6  398.12
  5752.4  404.26    5862  418.13  5904.5  421.82  5919.8  424.47  5948.7   427.1
#Mann= 7 ,-1 , 0
  4544.3     .07       0  4701.6     .12       0  4758.8     .07       0
  4815.5     .12       0  4968.3     .05       0  4999.5     .12       0
    5142     .07       0
Bank Sta=4968.3,4999.5
XS Rating Curve= 0 ,0
Exp/Cntr=0.3,0.1

Type RM Length L Ch R = 1 ,82615   ,587,587,587
BEGIN DESCRIPTION:
CLEAR FORK SANDIES CREEK 83.0
END DESCRIPTION:
XS GIS Cut Line= 3
      2346274.98     13662725.01        2345875.       13662825.
      2345075.03       13662675.
#Sta/Elev= 30
  4592.4  404.77  4739.3  396.55  4922.6  382.46  4940.3  380.05  4945.4  380.36
  4953.1  379.27  4963.5  376.25  4973.8  372.81  4978.7  363.84  4979.2  363.34
    5010  363.84  5014.9  370.76    5025  373.92    5031  374.56  5075.9  374.48
  5126.3   375.5  5147.1  376.83  5193.8  377.69    5304  378.22  5309.9  379.04
  5340.4  379.13  5513.4  383.67  5554.1  385.84    5605  389.98  5655.8  392.16
  5682.1  396.22  5687.2  395.79  5739.8  401.31  5777.9  407.15  5818.6  410.58
#Mann= 5 ,-1 , 0
  4592.4     .07       0  4922.6      .1       0  4978.7     .05       0
    5010      .1       0  5126.3     .07       0
Bank Sta=4978.7,5010
XS Rating Curve= 0 ,0
Exp/Cntr=0.3,0.1

Type RM Length L Ch R = 1 ,82028   ,554,554,554
BEGIN DESCRIPTION:
CLEAR FORK SANDIES CREEK 82.0
END DESCRIPTION:
XS GIS Cut Line= 3
        2346175.       13662425.        2345775.       13662275.
      2345375.01       13662175.
#Sta/Elev= 30
  4572.9  393.24  4594.3  392.84  4618.3  390.74  4626.3  388.67  4643.2  387.61
  4703.7  385.51  4783.8  380.69  4831.5  379.29  4861.3  378.43  4869.3  377.15
  4874.6  377.94  4899.5  375.66    4936  375.09  4968.1  373.41  4978.7  370.95
    4985  366.73  4990.3   366.5  4994.8  364.37  4995.3  363.87  5026.1  364.37
    5031  373.27  5033.2  373.75  5041.3   375.5  5059.4     375    5147   376.1
  5188.2  377.72  5229.4  381.02  5265.5  385.97  5311.9  389.56  5412.4  392.01
#Mann= 5 ,-1 , 0
  4572.9     .07       0  4831.5      .1       0  4994.8     .05       0
  5026.1      .1       0  5033.2     .07       0
Bank Sta=4994.8,5026.1
XS Rating Curve= 0 ,0
Exp/Cntr=0.3,0.1

Type RM Length L Ch R = 1 ,81474   ,553,553,553
BEGIN DESCRIPTION:
CLEAR FORK SANDIES CREEK 81.0
END DESCRIPTION:
XS GIS Cut Line= 3
      2346646.05     13662046.46        2345725.       13661775.
      2345274.96     13661925.01
#Sta/Elev= 30
  4039.8  389.66  4136.7  390.38  4241.6  388.96  4380.4  384.83    4571  382.19
  4590.7  383.24  4635.1  380.33  4724.1   378.1  4774.5  377.71  4839.6  374.77
  4876.2  374.29  4906.2  375.36  4911.5  374.01    4950  373.89  4958.3  371.01
  4967.7  362.79  4968.2  362.29  4999.1  362.79    5000  364.98  5002.7  364.98
  5010.6  371.55  5031.6  375.38  5073.8  375.06  5128.2  376.25  5158.1  377.75
  5179.2  379.84  5358.4   386.5  5411.1  390.39  5432.2  394.09  5474.4  396.96
#Mann= 9 ,-1 , 0
  4039.8     .07       0  4241.6     .05       0    4571     .07       0
  4724.1     .05       0  4774.5     .07       0  4876.2      .1       0
  4967.7     .05       0  4999.1      .1       0  5128.2     .07       0
Bank Sta=4967.7,4999.1
XS Rating Curve= 0 ,0
Exp/Cntr=0.3,0.1

Type RM Length L Ch R = 1 ,80921   ,538,538,538
BEGIN DESCRIPTION:
CLEAR FORK SANDIES CREEK 80.0
END DESCRIPTION:
XS GIS Cut Line= 3
      2346185.82     13661147.53        2345575.       13661275.
      2344869.92     13662067.87
#Sta/Elev= 30
  4380.7   390.1  4539.8  387.47  4584.7  388.03  4675.9  384.43  4759.5   379.5
  4812.4   377.9  4829.6  377.23  4834.7  378.11  4841.2  376.67  4861.7  374.91
  4929.7  370.91  4963.8  372.48  4969.1  363.03  4969.6  362.53  5000.5  363.03
    5008  363.51  5011.8  364.95  5018.5  370.92  5046.9  373.48  5061.1  373.93
  5082.9  372.42  5111.3  373.38  5146.4  376.13  5274.5  377.06  5358.8  376.78
  5450.8   379.1  5599.6  386.38  5868.9  401.77    5940     405  6065.7  408.47
#Mann= 6 ,-1 , 0
  4380.7     .05       0  4675.9     .07       0  4812.4      .1       0
  4969.1     .05       0  5000.5      .1       0  5274.5     .07       0
Bank Sta=4969.1,5000.5
XS Rating Curve= 0 ,0
Exp/Cntr=0.3,0.1

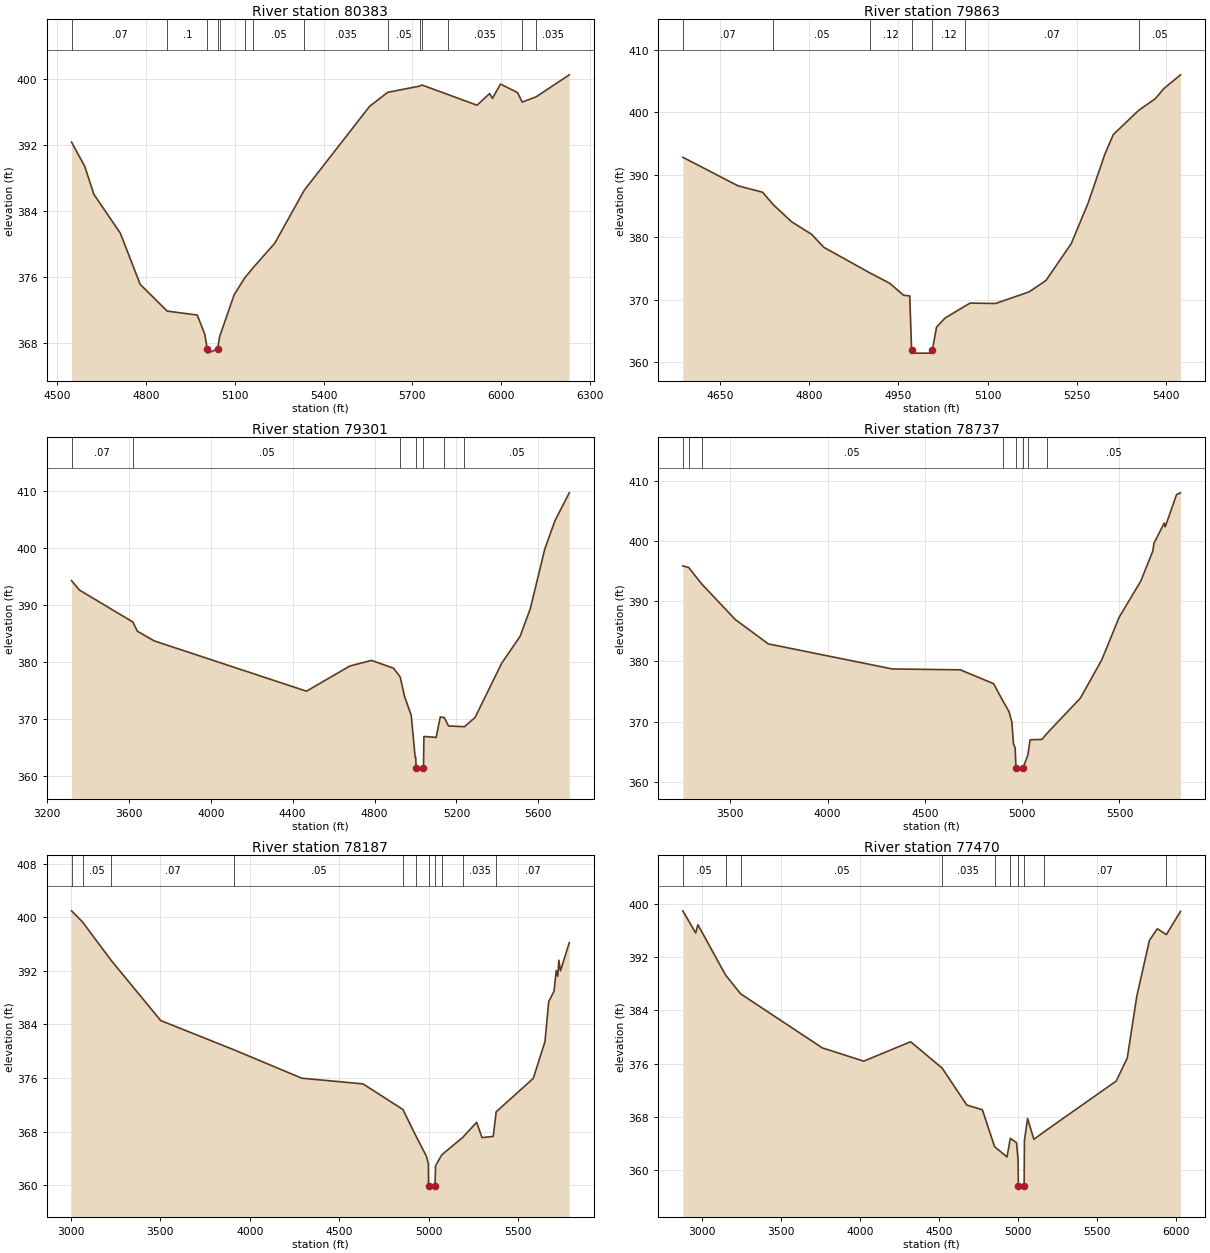
Type RM Length L Ch R = 1 ,80383   ,520,520,520
BEGIN DESCRIPTION:
CLEAR FORK SANDIES CREEK 79.0
END DESCRIPTION:
XS GIS Cut Line= 3
      2345925.02     13661025.01        2345525.       13660825.
      2344474.23      13660176.7
#Sta/Elev= 30
  4548.1  392.32  4592.8  389.37  4623.6  385.98    4713  381.27  4780.1  375.06
  4871.3  371.82    4973  371.34  4998.3     369  5006.9  367.22  5007.6  366.72
  5041.8  367.22  5048.5  368.73  5097.6   373.8  5133.4  375.85  5162.1   377.1
  5234.8  380.05  5334.3  386.47  5555.3  396.66  5616.5  398.36  5724.2  399.11
  5731.8  399.25  5821.7  398.07  5918.4  396.79  5960.9  398.21  5970.4  397.63
  5997.6  399.36  6055.5  398.32  6070.8  397.17    6118  397.81    6230  400.48
#Mann= 14 ,-1 , 0
  4548.1     .07       0  4871.3      .1       0  5006.9     .05       0
  5041.8      .1       0  5048.5     .05       0  5133.4    .035       0
  5162.1     .05       0  5334.3    .035       0  5616.5     .05       0
  5724.2    .035       0  5731.8     .05       0  5821.7    .035       0
  6070.8     .07       0    6118    .035       0
Bank Sta=5006.9,5041.8
XS Rating Curve= 0 ,0
Exp/Cntr=0.3,0.1

Type RM Length L Ch R = 1 ,79863   ,562,562,562
BEGIN DESCRIPTION:
CLEAR FORK SANDIES CREEK 78.0
END DESCRIPTION:
XS GIS Cut Line= 3
      2346025.01     13660975.03        2345925.       13660575.
      2345625.01     13660275.01
#Sta/Elev= 30
  4587.7  392.83  4680.5  388.26  4721.7  387.24  4739.8  385.24  4770.7   382.5
  4804.2   380.5  4824.8  378.42  4902.3  374.32  4935.6  372.66  4958.8  370.75
  4969.1  370.65  4972.3  361.99    4973  361.49  5006.5  361.49  5007.2  361.99
  5014.2  365.65  5028.3  367.09  5062.1  369.02  5070.8   369.5  5113.2  369.43
  5169.8  371.29    5198   373.1  5240.5  378.99  5268.7  385.44    5297  393.29
  5311.2  396.45    5354  400.34  5381.9   402.2    5396   403.8  5424.3  406.02
#Mann= 7 ,-1 , 0
  4587.7     .07       0  4739.8     .05       0  4902.3     .12       0
  4972.3     .05       0  5007.2     .12       0  5062.1     .07       0
    5354     .05       0
Bank Sta=4972.3,5007.2
XS Rating Curve= 0 ,0
Exp/Cntr=0.3,0.1

Type RM Length L Ch R = 1 ,79301   ,564,564,564
BEGIN DESCRIPTION:
CLEAR FORK SANDIES CREEK 77.0
END DESCRIPTION:
XS GIS Cut Line= 3
      2347875.04     13660875.02        2346325.       13660225.
      2345575.01       13660225.
#Sta/Elev= 30
  3320.1  394.22  3358.5  392.57  3619.4  386.97  3641.7  385.34  3723.9  383.65
  4467.5  374.83  4679.4  379.25  4785.3  380.23  4892.5  378.86  4925.1  377.34
  4946.7  373.88  4979.2  370.58  4998.2  363.26  5000.9  363.26    5003  361.31
  5003.8  360.81  5038.9  361.31  5040.9  366.89  5100.9  366.73  5120.9  370.31
  5140.6   370.2  5160.9  368.73    5239   368.6  5290.9  370.23  5420.9  379.74
  5510.9  384.46  5560.9  389.35  5630.9  399.71  5680.9  404.72  5750.9  409.62
#Mann= 7 ,-1 , 0
  3320.1     .07       0  3619.4     .05       0  4925.1      .1       0
    5003     .05       0  5038.9      .1       0  5140.6     .07       0
    5239     .05       0
Bank Sta=5003,5038.9
XS Rating Curve= 0 ,0
Exp/Cntr=0.3,0.1

Type RM Length L Ch R = 1 ,78737   ,550,550,550
BEGIN DESCRIPTION:
CLEAR FORK SANDIES CREEK 76.0
END DESCRIPTION:
XS GIS Cut Line= 3
      2347975.02     13660525.01        2346425.       13659725.
      2345625.04     13659874.99
#Sta/Elev= 30
  3255.7  395.86  3285.7  395.61  3352.1   392.9  3524.2     387  3694.6  382.93
  4332.7  378.76  4681.6  378.62  4853.2  376.32  4899.2  373.55  4932.5  371.67
  4947.4  369.87    4955  366.33    4964  365.63  4968.2   362.3    4969   361.8
  5004.1   362.3  5028.9  364.43  5040.7     367  5101.7  367.07  5129.6  368.14
  5299.3  373.92  5409.5   380.3  5498.5  387.35  5610.5   393.4  5671.5  398.35
  5677.4  399.64    5730  402.97  5735.1  402.35  5793.6  407.72  5813.9     408
#Mann= 8 ,-1 , 0
  3255.7     .05       0  3285.7     .07       0  3352.1     .05       0
  4899.2      .1       0  4968.2     .05       0  5004.1      .1       0
  5028.9     .07       0  5129.6     .05       0
Bank Sta=4968.2,5004.1
XS Rating Curve= 0 ,0
Exp/Cntr=0.3,0.1

Type RM Length L Ch R = 1 ,78187   ,717,717,717
BEGIN DESCRIPTION:
CLEAR FORK SANDIES CREEK 75.0
END DESCRIPTION:
XS GIS Cut Line= 3
      2348125.02     13660475.02        2346575.       13659225.
      2345925.02     13658775.02
#Sta/Elev= 30
    3004  400.95    3066  399.27  3224.4  393.59  3502.2  384.58  3912.3  380.21
  4290.7  375.98    4633  375.13  4856.1  371.31  4926.6  367.47  4988.1   364.3
  4998.3  363.22  4999.6  359.93  5000.4  359.43  5035.5  359.93  5038.5  362.92
    5073  364.54  5190.3  367.15  5268.2   369.4    5298  367.12  5360.8  367.29
  5377.4  370.97  5584.5  375.95    5650  381.43    5671  387.41  5700.7  388.96
  5712.9  392.04  5721.6   391.2  5727.7  393.58  5736.5  391.99  5785.8  396.19
#Mann= 11 ,-1 , 0
    3004     .07       0    3066     .05       0  3224.4     .07       0
  3912.3     .05       0  4856.1     .07       0  4926.6      .1       0
  4999.6     .05       0  5035.5      .1       0    5073     .05       0
  5190.3    .035       0  5377.4     .07       0
Bank Sta=4999.6,5035.5
XS Rating Curve= 0 ,0
Exp/Cntr=0.3,0.1

Type RM Length L Ch R = 1 ,77470   ,401,401,401
BEGIN DESCRIPTION:
CLEAR FORK SANDIES CREEK 74.0
END DESCRIPTION:
XS GIS Cut Line= 3
      2348415.11     13659860.31       2346919.3     13658565.86
      2345748.54     13658637.69
#Sta/Elev= 30
  2877.6  398.92  2959.1   395.6  2973.3  396.83  3148.9  389.26  3244.5  386.45
  3760.8  378.35  4022.9  376.36  4320.2  379.27    4520   375.3  4675.5  369.77
  4774.2  369.06  4851.4  363.53  4930.2  361.98  4951.1  364.77  4990.3  364.12
  5000.3  361.58  5002.1  357.65    5003  357.15  5038.5  357.65  5040.4  364.46
  5060.4  367.75  5100.5  364.62  5162.9  365.72  5621.5  373.37  5691.6  376.83
  5751.7  386.09  5831.9  394.49    5882  396.23  5938.8  395.34  6028.7  398.85
#Mann= 10 ,-1 , 0
  2877.6     .05       0  3148.9     .07       0  3244.5     .05       0
    4520    .035       0  4851.4    .063       0  4951.1      .1       0
  5002.1     .05       0  5038.5      .1       0  5162.9     .07       0
  5938.8     .05       0
Bank Sta=5002.1,5038.5
XS Rating Curve= 0 ,0
Exp/Cntr=0.3,0.1

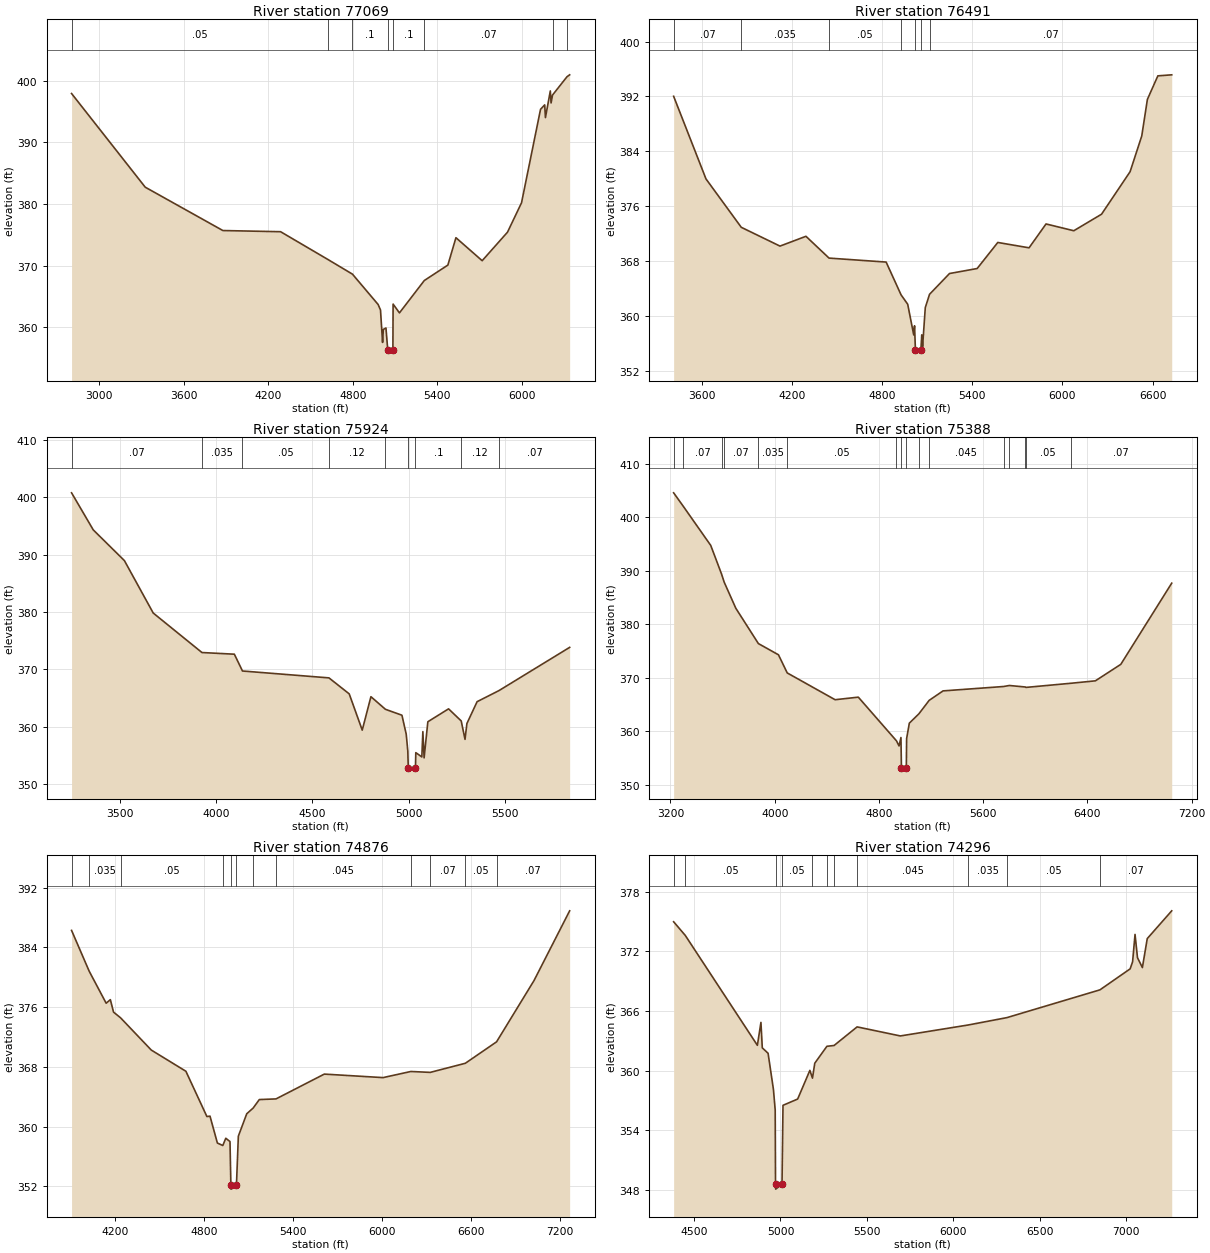
Type RM Length L Ch R = 1 ,77069   ,578,578,578
BEGIN DESCRIPTION:
CLEAR FORK SANDIES CREEK 73.0
END DESCRIPTION:
XS GIS Cut Line= 3
      2348474.98     13659774.98        2346925.       13658225.
      2345624.99       13658575.
#Sta/Elev= 30
  2802.9  397.89  3326.1  382.71  3877.7  375.68  4287.8  375.49  4621.6  371.02
  4798.4  368.61  4980.8  363.69  4997.5   362.8  5012.3  357.54  5017.5  359.65
  5036.3  359.88  5049.1  356.31    5050  355.81  5085.6  356.31    5087  363.76
  5132.1  362.33  5308.7  367.58  5476.1  370.08  5533.4  374.52  5719.8  370.79
  5899.9  375.42  5999.4  380.18  6134.4  395.33    6164  396.05  6169.2  393.99
    6204  398.31  6209.2  396.36  6219.6  397.64  6322.3  400.61  6341.2  400.92
#Mann= 8 ,-1 , 0
  2802.9     .05       0  4621.6    .035       0  4798.4      .1       0
  5049.1     .05       0  5085.6      .1       0  5308.7     .07       0
  6219.6     .05       0  6322.3    .035       0
Bank Sta=5049.1,5085.6
XS Rating Curve= 0 ,0
Exp/Cntr=0.3,0.1

Type RM Length L Ch R = 1 ,76491   ,567,567,567
BEGIN DESCRIPTION:
CLEAR FORK SANDIES CREEK 72.0
END DESCRIPTION:
XS GIS Cut Line= 3
        2348675.       13658075.        2347125.       13657725.
      2345525.02     13658374.99
#Sta/Elev= 30
  3411.3  392.02  3626.6  379.97  3861.6  372.91  4119.4  370.17  4292.2   371.6
  4445.9  368.42    4826  367.84  4925.5  363.06  4969.6  361.69  5009.7  357.21
  5015.1  358.55  5020.9  355.06  5021.8  354.56  5057.4  355.06  5063.2  357.22
  5068.6   355.5  5086.7   361.2    5115  363.14    5248  366.17  5432.1   366.9
  5569.3   370.7  5777.5  369.92  5890.6   373.4  6075.3  372.41  6260.1  374.82
  6450.2  381.02  6527.8  386.23  6565.4  391.57    6635     395  6727.3  395.15
#Mann= 7 ,-1 , 0
  3411.3     .07       0  3861.6    .035       0  4445.9     .05       0
  4925.5      .1       0  5020.9     .05       0  5057.4      .1       0
    5115     .07       0
Bank Sta=5020.9,5057.4
XS Rating Curve= 0 ,0
Exp/Cntr=0.3,0.1

Type RM Length L Ch R = 1 ,75924   ,536,536,536
BEGIN DESCRIPTION:
CLEAR FORK SANDIES CREEK 71.0
END DESCRIPTION:
XS GIS Cut Line= 3
      2348874.99       13658025.        2347325.       13657225.
      2346530.97     13656952.05
#Sta/Elev= 30
  3251.2  400.78  3363.7  394.32  3525.3  388.96  3674.8  379.82  3927.6  372.93
  4095.7  372.64  4137.8  369.71  4586.5  368.51  4691.6  365.72  4759.1   359.4
  4804.2  365.23  4879.5  363.03  4965.1     362  4987.2  358.71  4995.5  355.78
    4998  352.75    4999  352.25  5035.2  352.75    5037  355.47  5068.3  354.73
  5073.6  359.14  5080.1  354.56  5099.5  360.86    5207  363.11  5272.6     361
  5292.3  357.79  5302.1  360.55    5355  364.36  5468.8   366.3  5835.1  373.83
#Mann= 9 ,-1 , 0
  3251.2     .07       0  3927.6    .035       0  4137.8     .05       0
  4586.5     .12       0  4879.5      .1       0    4998     .05       0
  5035.2      .1       0  5272.6     .12       0  5468.8     .07       0
Bank Sta=4998,5035.2
XS Rating Curve= 0 ,0
Exp/Cntr=0.3,0.1

Type RM Length L Ch R = 1 ,75388   ,512,512,512
BEGIN DESCRIPTION:
CLEAR FORK SANDIES CREEK 70.0
END DESCRIPTION:
XS GIS Cut Line= 3
      2349025.03     13657925.02        2347625.       13656825.
      2346449.67     13655155.38
#Sta/Elev= 30
  3224.2  404.58  3299.4  402.02  3508.9  394.75  3591.7  389.41  3612.4  387.86
  3701.4     383  3874.4   376.4  4028.6   374.3  4095.9  370.91  4463.3   365.9
  4641.4  366.38  4934.3  358.21  4954.1  357.26  4968.6  358.83  4972.4  353.05
  4973.4  352.55  5009.8  353.05  5012.1  358.64    5033  361.52  5106.5  363.27
  5185.1  365.78  5291.7  367.55  5756.4  368.37  5800.1  368.56  5923.1  368.28
  5927.2   368.2  6270.4  368.97  6460.7  369.43  6655.6  372.51  7046.5  387.69
#Mann= 16 ,-1 , 0
  3224.2     .05       0  3299.4     .07       0  3591.7    .035       0
  3612.4     .07       0  3874.4    .035       0  4095.9     .05       0
  4934.3     .07       0  4972.4     .05       0  5009.8     .07       0
  5106.5      .1       0  5185.1    .045       0  5756.4     .07       0
  5800.1     .05       0  5923.1     .07       0  5927.2     .05       0
  6270.4     .07       0
Bank Sta=4972.4,5009.8
XS Rating Curve= 0 ,0
Exp/Cntr=0.3,0.1

Type RM Length L Ch R = 1 ,74876   ,580,580,580
BEGIN DESCRIPTION:
CLEAR FORK SANDIES CREEK 69.0
END DESCRIPTION:
XS GIS Cut Line= 3
      2348825.03     13657425.04        2348075.       13656625.
      2346474.98     13655024.98
#Sta/Elev= 30
  3908.3  386.26  4027.1   380.8  4141.6  376.51  4169.9  376.99  4191.4  375.32
  4238.6  374.56  4445.9  370.24  4679.4   367.4    4821  361.34    4842  361.39
  4891.8  357.79  4928.3  357.46  4948.5  358.43  4976.8  357.99  4982.8  352.12
  4983.8  351.62  5020.3  352.12  5033.2  358.71  5089.8  361.71  5132.9  362.47
  5174.6  363.61  5287.4   363.7    5613  367.02    6009  366.55  6196.4  367.37
  6327.5  367.25  6564.2  368.47  6774.8  371.34  7027.3  379.54  7267.7  388.88
#Mann= 12 ,-1 , 0
  3908.3     .05       0  4027.1    .035       0  4238.6     .05       0
  4928.3     .07       0  4982.8     .05       0  5020.3     .07       0
  5132.9     .05       0  5287.4    .045       0  6196.4     .05       0
  6327.5     .07       0  6564.2     .05       0  6774.8     .07       0
Bank Sta=4982.8,5020.3
XS Rating Curve= 0 ,0
Exp/Cntr=0.3,0.1

Type RM Length L Ch R = 1 ,74296   ,588,588,588
BEGIN DESCRIPTION:
CLEAR FORK SANDIES CREEK 68.0
END DESCRIPTION:
XS GIS Cut Line= 3
      2348774.99     13657124.96        2348625.       13656525.
      2347024.97     13654924.97
#Sta/Elev= 30
    4382  374.96  4449.3  373.59  4866.4  362.55    4887  364.85  4894.8  362.29
  4928.3  361.75  4959.2  358.13  4969.5  356.05  4971.4   348.6  4972.3   348.1
  5008.9   348.6  5014.6  356.52  5099.4  357.15  5170.1  360.03  5185.1  359.25
  5198.4  360.75  5268.6  362.45    5310  362.53  5443.3   364.4  5693.4  363.49
    6086  364.59  6309.7  365.33    6848  368.12  7022.7  370.23  7036.9  370.94
    7051  373.69  7065.2  371.35  7093.5  370.36  7121.7  373.27  7263.2  376.06
#Mann= 11 ,-1 , 0
    4382    .035       0  4449.3     .05       0  4971.4     .05       0
  5008.9     .05       0  5185.1     .05       0  5268.6     .07       0
    5310     .05       0  5443.3    .045       0    6086    .035       0
  6309.7     .05       0    6848     .07       0
Bank Sta=4971.4,5008.9
XS Rating Curve= 0 ,0
Exp/Cntr=0.3,0.1

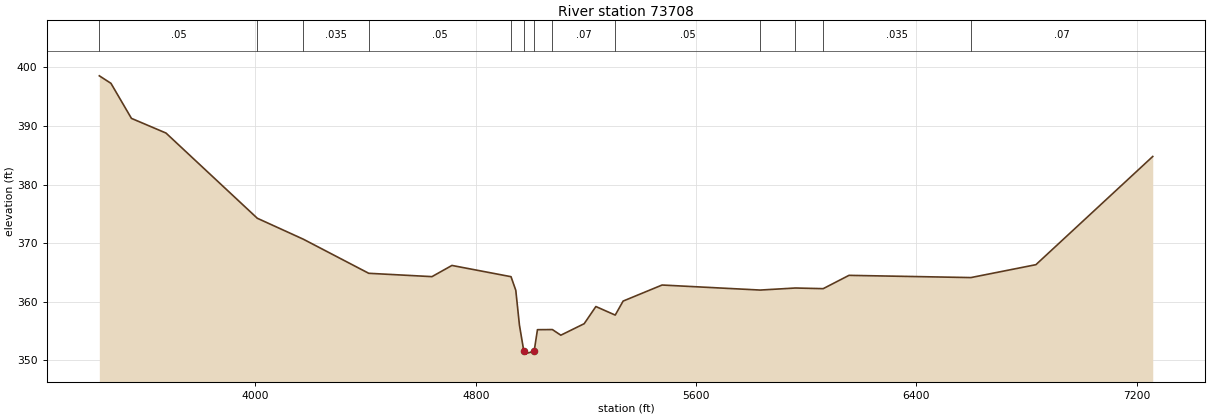
Type RM Length L Ch R = 1 ,73708   ,1102,1102,1102
BEGIN DESCRIPTION:
CLEAR FORK SANDIES CREEK 67.0
END DESCRIPTION:
XS GIS Cut Line= 3
        2349275.     13657724.99        2349075.       13656175.
      2347474.99     13654574.99
#Sta/Elev= 30
  3432.9  398.55  3475.1  397.27  3549.5  391.29  3674.9  388.79  4006.6  374.25
  4173.6  370.68  4411.3  364.86  4640.9  364.29  4713.4   366.2    4928  364.28
  4945.3  361.96  4958.6  356.01  4974.5  351.57  4975.4  351.07    5012  351.57
    5024  355.24  5078.2  355.26  5108.9   354.3  5193.7  356.26  5236.2  359.19
  5306.4  357.73  5335.1  360.12  5476.6  362.86  5833.1     362  5960.8  362.35
  6061.7  362.24  6155.4  364.51  6598.1  364.13  6834.2  366.33  7258.5  384.79
#Mann= 13 ,-1 , 0
  3432.9     .05       0  4006.6     .07       0  4173.6    .035       0
  4411.3     .05       0    4928      .1       0  4974.5     .05       0
    5012      .1       0  5078.2     .07       0  5306.4     .05       0
  5833.1    .035       0  5960.8     .07       0  6061.7    .035       0
  6598.1     .07       0
Bank Sta=4974.5,5012
XS Rating Curve= 0 ,0
Exp/Cntr=0.3,0.1