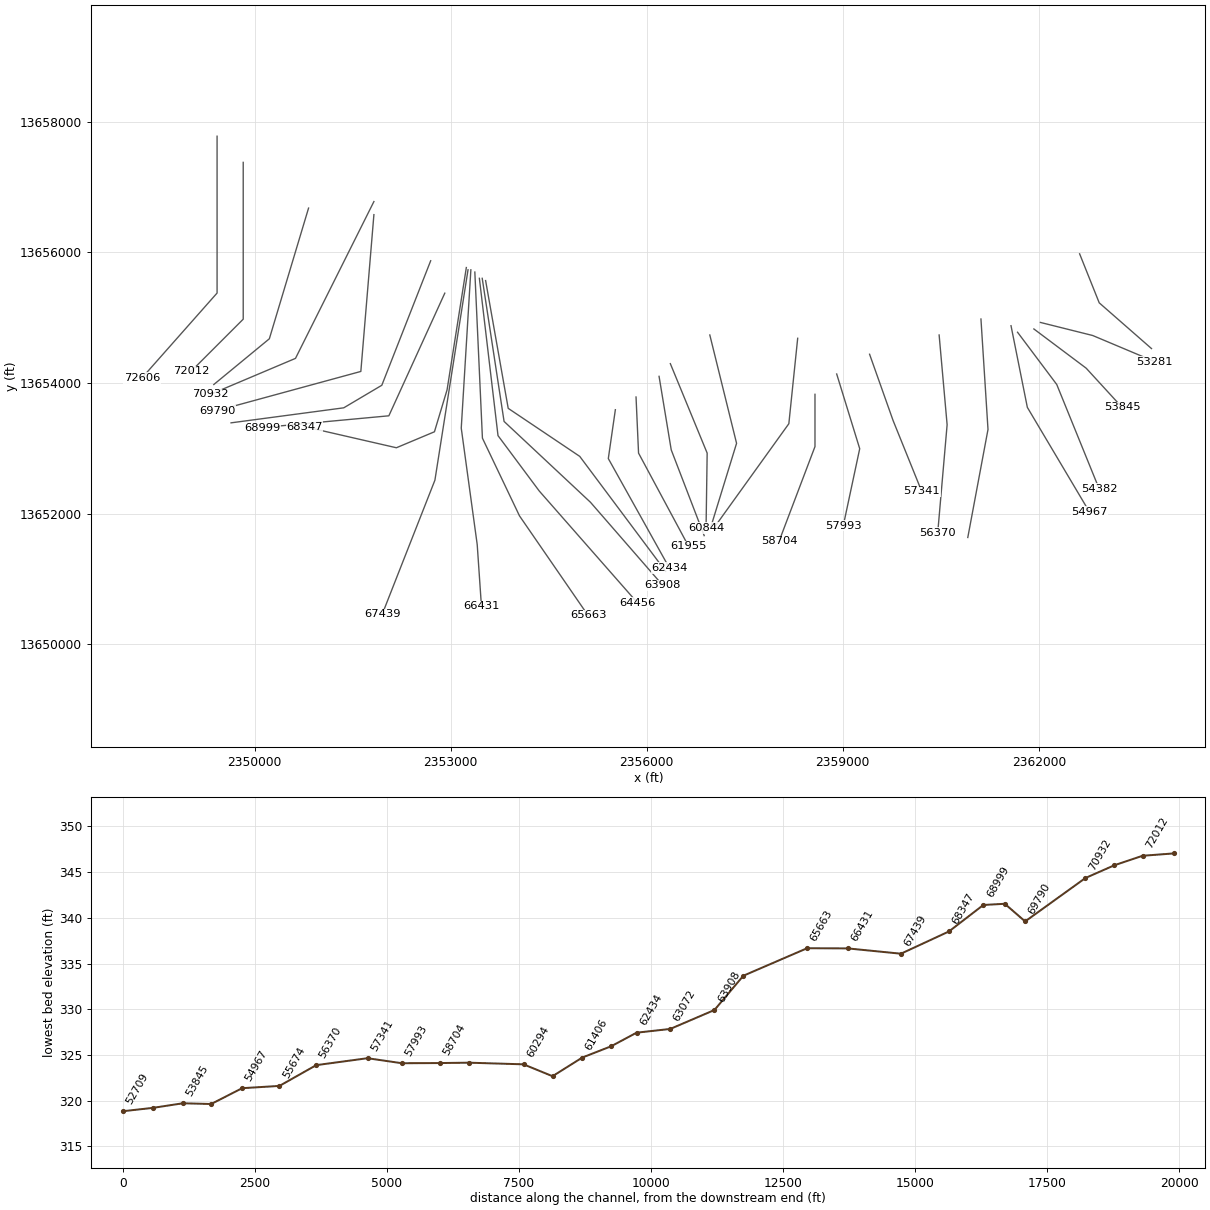
HEC-RAS study CLEAR FORK SANDIES CREEK.prj: CLEAR FORK SANDIES CREEK Base Level Engineering

--- CLEAR FORK SANDIES CREEK.g01 (geometry) --- (continued)

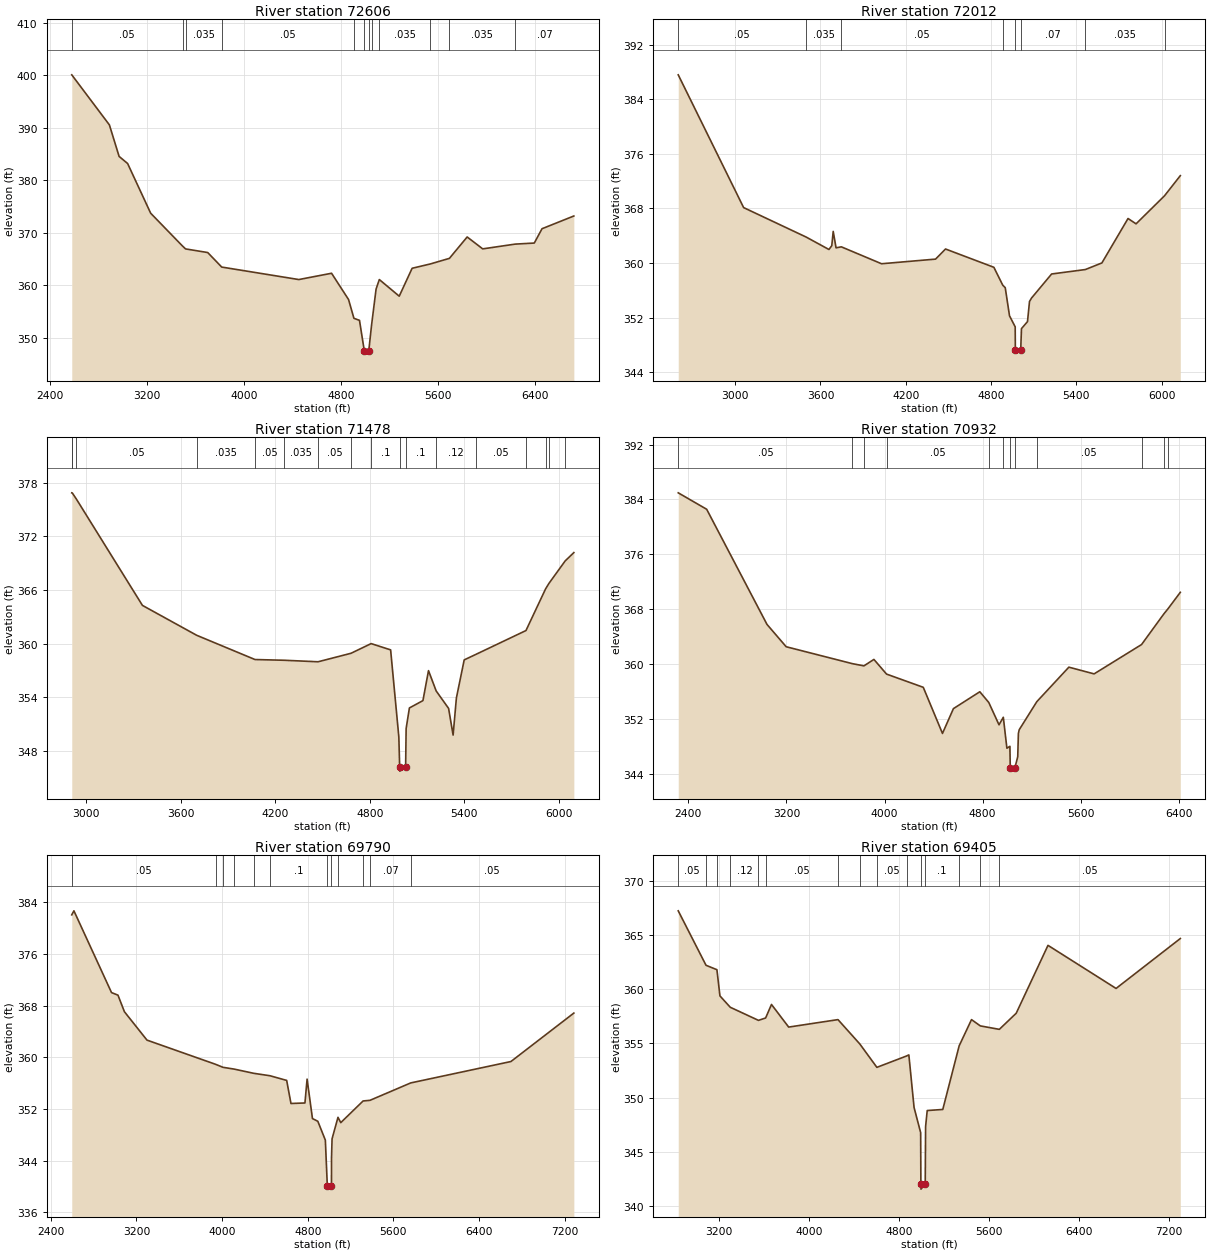
Type RM Length L Ch R = 1 ,72606   ,594,594,594
BEGIN DESCRIPTION:
CLEAR FORK SANDIES CREEK 66.0
END DESCRIPTION:
XS GIS Cut Line= 3
        2349425.     13657775.04        2349425.       13655375.
      2348274.99     13654074.99
#Sta/Elev= 30
  2583.2  400.12  2893.2  390.57  2973.2  384.56  3043.2  383.21  3233.2  373.73
  3495.5  367.47    3521  366.92  3703.2  366.23  3818.3  363.46  4453.2  361.08
  4723.2  362.28  4863.2  357.27  4907.4  353.69  4953.2   353.3  4992.5  347.55
  4993.4  347.05    5030  347.55  5052.4  352.34  5089.9  359.26  5116.6  361.08
  5280.6  357.91  5386.8  363.23  5535.8  364.05  5693.9  365.12  5840.2   369.2
  5968.2  366.93  6236.4  367.84  6393.1  368.04  6456.7  370.77  6718.9   373.2
#Mann= 12 ,-1 , 0
  2583.2     .05       0  3495.5     .07       0    3521    .035       0
  3818.3     .05       0  4907.4      .1       0  4992.5     .05       0
    5030      .1       0  5052.4      .1       0  5116.6    .035       0
  5535.8     .07       0  5693.9    .035       0  6236.4     .07       0
Bank Sta=4992.5,5030
XS Rating Curve= 0 ,0
Exp/Cntr=0.3,0.1

Type RM Length L Ch R = 1 ,72012   ,534,534,534
BEGIN DESCRIPTION:
CLEAR FORK SANDIES CREEK 65.0
END DESCRIPTION:
XS GIS Cut Line= 3
        2349825.     13657374.97        2349825.       13654975.
      2349025.03     13654175.03
#Sta/Elev= 30
  2599.8  387.58  3059.8  368.12  3499.7   363.8  3659.8  361.98  3679.8  362.54
  3689.8  364.63  3709.8  362.22  3746.8  362.37  4029.8  359.89  4409.8  360.57
  4479.8  362.05  4819.8  359.37    4882  356.76  4899.8  356.38  4929.8  352.26
  4969.8  350.64  4970.9  347.29  4971.8  346.79  5008.7  347.29  5013.9  350.38
  5056.3  351.41  5070.5  354.36  5084.6  354.86    5226  358.39  5463.1  359.04
  5579.6  360.01  5763.4  366.52    5820  365.74    6020  369.85  6131.1   372.8
#Mann= 8 ,-1 , 0
  2599.8     .05       0  3499.7    .035       0  3746.8     .05       0
    4882     .07       0  4970.9     .05       0  5008.7     .07       0
  5463.1    .035       0    6020     .07       0
Bank Sta=4970.9,5008.7
XS Rating Curve= 0 ,0
Exp/Cntr=0.3,0.1

Type RM Length L Ch R = 1 ,71478   ,546,546,546
BEGIN DESCRIPTION:
CLEAR FORK SANDIES CREEK 64.0
END DESCRIPTION:
XS GIS Cut Line= 3
        2350825.       13656675.        2350225.       13654675.
        2349375.       13653975.
#Sta/Elev= 30
  2907.1  376.85  2910.7  376.83  2936.1  376.16    3356  364.27  3700.6  360.93
    4071  358.22  4255.2  358.14  4471.7  357.97  4681.1  358.92  4808.7     360
  4932.5   359.3  4984.7  349.56  4989.9  346.25  4990.9  345.75  5027.8  346.25
    5031  350.51  5051.8  352.81  5137.7  353.63  5173.1  356.98  5221.8  354.71
  5300.7  352.76  5329.4  349.78  5350.3  353.93  5399.8  358.18  5473.4  358.79
  5792.2  361.46  5916.7  366.11  5937.8  366.72  6041.2  369.24  6096.3  370.17
#Mann= 17 ,-1 , 0
  2907.1     .05       0  2910.7    .035       0  2936.1     .05       0
  3700.6    .035       0    4071     .05       0  4255.2    .035       0
  4471.7     .05       0  4681.1    .035       0  4808.7      .1       0
  4989.9     .05       0  5027.8      .1       0  5221.8     .12       0
  5473.4     .05       0  5792.2     .07       0  5916.7    .035       0
  5937.8     .07       0  6041.2    .035       0
Bank Sta=4989.9,5027.8
XS Rating Curve= 0 ,0
Exp/Cntr=0.3,0.1

Type RM Length L Ch R = 1 ,70932   ,1142,1142,1142
BEGIN DESCRIPTION:
CLEAR FORK SANDIES CREEK 63.0
END DESCRIPTION:
XS GIS Cut Line= 3
      2351824.98     13656774.97        2350625.       13654375.
      2349325.01       13653825.
#Sta/Elev= 30
  2317.2  384.97  2549.2  382.57  3041.1  365.77  3197.6  362.51  3737.9  360.04
  3831.7  359.72  3913.2  360.66  4016.1  358.52  4315.7  356.59  4472.2  349.86
  4561.6  353.48  4776.8  355.94  4849.8  354.38  4933.4  351.12  4968.5  352.22
  4997.7   347.7  5022.2  347.98  5025.1  344.86  5026.1  344.36  5063.2  344.86
  5086.1  346.46  5091.5  349.87  5098.2   350.4  5241.9   354.5  5503.1  359.53
  5708.9  358.55  6095.9  362.83  6277.7   367.3  6309.4     368    6412  370.45
#Mann= 12 ,-1 , 0
  2317.2     .05       0  3737.9     .07       0  3831.7    .035       0
  4016.1     .05       0  4849.8     .12       0  4968.5      .1       0
  5025.1     .05       0  5063.2      .1       0  5241.9     .05       0
  6095.9     .07       0  6277.7     .05       0  6309.4     .07       0
Bank Sta=5025.1,5063.2
XS Rating Curve= 0 ,0
Exp/Cntr=0.3,0.1

Type RM Length L Ch R = 1 ,69790   ,385,385,385
BEGIN DESCRIPTION:
CLEAR FORK SANDIES CREEK 62.0
END DESCRIPTION:
XS GIS Cut Line= 3
        2351825.     13656574.99        2351625.       13654175.
      2349424.96     13653574.99
#Sta/Elev= 30
  2596.3  382.02  2616.4  382.64  2967.6     370  3027.8   369.6    3088  367.04
  3298.7  362.65  3939.1  358.91    4009  358.44  4112.6  358.17  4294.6  357.52
  4447.4  357.14  4603.2  356.42  4643.4  352.85  4773.8  352.93  4793.9  356.62
  4844.1  350.52  4894.2   350.1  4964.5  347.18  4982.8  340.11  4983.8  339.61
  5021.5  340.11  5021.9   344.4  5027.1  347.39  5082.4  350.71  5108.3  349.89
  5316.9  353.24  5381.2  353.34  5761.6  356.03  6697.6  359.34    7285  366.83
#Mann= 12 ,-1 , 0
  2596.3     .05       0  3939.1     .07       0    4009     .05       0
  4112.6    .035       0  4294.6    .063       0  4447.4      .1       0
  4982.8     .05       0  5021.5      .1       0  5082.4     .07       0
  5316.9     .05       0  5381.2     .07       0  5761.6     .05       0
Bank Sta=4982.8,5021.5
XS Rating Curve= 0 ,0
Exp/Cntr=0.3,0.1

Type RM Length L Ch R = 1 ,69405   ,406,406,406
BEGIN DESCRIPTION:
X18501
END DESCRIPTION:
XS GIS Cut Line= 4
      2352693.93     13655869.16      2351946.02     13653963.43
      2351363.53     13653618.24      2349638.82     13653388.28
#Sta/Elev= 30
    2836  367.25    3083  362.22  3179.9  361.81  3206.9  359.39  3298.7  358.34
  3549.5  357.13    3613  357.35  3665.1   358.6    3818  356.51  4256.5   357.2
  4450.6  354.95  4602.3  352.79  4866.4  353.84  4886.6  353.94    4933  349.08
  4991.5  346.76  4993.5  342.04  4994.5  341.54  5032.2  342.04  5035.5  347.32
  5049.9   348.8  5188.3   348.9    5334  354.78  5443.7   357.2    5522  356.62
  5691.1   356.3  5841.3  357.79  6123.8  364.06  6729.1  360.08  7300.3  364.69
#Mann= 15 ,-1 , 0
    2836     .05       0    3083     .07       0  3179.9     .05       0
  3298.7     .12       0  3549.5    .035       0    3613     .05       0
  4256.5    .035       0  4450.6     .12       0  4602.3     .05       0
  4866.4      .1       0  4993.5     .05       0  5032.2      .1       0
    5334     .07       0    5522    .035       0  5691.1     .05       0
Bank Sta=4993.5,5032.2
XS Rating Curve= 0 ,0
Exp/Cntr=0.3,0.1

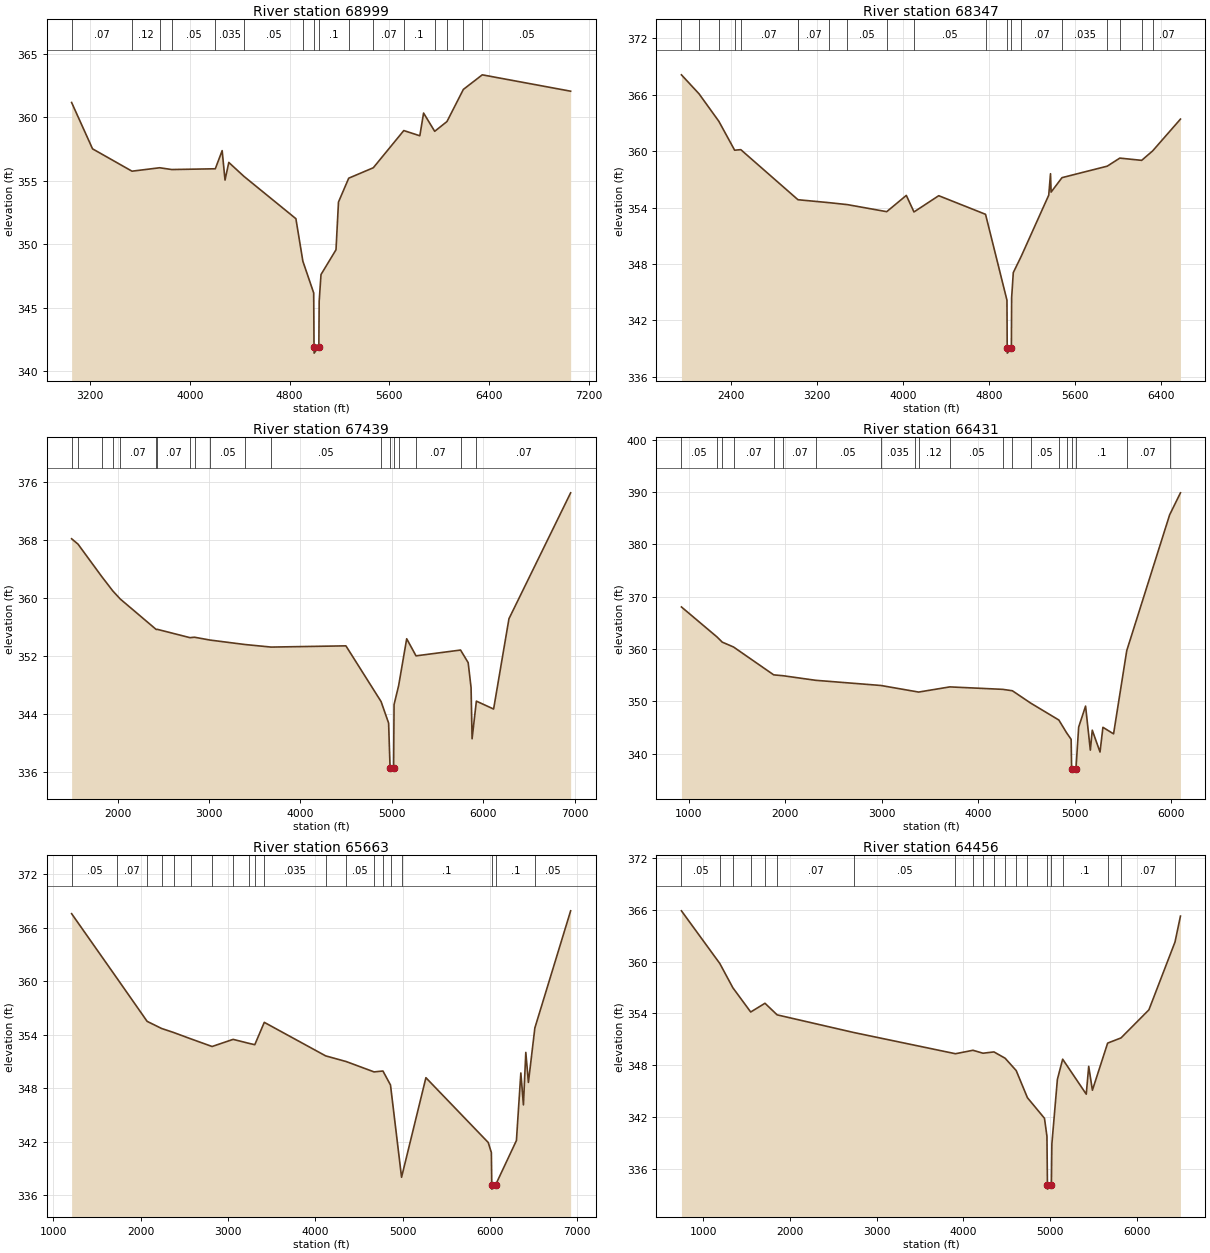
Type RM Length L Ch R = 1 ,68999   ,652,652,652
BEGIN DESCRIPTION:
X18500
END DESCRIPTION:
XS GIS Cut Line= 3
      2352909.65     13655372.91      2352053.89     13653495.99
      2350119.73     13653316.24
#Sta/Elev= 30
  3050.5  361.15  3218.5   357.5  3535.2  355.74  3757.1  356.01  3854.5  355.87
  4203.8  355.93  4258.8  357.36  4281.8  355.04  4312.1  356.43  4433.9  355.33
  4850.6     352  4906.6  348.65  4993.5  346.15  4996.1  341.91  4997.1  341.41
  5034.8  341.91  5037.5   345.5  5052.2   347.6  5172.5  349.55  5192.5  353.31
  5274.7  355.19  5471.9  356.01  5716.6  358.94  5845.3  358.53  5875.5  360.32
  5964.7  358.88  6063.2  359.65  6194.7  362.18  6346.6  363.33  7055.8  362.04
#Mann= 16 ,-1 , 0
  3050.5     .07       0  3535.2     .12       0  3757.1     .07       0
  3854.5     .05       0  4203.8    .035       0  4433.9     .05       0
  4906.6      .1       0  4996.1     .05       0  5034.8      .1       0
  5274.7     .12       0  5471.9     .07       0  5716.6      .1       0
  5964.7    .035       0  6063.2     .05       0  6194.7     .07       0
  6346.6     .05       0
Bank Sta=4996.1,5034.8
XS Rating Curve= 0 ,0
Exp/Cntr=0.3,0.1

Type RM Length L Ch R = 1 ,68347   ,908,908,908
BEGIN DESCRIPTION:
X18499
END DESCRIPTION:
XS GIS Cut Line= 5
      2353239.39     13655765.26      2352944.76     13653893.55
      2352751.45     13653251.49      2352168.95     13653006.98
      2350761.01     13653330.24
#Sta/Elev= 30
  1936.1  368.12  2099.8   366.1  2284.4  363.17    2431   360.1  2488.1  360.16
  3017.2  354.86  3020.8  354.83  3308.6  354.52  3479.9  354.31  3845.3  353.56
  4027.8  355.29    4099  353.53  4329.2  355.26  4764.6  353.28  4963.9  344.14
  4966.2  339.01  4967.2  338.51  5004.9  339.01  5007.3  344.39  5022.8  347.08
    5097  348.82  5352.6  355.32    5369   357.6  5374.2  355.64  5475.9  357.18
  5896.2   358.4  6013.6  359.26  6216.9  359.02  6318.5  360.02  6577.7  363.41
#Mann= 20 ,-1 , 0
  1936.1     .07       0  2099.8     .05       0  2284.4     .07       0
    2431     .05       0  2488.1     .07       0  3017.2     .12       0
  3020.8     .07       0  3308.6     .07       0  3479.9     .05       0
  3845.3    .035       0    4099     .05       0  4764.6      .1       0
  4966.2     .05       0  5004.9      .1       0    5097     .07       0
  5475.9    .035       0  5896.2      .1       0  6013.6     .07       0
  6216.9    .035       0  6318.5     .07       0
Bank Sta=4966.2,5004.9
XS Rating Curve= 0 ,0
Exp/Cntr=0.3,0.1

Type RM Length L Ch R = 1 ,67439   ,1008,1008,1008
BEGIN DESCRIPTION:
CLEAR FORK SANDIES CREEK 61.0
END DESCRIPTION:
XS GIS Cut Line= 3
      2353265.44     13655730.55      2352758.64     13652510.78
      2351953.22     13650461.27
#Sta/Elev= 30
  1495.9  368.15  1565.8  367.41  1825.9  362.93  1946.8  360.95  2027.8  359.84
  2421.7  355.63  2433.6  355.65  2791.7   354.5  2840.9  354.56  3010.4  354.17
  3395.5  353.55  3680.1   353.2    4498  353.37  4882.8  345.68  4965.3  342.71
  4981.1  336.58  4982.1  336.08  5019.9  336.58  5024.9  345.27  5074.8  347.87
  5163.1  354.35  5265.2  351.99  5752.6  352.79    5836  351.05  5867.7   347.6
  5878.9  340.55  5925.5  345.74  6114.3  344.65  6282.3  357.11  6957.4  374.49
#Mann= 19 ,-1 , 0
  1495.9     .07       0  1565.8     .05       0  1825.9     .07       0
  1946.8     .05       0  2027.8     .07       0  2421.7     .12       0
  2433.6     .07       0  2791.7     .05       0  2840.9     .07       0
  3010.4     .05       0  3395.5    .035       0  3680.1     .05       0
  4882.8      .1       0  4981.1     .05       0  5019.9      .1       0
  5074.8      .1       0  5265.2     .07       0  5752.6     .12       0
  5925.5     .07       0
Bank Sta=4981.1,5019.9
XS Rating Curve= 0 ,0
Exp/Cntr=0.3,0.1

Type RM Length L Ch R = 1 ,66431   ,768,768,768
BEGIN DESCRIPTION:
X18498
END DESCRIPTION:
XS GIS Cut Line= 4
      2353308.84     13655730.56      2353161.68     13653307.52
      2353405.86     13651525.57      2353470.58      13650583.5
#Sta/Elev= 30
   924.2  368.02  1292.7  362.29    1347   361.3    1464  360.37  1880.1  355.05
  1978.9  354.88  2314.3  354.01  2990.5  353.02  3345.2  351.88  3381.4  351.76
  3704.6  352.75  4254.2  352.28  4353.2  352.01  4541.4  349.67  4834.6  346.42
  4915.7  343.96    4962  342.73  4966.8  337.16  4967.8  336.66  5011.9  337.16
  5039.9  345.07  5111.4  349.08  5160.9  340.67  5180.9  344.48  5261.1  340.31
  5291.2  345.03  5401.5  343.78    5538  359.67  5982.5  385.62  6094.6  389.82
#Mann= 20 ,-1 , 0
   924.2     .05       0  1292.7     .07       0    1347     .05       0
    1464     .07       0  1880.1     .12       0  1978.9     .07       0
  2314.3     .05       0  2990.5    .035       0  3345.2     .05       0
  3381.4     .12       0  3704.6     .05       0  4254.2      .1       0
  4353.2     .05       0  4541.4     .05       0  4834.6     .12       0
  4915.7      .1       0  4966.8     .05       0  5011.9      .1       0
    5538     .07       0  5982.5     .05       0
Bank Sta=4966.8,5011.9
XS Rating Curve= 0 ,0
Exp/Cntr=0.3,0.1

Type RM Length L Ch R = 1 ,65663   ,1207,1207,1207
BEGIN DESCRIPTION:
X18497
END DESCRIPTION:
XS GIS Cut Line= 4
       2353369.6     13655695.78      2353485.73     13653153.97
      2354053.07     13651964.24      2355102.92     13650439.81
#Sta/Elev= 30
  1209.1  367.58  1730.5  360.31  2073.8   355.5  2239.7   354.7  2377.5  354.25
  2573.5  353.54  2817.5  352.68  3058.1  353.48  3236.5  353.04  3306.3  352.88
  3415.1  355.39  4117.3  351.63    4353  350.99  4672.2  349.83  4773.6  349.93
  4860.1  348.36  4986.8  338.01  5265.6  349.18  5979.2  341.91    6015  340.78
  6019.5  337.18  6020.5  336.68  6064.6  337.18  6301.8  342.13  6352.5  349.71
  6382.1  346.13  6409.3  352.02  6439.1  348.65  6512.9  354.76  6922.6   367.9
#Mann= 20 ,-1 , 0
  1209.1     .05       0  1730.5     .07       0  2073.8     .07       0
  2239.7     .12       0  2377.5     .07       0  2573.5     .12       0
  2817.5     .07       0  3058.1     .05       0  3236.5     .07       0
  3306.3    .035       0  3415.1    .035       0  4117.3    .035       0
    4353     .05       0  4672.2     .12       0  4773.6      .1       0
  4860.1     .12       0  4986.8      .1       0  6019.5     .05       0
  6064.6      .1       0  6512.9     .05       0
Bank Sta=6019.5,6064.6
XS Rating Curve= 0 ,0
Exp/Cntr=0.3,0.1

Type RM Length L Ch R = 1 ,64456   ,548,548,548
BEGIN DESCRIPTION:
X18496
END DESCRIPTION:
XS GIS Cut Line= 4
      2353439.05      13655600.3      2353724.24     13653192.65
      2354355.11     13652345.38      2355858.09     13650633.85
#Sta/Elev= 30
   746.6  365.88    1189  359.79  1340.4  356.97  1545.9  354.17  1710.7  355.18
    1851  353.84  2733.6   351.8  3908.9  349.34  4110.5  349.74  4226.4   349.4
  4352.9  349.55    4482  348.82  4609.8  347.39  4739.3  344.25  4935.9  341.87
  4964.4  339.79  4970.1  334.17  4971.1  333.67  5015.6  334.17  5021.3  338.91
  5084.9  346.37  5145.9  348.71    5418  344.66  5446.4  347.88  5489.1  345.12
  5664.9  350.57  5819.1  351.17    6141  354.42  6442.2  362.27  6505.2  365.27
#Mann= 20 ,-1 , 0
   746.6     .05       0    1189     .07       0  1340.4     .12       0
  1545.9     .07       0  1710.7     .12       0    1851     .07       0
  2733.6     .05       0  3908.9    .035       0  4110.5     .07       0
  4226.4    .035       0  4352.9     .05       0    4482     .07       0
  4609.8     .07       0  4739.3     .07       0  4970.1     .05       0
  5015.6      .1       0  5145.9      .1       0  5664.9     .07       0
  5819.1     .07       0  6442.2    .035       0
Bank Sta=4970.1,5015.6
XS Rating Curve= 0 ,0
Exp/Cntr=0.3,0.1

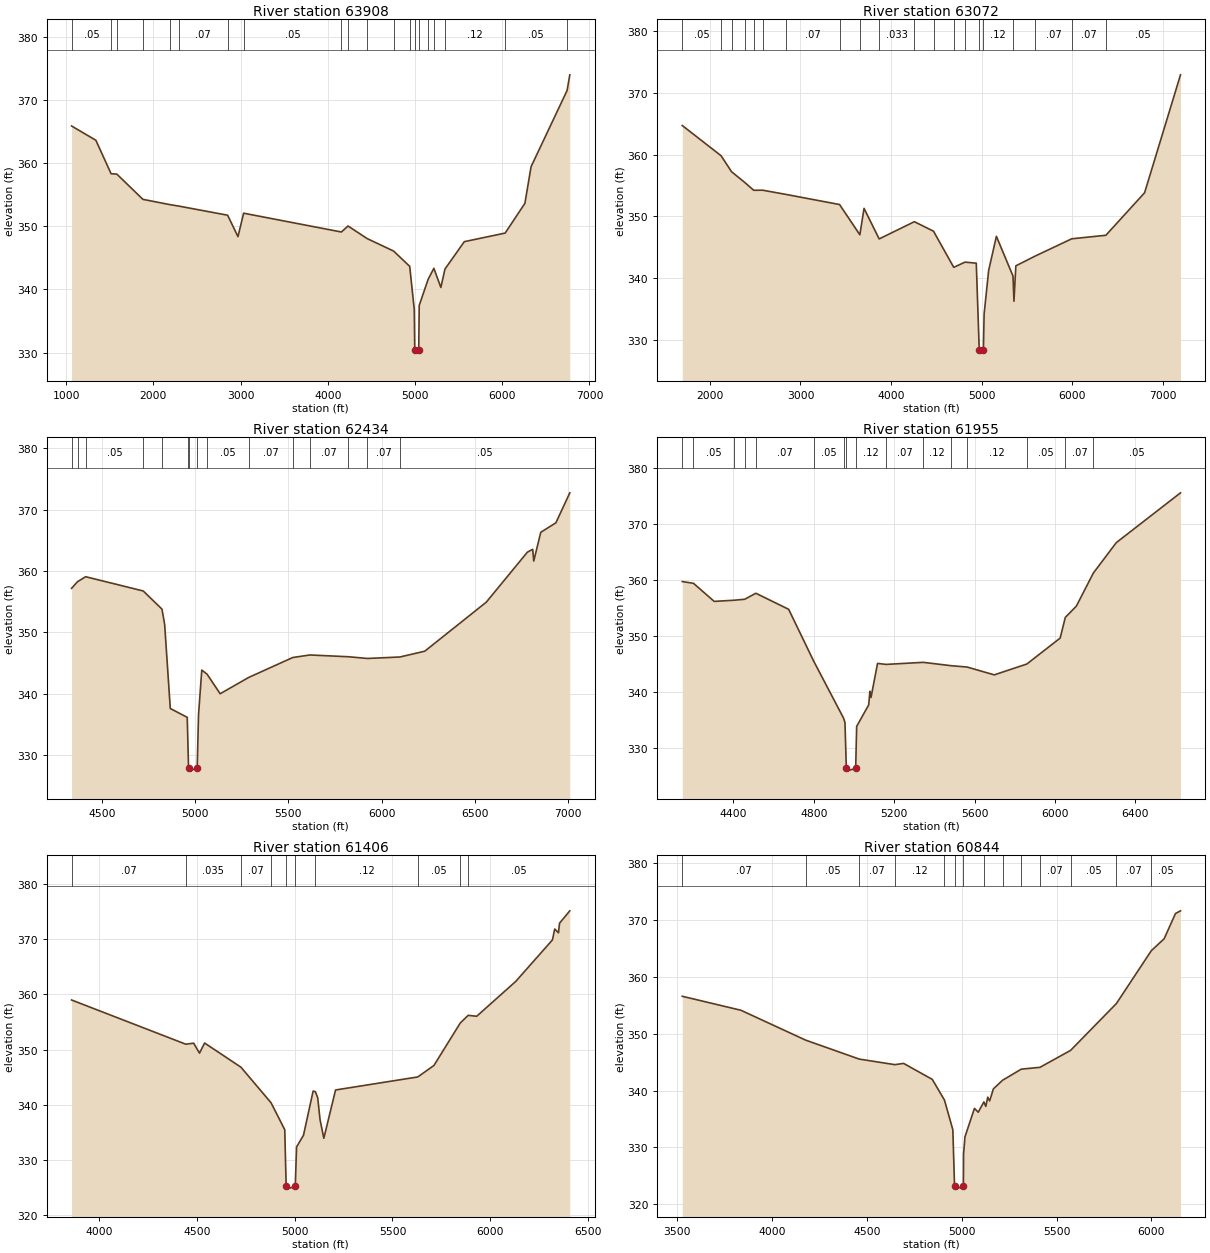
Type RM Length L Ch R = 1 ,63908   ,836,836,836
BEGIN DESCRIPTION:
CLEAR FORK SANDIES CREEK 60.0
END DESCRIPTION:
XS GIS Cut Line= 4
      2353482.44     13655600.34      2353817.01     13653409.76
      2355138.96     13652172.79      2356246.42     13650899.94
#Sta/Elev= 30
  1061.3  365.89  1339.8  363.63  1514.5  358.33  1580.3  358.27  1879.4  354.27
  2186.7  353.44  2288.4  353.21  2850.8  351.76  2969.7  348.37  3034.3  352.08
  4155.4   349.1  4231.9  350.05  4450.9  348.06  4754.7  346.08    4939  343.66
  4991.3  336.83  4996.9  330.42  4997.9  329.92  5042.4  330.42    5048  337.47
  5150.4  341.61  5215.9  343.35  5296.4  340.32  5343.3  343.23  5565.1  347.57
  6033.7  348.93  6260.1  353.64  6330.8  359.44  6743.9  371.51  6774.9  373.99
#Mann= 20 ,-1 , 0
  1061.3     .05       0  1514.5     .07       0  1580.3     .12       0
  1879.4     .07       0  2186.7     .12       0  2288.4     .07       0
  2850.8     .05       0  3034.3     .05       0  4155.4    .035       0
  4231.9     .07       0  4450.9     .12       0  4754.7     .05       0
    4939      .1       0  4996.9     .05       0  5042.4      .1       0
  5150.4     .07       0  5215.9     .12       0  5343.3     .12       0
  6033.7     .05       0  6743.9    .035       0
Bank Sta=4996.9,5042.4
XS Rating Curve= 0 ,0
Exp/Cntr=0.3,0.1

Type RM Length L Ch R = 1 ,63072   ,638,638,638
BEGIN DESCRIPTION:
CLEAR FORK SANDIES CREEK 59.0
END DESCRIPTION:
XS GIS Cut Line= 4
      2353534.52     13655565.62       2353880.2     13653610.16
        2354975.       13652875.      2356289.56     13651115.68
#Sta/Elev= 30
  1695.4  364.72  2123.5  359.83  2239.7  357.23  2384.8   355.5  2484.3  354.23
  2583.8  354.24  2839.9  353.56  3431.9  351.92  3655.9  347.02  3702.2   351.3
  3869.2  346.35  4257.8  349.14  4469.3   347.6  4692.5  341.75  4817.7  342.59
  4941.4  342.42  4974.1  328.35  4975.1  327.85  5019.7  328.35    5028   334.2
  5078.1  341.25  5163.5  346.77  5346.6  340.34  5357.4  336.26  5378.2  341.99
  5588.6  343.55  5995.4  346.37    6372  346.94  6799.8  353.83  7196.1  372.93
#Mann= 20 ,-1 , 0
  1695.4     .05       0  2123.5     .07       0  2239.7     .12       0
  2384.8     .07       0  2484.3     .12       0  2583.8     .07       0
  2839.9     .07       0  3431.9     .05       0  3655.9     .05       0
  3869.2    .033       0  4257.8     .05       0  4469.3     .07       0
  4692.5    .035       0  4817.7     .12       0  4974.1     .05       0
  5019.7     .12       0  5346.6     .05       0  5588.6     .07       0
  5995.4     .07       0    6372     .05       0
Bank Sta=4974.1,5019.7
XS Rating Curve= 0 ,0
Exp/Cntr=0.3,0.1

Type RM Length L Ch R = 1 ,62434   ,479,479,479
BEGIN DESCRIPTION:
CLEAR FORK SANDIES CREEK 58.0
END DESCRIPTION:
XS GIS Cut Line= 3
      2355520.09     13653589.44      2355412.23     13652841.58
      2356347.09     13651166.03
#Sta/Elev= 30
  4336.1  357.18    4368  358.26  4411.7  359.07  4720.8  356.75  4821.3   353.8
  4835.7  351.33    4866  337.63  4956.9  336.19  4963.4  328.64    4964  327.94
    4965  327.44  5010.4  327.94  5017.5   336.6    5035  343.88  5063.3  343.22
  5133.7  340.03  5286.6  342.68    5523  345.92  5615.1  346.34  5822.4  346.05
  5924.3  345.77  6098.6  346.01  6231.8  346.95  6562.1  354.93  6782.6  363.06
  6811.2  363.53  6816.9  361.62  6854.6   366.3  6935.7  367.84  7010.4  372.72
#Mann= 15 ,-1 , 0
  4336.1     .05       0    4368    .035       0  4411.7     .05       0
  4720.8     .12       0  4821.3     .05       0  4963.4     .12       0
    4964     .05       0  5010.4     .12       0  5063.3     .05       0
  5286.6     .07       0    5523     .12       0  5615.1     .07       0
  5822.4     .12       0  5924.3     .07       0  6098.6     .05       0
Bank Sta=4964,5010.4
XS Rating Curve= 0 ,0
Exp/Cntr=0.3,0.1

Type RM Length L Ch R = 1 ,61955   ,549,549,549
BEGIN DESCRIPTION:
CLEAR FORK SANDIES CREEK 57.0
END DESCRIPTION:
XS GIS Cut Line= 3
      2355836.52      13653783.6        2355875.       13652925.
      2356641.07     13651498.44
#Sta/Elev= 30
  4145.7  359.71  4201.4   359.4  4304.5  356.18    4405  356.39  4456.2  356.56
  4511.7  357.63    4675  354.77  4799.4  345.55  4948.6  335.36  4955.1  334.59
  4961.9  326.46  4962.9  325.96  5008.4  326.46  5013.3  333.93  5073.3  337.76
    5079  340.18  5084.7  339.08  5117.2  345.14  5159.5  344.96  5344.2  345.33
  5483.9  344.73  5563.1  344.49  5697.7   343.1  5859.9  345.03  6025.7  349.65
  6051.3  353.33  6106.2  355.33  6190.9  361.23  6304.9  366.64  6624.4  375.51
#Mann= 16 ,-1 , 0
  4145.7    .035       0  4201.4     .05       0    4405     .07       0
  4456.2     .05       0  4511.7     .07       0  4799.4     .05       0
  4948.6     .12       0  4961.9     .05       0  5008.4     .12       0
  5159.5     .07       0  5344.2     .12       0  5483.9     .07       0
  5563.1     .12       0  5859.9     .05       0  6051.3     .07       0
  6190.9     .05       0
Bank Sta=4961.9,5008.4
XS Rating Curve= 0 ,0
Exp/Cntr=0.3,0.1

Type RM Length L Ch R = 1 ,61406   ,562,562,562
BEGIN DESCRIPTION:
CLEAR FORK SANDIES CREEK 56.0
END DESCRIPTION:
XS GIS Cut Line= 3
      2356188.88     13654100.11        2356375.       13652975.
      2356879.26     13651662.21
#Sta/Elev= 30
  3859.7     359  4443.3  350.99  4483.8  351.17  4513.6  349.37  4539.7   351.2
  4725.4  346.82  4879.4  340.37  4949.4  335.49  4956.6  325.22  4957.6  324.72
  5003.1  325.22  5009.7  332.36  5045.1  334.48  5094.4  342.49  5106.2  342.38
  5117.9  341.26  5129.8   337.3  5149.1  333.94  5209.1  342.69  5629.1  345.05
  5711.9  347.13  5846.5  354.83    5887  356.22  5930.5  356.05  6129.9  362.36
  6317.7  369.89  6329.3  371.86  6348.6  371.18    6354  372.92  6406.4  375.16
#Mann= 10 ,-1 , 0
  3859.7     .07       0  4443.3    .035       0  4725.4     .07       0
  4879.4     .12       0  4956.6     .05       0  5003.1     .12       0
  5106.2     .12       0  5629.1     .05       0  5846.5     .07       0
    5887     .05       0
Bank Sta=4956.6,5003.1
XS Rating Curve= 0 ,0
Exp/Cntr=0.3,0.1

Type RM Length L Ch R = 1 ,60844   ,550,550,550
BEGIN DESCRIPTION:
CLEAR FORK SANDIES CREEK 55.0
END DESCRIPTION:
XS GIS Cut Line= 3
      2356361.49      13654294.2        2356925.       13652925.
      2356908.04     13651778.65
#Sta/Elev= 30
  3526.3  356.58  3835.7  354.12  4176.9  348.87  4459.1  345.54  4647.3  344.56
  4693.3  344.78  4844.7  341.97  4908.8  338.33  4952.9  333.13    4962  323.18
    4963  322.68  5008.6  323.18  5009.4  328.79  5016.9  331.87  5066.9  336.88
  5086.9   336.2  5116.7  338.01  5126.9  337.22  5136.9  338.84  5146.9  338.18
  5166.9  340.31  5215.3  341.82  5313.9  343.77  5412.4  344.09  5573.9  347.07
  5815.3   355.3  5999.6   364.6    6067  366.68    6127  371.13  6153.4   371.6
#Mann= 14 ,-1 , 0
  3526.3     .07       0  4176.9     .05       0  4459.1     .07       0
  4647.3     .12       0  4908.8      .1       0    4962     .05       0
  5008.6      .1       0  5116.7     .12       0  5215.3     .07       0
  5313.9     .12       0  5412.4     .07       0  5573.9     .05       0
  5815.3     .07       0  5999.6     .05       0
Bank Sta=4962,5008.6
XS Rating Curve= 0 ,0
Exp/Cntr=0.3,0.1

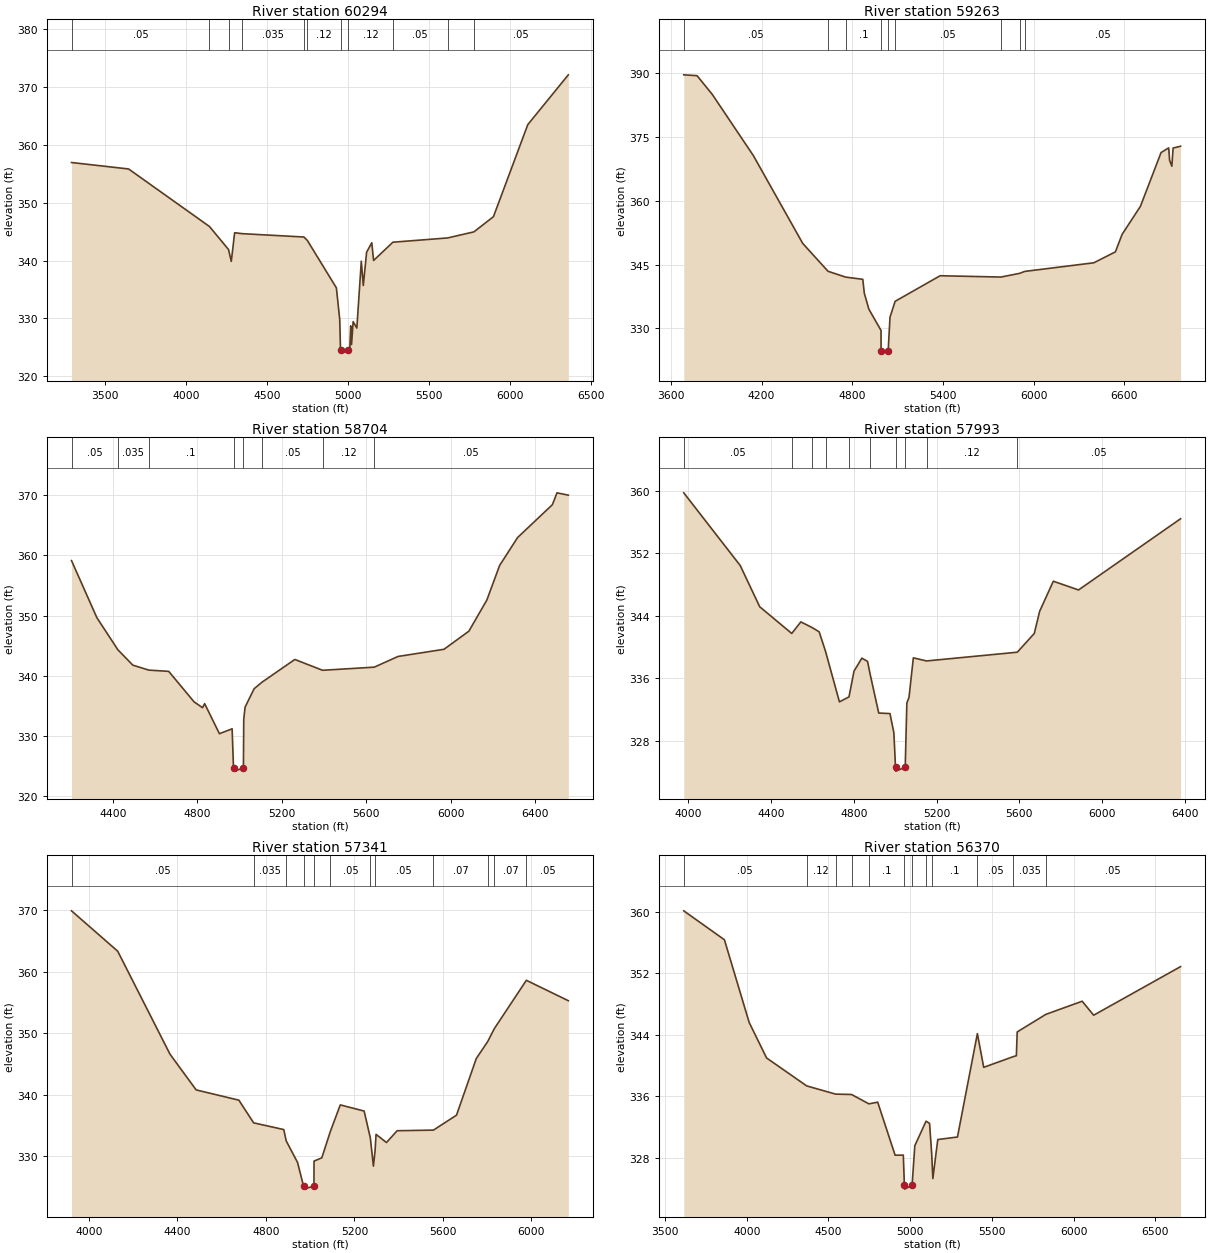
Type RM Length L Ch R = 1 ,60294   ,1031,1031,1031
BEGIN DESCRIPTION:
CLEAR FORK SANDIES CREEK 54.0
END DESCRIPTION:
XS GIS Cut Line= 3
      2356965.54     13654732.94        2357375.       13653075.
        2356975.       13651775.
#Sta/Elev= 30
  3292.2  356.96    3645  355.84  4144.1  345.89    4262   341.9  4278.9  339.85
  4299.5  344.81  4345.6  344.65  4727.3  344.07  4748.5  343.48  4927.9  335.27
  4948.5   329.8  4953.4  324.48  4954.4  323.98    5000  324.48  5010.4  324.49
  5016.3   328.7  5021.5  325.47  5031.3  329.43  5054.2  328.32  5081.7  339.89
  5094.1  335.68  5114.4  341.43  5146.4  343.08  5157.6  340.01  5276.7  343.17
    5615  343.91  5777.1  344.96  5897.8  347.59  6109.7  363.51  6360.1  372.13
#Mann= 11 ,-1 , 0
  3292.2     .05       0  4144.1    .035       0    4262     .07       0
  4345.6    .035       0  4727.3     .07       0  4748.5     .12       0
  4953.4     .05       0    5000     .12       0  5276.7     .05       0
    5615     .12       0  5777.1     .05       0
Bank Sta=4953.4,5000
XS Rating Curve= 0 ,0
Exp/Cntr=0.3,0.1

Type RM Length L Ch R = 1 ,59263   ,559,559,559
BEGIN DESCRIPTION:
CLEAR FORK SANDIES CREEK 53.0
END DESCRIPTION:
XS GIS Cut Line= 3
      2358310.33     13654682.57        2358175.       13653375.
      2357024.97     13651774.96
#Sta/Elev= 30
  3685.8  389.68  3773.8  389.48  3874.4  385.07  4145.8  370.68  4472.5  349.99
  4639.8  343.43  4756.1  342.06  4869.7  341.54  4879.7  338.25  4909.9   334.5
  4990.3   329.5  4990.5  324.66  4991.5  324.16  5037.3  324.66  5049.6  332.62
  5083.3  336.35  5380.9  342.38  5782.5  342.07  5906.4  342.94  5940.9   343.4
  6397.4  345.43  6539.9     348    6584   352.1  6705.6  358.74  6841.8  371.38
  6892.2  372.48  6898.3  369.55  6913.1  368.17  6921.5  372.44  6970.8  372.87
#Mann= 9 ,-1 , 0
  3685.8     .05       0  4639.8    .035       0  4756.1      .1       0
  4990.5     .05       0  5037.3      .1       0  5083.3     .05       0
  5782.5     .12       0  5906.4     .07       0  5940.9     .05       0
Bank Sta=4990.5,5037.3
XS Rating Curve= 0 ,0
Exp/Cntr=0.3,0.1

Type RM Length L Ch R = 1 ,58704   ,711,711,711
BEGIN DESCRIPTION:
CLEAR FORK SANDIES CREEK 52.0
END DESCRIPTION:
XS GIS Cut Line= 3
        2358575.     13653824.98        2358575.       13653025.
      2358024.99     13651574.99
#Sta/Elev= 30
    4205  359.13    4325  349.64  4424.5   344.3    4495  341.75  4570.4  340.92
    4665  340.71    4785  335.64    4825  334.67    4835  335.34    4905  330.34
    4965  331.16  4971.6  324.62  4972.6  324.12  5018.4  324.62    5020  332.73
  5026.4  334.77  5069.1  337.82  5106.8  338.92  5261.7  342.69  5392.8  340.89
  5637.6  341.41  5750.2  343.19  5967.5  344.38  6085.2  347.39  6170.3  352.57
  6230.6  358.31  6315.6  362.96  6480.4  368.43  6502.3   370.4  6555.8  370.01
#Mann= 8 ,-1 , 0
    4205     .05       0  4424.5    .035       0  4570.4      .1       0
  4971.6     .05       0  5018.4      .1       0  5106.8     .05       0
  5392.8     .12       0  5637.6     .05       0
Bank Sta=4971.6,5018.4
XS Rating Curve= 0 ,0
Exp/Cntr=0.3,0.1

Type RM Length L Ch R = 1 ,57993   ,652,652,652
BEGIN DESCRIPTION:
X18495
END DESCRIPTION:
XS GIS Cut Line= 3
      2358907.22     13654135.98      2359259.58      13652992.6
      2359007.88      13651813.2
#Sta/Elev= 30
  3977.3  359.74  4250.4  350.43  4344.6  345.15  4499.5  341.73  4543.4  343.21
  4596.4  342.51  4632.1  341.94  4662.8  339.45  4730.1  332.97  4776.3  333.61
  4800.7  336.91  4838.6  338.57  4866.1  338.15  4878.4  336.54  4920.1  331.54
  4974.5  331.47  4993.3  329.01  5001.3   324.6  5002.3   324.1  5048.2   324.6
  5056.1  332.81  5066.6  333.56  5087.5  338.61  5151.2  338.21  5590.2  339.33
  5672.3  341.73  5698.3  344.57  5764.4  348.42  5886.2   347.3  6379.7  356.42
#Mann= 10 ,-1 , 0
  3977.3     .05       0  4499.5     .07       0  4596.4     .05       0
  4662.8     .07       0  4776.3    .035       0  4878.4      .1       0
  5001.3     .05       0  5048.2      .1       0  5151.2     .12       0
  5590.2     .05       0
Bank Sta=5001.3,5048.2
XS Rating Curve= 0 ,0
Exp/Cntr=0.3,0.1

Type RM Length L Ch R = 1 ,57341   ,971,971,971
BEGIN DESCRIPTION:
CLEAR FORK SANDIES CREEK 51.0
END DESCRIPTION:
XS GIS Cut Line= 3
       2359410.6     13654438.05      2359770.16     13653424.08
      2360208.46      13652339.1
#Sta/Elev= 30
  3921.1  369.92    4130  363.35  4366.4   346.6  4484.6  340.79  4677.7  339.12
  4744.5  335.43  4880.7  334.34  4891.8  332.49  4942.9     329  4970.1  325.15
  4971.1  324.65  5017.1  325.15  5017.5  329.21  5052.6  329.74  5091.6  334.06
  5136.2  338.35    5244  337.35  5271.9  333.01    5286  328.39  5293.4  330.87
  5297.9  333.56    5345  332.23  5393.3  334.15  5557.4  334.25  5661.6  336.68
  5750.9  345.88  5803.4   348.7  5832.3  350.74  5977.4  358.62  6167.1   355.3
#Mann= 12 ,-1 , 0
  3921.1     .05       0  4744.5    .035       0  4891.8      .1       0
  4970.1     .05       0  5017.1      .1       0  5091.6     .05       0
  5271.9     .12       0  5293.4     .05       0  5557.4     .07       0
  5803.4     .05       0  5832.3     .07       0  5977.4     .05       0
Bank Sta=4970.1,5017.1
XS Rating Curve= 0 ,0
Exp/Cntr=0.3,0.1

Type RM Length L Ch R = 1 ,56370   ,696,696,696
BEGIN DESCRIPTION:
CLEAR FORK SANDIES CREEK 50.0
END DESCRIPTION:
XS GIS Cut Line= 3
      2360474.91     13654732.85      2360597.16     13653359.36
      2360453.33     13651705.32
#Sta/Elev= 30
  3614.9  360.15  3863.7  356.38    4015  345.61  4121.6  340.98    4367  337.34
  4543.7  336.27  4641.4  336.22  4747.6     335  4801.3  335.22  4907.8  328.31
    4958  328.32  4964.6  324.39  4965.6  323.89  5011.7  324.39  5028.3  329.54
    5097  332.74  5118.6  332.46  5131.6  328.51  5138.7  325.27  5168.8  330.35
  5289.3  330.68  5411.1  344.15  5449.9  339.76  5631.8  341.16  5649.6  341.27
  5654.7  344.37    5830  346.66  6052.2  348.37  6122.4  346.55  6654.1  352.88
#Mann= 12 ,-1 , 0
  3614.9     .05       0    4367     .12       0  4543.7    .035       0
  4641.4     .12       0  4747.6      .1       0  4964.6     .05       0
  5011.7      .1       0    5097     .05       0  5131.6      .1       0
  5411.1     .05       0  5631.8    .035       0    5830     .05       0
Bank Sta=4964.6,5011.7
XS Rating Curve= 0 ,0
Exp/Cntr=0.3,0.1

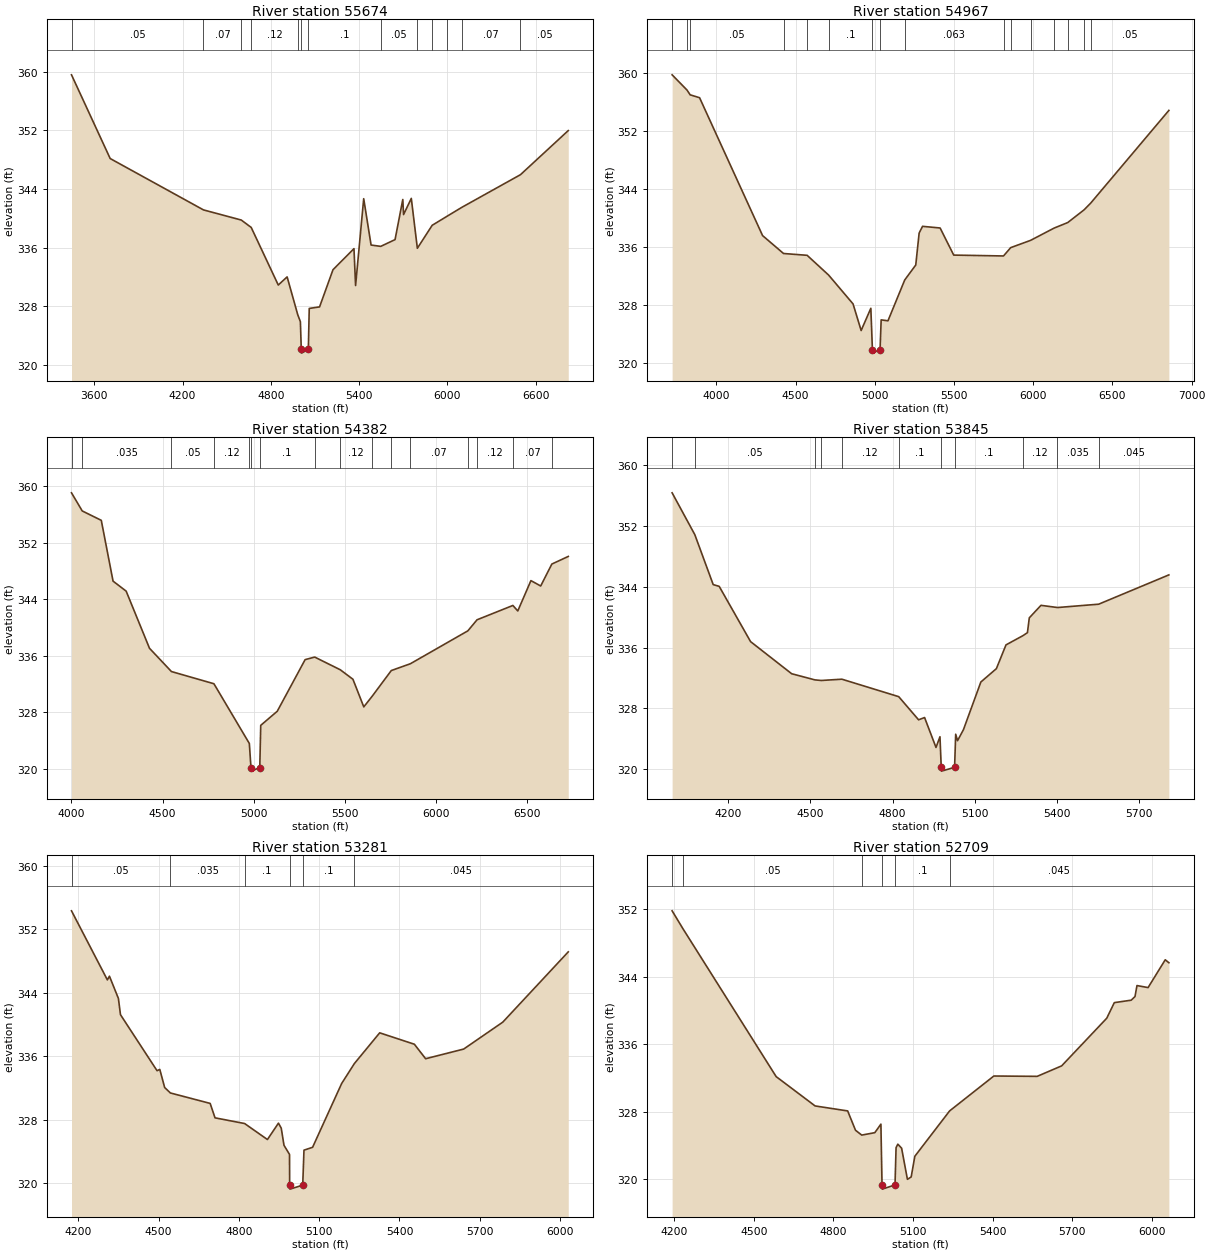
Type RM Length L Ch R = 1 ,55674   ,707,707,707
BEGIN DESCRIPTION:
X18494
END DESCRIPTION:
XS GIS Cut Line= 3
      2361114.94     13654977.38       2361222.8     13653287.44
      2360913.58     13651633.47
#Sta/Elev= 30
  3445.2  359.55  3708.1  348.14  4342.1  341.14  4598.8  339.76  4666.5  338.75
  4850.4   330.9  4910.6  332.01  4982.7  326.86  5000.7   325.9  5006.8  322.12
  5007.8  321.62  5054.7  322.12  5060.9  327.71    5131  327.92  5222.4  332.99
  5364.9  335.86  5375.8  330.83    5431  342.67  5481.1  336.35  5546.7  336.17
  5644.1  337.09  5696.7  342.56  5701.8   340.5  5754.5  342.71  5795.6  335.91
  5896.3  339.04  5997.1  340.27  6097.9  341.49  6496.5  345.94  6821.2  351.95
#Mann= 13 ,-1 , 0
  3445.2     .05       0  4342.1     .07       0  4598.8    .035       0
  4666.5     .12       0  4982.7      .1       0  5006.8     .05       0
  5054.7      .1       0  5546.7     .05       0  5795.6     .07       0
  5896.3     .05       0  5997.1    .035       0  6097.9     .07       0
  6496.5     .05       0
Bank Sta=5006.8,5054.7
XS Rating Curve= 0 ,0
Exp/Cntr=0.3,0.1

Type RM Length L Ch R = 1 ,54967   ,585,585,585
BEGIN DESCRIPTION:
CLEAR FORK SANDIES CREEK 49.0
END DESCRIPTION:
XS GIS Cut Line= 3
      2361575.01     13654874.95        2361825.       13653625.
      2362775.01     13652024.99
#Sta/Elev= 30
  3720.7  359.78  3814.6  357.68  3834.6  357.02    3894  356.62  4291.7  337.59
  4423.9  335.12  4572.9  334.87  4708.6  332.14  4862.8  328.16  4913.8  324.49
    4975  327.56  4984.9  321.87  4985.9  321.37  5033.2  321.87  5040.2  325.96
  5083.1  325.83    5189  331.47  5258.5  333.53  5279.9  337.94  5301.3  338.87
  5412.4  338.64  5498.1   334.9  5812.4  334.78  5857.8  335.93  5982.9  336.93
  6132.2  338.63  6217.8  339.39  6320.7  341.14  6362.5  342.07  6856.2  354.87
#Mann= 16 ,-1 , 0
  3720.7     .05       0  3814.6    .063       0  3834.6     .05       0
  4423.9    .035       0  4572.9     .12       0  4708.6      .1       0
  4984.9     .05       0  5033.2      .1       0    5189    .063       0
  5812.4     .12       0  5857.8     .07       0  5982.9     .05       0
  6132.2     .07       0  6217.8     .05       0  6320.7     .07       0
  6362.5     .05       0
Bank Sta=4984.9,5033.2
XS Rating Curve= 0 ,0
Exp/Cntr=0.3,0.1

Type RM Length L Ch R = 1 ,54382   ,537,537,537
BEGIN DESCRIPTION:
CLEAR FORK SANDIES CREEK 48.0
END DESCRIPTION:
XS GIS Cut Line= 3
      2361675.03     13654774.96        2362275.       13653975.
      2362924.98     13652375.04
#Sta/Elev= 30
  4000.3   359.1  4059.2  356.53  4163.8   355.2  4228.4  346.58  4300.3  345.16
  4428.4  337.06  4548.8  333.76  4782.1  332.03  4976.5  323.56  4985.4  320.14
  4986.4  319.64  5033.8  320.14  5039.1  326.13  5129.8  328.13  5282.8  335.45
  5335.4  335.81  5475.8  334.01  5545.1  332.67  5604.7  328.75  5650.6  330.25
  5755.7   333.9  5860.8  334.87    6176  339.53  6226.6   341.1  6423.2  343.13
  6450.1  342.35  6522.2  346.65  6575.9  345.89  6637.1     349  6727.2  350.08
#Mann= 16 ,-1 , 0
  4000.3    .063       0  4059.2    .035       0  4548.8     .05       0
  4782.1     .12       0  4976.5      .1       0  4985.4     .05       0
  5033.8      .1       0  5335.4     .07       0  5475.8     .12       0
  5650.6      .1       0  5755.7    .035       0  5860.8     .07       0
    6176     .05       0  6226.6     .12       0  6423.2     .07       0
  6637.1     .05       0
Bank Sta=4985.4,5033.8
XS Rating Curve= 0 ,0
Exp/Cntr=0.3,0.1

Type RM Length L Ch R = 1 ,53845   ,564,564,564
BEGIN DESCRIPTION:
CLEAR FORK SANDIES CREEK 47.0
END DESCRIPTION:
XS GIS Cut Line= 3
      2361924.98     13654825.01        2362725.       13654225.
      2363275.02     13653624.97
#Sta/Elev= 30
  3995.1  356.38    4078  350.87  4145.1  344.29    4167  344.06  4281.6  336.78
  4431.6  332.55  4516.4  331.74  4539.7  331.66    4615  331.83  4822.5  329.53
  4895.1  326.48    4917  326.78  4958.7  322.84  4973.2  324.25  4977.8  320.22
  4978.8  319.72  5026.6  320.22  5030.6  324.58  5037.4  323.73  5058.9  325.18
  5122.5  331.46  5179.2  333.22  5214.3  336.35  5276.4  337.57  5292.6  337.96
  5299.4  339.91    5342  341.56  5402.3  341.27  5552.7  341.71  5809.1  345.57
#Mann= 11 ,-1 , 0
  3995.1    .035       0    4078     .05       0  4516.4     .07       0
  4539.7     .05       0    4615     .12       0  4822.5      .1       0
  4977.8     .05       0  5026.6      .1       0  5276.4     .12       0
  5402.3    .035       0  5552.7    .045       0
Bank Sta=4977.8,5026.6
XS Rating Curve= 0 ,0
Exp/Cntr=0.3,0.1

Type RM Length L Ch R = 1 ,53281   ,572,572,572
BEGIN DESCRIPTION:
CLEAR FORK SANDIES CREEK 46.0
END DESCRIPTION:
XS GIS Cut Line= 3
      2362025.03     13654924.99        2362825.       13654725.
      2363775.03     13654324.99
#Sta/Elev= 30
    4175  354.35    4309  345.63  4316.7   346.1  4350.2  343.29  4357.9  341.24
  4494.5  334.17  4504.8  334.33  4522.9  332.05  4544.2  331.36  4692.9  330.04
    4711  328.22  4821.6   327.5  4906.8  325.48    4948  327.55  4958.4  326.91
  4968.7  324.75  4989.3   323.6  4989.8  319.72  4990.8  319.22  5038.6  319.72
  5043.3  324.14  5075.5   324.5    5184  332.55  5231.5  335.07  5326.1  338.95
  5455.6  337.51  5497.7  335.68  5639.8   336.9  5785.9   340.3  6030.4  349.17
#Mann= 6 ,-1 , 0
    4175     .05       0  4544.2    .035       0  4821.6      .1       0
  4989.8     .05       0  5038.6      .1       0  5231.5    .045       0
Bank Sta=4989.8,5038.6
XS Rating Curve= 0 ,0
Exp/Cntr=0.3,0.1

Type RM Length L Ch R = 1 ,52709   ,585,585,585
BEGIN DESCRIPTION:
CLEAR FORK SANDIES CREEK 45.0
END DESCRIPTION:
XS GIS Cut Line= 3
      2362624.99     13655975.02        2362925.       13655225.
      2363724.99     13654525.01
#Sta/Elev= 30
  4192.5  351.77  4233.5  349.64  4584.3  332.16    4731  328.69  4853.6   328.1
  4883.2  325.81  4906.7  325.24  4955.9  325.53  4978.8  326.54    4983  319.35
    4984  318.85  5031.9  319.35  5035.9  323.75  5042.5  324.17  5056.8  323.69
  5078.6  320.01  5092.8  320.29  5106.6  322.74  5237.5   328.1  5404.1  332.23
  5567.4  332.19  5659.5  333.43  5829.4  339.07  5857.8  340.91  5921.4   341.2
  5935.7  341.63  5943.2  342.93    5985  342.69  6049.6  345.98  6063.3  345.63
#Mann= 6 ,-1 , 0
  4192.5    .035       0  4233.5     .05       0  4906.7      .1       0
    4983     .05       0  5031.9      .1       0  5237.5    .045       0
Bank Sta=4983,5031.9
XS Rating Curve= 0 ,0
Exp/Cntr=0.3,0.1