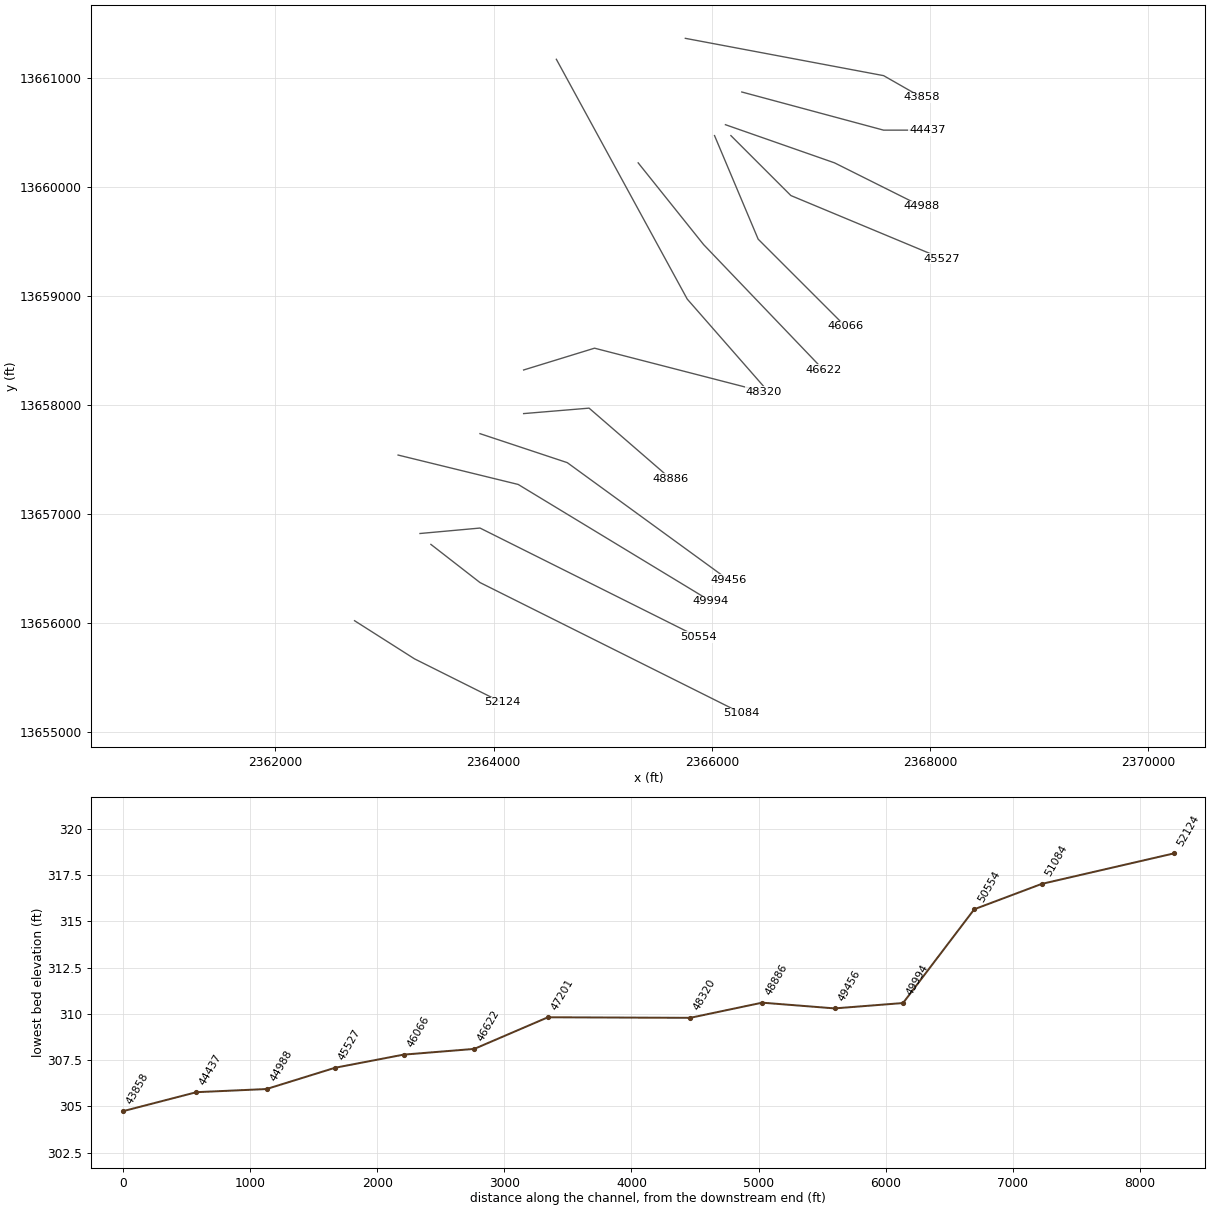
HEC-RAS study CLEAR FORK SANDIES CREEK.prj: CLEAR FORK SANDIES CREEK Base Level Engineering

--- CLEAR FORK SANDIES CREEK.g01 (geometry) --- (continued)

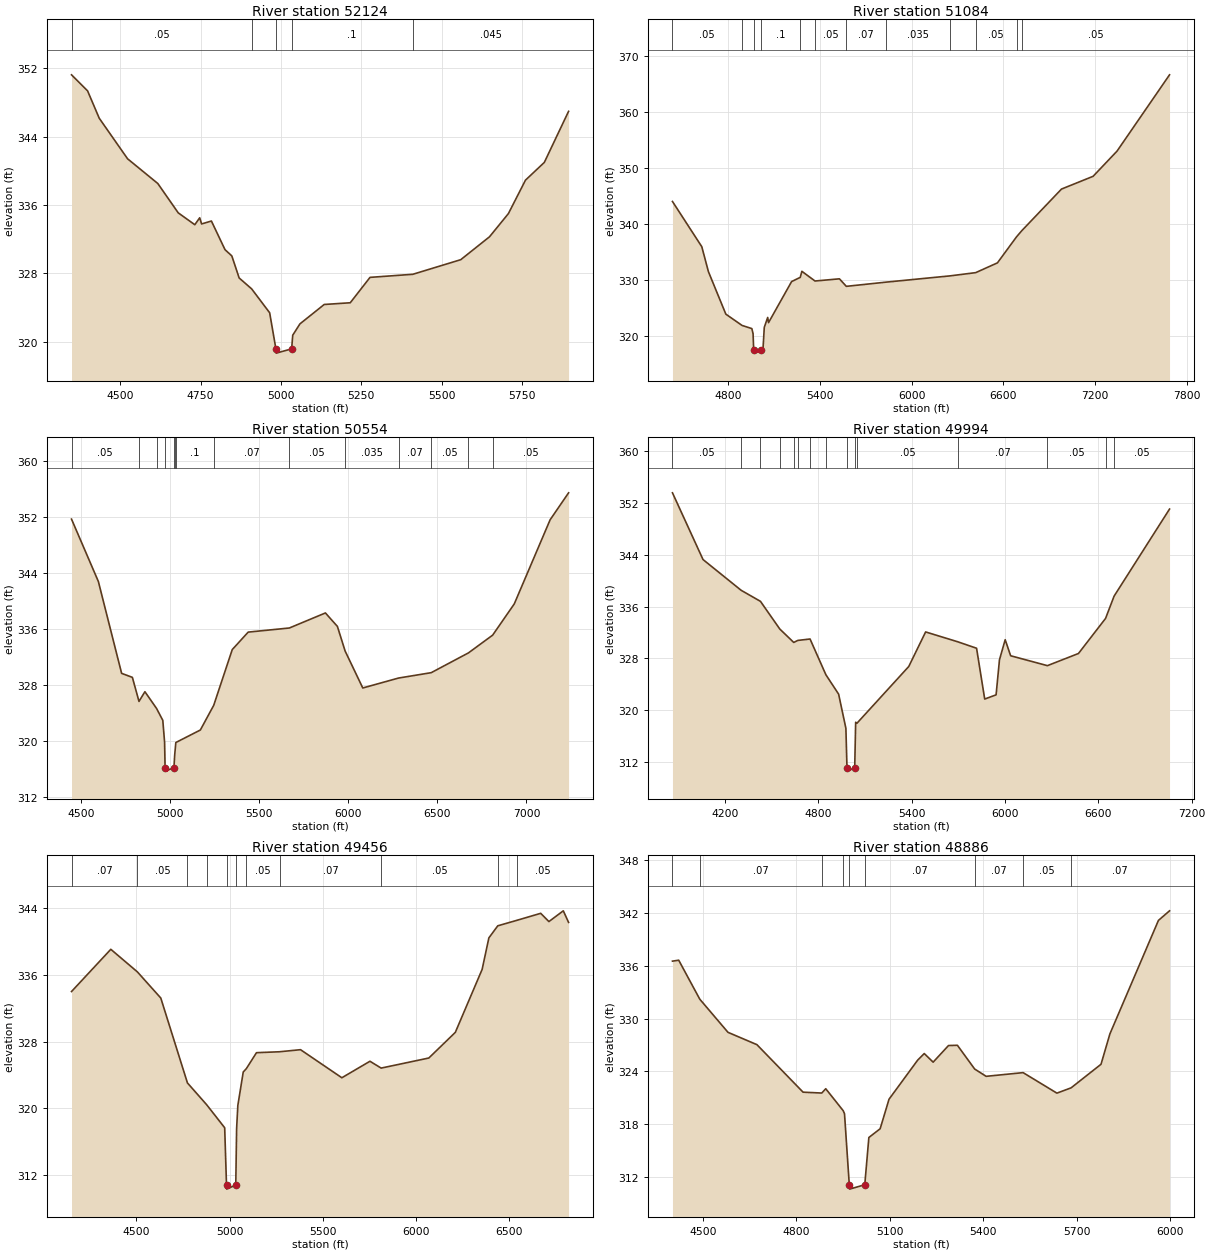
Type RM Length L Ch R = 1 ,52124   ,1040,1040,1040
BEGIN DESCRIPTION:
CLEAR FORK SANDIES CREEK 44.0
END DESCRIPTION:
XS GIS Cut Line= 3
      2362725.01       13656025.        2363275.       13655675.
      2364074.97     13655275.02
#Sta/Elev= 30
  4348.6  351.23  4398.5  349.36  4434.9  346.15    4523  341.41    4617  338.52
  4680.5  335.09  4732.1   333.7  4747.4  334.51  4753.3  333.79  4783.8  334.13
  4826.1  330.78  4847.3  330.05  4870.1  327.47  4909.1  326.19    4965   323.4
  4984.4  319.18  4985.4  318.68  5033.4  319.18  5036.8  320.78  5059.2   322.1
  5134.7  324.37  5215.7  324.57  5277.2  327.54  5410.3   327.9  5559.5  329.61
    5649  332.29  5707.7     335  5760.8  338.91  5819.5  340.99  5894.9  346.96
#Mann= 5 ,-1 , 0
  4348.6     .05       0  4909.1      .1       0  4984.4     .05       0
  5033.4      .1       0  5410.3    .045       0
Bank Sta=4984.4,5033.4
XS Rating Curve= 0 ,0
Exp/Cntr=0.3,0.1

Type RM Length L Ch R = 1 ,51084   ,530,530,530
BEGIN DESCRIPTION:
CLEAR FORK SANDIES CREEK 43.0
END DESCRIPTION:
XS GIS Cut Line= 3
      2363424.97     13656725.02        2363875.       13656375.
      2366274.99       13655175.
#Sta/Elev= 30
  4433.8  344.03  4625.7  335.98  4669.1  331.54  4783.1  323.97  4889.3  321.96
  4953.3   321.4  4961.4  320.48  4965.5  317.53  4966.5  317.03  5015.2  317.53
  5026.3  317.75  5034.7  321.61    5057  323.38  5062.6  322.46  5213.6  329.77
  5270.2  330.52  5280.6   331.6  5366.8  329.87  5526.6  330.26  5571.7  328.92
  5828.5  329.66  6249.2  330.78  6418.5  331.36  6560.8   333.1  6685.9  337.74
  6721.6  338.87  6980.1  346.24  7186.9  348.51  7343.4  352.99  7687.2  366.58
#Mann= 12 ,-1 , 0
  4433.8     .05       0  4889.3      .1       0  4965.5     .05       0
  5015.2      .1       0  5270.2     .07       0  5366.8     .05       0
  5571.7     .07       0  5828.5    .035       0  6249.2     .07       0
  6418.5     .05       0  6685.9    .035       0  6721.6     .05       0
Bank Sta=4965.5,5015.2
XS Rating Curve= 0 ,0
Exp/Cntr=0.3,0.1

Type RM Length L Ch R = 1 ,50554   ,560,560,560
BEGIN DESCRIPTION:
CLEAR FORK SANDIES CREEK 42.0
END DESCRIPTION:
XS GIS Cut Line= 3
      2363325.03       13656825.        2363875.       13656875.
        2365875.       13655875.
#Sta/Elev= 30
  4448.2   351.7  4598.8  342.78  4729.3  329.64  4789.6  329.07  4826.7  325.63
  4859.9  327.02  4925.3  324.62  4960.3  322.92  4970.3  319.79  4973.1  316.16
  4974.1  315.66  5022.8  316.16  5026.9  317.93  5033.3  319.75  5170.9  321.54
  5245.9  325.07  5349.8  333.04  5439.3  335.54  5670.3  336.13  5872.5  338.28
  5939.6  336.36  5983.1  332.83  6082.1  327.55  6282.5  328.97    6466  329.74
  6674.9  332.57  6810.7  335.11  6931.8  339.57  7133.1  351.61  7236.5  355.46
#Mann= 14 ,-1 , 0
  4448.2     .05       0  4826.7    .035       0  4925.3     .05       0
  4973.1     .05       0  5022.8     .05       0  5026.9    .035       0
  5033.3      .1       0  5245.9     .07       0  5670.3     .05       0
  5983.1    .035       0  6282.5     .07       0    6466     .05       0
  6674.9    .035       0  6810.7     .05       0
Bank Sta=4973.1,5022.8
XS Rating Curve= 0 ,0
Exp/Cntr=0.3,0.1

Type RM Length L Ch R = 1 ,49994   ,538,538,538
BEGIN DESCRIPTION:
CLEAR FORK SANDIES CREEK 41.0
END DESCRIPTION:
XS GIS Cut Line= 3
       2363124.2     13657544.59        2364225.       13657275.
      2365988.37      13656204.9
#Sta/Elev= 30
  3861.3   353.6  4057.7  343.29  4302.7  338.54  4427.1  336.83  4551.4  332.55
    4641  330.48  4667.3  330.79  4745.9  331.01  4847.9  325.48  4929.6  322.49
  4976.4   317.2  4983.4  311.09  4984.4  310.59  5033.1  311.09  5039.2  318.14
  5047.5  317.99  5380.6  326.76    5489   332.1  5695.6  330.58  5816.6  329.58
  5868.9  321.73  5942.1  322.38  5963.9   327.8  6000.6   330.9  6035.7  328.42
  6272.1  326.89  6471.8  328.77    6646  334.19    6701  337.64  7057.3  351.09
#Mann= 15 ,-1 , 0
  3861.3     .05       0  4302.7    .035       0  4427.1     .05       0
  4551.4     .07       0    4641     .05       0  4667.3      .1       0
  4745.9     .07       0  4847.9      .1       0  4983.4     .05       0
  5033.1      .1       0  5047.5     .05       0  5695.6     .07       0
  6272.1     .05       0    6646    .035       0    6701     .05       0
Bank Sta=4983.4,5033.1
XS Rating Curve= 0 ,0
Exp/Cntr=0.3,0.1

Type RM Length L Ch R = 1 ,49456   ,570,570,570
BEGIN DESCRIPTION:
CLEAR FORK SANDIES CREEK 40.0
END DESCRIPTION:
XS GIS Cut Line= 3
      2363874.88     13657740.92        2364675.       13657475.
      2366150.02     13656401.25
#Sta/Elev= 30
    4152  334.02  4362.9  339.09  4505.5  336.38  4631.1  333.24  4774.1  323.05
    4877  320.44    4974  317.67  4983.8   310.8  4984.8   310.3  5033.5   310.8
    5038  317.55  5044.6  320.35  5073.6  324.36  5090.4  324.77  5144.7  326.68
  5268.2  326.79  5381.1  327.04  5602.9  323.67  5753.6  325.65  5813.8  324.83
  6069.6  326.04  6211.8  329.12  6355.7  336.68  6391.8  340.46  6439.6  341.91
  6543.6  342.58    6670  343.41    6714  342.42  6791.3  343.71  6819.6  342.32
#Mann= 11 ,-1 , 0
    4152     .07       0  4505.5     .05       0  4774.1     .07       0
    4877      .1       0  4983.8     .05       0  5033.5      .1       0
  5090.4     .05       0  5268.2     .07       0  5813.8     .05       0
  6439.6    .035       0  6543.6     .05       0
Bank Sta=4983.8,5033.5
XS Rating Curve= 0 ,0
Exp/Cntr=0.3,0.1

Type RM Length L Ch R = 1 ,48886   ,566,566,566
BEGIN DESCRIPTION:
CLEAR FORK SANDIES CREEK 39.0
END DESCRIPTION:
XS GIS Cut Line= 3
      2364275.03       13657925.        2364875.       13657975.
      2365624.98     13657325.02
#Sta/Elev= 30
  4402.7  336.52  4422.7  336.63  4490.3   332.2  4580.8  328.43  4673.6  327.03
  4821.6  321.63  4881.6  321.53  4894.4  322.02  4950.5  319.52  4954.6  319.17
  4969.9  311.11  4970.9  310.61  5019.6  311.11  5032.7  316.48  5068.9  317.47
  5097.4  320.83  5189.5  325.28  5210.4  326.02  5238.9  325.04  5288.2  326.93
  5316.7  326.96  5372.1  324.26  5408.9  323.43  5527.5  323.85  5635.9  321.52
  5681.4  322.12  5777.4   324.8  5805.9  328.25  5961.6  341.15  5997.2  342.24
#Mann= 9 ,-1 , 0
  4402.7     .05       0  4490.3     .07       0  4881.6     .12       0
  4950.5     .07       0  4969.9     .05       0  5019.6     .07       0
  5372.1     .07       0  5527.5     .05       0  5681.4     .07       0
Bank Sta=4969.9,5019.6
XS Rating Curve= 0 ,0
Exp/Cntr=0.3,0.1

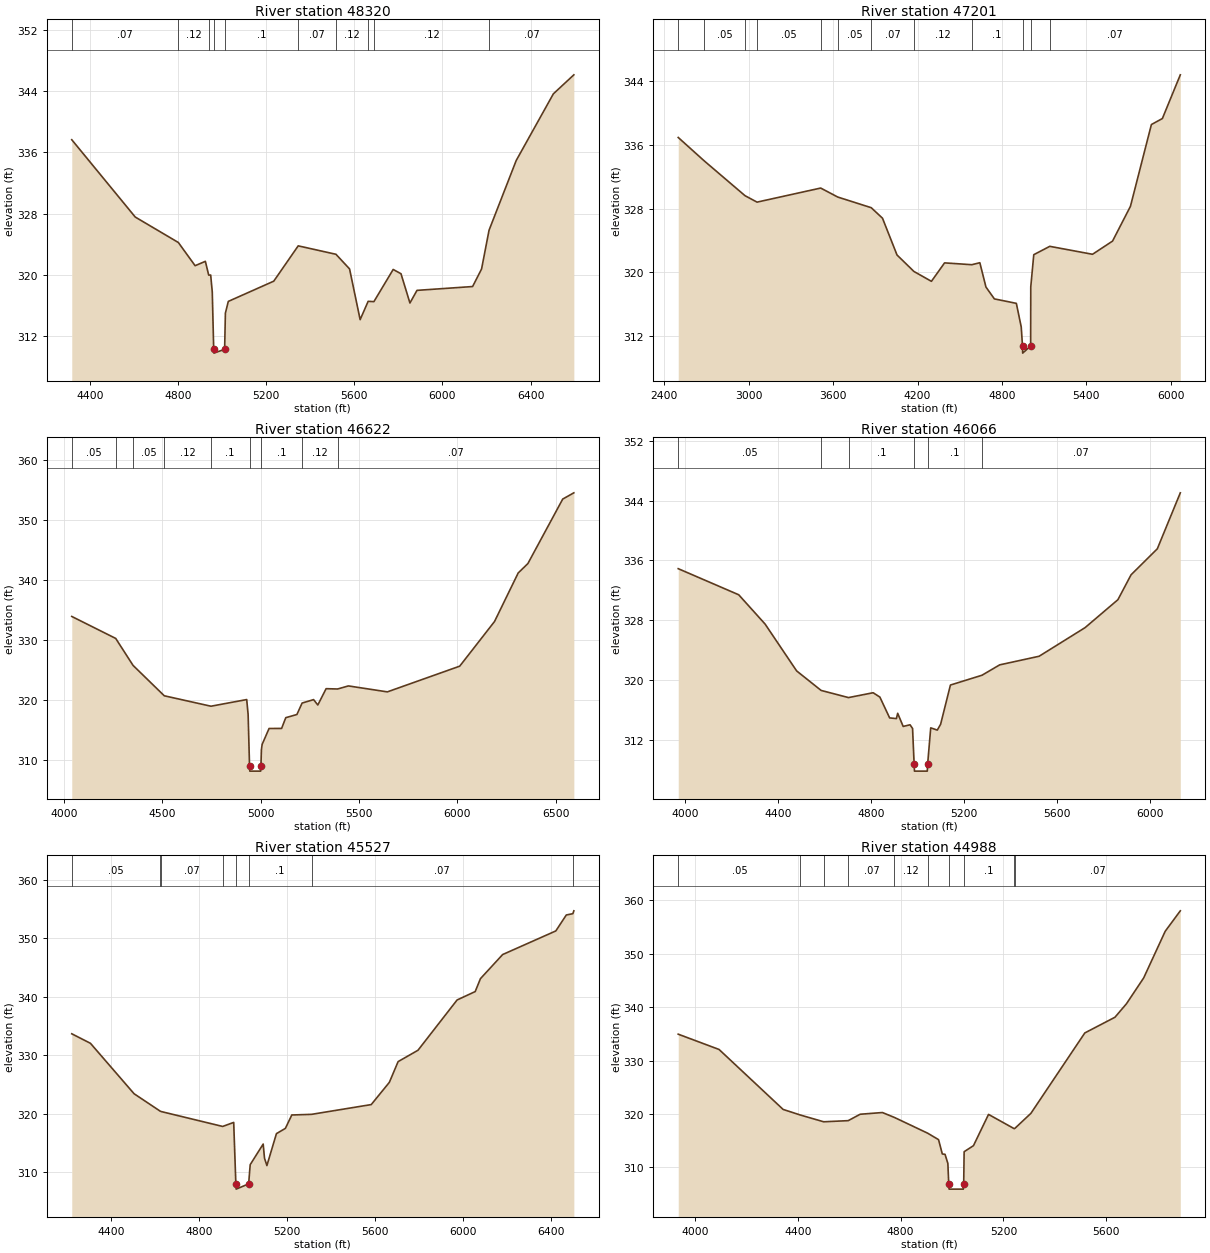
Type RM Length L Ch R = 1 ,48320   ,1119,1119,1119
BEGIN DESCRIPTION:
CLEAR FORK SANDIES CREEK 38.0
END DESCRIPTION:
XS GIS Cut Line= 3
      2364274.97     13658324.99        2364925.       13658525.
      2366475.01       13658125.
#Sta/Elev= 30
    4316  337.64  4604.4  327.55  4800.1  324.23  4876.4   321.2  4922.9  321.77
  4938.1  319.97  4947.1  319.98  4954.3  317.77  4960.8  310.29  4961.8  309.79
  5010.5  310.29  5013.9  315.01  5027.1  316.54  5233.6  319.18  5344.7  323.79
  5516.2  322.69    5578  320.78  5626.1  314.16  5662.5  316.55  5688.6  316.51
  5776.2  320.71  5811.7  320.15  5852.3  316.33  5884.3  317.98    6137  318.48
  6177.7  320.77  6211.7  325.83  6335.1  334.93  6503.9  343.63  6596.9  346.11
#Mann= 10 ,-1 , 0
    4316     .07       0  4800.1     .12       0  4938.1      .1       0
  4960.8     .05       0  5010.5      .1       0  5344.7     .07       0
  5516.2     .12       0  5662.5     .05       0  5688.6     .12       0
  6211.7     .07       0
Bank Sta=4960.8,5010.5
XS Rating Curve= 0 ,0
Exp/Cntr=0.3,0.1

Type RM Length L Ch R = 1 ,47201   ,579,579,579
BEGIN DESCRIPTION:
CLEAR FORK SANDIES CREEK 37.0
END DESCRIPTION:
XS GIS Cut Line= 3
      2364574.99     13661175.01        2365775.       13658975.
      2366474.99     13658175.01
#Sta/Elev= 30
  2499.2  336.94  2683.8     334    2974  329.62  3059.4  328.81  3511.8  330.58
  3633.1  329.45  3871.1  328.11  3951.1  326.79  4054.5  322.16  4174.7  320.09
    4299  318.85  4392.5  321.17  4585.9  320.94  4643.1  321.19  4686.7  318.13
  4746.5  316.64  4902.7  316.08  4937.3  313.12  4946.4  310.72  4947.7  309.82
  5004.3  310.72  5005.2  318.16  5026.6   322.2  5140.4  323.25  5444.2  322.25
  5586.5  323.91  5713.7  328.28  5862.7  338.57  5940.6  339.32  6068.2  344.82
#Mann= 12 ,-1 , 0
  2499.2     .07       0  2683.8     .05       0    2974     .07       0
  3059.4     .05       0  3511.8     .07       0  3633.1     .05       0
  3871.1     .07       0  4174.7     .12       0  4585.9      .1       0
  4946.4     .05       0  5004.3      .1       0  5140.4     .07       0
Bank Sta=4946.4,5004.3
XS Rating Curve= 0 ,0
Exp/Cntr=0.3,0.1

Type RM Length L Ch R = 1 ,46622   ,556,556,556
BEGIN DESCRIPTION:
CLEAR FORK SANDIES CREEK 36.0
END DESCRIPTION:
XS GIS Cut Line= 3
        2365325.       13660225.        2365925.       13659475.
      2367025.03     13658324.97
#Sta/Elev= 30
  4040.1  333.87  4263.5  330.21  4351.6  325.72  4510.2  320.66  4747.6  318.92
  4929.3  320.03  4936.5  317.52  4943.6  309.01    4945  308.11  5000.2  308.11
  5001.6  309.01    5004  311.68  5007.7  312.56  5042.9  315.21  5106.7  315.22
  5127.8  317.01  5184.4  317.54  5210.9  319.45  5269.3  320.02  5290.7  319.12
  5332.8  321.84  5391.5  321.79  5446.1   322.3  5644.2  321.31  6011.9  325.59
  6188.9  333.03  6309.1  341.11  6358.4  342.68  6535.5  353.42    6592  354.46
#Mann= 9 ,-1 , 0
  4040.1     .05       0  4263.5     .07       0  4351.6     .05       0
  4510.2     .12       0  4747.6      .1       0  4943.6     .05       0
  5001.6      .1       0  5210.9     .12       0  5391.5     .07       0
Bank Sta=4943.6,5001.6
XS Rating Curve= 0 ,0
Exp/Cntr=0.3,0.1

Type RM Length L Ch R = 1 ,46066   ,539,539,539
BEGIN DESCRIPTION:
CLEAR FORK SANDIES CREEK 35.0
END DESCRIPTION:
XS GIS Cut Line= 3
      2366025.01     13660474.98        2366425.       13659525.
      2367224.98     13658725.02
#Sta/Elev= 30
  3969.2  334.89  4229.6   331.4  4343.2  327.48  4479.1  321.21  4584.4   318.6
  4702.5  317.64  4808.4  318.29  4837.5  317.71  4879.6  314.92  4908.7  314.83
  4914.2  315.54  4937.9  313.78  4967.4     314  4978.3  313.51  4985.1   308.7
  4986.5   307.8  5041.7   307.8  5043.1   308.7  5056.5  313.59  5084.8  313.29
    5099  314.06  5141.4  319.32  5277.2  320.63  5353.5  322.02  5523.2  323.17
  5721.2     327  5862.6  330.74  5919.2  334.07  6032.3  337.55  6131.3  345.04
#Mann= 6 ,-1 , 0
  3969.2     .05       0  4584.4     .07       0  4702.5      .1       0
  4985.1     .05       0  5043.1      .1       0  5277.2     .07       0
Bank Sta=4985.1,5043.1
XS Rating Curve= 0 ,0
Exp/Cntr=0.3,0.1

Type RM Length L Ch R = 1 ,45527   ,539,539,539
BEGIN DESCRIPTION:
CLEAR FORK SANDIES CREEK 34.0
END DESCRIPTION:
XS GIS Cut Line= 3
      2366174.99     13660475.01        2366725.       13659925.
      2368111.69     13659346.87
#Sta/Elev= 30
  4222.2  333.66  4307.1  332.03  4505.1  323.41  4623.7  320.43  4629.3  320.35
  4907.6  317.81  4957.6   318.5  4967.4  307.99  4968.8  307.09  5025.5  307.99
  5032.5  311.27  5091.5   314.8  5097.5  312.38  5108.4  311.12  5151.7  316.58
  5192.3  317.48  5221.5  319.77  5311.1  319.88  5582.2  321.55  5664.5  325.35
  5704.3   328.9  5794.5  330.84  5972.1  339.44  6054.4  340.88  6078.3  343.09
    6179  347.21  6420.5  351.25  6468.2  353.98  6497.9   354.2  6502.4  354.69
#Mann= 8 ,-1 , 0
  4222.2     .05       0  4623.7     .12       0  4629.3     .07       0
  4907.6      .1       0  4967.4     .05       0  5025.5      .1       0
  5311.1     .07       0  6497.9     .05       0
Bank Sta=4967.4,5025.5
XS Rating Curve= 0 ,0
Exp/Cntr=0.3,0.1

Type RM Length L Ch R = 1 ,44988   ,551,551,551
BEGIN DESCRIPTION:
CLEAR FORK SANDIES CREEK 33.0
END DESCRIPTION:
XS GIS Cut Line= 3
      2366124.98     13660575.01        2367125.       13660225.
      2367924.98     13659825.01
#Sta/Elev= 30
  3934.4  334.93  4093.3  332.07  4342.7  320.85    4410   319.8  4500.5  318.54
  4595.8  318.75  4642.4  319.95    4729  320.27  4775.8  319.35  4904.9  316.41
  4947.4   315.2  4962.1  312.52  4972.7  312.45  4983.7  310.75  4987.2  306.84
  4988.6  305.94    5044  305.94  5045.3  306.84    5047  312.94  5083.3  314.07
    5142  319.92  5241.9  317.25  5245.2  317.34  5306.9  320.12  5516.6  335.16
    5634   338.1  5678.7  340.62  5745.8  345.46  5829.6  354.19  5888.3  358.01
#Mann= 10 ,-1 , 0
  3934.4     .05       0    4410     .07       0  4500.5     .12       0
  4595.8     .07       0  4775.8     .12       0  4904.9      .1       0
  4987.2     .05       0  5045.3      .1       0  5241.9     .12       0
  5245.2     .07       0
Bank Sta=4987.2,5045.3
XS Rating Curve= 0 ,0
Exp/Cntr=0.3,0.1

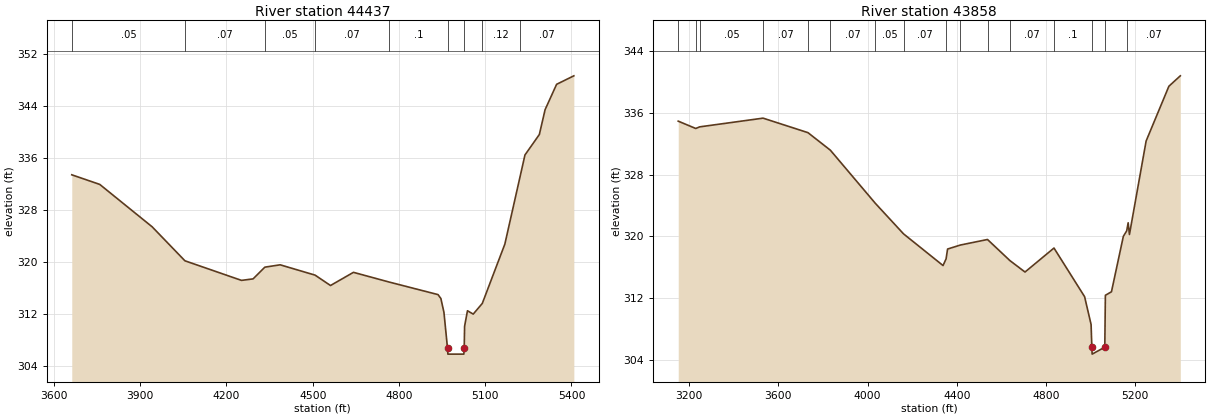
Type RM Length L Ch R = 1 ,44437   ,579,579,579
BEGIN DESCRIPTION:
CLEAR FORK SANDIES CREEK 32.0
END DESCRIPTION:
XS GIS Cut Line= 3
        2366275.       13660875.        2367575.       13660525.
      2367975.01       13660525.
#Sta/Elev= 30
  3661.9  333.42  3759.2  331.94  3941.5   325.4  4055.5  320.16  4252.2  317.14
  4292.5  317.37  4333.5  319.18  4386.8  319.54  4508.2  317.95  4561.8  316.35
  4641.7  318.38  4765.3  316.89  4935.7  314.95  4945.7  314.35  4956.4  312.21
  4968.8  306.67  4970.1  305.77  5025.5  305.77  5026.9  306.67  5028.2  310.06
  5038.2  312.46  5058.2  311.94  5089.8  313.59  5168.2  322.73  5220.9  333.08
  5238.2  336.48  5288.2  339.63  5308.2  343.46  5348.2  347.37  5408.2  348.68
#Mann= 9 ,-1 , 0
  3661.9     .05       0  4055.5     .07       0  4333.5     .05       0
  4508.2     .07       0  4765.3      .1       0  4968.8     .05       0
  5026.9      .1       0  5089.8     .12       0  5220.9     .07       0
Bank Sta=4968.8,5026.9
XS Rating Curve= 0 ,0
Exp/Cntr=0.3,0.1

Type RM Length L Ch R = 1 ,43858   ,1116,1116,1116
BEGIN DESCRIPTION:
CLEAR FORK SANDIES CREEK 31.0
END DESCRIPTION:
XS GIS Cut Line= 3
       2365757.4     13661367.23        2367575.       13661025.
      2367925.04     13660824.98
#Sta/Elev= 30
  3150.5  334.96  3229.1  334.01  3246.8  334.22  3531.1  335.35  3732.5  333.47
  3833.2  331.19  4034.6  324.31  4161.4  320.34  4338.6  316.23  4352.3   317.1
    4359  318.37  4416.3  318.89  4538.1  319.61  4638.8  316.87  4706.4  315.39
  4836.4   318.5  4973.8  312.19  5002.9  308.58  5006.2  305.64  5007.6  304.74
  5064.4  305.64    5067  312.37  5094.3  312.83  5147.6  320.02  5162.8  320.74
  5169.2  321.78    5175  320.26  5249.8  332.38    5352  339.49  5403.2  340.84
#Mann= 16 ,-1 , 0
  3150.5     .05       0  3229.1    .035       0  3246.8     .05       0
  3531.1     .07       0  3732.5     .05       0  3833.2     .07       0
  4034.6     .05       0  4161.4     .07       0  4352.3     .12       0
  4416.3     .07       0  4538.1     .05       0  4638.8     .07       0
  4836.4      .1       0  5006.2     .05       0  5064.4      .1       0
  5162.8     .07       0
Bank Sta=5006.2,5064.4
XS Rating Curve= 0 ,0
Exp/Cntr=0.3,0.1