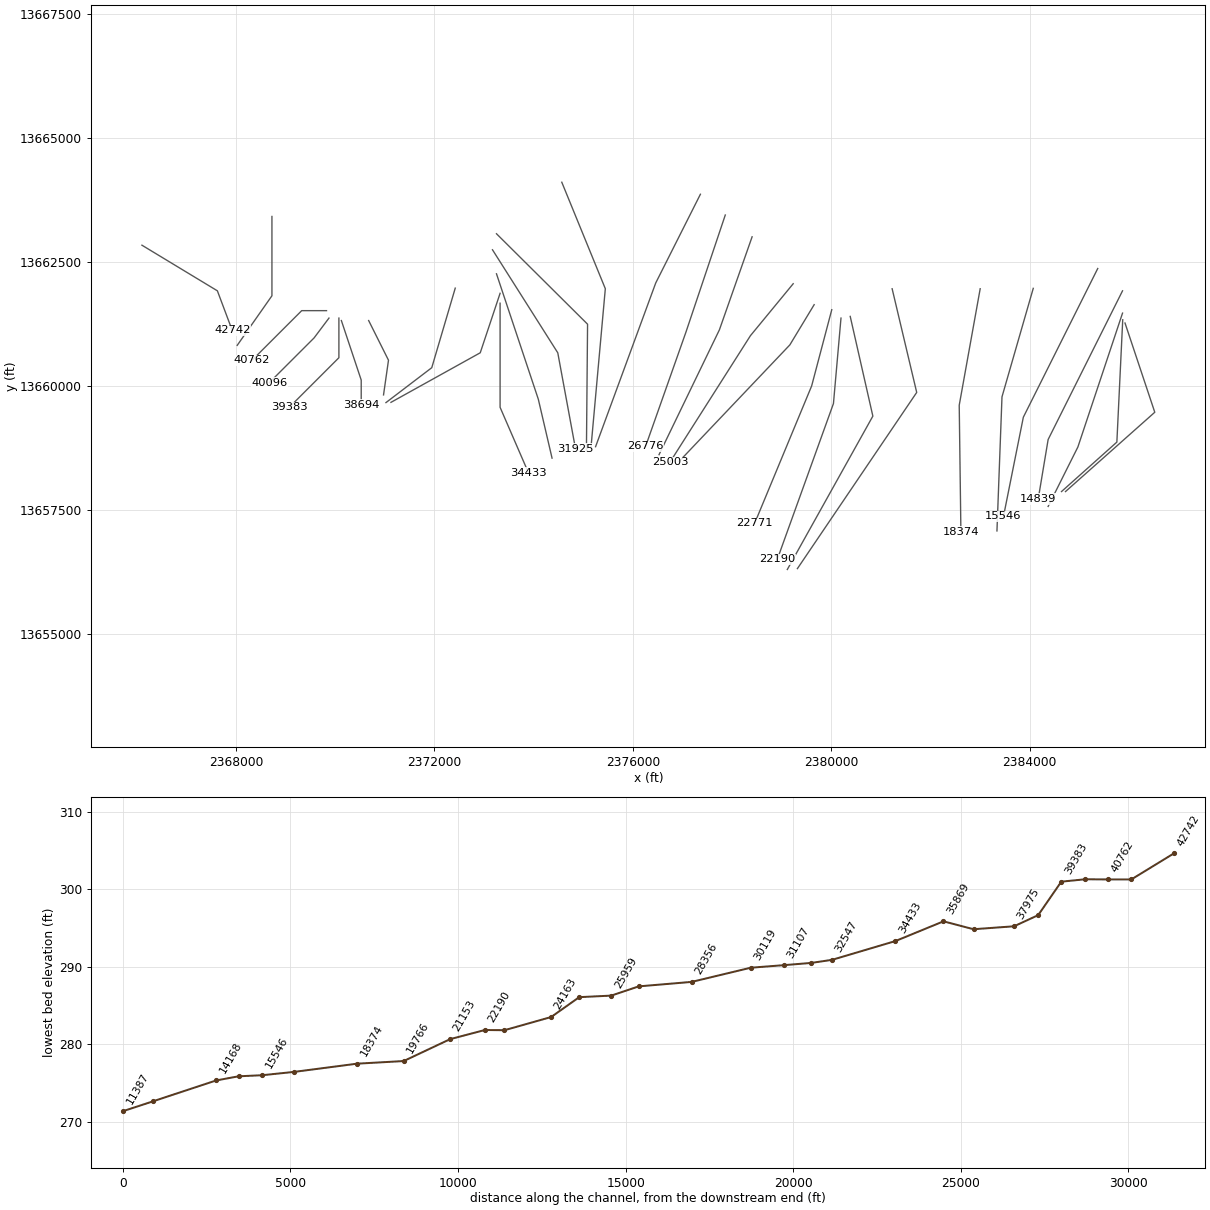
HEC-RAS study CLEAR FORK SANDIES CREEK.prj: CLEAR FORK SANDIES CREEK Base Level Engineering

--- CLEAR FORK SANDIES CREEK.g01 (geometry) --- (continued)

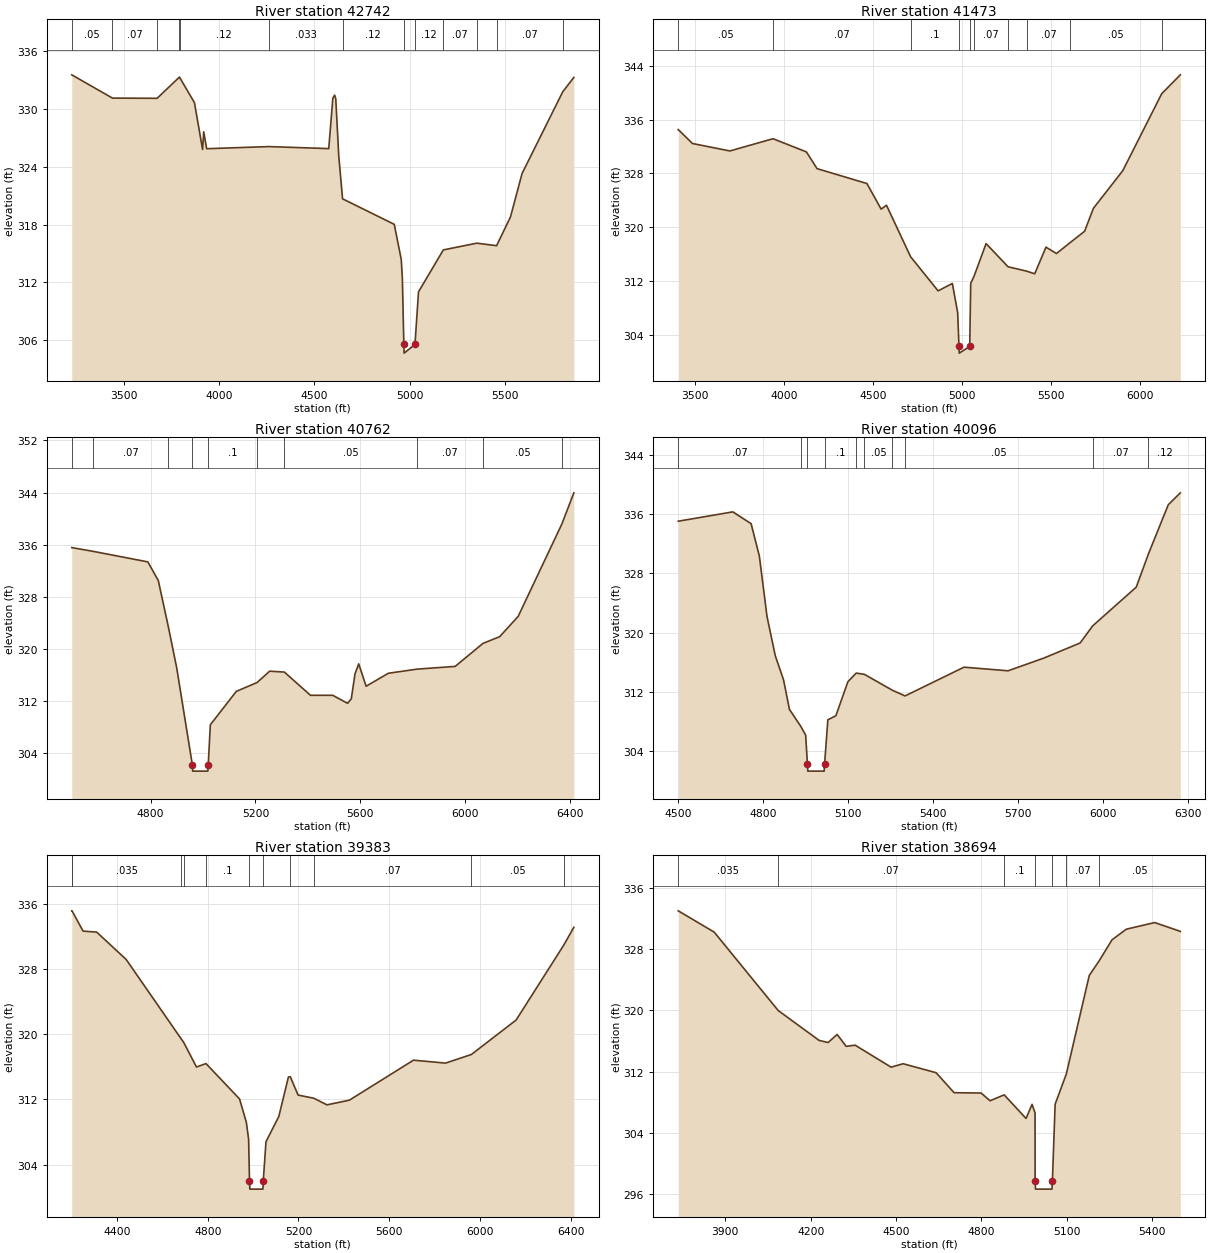
Type RM Length L Ch R = 1 ,42742   ,1269,1269,1269
BEGIN DESCRIPTION:
CLEAR FORK SANDIES CREEK 30.0
END DESCRIPTION:
XS GIS Cut Line= 3
      2366103.85     13662845.47        2367625.       13661925.
      2367925.01     13661124.96
#Sta/Elev= 30
    3228  333.57  3441.4  331.15  3675.6  331.13  3792.7  333.34  3793.3  333.31
  3871.2  330.68  3913.9  325.81  3919.7  327.65  3935.2  325.89    4261  326.11
  4575.3   325.9  4596.9  331.15  4606.3  331.46  4612.2  331.07  4627.7  325.17
  4647.8  320.68  4918.7  318.03  4955.5  314.38  4961.4  312.37  4969.1  305.54
  4970.5  304.64  5027.4  305.54    5046  311.01  5176.2  315.37  5351.4  316.07
  5455.4  315.81  5528.4  318.81  5588.9  323.31    5802   331.8  5860.4   333.3
#Mann= 13 ,-1 , 0
    3228     .05       0  3441.4     .07       0  3675.6    .035       0
  3792.7     .05       0  3793.3     .12       0    4261    .033       0
  4647.8     .12       0  4969.1     .05       0  5027.4     .12       0
  5176.2     .07       0  5351.4     .12       0  5455.4     .07       0
    5802     .05       0
Bank Sta=4969.1,5027.4
XS Rating Curve= 0 ,0
Exp/Cntr=0.3,0.1

Type RM Length L Ch R = 1 ,41473   ,711,711,711
BEGIN DESCRIPTION:
CLEAR FORK SANDIES CREEK 29.0
END DESCRIPTION:
XS GIS Cut Line= 3
        2368725.     13663425.01        2368725.       13661825.
      2368024.98     13660824.97
#Sta/Elev= 30
    3404  334.52    3484  332.45    3694  331.34  3936.5  333.16    4124   331.2
    4184  328.71    4464   326.5    4544  322.69    4574  323.27  4709.5  315.61
    4864  310.54    4944  311.64    4974   307.3  4981.2  302.28  4982.7  301.28
  5041.6  302.28  5047.2  311.65  5066.8  312.77  5133.5  317.57  5256.8  314.12
  5361.2  313.47  5406.8  313.08    5470  317.04  5528.9  316.09  5607.7  317.75
  5687.1   319.4  5736.4  322.81  5901.6  328.41  6120.1  339.85  6224.7  342.66
#Mann= 10 ,-1 , 0
    3404     .05       0  3936.5     .07       0  4709.5      .1       0
  4981.2     .05       0  5041.6      .1       0  5066.8     .07       0
  5256.8     .05       0  5361.2     .07       0  5607.7     .05       0
  6120.1     .07       0
Bank Sta=4981.2,5041.6
XS Rating Curve= 0 ,0
Exp/Cntr=0.3,0.1

Type RM Length L Ch R = 1 ,40762   ,666,666,666
BEGIN DESCRIPTION:
CLEAR FORK SANDIES CREEK 28.0
END DESCRIPTION:
XS GIS Cut Line= 3
        2369825.       13661525.        2369325.       13661525.
      2368325.01     13660525.01
#Sta/Elev= 30
  4499.8  335.56  4579.3     335  4789.8  333.37  4829.8   330.5  4867.8  323.45
  4899.8  317.14  4959.4  302.28  4960.9  301.28  5018.6  301.28  5020.1  302.28
  5028.1  308.39  5127.1  313.51  5206.4  314.87  5254.4  316.61  5310.4  316.47
  5409.9  312.91  5494.8  312.91  5551.3  311.68  5565.5  312.36  5579.6  316.19
  5593.8  317.73  5622.1   314.3  5706.9  316.29  5815.8  316.92  5961.5  317.34
  6067.6  320.87  6131.2   321.9  6201.9  325.02  6368.7  339.21    6414  343.96
#Mann= 10 ,-1 , 0
  4499.8    .035       0  4579.3     .07       0  4867.8      .1       0
  4959.4     .05       0  5020.1      .1       0  5206.4     .07       0
  5310.4     .05       0  5815.8     .07       0  6067.6     .05       0
  6368.7    .035       0
Bank Sta=4959.4,5020.1
XS Rating Curve= 0 ,0
Exp/Cntr=0.3,0.1

Type RM Length L Ch R = 1 ,40096   ,713,713,713
BEGIN DESCRIPTION:
CLEAR FORK SANDIES CREEK 27.0
END DESCRIPTION:
XS GIS Cut Line= 3
      2369874.99     13661374.99        2369575.       13660975.
      2368674.98     13660074.98
#Sta/Elev= 30
  4499.9  335.03  4692.6  336.29  4757.2   334.7  4786.3  330.33  4813.4  322.16
  4842.6  316.87  4871.8  313.61  4892.6  309.63  4933.3   307.3  4949.9  306.15
    4956   302.3  4957.5   301.3  5015.2   301.3  5016.7   302.3  5028.2  308.23
  5056.5  308.77  5098.9  313.36  5128.2  314.53  5157.4  314.36  5256.3  312.21
  5300.9  311.45    5509  315.33  5664.6  314.84  5791.8  316.57  5919.1   318.6
  5963.2   320.9  6117.1  326.13  6160.3  330.63  6230.2  337.25  6272.7  338.86
#Mann= 10 ,-1 , 0
  4499.9     .07       0  4933.3      .1       0    4956     .05       0
  5016.7      .1       0  5128.2     .07       0  5157.4     .05       0
  5256.3     .07       0  5300.9     .05       0  5963.2     .07       0
  6160.3     .12       0
Bank Sta=4956,5016.7
XS Rating Curve= 0 ,0
Exp/Cntr=0.3,0.1

Type RM Length L Ch R = 1 ,39383   ,689,689,689
BEGIN DESCRIPTION:
CLEAR FORK SANDIES CREEK 26.0
END DESCRIPTION:
XS GIS Cut Line= 3
        2370075.     13661374.97        2370075.       13660575.
      2369074.99     13659574.99
#Sta/Elev= 30
  4200.4  335.13  4201.5  335.13  4250.4  332.64  4310.4  332.52  4440.4  329.16
  4682.1  319.46    4694  318.99  4750.4  315.97  4792.4  316.39  4940.4  312.05
  4970.4  309.18  4980.4  307.09  4984.2  301.99  4985.7  300.99  5043.4  300.99
  5044.9  301.99  5056.9  306.81  5113.5   309.9  5155.9  314.75  5164.2  314.78
  5198.4  312.53  5267.9  312.14  5325.6  311.33  5424.6   311.9  5707.5  316.81
  5848.9  316.45    5963  317.51    6160  321.73  6370.7  330.95  6414.6  333.11
#Mann= 11 ,-1 , 0
  4200.4     .07       0  4201.5    .035       0  4682.1     .07       0
    4694    .035       0  4792.4      .1       0  4984.2     .05       0
  5044.9      .1       0  5164.2     .05       0  5267.9     .07       0
    5963     .05       0  6370.7     .07       0
Bank Sta=4984.2,5044.9
XS Rating Curve= 0 ,0
Exp/Cntr=0.3,0.1

Type RM Length L Ch R = 1 ,38694   ,719,719,719
BEGIN DESCRIPTION:
CLEAR FORK SANDIES CREEK 25.0
END DESCRIPTION:
XS GIS Cut Line= 3
      2370125.01     13661324.98        2370525.       13660125.
        2370525.     13659624.99
#Sta/Elev= 30
  3734.6  332.98  3861.1   330.2  4086.1  319.97    4230  316.07  4261.6   315.8
  4293.2  316.85  4324.9   315.3  4356.5  315.45    4483  312.58  4525.1  313.03
  4641.1  311.86  4704.3  309.25  4799.2  309.21  4830.8   308.2  4880.4  308.97
  4957.3  305.89  4978.4  307.73  4988.9  306.61  4989.1  297.67  4990.6  296.67
  5048.3  296.67  5049.8  297.67  5059.5  307.75  5098.8  311.69  5179.5  324.55
    5214  326.44  5259.5   329.2  5309.5  330.58  5409.5  331.45  5499.5   330.3
#Mann= 7 ,-1 , 0
  3734.6    .035       0  4086.1     .07       0  4880.4      .1       0
  4989.1     .05       0  5049.8      .1       0  5098.8     .07       0
    5214     .05       0
Bank Sta=4989.1,5049.8
XS Rating Curve= 0 ,0
Exp/Cntr=0.3,0.1

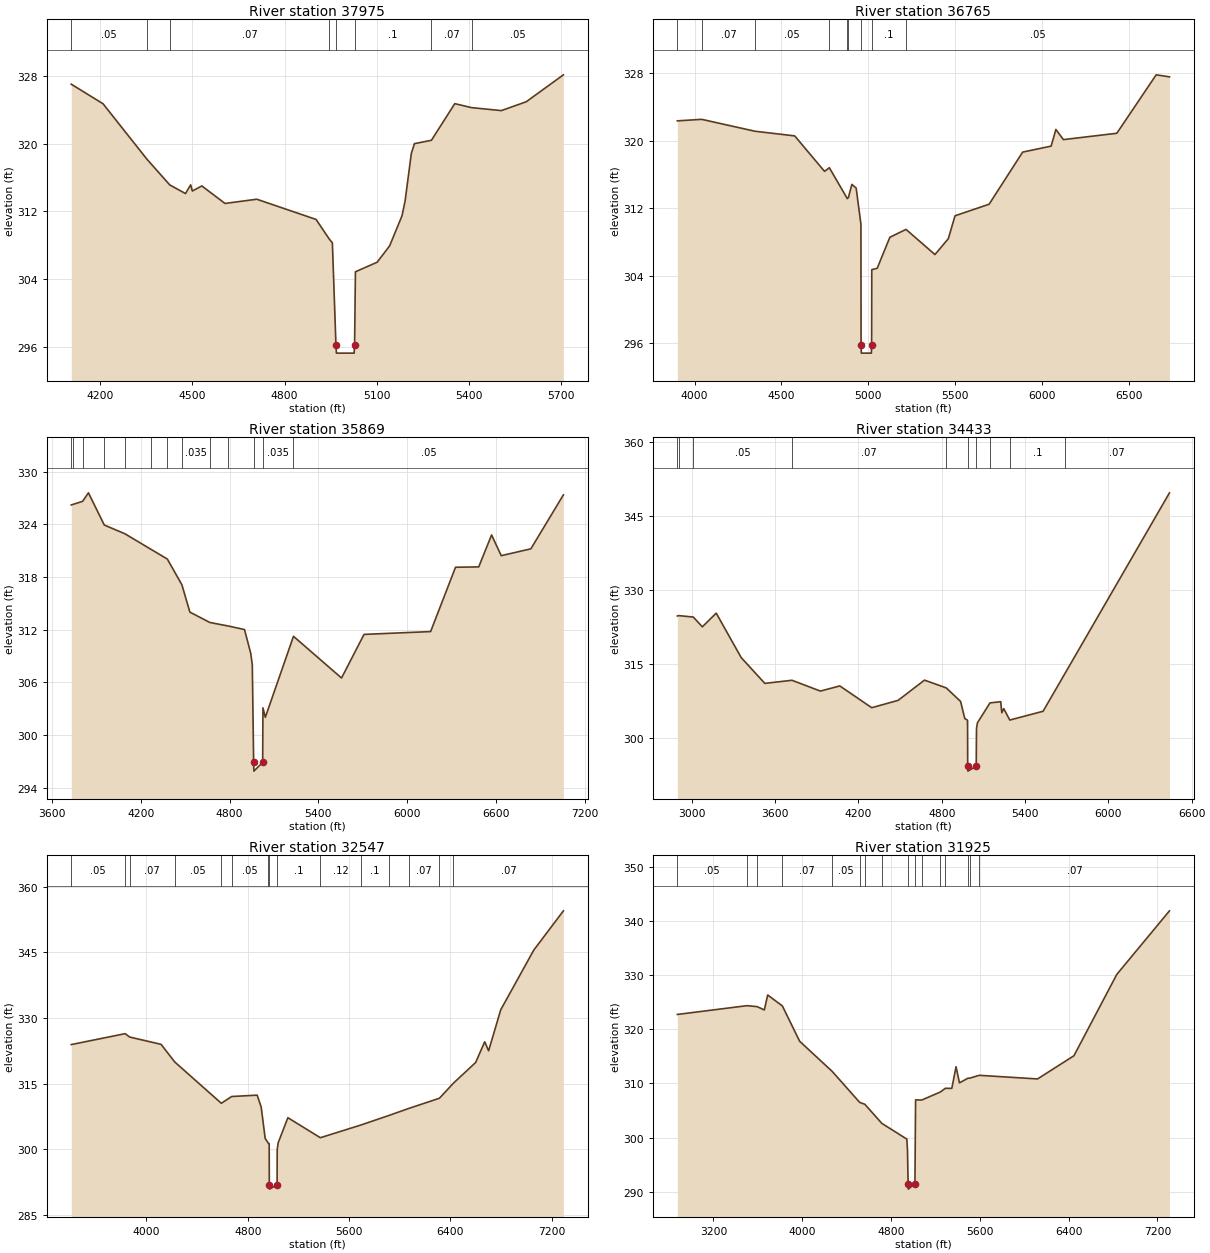
Type RM Length L Ch R = 1 ,37975   ,1210,1210,1210
BEGIN DESCRIPTION:
CLEAR FORK SANDIES CREEK 24.0
END DESCRIPTION:
XS GIS Cut Line= 3
        2370675.       13661325.        2371075.       13660525.
      2370975.01     13659825.04
#Sta/Elev= 30
  4105.6  327.03    4209  324.72  4351.9  318.16  4426.2  315.12  4477.3   314.1
  4494.1  315.13  4499.7   314.4  4530.5     315  4605.9  312.93  4709.3  313.43
  4902.2  311.04    4945  308.73  4955.3  308.27  4966.9  296.23  4968.4  295.23
  5026.1  295.23  5027.6  296.23  5030.3  304.85    5101  305.98  5141.5  307.91
  5181.9  311.47    5192  313.23  5212.2  318.84  5222.3     320  5277.6   320.4
  5353.6  324.73  5408.3  324.26  5505.1  323.91  5585.9  324.95  5707.1  328.14
#Mann= 8 ,-1 , 0
  4105.6     .05       0  4351.9    .035       0  4426.2     .07       0
    4945      .1       0  4966.9     .05       0  5027.6      .1       0
  5277.6     .07       0  5408.3     .05       0
Bank Sta=4966.9,5027.6
XS Rating Curve= 0 ,0
Exp/Cntr=0.3,0.1

Type RM Length L Ch R = 1 ,36765   ,896,896,896
BEGIN DESCRIPTION:
X18493
END DESCRIPTION:
XS GIS Cut Line= 3
      2372421.03     13661979.36      2371947.52     13660374.04
      2371023.89     13659669.77
#Sta/Elev= 30
  3900.8  322.35  4041.1  322.53  4348.1  321.12  4576.9  320.57  4748.7  316.37
  4776.5   316.8    4880  313.14  4886.5  313.28  4906.2  314.83  4930.9  314.39
  4958.4  310.12  4959.2  295.85  4960.7  294.85  5018.5  294.85    5020  295.85
  5020.9  304.73  5052.2   304.9  5125.2  308.57  5218.2   309.5  5384.8  306.52
  5461.9   308.4  5500.5  311.11  5696.9  312.48  5890.1  318.65  6054.3  319.36
  6081.5  321.33  6125.1  320.13  6432.6  320.88  6659.3   327.8    6736  327.56
#Mann= 9 ,-1 , 0
  3900.8     .05       0  4041.1     .07       0  4348.1     .05       0
  4776.5     .07       0    4880    .035       0  4886.5      .1       0
  4959.2     .05       0    5020      .1       0  5218.2     .05       0
Bank Sta=4959.2,5020
XS Rating Curve= 0 ,0
Exp/Cntr=0.3,0.1

Type RM Length L Ch R = 1 ,35869   ,1436,1436,1436
BEGIN DESCRIPTION:
CLEAR FORK SANDIES CREEK 23.0
END DESCRIPTION:
XS GIS Cut Line= 3
      2373325.01     13661875.03        2372925.       13660675.
      2371124.97     13659674.98
#Sta/Elev= 30
  3730.9   326.2  3744.3  326.27  3807.5  326.61  3846.9  327.58    3954  323.91
  4093.8  322.91  4268.5  321.15    4380  320.03  4478.2   317.1    4532  313.99
  4666.3  312.81  4792.7   312.4    4901     312  4943.1   309.3  4953.7  307.97
  4962.8  296.87  4964.3  295.87  5023.7  296.87  5025.6  303.08  5041.6     302
  5231.9  311.23  5556.4  306.48  5708.5  311.45  6158.1  311.77  6326.3   319.1
    6483  319.14  6569.9  322.78  6635.1  320.42  6835.3   321.2    7055  327.35
#Mann= 13 ,-1 , 0
  3730.9     .05       0  3744.3    .035       0  3807.5     .05       0
    3954    .035       0  4093.8     .05       0  4268.5    .035       0
    4380     .07       0  4478.2    .035       0  4666.3     .07       0
  4792.7    .035       0  4962.8    .035       0  5023.7    .035       0
  5231.9     .05       0
Bank Sta=4962.8,5023.7
XS Rating Curve= 0 ,0
Exp/Cntr=0.3,0.1

Type RM Length L Ch R = 1 ,34433   ,1886,1886,1886
BEGIN DESCRIPTION:
CLEAR FORK SANDIES CREEK 22.0
END DESCRIPTION:
XS GIS Cut Line= 3
        2373325.       13661675.        2373325.       13659575.
      2373899.04     13658249.57
#Sta/Elev= 30
  2895.9  324.75  2905.4  324.83  3010.7  324.54  3075.9  322.56  3175.9  325.33
  3355.9  316.32  3525.9   311.1  3721.5  311.73  3925.9  309.54  4065.9  310.58
  4295.9  306.17  4485.9  307.66  4675.9  311.76  4832.7  310.18  4935.9  307.44
  4965.9  303.98  4985.9  303.64    4987  294.32  4988.5  293.32  5048.3  294.32
  5050.4  301.97  5057.3  303.11  5147.4  307.14  5224.8  307.39  5232.6  305.15
  5246.5  305.99  5290.2  303.67  5529.9  305.45  5686.9  313.07  6440.3  349.71
#Mann= 10 ,-1 , 0
  2895.9    .035       0  2905.4     .07       0  3010.7     .05       0
  3721.5     .07       0  4832.7      .1       0    4987     .05       0
  5048.3      .1       0  5147.4    .035       0  5290.2      .1       0
  5686.9     .07       0
Bank Sta=4987,5048.3
XS Rating Curve= 0 ,0
Exp/Cntr=0.3,0.1

Type RM Length L Ch R = 1 ,32547   ,622,622,622
BEGIN DESCRIPTION:
X18492
END DESCRIPTION:
XS GIS Cut Line= 3
      2373252.54     13662268.02       2374095.6     13659738.86
      2374372.68     13658549.68
#Sta/Elev= 30
  3406.3  323.91  3831.9   326.4  3867.4  325.63  4115.7  323.96    4223  319.95
  4591.5   310.5  4673.1  312.05  4874.7  312.36  4906.3  309.64  4937.9  302.47
    4963  301.37  4969.5  301.29  4970.5   291.9    4972   290.9  5031.9   291.9
  5032.8   299.9  5040.3  301.46  5117.1  307.21  5373.6  302.64  5690.7  305.51
  5912.9   307.7  6070.4  309.31  6314.5  311.66  6424.5  315.09  6599.9  319.81
  6671.8  324.54  6702.6  322.49  6798.4  331.85    7059  345.47  7293.3  354.45
#Mann= 15 ,-1 , 0
  3406.3     .05       0  3831.9    .035       0  3867.4     .07       0
    4223     .05       0  4591.5     .07       0  4673.1     .05       0
    4963      .1       0  4970.5     .05       0  5031.9      .1       0
  5373.6     .12       0  5690.7      .1       0  5912.9    .035       0
  6070.4     .07       0  6314.5     .12       0  6424.5     .07       0
Bank Sta=4970.5,5031.9
XS Rating Curve= 0 ,0
Exp/Cntr=0.3,0.1

Type RM Length L Ch R = 1 ,31925   ,818,818,818
BEGIN DESCRIPTION:
X18491
END DESCRIPTION:
XS GIS Cut Line= 3
      2373171.69      13662753.1      2374488.25     13660674.31
      2374846.27      13658734.1
#Sta/Elev= 30
  2874.9  322.73  3502.3  324.35  3594.3  324.17  3658.3  323.56  3688.8  326.32
    3821   324.3  3976.9  317.78    4270  312.22  4517.5   306.5  4563.9  306.16
  4716.6  302.64  4942.2  299.73  4948.2  297.76  4953.9   291.5  4955.4   290.5
  5015.3   291.5  5021.1  306.97  5076.7  306.94  5244.5  308.42    5289   309.1
  5347.6  309.09  5385.7  313.09  5416.2  310.11  5494.3  310.98    5507  310.96
  5593.9   311.5  6119.8  310.83  6447.8  315.11  6833.9  330.12  7308.5  341.85
#Mann= 16 ,-1 , 0
  2874.9     .05       0  3502.3    .035       0  3594.3     .05       0
    3821     .07       0    4270     .05       0  4517.5     .07       0
  4563.9     .05       0  4716.6      .1       0  4953.9     .05       0
  5015.3      .1       0  5076.7     .12       0  5244.5     .07       0
    5289     .12       0  5494.3     .07       0    5507    .035       0
  5593.9     .07       0
Bank Sta=4953.9,5015.3
XS Rating Curve= 0 ,0
Exp/Cntr=0.3,0.1

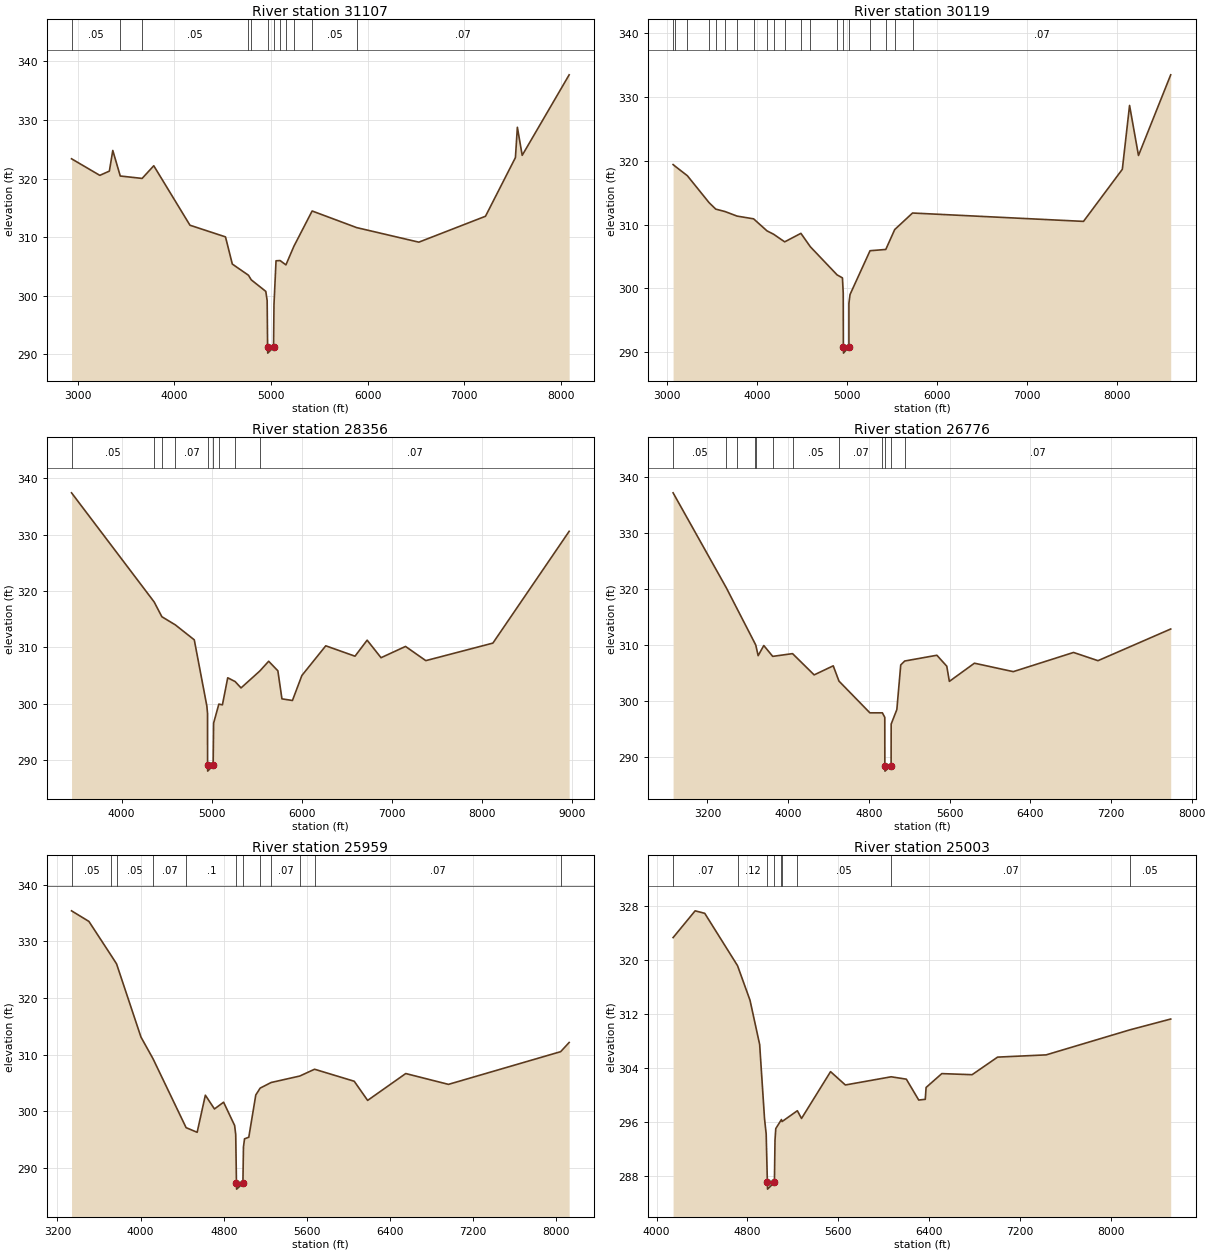
Type RM Length L Ch R = 1 ,31107   ,988,988,988
BEGIN DESCRIPTION:
X18490
END DESCRIPTION:
XS GIS Cut Line= 3
      2373252.56     13663076.43      2375088.79     13661251.75
       2375065.7     13658688.92
#Sta/Elev= 30
  2934.4  323.38  3227.1  320.55    3326  321.28  3361.4   324.8  3438.8  320.44
    3665  320.03  3785.7  322.19  4160.4  312.04  4528.1  310.05  4598.9  305.41
  4766.2   303.5  4794.8  302.72  4945.3  300.75  4959.5  299.19  4964.1  291.21
  4965.6  290.21  5025.5  291.21  5030.2  298.53  5051.4  305.97  5093.6  306.01
  5153.7  305.27  5236.4  308.45  5425.2  314.47  5886.8  311.63  6529.9  309.15
  7219.9  313.57  7529.9  323.59  7549.9  328.76  7599.9  323.97    8086  337.71
#Mann= 12 ,-1 , 0
  2934.4     .05       0  3438.8    .035       0    3665     .05       0
  4766.2     .07       0  4794.8      .1       0  4964.1     .05       0
  5025.5      .1       0  5093.6     .12       0  5153.7     .07       0
  5236.4     .12       0  5425.2     .05       0  5886.8     .07       0
Bank Sta=4964.1,5025.5
XS Rating Curve= 0 ,0
Exp/Cntr=0.3,0.1

Type RM Length L Ch R = 1 ,30119   ,1763,1763,1763
BEGIN DESCRIPTION:
X18489
END DESCRIPTION:
XS GIS Cut Line= 3
      2374569.12     13664115.81      2375446.81     13661967.78
      2375158.14      13658769.4
#Sta/Elev= 30
  3065.5  319.38  3090.7  319.09  3224.4  317.63  3465.7  313.42  3539.8  312.41
    3645  312.02  3775.9  311.32  3960.4  310.89  4109.1  309.01  4182.8  308.48
    4306  307.29  4486.2  308.62  4591.3  306.52  4888.8  302.12  4948.2  301.65
  4956.8  299.26  4958.4  290.88  4959.9  289.88  5020.1  290.88  5020.2  297.69
  5032.4  299.05  5254.8   305.9  5429.9   306.1    5529  309.21  5727.3   311.8
  7627.8  310.49  8059.5  318.64  8139.9  328.63  8239.1   320.8  8597.3  333.42
#Mann= 20 ,-1 , 0
  3065.5     .05       0  3090.7     .07       0  3224.4     .07       0
  3465.7     .05       0  3539.8     .07       0    3645     .05       0
  3775.9     .07       0  3960.4    .035       0  4109.1     .07       0
  4182.8    .035       0    4306    .035       0  4486.2     .05       0
  4591.3     .07       0  4888.8      .1       0  4958.4     .05       0
  5020.1      .1       0  5254.8     .12       0  5429.9     .07       0
    5529     .05       0  5727.3     .07       0
Bank Sta=4958.4,5020.1
XS Rating Curve= 0 ,0
Exp/Cntr=0.3,0.1

Type RM Length L Ch R = 1 ,28356   ,1580,1580,1580
BEGIN DESCRIPTION:
X18488
END DESCRIPTION:
XS GIS Cut Line= 3
       2377363.9     13663873.31       2376463.1     13662083.26
      2375250.49     13658780.34
#Sta/Elev= 30
  3445.4  337.42  4362.3  318.06  4447.8  315.44  4597.6  313.99  4807.4  311.34
  4946.9  299.62  4954.8  298.25    4955  289.05  4956.5  288.05  5016.9  289.05
    5022  296.57  5080.2  299.94  5119.8  299.81  5178.7  304.61  5260.8  303.94
  5326.3  302.81    5534   305.8  5633.1  307.54  5735.1  305.85  5780.3  300.87
  5896.9  300.58  6001.4  305.01  6266.6  310.28  6591.3  308.44  6725.8  311.28
  6880.2  308.17  7151.9  310.17  7377.1  307.65  8121.3  310.76  8967.8  330.59
#Mann= 9 ,-1 , 0
  3445.4     .05       0  4362.3     .07       0  4447.8     .05       0
  4597.6     .07       0    4955     .05       0  5016.9     .07       0
  5080.2     .12       0  5260.8    .035       0    5534     .07       0
Bank Sta=4955,5016.9
XS Rating Curve= 0 ,0
Exp/Cntr=0.3,0.1

Type RM Length L Ch R = 1 ,26776   ,817,817,817
BEGIN DESCRIPTION:
X18487
END DESCRIPTION:
XS GIS Cut Line= 3
       2377865.4     13663454.38      2377070.81     13661087.52
      2376259.95     13658790.09
#Sta/Elev= 30
  2859.3  337.21  3386.8  320.24  3488.2  316.68  3671.7  310.26  3679.5  309.95
  3702.5  308.11  3758.3  309.92  3846.8  307.98  4043.5  308.47  4257.6  304.67
  4446.8  306.29  4503.6  303.56  4810.1  297.89  4933.9  297.89  4957.8  297.08
  4958.4  288.47  4959.9  287.47  5020.4  288.47  5021.1  295.88  5077.4  298.47
    5116  306.45  5155.4  307.15  5474.3  308.18  5572.4  306.22    5598  303.51
  5846.5  306.76  6231.6  305.25    6829  308.68  7071.2  307.21  7792.3  312.87
#Mann= 12 ,-1 , 0
  2859.3     .05       0  3386.8     .07       0  3488.2     .05       0
  3671.7     .07       0  3679.5     .05       0  3846.8     .07       0
  4043.5     .05       0  4503.6     .07       0  4933.9      .1       0
  4958.4     .05       0  5020.4      .1       0  5155.4     .07       0
Bank Sta=4958.4,5020.4
XS Rating Curve= 0 ,0
Exp/Cntr=0.3,0.1

Type RM Length L Ch R = 1 ,25959   ,956,956,956
BEGIN DESCRIPTION:
X18486
END DESCRIPTION:
XS GIS Cut Line= 3
       2378406.4     13663014.81      2377747.06     13661138.24
      2376530.09     13658619.79
#Sta/Elev= 30
  3336.1   335.4  3503.2  333.53  3719.3  327.46    3769  326.04  4003.7  313.12
  4119.6   309.3  4437.9  297.13  4544.2  296.31  4623.1  302.86  4710.7  300.43
  4798.4  301.62  4904.6  297.52  4915.2  295.92  4922.3  287.28  4923.8  286.28
  4984.3  287.28  4989.6  293.73    5000  295.16  5040.9  295.44  5108.2   302.9
  5150.3  304.11  5255.7   305.1  5531.1  306.24  5673.7  307.44    6055  305.32
  6183.9  301.94  6550.4  306.68  6961.4  304.77  8040.2  310.54  8122.2  312.16
#Mann= 12 ,-1 , 0
  3336.1     .05       0  3719.3     .07       0    3769     .05       0
  4119.6     .07       0  4437.9      .1       0  4922.3     .05       0
  4984.3      .1       0  5150.3     .05       0  5255.7     .07       0
  5531.1     .05       0  5673.7     .07       0  8040.2     .05       0
Bank Sta=4922.3,4984.3
XS Rating Curve= 0 ,0
Exp/Cntr=0.3,0.1

Type RM Length L Ch R = 1 ,25003   ,840,840,840
BEGIN DESCRIPTION:
X18485
END DESCRIPTION:
XS GIS Cut Line= 3
      2379234.79     13662068.05      2378372.59      13661019.9
      2376749.59     13658467.04
#Sta/Elev= 30
  4145.6  323.27  4339.7  327.23  4424.3  326.86  4713.1  319.12  4822.9  314.01
  4907.9  307.47  4950.9  296.47  4965.3  294.24  4975.9  287.08  4977.4  286.08
  5037.9  287.08    5043  293.29  5049.9  295.03  5099.7  296.37  5105.1  296.07
  5239.9  297.67  5276.7  296.53  5532.3  303.45  5662.7  301.48  6066.2  302.69
  6199.6  302.34  6308.8  299.25  6366.4  299.36  6373.6  301.11    6512  303.16
  6778.8     303  7003.2   305.6  7430.8  305.93  8168.2  309.63  8527.9  311.23
#Mann= 9 ,-1 , 0
  4145.6     .07       0  4713.1     .12       0  4975.9     .05       0
  5037.9     .12       0  5099.7     .12       0  5105.1      .1       0
  5239.9     .05       0  6066.2     .07       0  8168.2     .05       0
Bank Sta=4975.9,5037.9
XS Rating Curve= 0 ,0
Exp/Cntr=0.3,0.1

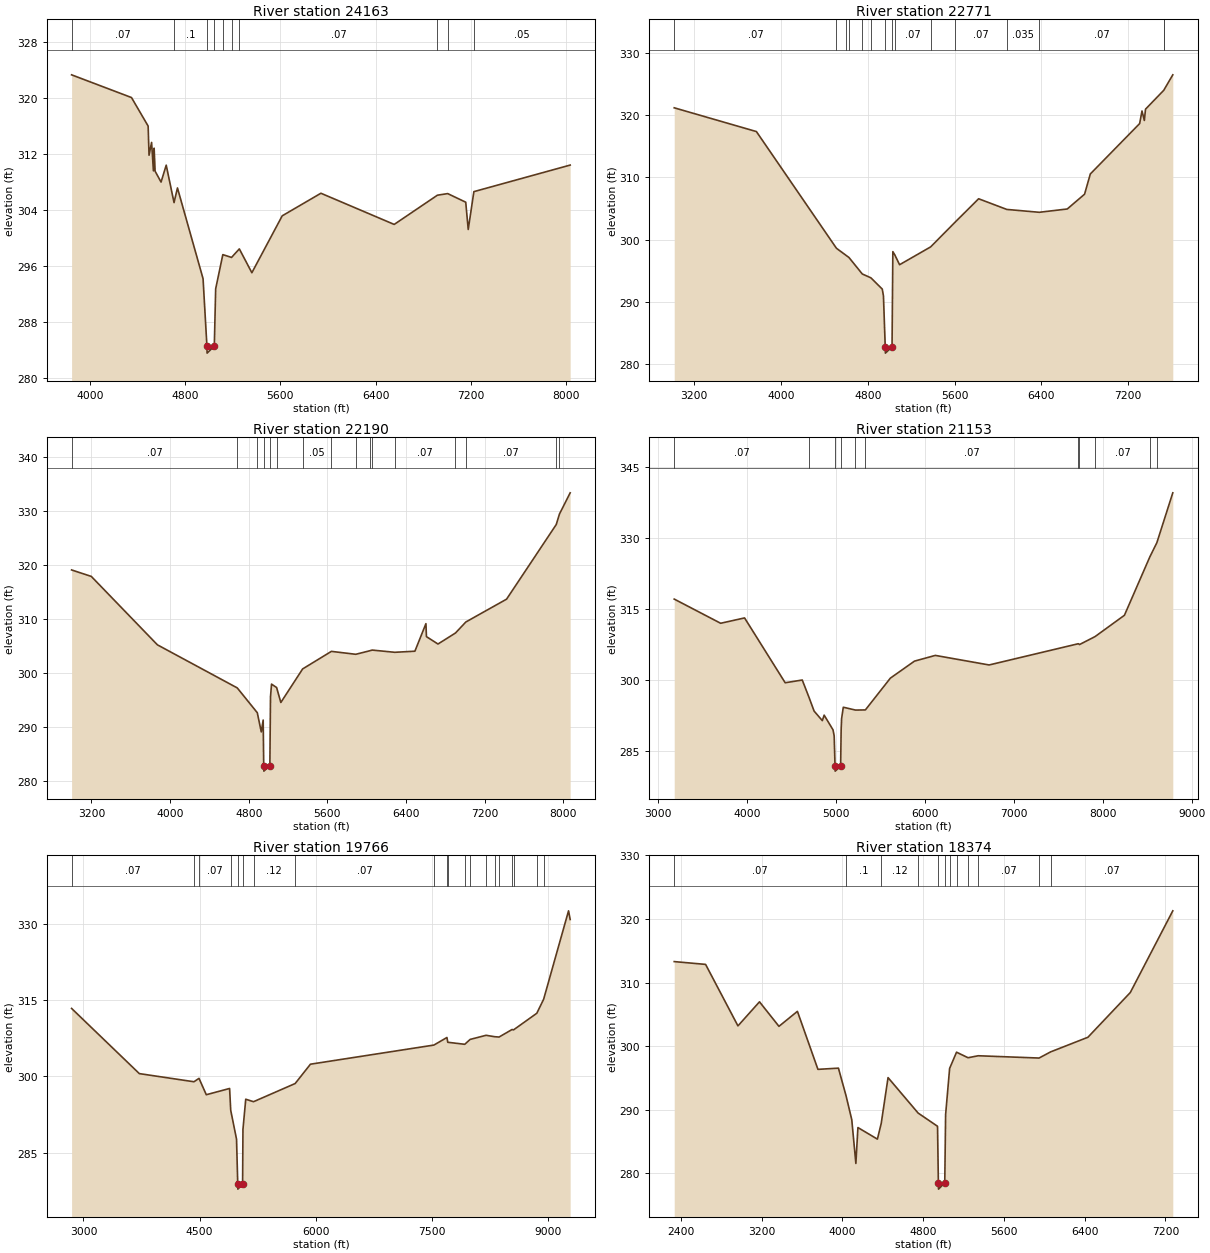
Type RM Length L Ch R = 1 ,24163   ,1392,1392,1392
BEGIN DESCRIPTION:
X18484
END DESCRIPTION:
XS GIS Cut Line= 3
      2379657.46     13661645.41      2379167.19     13660833.93
      2376935.53     13658483.92
#Sta/Elev= 30
  3845.6  323.32  4348.9  320.07  4488.7  315.99  4496.3  311.82  4517.7  313.65
  4533.2  309.58  4539.1  312.83  4547.1  309.54  4597.3  307.98  4640.6   310.4
  4706.3  305.04  4735.1  307.14  4950.1  294.16  4982.6  284.51  4984.1  283.51
  5044.6  284.51  5056.1  292.71  5116.2   297.6  5189.5   297.2  5254.9  298.42
  5360.2  295.01  5615.1  303.15  5940.3  306.38  6555.9  301.92    6919   306.1
  7005.4  306.33    7157   305.1    7178   301.2  7225.5  306.61  8034.5  310.41
#Mann= 10 ,-1 , 0
  3845.6     .07       0  4706.3      .1       0  4982.6     .05       0
  5044.6      .1       0  5116.2     .07       0  5189.5     .05       0
  5254.9     .07       0    6919     .05       0  7005.4     .07       0
  7225.5     .05       0
Bank Sta=4982.6,5044.6
XS Rating Curve= 0 ,0
Exp/Cntr=0.3,0.1

Type RM Length L Ch R = 1 ,22771   ,581,581,581
BEGIN DESCRIPTION:
X18483
END DESCRIPTION:
XS GIS Cut Line= 3
      2380012.51     13661544.01      2379606.75     13660005.52
      2378457.13      13657232.9
#Sta/Elev= 30
    3017  321.16    3774  317.35  4511.3  298.63  4603.9  297.44  4626.6  297.15
  4749.7   294.5  4828.6  293.89  4933.4  292.08  4944.3  290.99  4960.8  282.81
  4962.3  281.81  5023.4  282.81  5030.9  298.09  5048.5  297.58    5093  295.99
  5379.1  298.85    5604  302.81  5821.1  306.57  6080.3  304.86  6379.4   304.4
  6637.3  304.93  6796.8   307.3    6850  310.55  7304.2  318.63  7325.9  320.65
  7347.5  319.13  7358.3  320.94  7527.5  323.99  7532.9  324.17  7609.6  326.45
#Mann= 15 ,-1 , 0
    3017     .07       0  4511.3      .1       0  4603.9     .07       0
  4626.6      .1       0  4749.7     .12       0  4828.6      .1       0
  4960.8     .05       0  5023.4      .1       0  5048.5     .07       0
  5379.1     .05       0    5604     .07       0  6080.3    .035       0
  6379.4     .07       0  7527.5    .035       0  7532.9     .07       0
Bank Sta=4960.8,5023.4
XS Rating Curve= 0 ,0
Exp/Cntr=0.3,0.1

Type RM Length L Ch R = 1 ,22190   ,1037,1037,1037
BEGIN DESCRIPTION:
X18482
END DESCRIPTION:
XS GIS Cut Line= 3
      2380198.47     13661374.93      2380046.32     13659650.49
       2378913.6     13656505.92
#Sta/Elev= 30
  2997.9  319.07  3198.6  317.87  3871.2  305.21  4683.6  297.24  4887.5  292.65
  4928.1   289.1  4947.5  291.29  4952.9  282.84  4954.4  281.84  5015.5  282.84
  5021.9  295.57  5032.5  297.94  5084.2  297.31  5127.1  294.54  5348.9  300.75
  5641.5     304  5889.4  303.46  6031.3  304.11  6056.5  304.24  6286.8  303.83
  6491.3  304.03  6603.5  309.13  6608.8  306.73  6726.2  305.36  6904.2   307.4
    7010  309.44    7424  313.66  7929.7  327.47  7962.2  329.41  8071.4  333.34
#Mann= 16 ,-1 , 0
  2997.9     .07       0  4683.6     .12       0  4887.5      .1       0
  4952.9     .05       0  5015.5      .1       0  5084.2     .07       0
  5348.9     .05       0  5641.5     .07       0  5889.4     .05       0
  6031.3     .07       0  6056.5    .035       0  6286.8     .07       0
  6904.2    .035       0    7010     .07       0  7929.7    .035       0
  7962.2     .07       0
Bank Sta=4952.9,5015.5
XS Rating Curve= 0 ,0
Exp/Cntr=0.3,0.1

Type RM Length L Ch R = 1 ,21153   ,1387,1387,1387
BEGIN DESCRIPTION:
CLEAR FORK SANDIES CREEK 13.0
END DESCRIPTION:
XS GIS Cut Line= 3
      2380384.44     13661408.75      2380840.91     13659396.89
      2379116.45     13656303.01
#Sta/Elev= 30
  3182.3  317.01  3704.3   311.9  3973.2  313.03  4429.8  299.33  4621.7  299.91
  4698.7  296.19    4755  293.34  4847.3  291.33  4867.8  292.49  4967.6  289.38
  4980.6   288.1  4990.3  281.66  4991.8  280.66    5053  281.66    5059  289.48
  5064.1  291.76  5083.2  294.16  5220.2  293.56  5331.3  293.59  5612.5  300.31
  5883.4   303.9  6117.5  305.11  6722.3  303.09  7725.6  307.58  7738.3   307.4
    7913  309.08  8243.6  313.59  8528.8  325.91  8608.1  328.92  8787.3  339.46
#Mann= 11 ,-1 , 0
  3182.3     .07       0  4698.7      .1       0  4990.3     .05       0
    5053      .1       0  5220.2     .12       0  5331.3     .07       0
  7725.6    .035       0  7738.3     .05       0    7913     .07       0
  8528.8    .035       0  8608.1     .07       0
Bank Sta=4990.3,5053
XS Rating Curve= 0 ,0
Exp/Cntr=0.3,0.1

Type RM Length L Ch R = 1 ,19766   ,1392,1392,1392
BEGIN DESCRIPTION:
CLEAR FORK SANDIES CREEK 12.0
END DESCRIPTION:
XS GIS Cut Line= 3
      2381229.75     13661966.67        2381725.       13659875.
      2379319.68     13656320.45
#Sta/Elev= 30
  2846.3  313.34  3721.5  300.53  4427.2  298.93  4492.3   299.6  4586.7  296.38
  4887.6  297.61  4902.1  293.33  4977.2  287.65  4992.9  278.83  4994.4  277.83
  5055.6  278.83  5060.2  289.56  5096.2   295.5  5196.7  295.01  5734.6  298.58
  5932.1  302.38  7527.3  306.14  7695.6  307.63  7706.4  306.69  7925.4  306.29
  7995.5  307.25  8200.8  308.06  8312.9  307.78  8369.1  307.72  8537.5   309.2
  8555.6  309.12  8856.6  312.39  8944.8  315.14  9266.7  332.52  9287.7  330.82
#Mann= 20 ,-1 , 0
  2846.3     .07       0  4427.2    .035       0  4492.3     .07       0
  4902.1      .1       0  4992.9     .05       0  5055.6      .1       0
  5196.7     .12       0  5734.6     .07       0  7527.3     .05       0
  7695.6    .035       0  7706.4     .05       0  7925.4    .035       0
  7995.5     .05       0  8200.8    .035       0  8312.9     .05       0
  8369.1    .035       0  8537.5     .05       0  8555.6    .035       0
  8856.6     .07       0  8944.8    .035       0
Bank Sta=4992.9,5055.6
XS Rating Curve= 0 ,0
Exp/Cntr=0.3,0.1

Type RM Length L Ch R = 1 ,18374   ,1876,1876,1876
BEGIN DESCRIPTION:
CLEAR FORK SANDIES CREEK 11.0
END DESCRIPTION:
XS GIS Cut Line= 3
      2383004.91     13661966.64      2382582.26     13659616.68
      2382616.07     13657063.87
#Sta/Elev= 30
  2332.5   313.3  2643.4  312.86  2964.1  303.18  3177.5  306.97  3370.5  303.11
  3553.4  305.47  3756.6  296.34  3959.8  296.53  4034.9  292.21  4091.9  288.43
  4132.6  281.53  4152.9  287.18  4345.9  285.36  4383.8  287.83  4451.5  295.04
  4749.7  289.46  4941.9  287.38  4950.2  278.49  4951.7  277.49  5013.5  278.49
  5021.9  289.21  5061.7  296.49  5130.1  299.04  5244.1  298.17  5345.2  298.48
  5947.9  298.12  6062.6  299.09    6432  301.39    6852  308.43  7273.2  321.29
#Mann= 12 ,-1 , 0
  2332.5     .07       0  4034.9      .1       0  4383.8     .12       0
  4749.7      .1       0  4950.2     .05       0  5013.5      .1       0
  5061.7     .12       0  5130.1     .07       0  5244.1     .12       0
  5345.2     .07       0  5947.9     .12       0  6062.6     .07       0
Bank Sta=4950.2,5013.5
XS Rating Curve= 0 ,0
Exp/Cntr=0.3,0.1

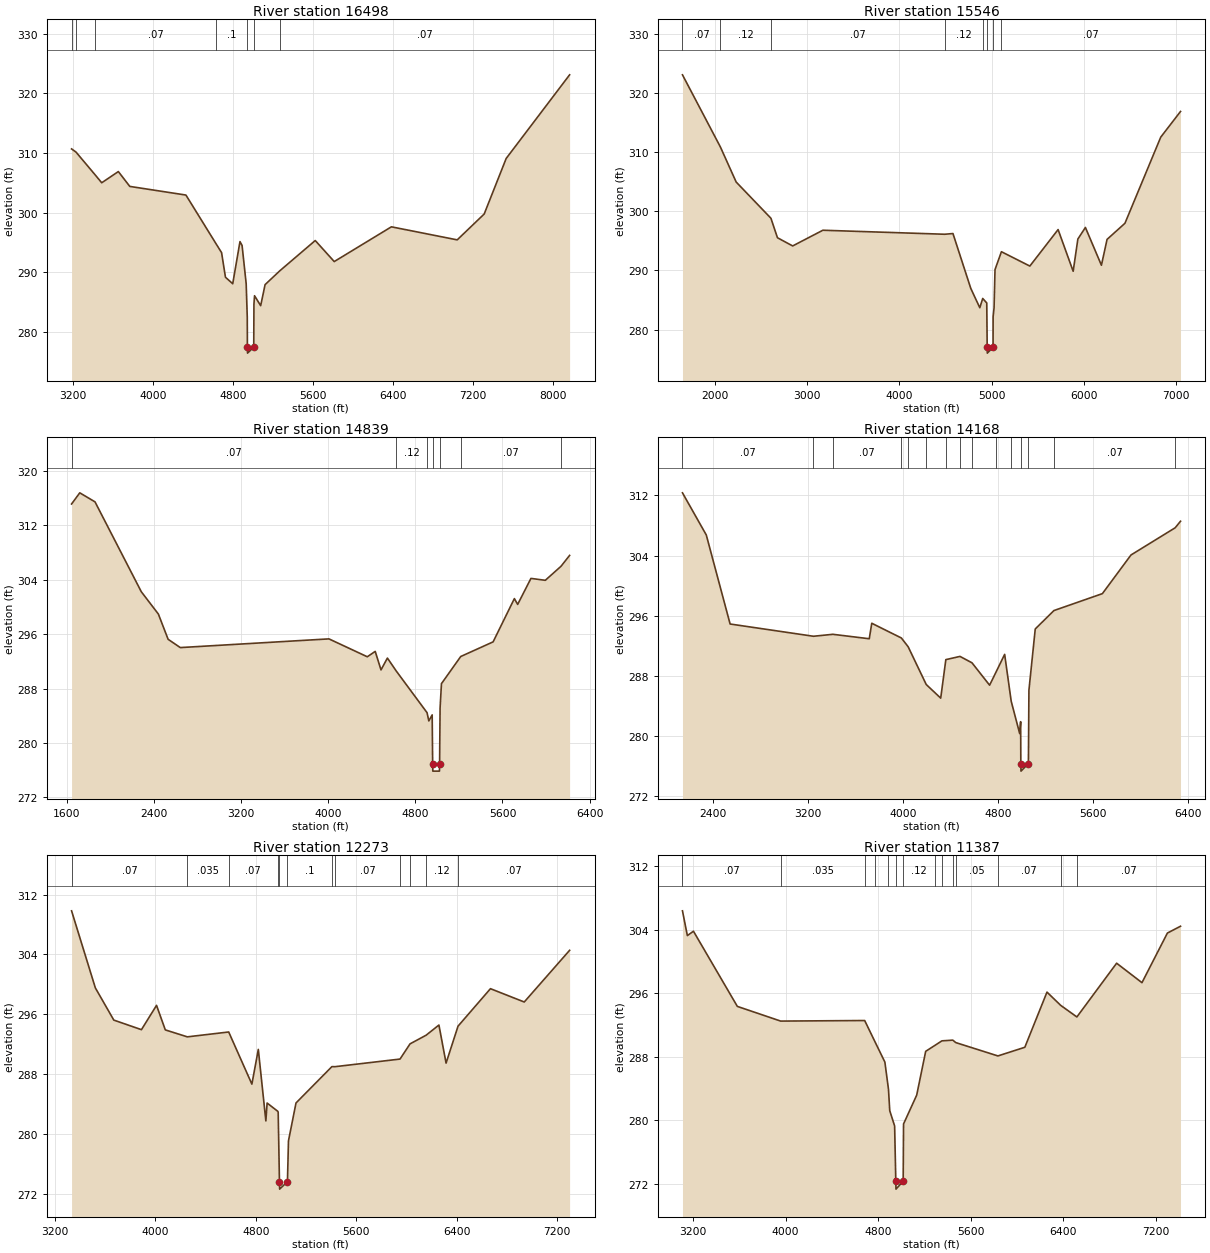
Type RM Length L Ch R = 1 ,16498   ,952,952,952
BEGIN DESCRIPTION:
CLEAR FORK SANDIES CREEK 10.0
END DESCRIPTION:
XS GIS Cut Line= 3
        2384075.       13661975.      2383444.48     13659785.74
      2383343.04     13657080.69
#Sta/Elev= 30
  3182.4  310.69  3226.2  310.17    3413  306.45  3484.2  305.01  3650.7  306.89
  3765.2   304.4  4327.1  302.95    4630  294.74    4684  293.29  4722.9  289.16
  4795.5  288.07  4868.2  295.14  4889.1   294.5  4930.2  288.08  4941.1  282.45
  4942.4  277.43  4943.9  276.43    5006  277.43  5007.9  284.66  5013.9  286.06
  5075.3  284.39  5119.4  287.92  5267.5  290.25  5621.5  295.32  5811.6  291.79
  6383.9  297.62  7042.5  295.43  7312.7  299.77  7532.8  309.09  8167.6  323.12
#Mann= 7 ,-1 , 0
  3182.4     .07       0  3226.2     .12       0    3413     .07       0
    4630      .1       0  4942.4     .05       0    5006      .1       0
  5267.5     .07       0
Bank Sta=4942.4,5006
XS Rating Curve= 0 ,0
Exp/Cntr=0.3,0.1

Type RM Length L Ch R = 1 ,15546   ,707,707,707
BEGIN DESCRIPTION:
CLEAR FORK SANDIES CREEK 9.0
END DESCRIPTION:
XS GIS Cut Line= 3
      2385375.01     13662375.02        2383875.       13659375.
      2383475.01     13657375.03
#Sta/Elev= 30
  1652.2  323.15  2063.1  310.92  2233.6  304.99  2610.2  298.85  2680.8  295.55
  2845.7  294.16  3172.7  296.82  4492.8  296.14  4581.5  296.26  4774.3  286.98
  4872.2  283.69  4903.8  285.26  4947.6   284.5  4952.2     277  4953.7     276
  5015.8     277  5016.5  282.19  5026.7  283.68  5036.9  290.15  5106.4  293.18
  5414.2  290.75  5720.2  296.93  5883.4  289.87  5934.3  295.33  6015.9  297.29
  6189.3  290.89  6250.5  295.27  6444.2     298  6831.8  312.59  7045.9  316.94
#Mann= 8 ,-1 , 0
  1652.2     .07       0  2063.1     .12       0  2610.2     .07       0
  4492.8     .12       0  4903.8      .1       0  4952.2     .05       0
  5015.8      .1       0  5106.4     .07       0
Bank Sta=4952.2,5015.8
XS Rating Curve= 0 ,0
Exp/Cntr=0.3,0.1

Type RM Length L Ch R = 1 ,14839   ,671,671,671
BEGIN DESCRIPTION:
CLEAR FORK SANDIES CREEK 8.0
END DESCRIPTION:
XS GIS Cut Line= 3
      2385874.99     13661924.98        2384375.       13658925.
        2384175.     13657725.03
#Sta/Elev= 30
  1645.6  315.13    1721  316.77  1860.8  315.44  2285.6  302.23  2442.2  298.95
  2531.6  295.24  2643.4  294.02  4007.4   295.3  4359.6  292.67  4432.3  293.46
  4485.4  290.74  4544.1  292.48  4626.1  290.56    4908  284.45  4924.2  283.24
    4955  284.13  4959.4  276.86  4960.9  275.86  5021.6  275.86  5023.1  276.86
  5027.6  285.14  5040.2  288.72  5217.2  292.71  5514.2  294.86  5709.3  301.22
  5739.7  300.37  5861.4  304.19  5993.2  303.91  6137.3  305.97  6216.2  307.57
#Mann= 7 ,-1 , 0
  1645.6     .07       0  4626.1     .12       0    4908      .1       0
  4959.4     .05       0  5023.1      .1       0  5217.2     .07       0
  6137.3     .12       0
Bank Sta=4959.4,5023.1
XS Rating Curve= 0 ,0
Exp/Cntr=0.3,0.1

Type RM Length L Ch R = 1 ,14168   ,1895,1895,1895
BEGIN DESCRIPTION:
CLEAR FORK SANDIES CREEK 7.0
END DESCRIPTION:
XS GIS Cut Line= 3
        2385875.     13661475.01        2384975.       13658775.
        2384375.       13657575.
#Sta/Elev= 30
  2146.6  312.34  2346.9  306.73  2547.2  294.89  3248.2  293.26  3410.6  293.52
  3717.2  292.93  3738.3  294.99  3987.1  293.03    4044  291.87  4196.3  286.84
    4318  285.03  4361.1  290.15  4480.1  290.58  4580.9  289.73  4729.1  286.75
  4778.9  288.36  4855.6  290.85  4910.7  284.62  4982.1  280.31    4990   281.9
  4991.6  276.32  4993.1  275.32  5055.3  276.32  5059.7  286.08  5112.9  294.23
    5270  296.68  5677.5  298.93  5917.8  304.07  6289.4  307.69  6334.3  308.56
#Mann= 15 ,-1 , 0
  2146.6     .07       0  3248.2    .035       0  3410.6     .07       0
  3987.1      .1       0    4044     .07       0  4196.3     .12       0
  4361.1     .07       0  4480.1     .12       0  4580.9     .07       0
  4778.9     .12       0  4910.7      .1       0  4991.6     .05       0
  5055.3      .1       0    5270     .07       0  6289.4     .12       0
Bank Sta=4991.6,5055.3
XS Rating Curve= 0 ,0
Exp/Cntr=0.3,0.1

Type RM Length L Ch R = 1 ,12273   ,886,886,886
BEGIN DESCRIPTION:
X18481
END DESCRIPTION:
XS GIS Cut Line= 3
      2385878.98     13661341.08      2385760.64      13658872.8
      2384644.81     13657875.31
#Sta/Elev= 30
  3332.4  309.82  3521.8  299.52  3668.9  295.21  3889.1  293.93  4009.3  297.18
  4079.3   293.9  4254.7  292.97  4584.3  293.62    4769  286.65  4820.2  291.29
  4880.3  281.73  4890.3  284.12  4974.9  283.02  4978.5   282.9  4988.6  273.61
  4990.1  272.61  5052.3  273.61  5060.5  279.07  5120.5  284.13  5406.5  288.99
  5430.9  288.98  5949.2     290  6028.9  292.03  6157.1  293.19  6259.1  294.55
    6316  289.46  6411.4   294.4  6669.6  299.41  6938.8  297.63  7300.2  304.54
#Mann= 12 ,-1 , 0
  3332.4     .07       0  4254.7    .035       0  4584.3     .07       0
  4974.9      .1       0  4988.6     .05       0  5052.3      .1       0
  5406.5     .05       0  5430.9     .07       0  5949.2      .1       0
  6028.9     .07       0  6157.1     .12       0  6411.4     .07       0
Bank Sta=4988.6,5052.3
XS Rating Curve= 0 ,0
Exp/Cntr=0.3,0.1

Type RM Length L Ch R = 1 ,11387   ,1380,1380,1380
BEGIN DESCRIPTION:
CLEAR FORK SANDIES CREEK 6.0
END DESCRIPTION:
XS GIS Cut Line= 3
        2385925.       13661275.        2386525.       13659475.
      2384724.99     13657874.99
#Sta/Elev= 30
  3109.3  306.41  3151.5  303.29  3204.2  303.84  3583.6  294.37  3958.2  292.52
  4684.6  292.59  4770.7     290  4859.1  287.36  4890.3  283.93  4901.3  281.23
  4943.4  279.31  4953.7  272.35  4955.2  271.35  5017.4  272.35  5020.5  279.56
  5134.2  283.19    5212  288.71    5293  289.47  5352.3  290.03  5446.3  290.12
  5472.2  289.81  5836.4  288.13  6069.1  289.22  6260.6  296.17  6379.2   294.5
  6519.1  293.04  6862.7  299.81  7081.8  297.36  7301.7  303.61    7415  304.47
#Mann= 14 ,-1 , 0
  3109.3     .07       0  3958.2    .035       0  4684.6     .12       0
  4770.7     .07       0  4890.3     .12       0  4953.7     .05       0
  5017.4     .12       0    5293     .07       0  5352.3     .05       0
  5446.3     .07       0  5472.2     .05       0  5836.4     .07       0
  6379.2     .12       0  6519.1     .07       0
Bank Sta=4953.7,5017.4
XS Rating Curve= 0 ,0
Exp/Cntr=0.3,0.1