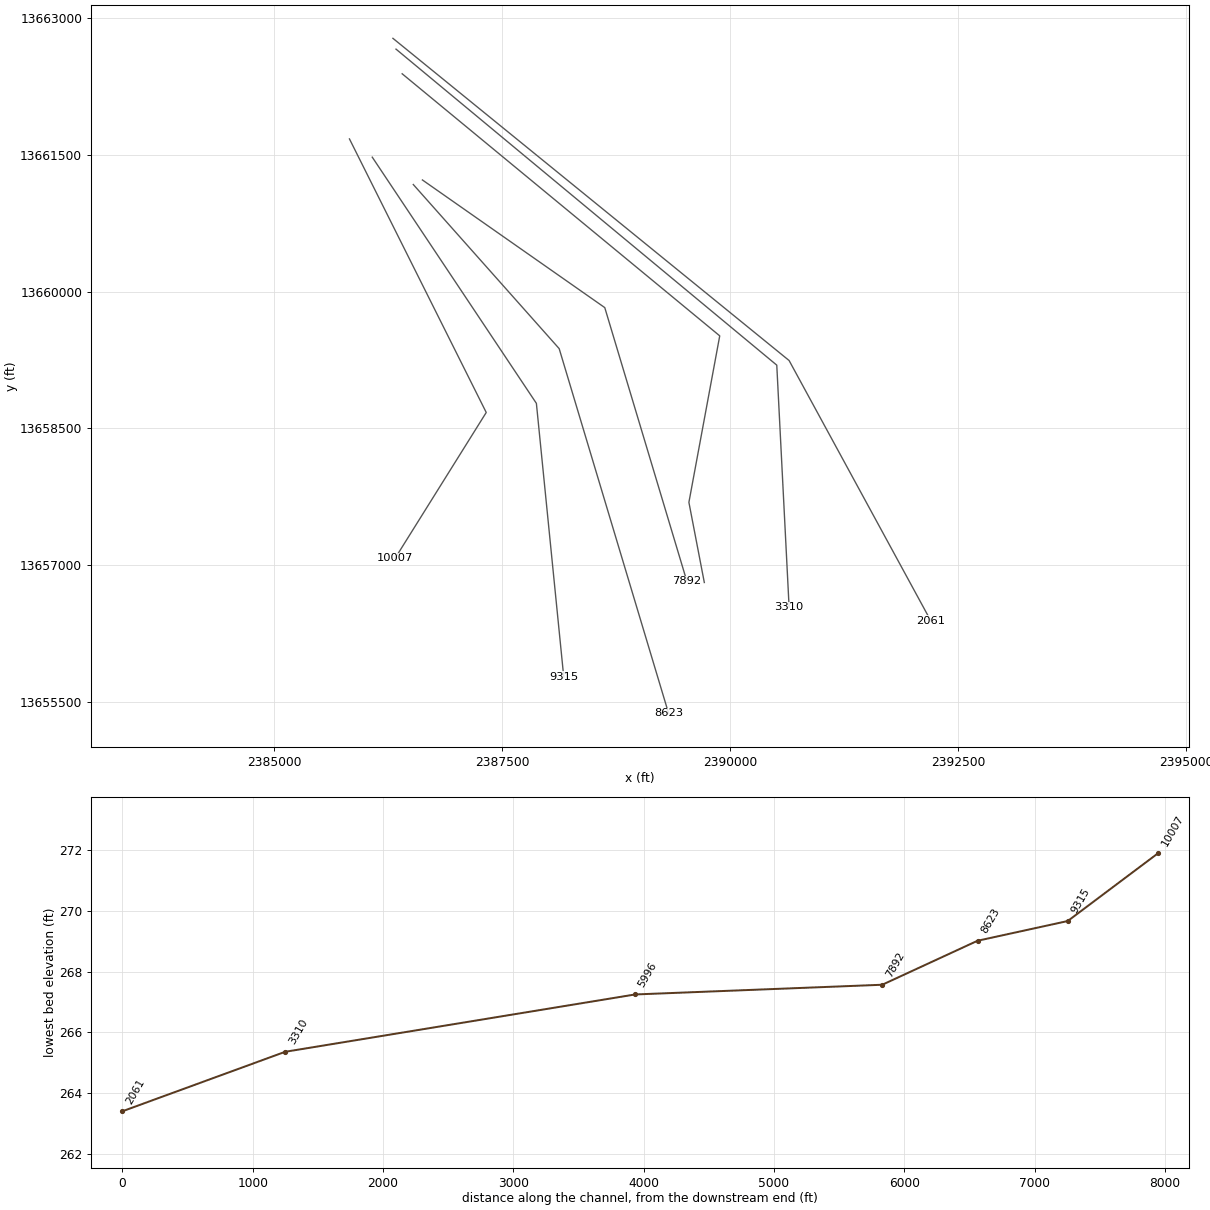
HEC-RAS study CLEAR FORK SANDIES CREEK.prj: CLEAR FORK SANDIES CREEK Base Level Engineering

--- CLEAR FORK SANDIES CREEK.g01 (geometry) --- (continued)

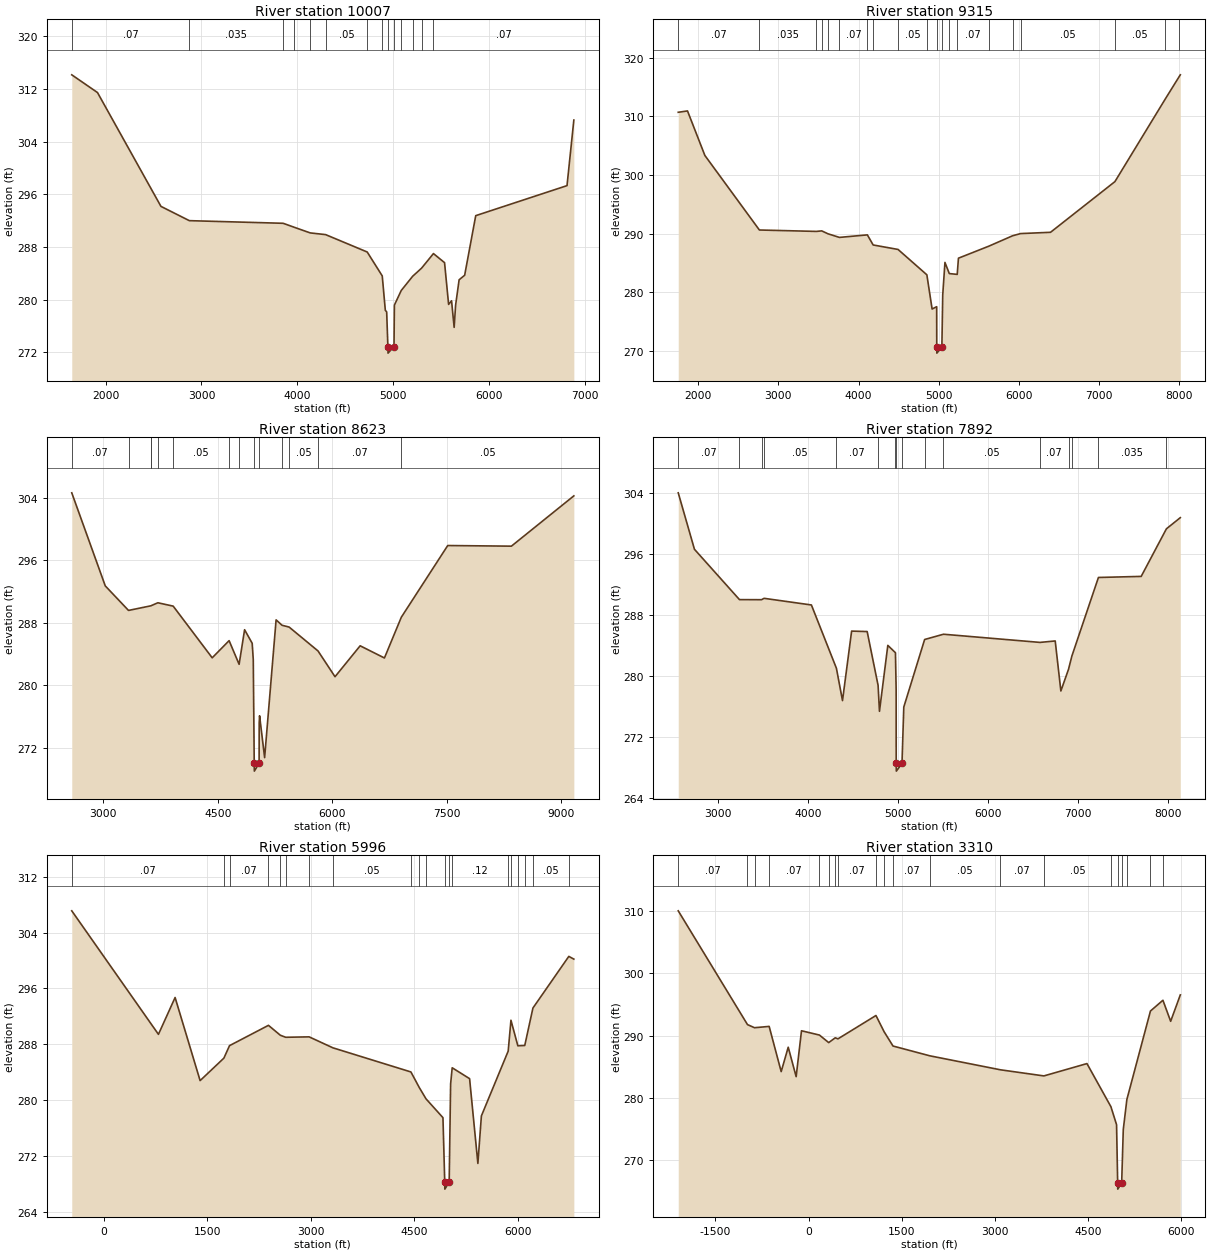
Type RM Length L Ch R = 1 ,10007   ,692,692,692
BEGIN DESCRIPTION:
CLEAR FORK SANDIES CREEK 5.0
END DESCRIPTION:
XS GIS Cut Line= 3
      2385824.99     13661675.03        2387325.       13658675.
      2386325.02     13657075.03
#Sta/Elev= 30
  1645.9  314.17  1914.3  311.48  2576.7  294.19  2873.1  292.02  3852.6  291.62
  3963.3  291.04    4135  290.16  4295.6   289.9  4729.8  287.26  4886.8  283.63
    4919   278.4    4933  278.17  4945.7   272.9  4947.2   271.9  5009.6   272.9
  5013.6  279.19    5085  281.41    5204  283.57    5297   284.8  5421.3  287.02
  5537.2  285.64  5579.6   279.3  5610.3  279.85  5637.4  275.81  5652.7   279.2
  5689.3  283.04  5747.1  283.73  5862.7  292.78  6815.5  297.34  6886.8   307.3
#Mann= 14 ,-1 , 0
  1645.9     .07       0  2873.1    .035       0  3852.6     .07       0
  3963.3     .05       0    4135     .07       0  4295.6     .05       0
  4729.8     .07       0  4886.8      .1       0  4945.7     .05       0
  5009.6      .1       0    5085     .12       0    5204     .07       0
    5297     .12       0  5421.3     .07       0
Bank Sta=4945.7,5009.6
XS Rating Curve= 0 ,0
Exp/Cntr=0.3,0.1

Type RM Length L Ch R = 1 ,9315    ,692,692,692
BEGIN DESCRIPTION:
CLEAR FORK SANDIES CREEK 4.0
END DESCRIPTION:
XS GIS Cut Line= 3
      2386075.02     13661474.97        2387875.       13658775.
        2388175.     13655775.02
#Sta/Elev= 30
  1751.4  310.69    1867  310.92  2083.4  303.34  2763.2  290.64  3474.7   290.4
  3540.5  290.49  3619.5  289.99  3761.2  289.38  4109.6  289.81  4181.8  288.09
  4491.9  287.33  4851.3  283.01  4916.7  277.18  4973.8  277.58  4974.5  270.67
    4976  269.67  5038.4  270.67  5049.1  279.57  5076.8  285.12    5131  283.22
  5229.7  283.08  5245.1  285.84  5624.5  287.89  5920.6  289.66  6019.3  290.03
  6393.3  290.25    7196  298.88  7825.5  312.99    8001  316.85  8011.3  317.07
#Mann= 20 ,-1 , 0
  1751.4     .07       0  2763.2    .035       0  3474.7     .05       0
  3540.5    .035       0  3619.5     .05       0  3761.2     .07       0
  4109.6     .05       0  4181.8     .07       0  4491.9     .05       0
  4851.3      .1       0  4974.5     .05       0  5038.4      .1       0
    5131     .12       0  5229.7     .07       0  5624.5     .12       0
  5920.6     .07       0  6019.3     .05       0    7196     .05       0
  7825.5    .035       0    8001     .05       0
Bank Sta=4974.5,5038.4
XS Rating Curve= 0 ,0
Exp/Cntr=0.3,0.1

Type RM Length L Ch R = 1 ,8623    ,731,731,731
BEGIN DESCRIPTION:
CLEAR FORK SANDIES CREEK 3.0
END DESCRIPTION:
XS GIS Cut Line= 3
      2386525.02     13661174.97        2388125.       13659375.
        2389325.     13655375.01
#Sta/Elev= 30
    2585  304.66  3024.4  292.74  3329.2   289.6  3627.2   290.2  3629.2  290.22
  3714.3  290.58  3915.1  290.15  4426.7  283.53  4648.4  285.73  4779.6   282.7
  4851.5  287.13  4951.1  285.39  4965.3   283.3  4977.9  270.02  4979.4  269.02
  5041.8  270.02  5042.9  275.17  5048.1  276.11  5114.2  270.75  5264.7  288.39
  5342.5   287.7  5435.2  287.47  5814.4  284.41  6037.3  281.11  6367.1  285.07
  6685.5  283.51  6906.9  288.73  7515.5  297.91  8350.7  297.83  9169.4  304.27
#Mann= 14 ,-1 , 0
    2585     .07       0  3329.2    .035       0  3627.2     .07       0
  3629.2     .05       0  3714.3     .07       0  3915.1     .05       0
  4648.4     .07       0  4779.6      .1       0  4977.9     .05       0
  5041.8      .1       0  5342.5     .07       0  5435.2     .05       0
  5814.4     .07       0  6906.9     .05       0
Bank Sta=4977.9,5041.8
XS Rating Curve= 0 ,0
Exp/Cntr=0.3,0.1

Type RM Length L Ch R = 1 ,7892    ,1896,1896,1896
BEGIN DESCRIPTION:
CLEAR FORK SANDIES CREEK 2.0
END DESCRIPTION:
XS GIS Cut Line= 3
      2386625.02     13661224.98        2388625.       13659825.
      2389525.01     13656824.98
#Sta/Elev= 30
  2559.6     304  2739.6  296.61  3239.5  290.02  3484.2  290.01    3513  290.19
  4037.9  289.32  4315.7  281.03  4383.1   276.8  4484.3   285.9  4656.9  285.84
  4778.1   278.8  4793.4   275.4  4886.2  284.03  4970.8  283.07  4978.6  278.26
  4979.2  268.57  4980.7  267.57  5043.4  268.57  5063.5  275.96  5294.8   284.8
  5503.9  285.49  6575.3  284.42  6744.4  284.61  6807.1  278.06  6892.3  280.91
  6929.2  282.63  7224.1  292.92  7698.8  293.06  7978.8  299.29    8133  300.75
#Mann= 16 ,-1 , 0
  2559.6     .07       0  3239.5    .035       0  3484.2     .07       0
    3513     .05       0  4315.7     .07       0  4778.1     .12       0
  4970.8      .1       0  4979.2     .05       0  5043.4      .1       0
  5294.8     .07       0  5503.9     .05       0  6575.3     .07       0
  6892.3     .12       0  6929.2     .07       0  7224.1    .035       0
  7978.8     .05       0
Bank Sta=4979.2,5043.4
XS Rating Curve= 0 ,0
Exp/Cntr=0.3,0.1

Type RM Length L Ch R = 1 ,5996    ,2686,2686,2686
BEGIN DESCRIPTION:
X18480
END DESCRIPTION:
XS GIS Cut Line= 4
      2386403.08     13662389.31      2389885.78     13659515.24
      2389547.65     13657689.36      2389716.71     13656810.25
#Sta/Elev= 30
  -460.3  307.13   794.4  289.43  1035.4  294.71  1397.6   282.8  1741.6  286.02
  1823.2  287.81  2386.6  290.72  2559.1   289.3  2636.2  289.01  2975.7  289.07
  3319.3   287.5  4449.1  284.04  4569.8  281.81  4667.3  280.19  4912.7  277.49
  4938.6  268.25  4940.1  267.25  5002.8  268.25  5023.6  282.33  5046.5  284.64
  5298.2  283.08  5418.2  270.93    5469  277.74    5857  287.03  5896.9  291.45
  5996.8  287.79  6096.6  287.83  6215.1   293.2  6734.5   300.6  6807.3  300.21
#Mann= 20 ,-1 , 0
  -460.3     .07       0  1741.6     .05       0  1823.2     .07       0
  2386.6     .05       0  2559.1     .07       0  2636.2     .05       0
  2975.7     .07       0  3319.3     .05       0  4449.1     .07       0
  4569.8     .05       0  4667.3      .1       0  4938.6     .05       0
  5002.8      .1       0  5046.5     .12       0    5857    .035       0
  5896.9     .07       0  5996.8      .1       0  6096.6     .07       0
  6215.1     .05       0  6734.5     .05       0
Bank Sta=4938.6,5002.8
XS Rating Curve= 0 ,0
Exp/Cntr=0.3,0.1

Type RM Length L Ch R = 1 ,3310    ,1249,1249,1249
BEGIN DESCRIPTION:
X18479
END DESCRIPTION:
XS GIS Cut Line= 3
      2386335.49     13662659.78      2390511.31     13659194.02
      2390646.55     13656539.85
#Sta/Elev= 30
 -2097.9  310.05  -982.8  291.78  -869.6  291.28    -634  291.49  -440.1  284.23
  -326.8  288.15  -199.2  283.42  -113.2  290.79   175.9   290.1   324.9  288.89
   430.6  289.66   473.9  289.49  1085.8  293.24  1216.8  290.64  1360.3  288.34
    1952  286.77    3091  284.52  3789.7  283.54  4483.2  285.52  4869.4  278.59
  4959.9  275.71  4977.8  266.36  4979.3  265.36  5042.2  266.36  5068.3  274.95
  5125.9  279.75  5505.7  293.96  5706.4  295.69    5831  292.31  5986.4  296.55
#Mann= 20 ,-1 , 0
 -2097.9     .07       0  -982.8     .12       0  -869.6     .12       0
    -634     .07       0   175.9     .07       0   324.9     .05       0
   430.6    .035       0   473.9     .07       0  1085.8     .07       0
  1216.8     .05       0  1360.3     .07       0    1952     .05       0
    3091     .07       0  3789.7     .05       0  4869.4      .1       0
  4977.8     .05       0  5042.2      .1       0  5125.9     .05       0
  5505.7     .07       0  5706.4     .05       0
Bank Sta=4977.8,5042.2
XS Rating Curve= 0 ,0
Exp/Cntr=0.3,0.1

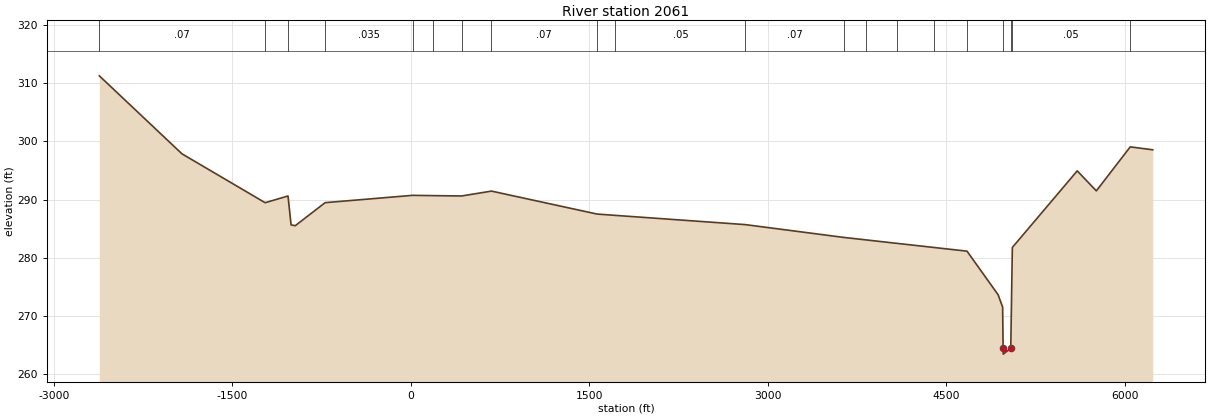
Type RM Length L Ch R = 1 ,2061    ,0,0,0
BEGIN DESCRIPTION:
CLEAR FORK SANDIES CREEK 1.0
END DESCRIPTION:
XS GIS Cut Line= 3
      2386301.62     13662778.17      2390646.56     13659244.74
      2392201.26     13656388.81
#Sta/Elev= 30
 -2616.2   311.3   -1922  297.88 -1222.8  289.46 -1030.7  290.62 -1004.8  285.64
  -969.6  285.51  -718.9  289.47    17.2  290.73   190.4  290.68   428.5  290.62
   679.1  291.46  1565.7  287.51  1720.7  287.28    2812  285.69  3642.1  283.48
  3822.4  283.07    4084  282.47  4395.7  281.76  4675.2  281.12  4936.5  273.62
  4974.4  271.49  4978.3   264.4  4979.8   263.4  5042.7   264.4  5049.1  272.75
    5056  281.76  5601.3  294.94  5761.9   291.5  6046.6  299.07  6235.8  298.57
#Mann= 20 ,-1 , 0
 -2616.2     .07       0 -1222.8     .12       0 -1030.7     .07       0
  -718.9    .035       0    17.2    .035       0   190.4    .035       0
   428.5     .07       0   679.1     .07       0  1565.7     .05       0
  1720.7     .05       0    2812     .07       0  3642.1     .05       0
  3822.4     .07       0    4084     .05       0  4395.7     .07       0
  4675.2      .1       0  4978.3     .05       0  5042.7      .1       0
  5049.1     .05       0  6046.6     .07       0
Bank Sta=4978.3,5042.7
XS Rating Curve= 0 ,0
Exp/Cntr=0.3,0.1

Chan Stop Cuts=-1
Use User Specified Reach Order=0
Composite Channel Slope=5