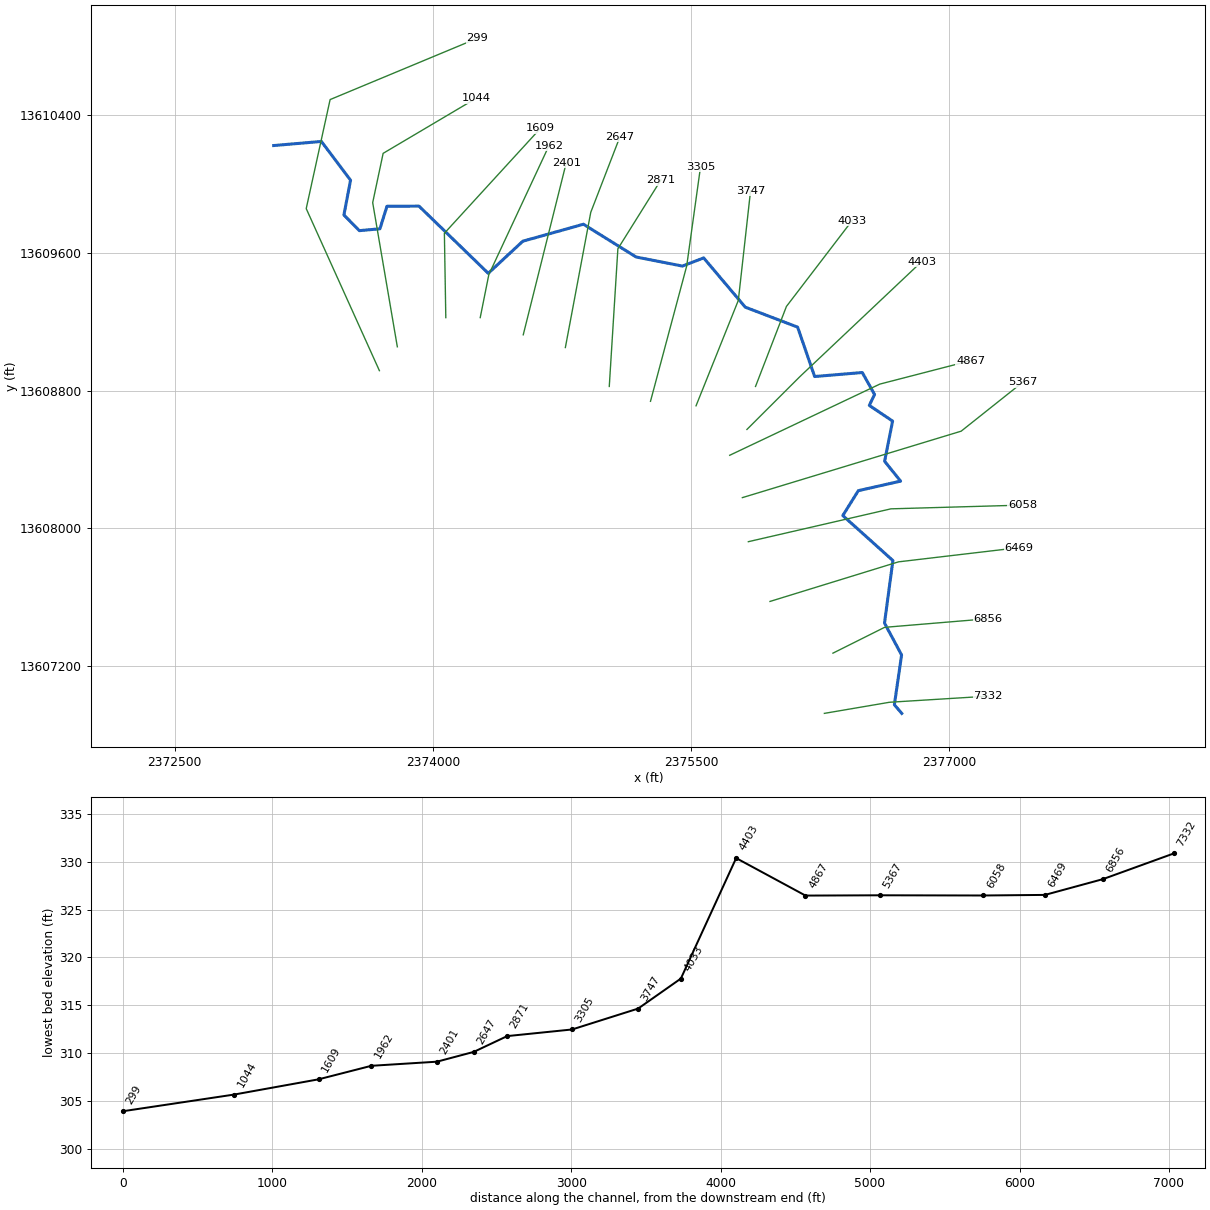
--- CORRAL CREEK.prj (project) ---

Proj Title=CORRAL CREEK Base Level Engineering
Current Plan=p01
Default Exp/Contr=0.3,0.1
English Units
Geom File=g01
Flow File=f01
Plan File=p01
Y Axis Title=Elevation
X Axis Title(PF)=Main Channel Distance
X Axis Title(XS)=Station
BEGIN DESCRIPTION:
CORRAL CREEK
END DESCRIPTION:
DSS Export Rating Curves= 0
DSS Export Rating Curve Sorted= 0
DSS Export Volume Flow Curves= 0
DXF OffsetX= 0
DXF OffsetY= 0
DXF ScaleX= 1
DXF ScaleY= 10

--- CORRAL CREEK.p01 (plan) ---

Plan Title=Multiple Run
Short Identifier=Multiple
Geom File=g01
Flow File=f01
Subcritical Flow
K Sum by GR= 0
Std Step Tol= 0.01
Critical Tol= 0.01
Num of Std Step Trials= 20
Max Error Tol= 0.3
Flow Tol Ratio= 0.001
Split Flow NTrial= 30
Split Flow Tol= 0.02
Split Flow Ratio= 0.02
Log Output Level= 0
Friction Slope Method= 1
Unsteady Friction Slope Method= 2
Unsteady Bridges Friction Slope Method= 1
Parabolic Critical Depth
Global Vel Dist=  1 , 1 , 1
Global Log Level= 0
CheckData=True
Encroach Param= -1, 0, 0, 0
BEGIN DESCRIPTION:
Multiple Run
END DESCRIPTION:

--- CORRAL CREEK.f01 (steady flow) ---

Flow Title=Multiple
Number of Profiles=7
Profile Names=10-year,25-year,50-year,1pct_min,100-year,1pct_plu,500-year
River Rch & RM= CORRAL CREEK,Reach-1,7332
     510     810    1077     693    1382    2758    2258
River Rch & RM= CORRAL CREEK,Reach-1,2871
     544     867    1155     744    1485    2964    2435
Boundary for River Rch & Prof#=CORRAL CREEK,Reach-1,1
Up Type=0
Dn Type=3
Dn Slope=0.005
Boundary for River Rch & Prof#=CORRAL CREEK,Reach-1,2
Up Type=0
Dn Type=3
Dn Slope=0.005
Boundary for River Rch & Prof#=CORRAL CREEK,Reach-1,3
Up Type=0
Dn Type=3
Dn Slope=0.005
Boundary for River Rch & Prof#=CORRAL CREEK,Reach-1,4
Up Type=0
Dn Type=3
Dn Slope=0.005
Boundary for River Rch & Prof#=CORRAL CREEK,Reach-1,5
Up Type=0
Dn Type=3
Dn Slope=0.005
Boundary for River Rch & Prof#=CORRAL CREEK,Reach-1,6
Up Type=0
Dn Type=3
Dn Slope=0.005
Boundary for River Rch & Prof#=CORRAL CREEK,Reach-1,7
Up Type=0
Dn Type=3
Dn Slope=0.005

--- CORRAL CREEK.g01 (geometry) ---

Geom Title=Existing Conditions

River Reach=CORRAL CREEK,Reach-1
Reach XY= 30
      2376725.00     13606925.00      2376681.91     13606974.86
      2376723.80     13607264.50      2376624.59     13607450.00
      2376673.38     13607813.17      2376382.20     13608074.70
      2376472.46     13608219.30      2376718.01     13608274.72
      2376625.25     13608390.22      2376671.63     13608623.72
      2376536.11     13608714.68      2376566.75     13608778.22
      2376495.43     13608905.87      2376218.48     13608882.67
      2376119.56     13609169.75      2375815.32     13609285.76
      2375573.58     13609571.96      2375450.00     13609524.61
      2375180.94     13609577.26      2374875.10     13609767.68
      2374522.70     13609669.17      2374321.67     13609482.59
      2373919.15     13609872.95      2373732.97     13609872.06
      2373692.20     13609741.22      2373572.55     13609730.39
      2373482.79     13609821.57      2373521.46     13610023.53
      2373351.93     13610248.87      2373075.00     13610225.00

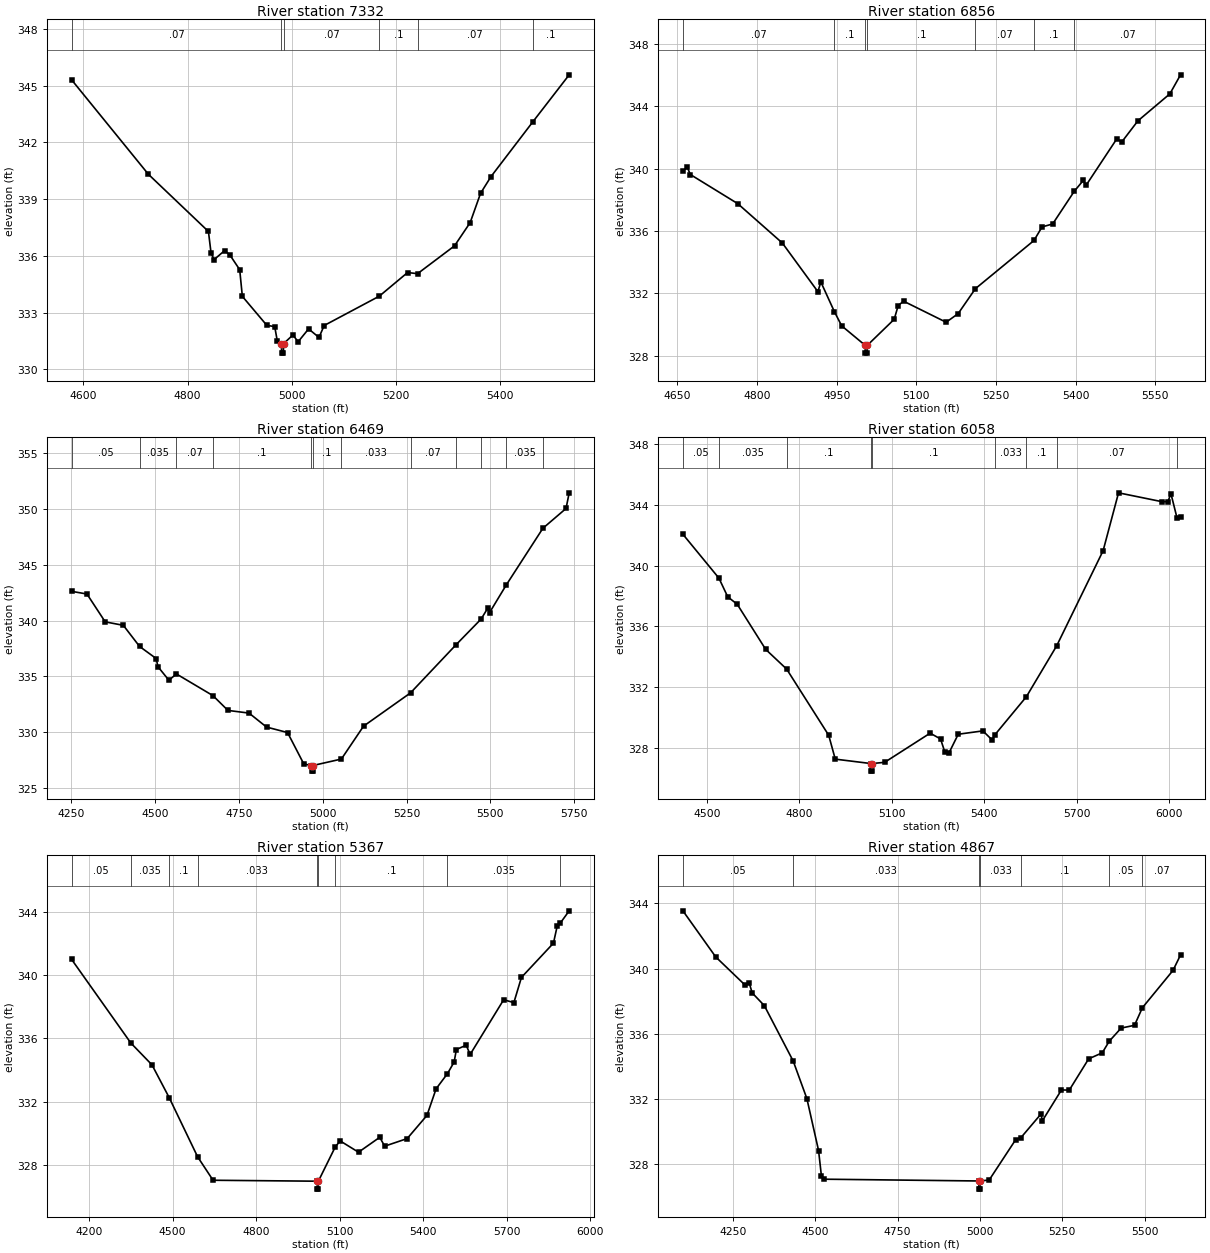
Type RM Length L Ch R = 1,7332,476,476,476
BEGIN DESCRIPTION:
CORRAL CREEK 14.0
END DESCRIPTION:
XS GIS Cut Line= 3
      2376275.04     13606925.01      2376653.51     13606989.59
      2377224.97     13607025.00
#Sta/Elev= 30
  4577.1  345.31  4724.9  340.31  4840.2  337.29  4845.2  336.16  4851.0  335.80
  4871.3  336.28  4881.4  336.05  4900.3  335.27  4905.4  333.86  4952.4  332.33
  4967.6  332.26  4972.6  331.50  4980.6  331.36  4980.8  330.86  4984.3  330.86
  4984.6  331.36  5002.6  331.82  5012.6  331.46  5032.7  332.14  5052.7  331.69
  5062.7  332.32  5168.6  333.87  5223.0  335.12  5242.2  335.06  5313.2  336.53
  5343.3  337.76  5363.3  339.31  5383.3  340.19  5463.3  343.07  5533.6  345.57
#Mann=6,-1,0
  4577.1    0.07       0  4980.6    0.05       0  4984.6    0.07       0
  5168.6     0.1       0  5242.2    0.07       0  5463.3     0.1       0
Bank Sta=4980.6,4984.6
Exp/Cntr=0.3,0.1

Type RM Length L Ch R = 1,6856,387,387,387
BEGIN DESCRIPTION:
CORRAL CREEK 13.0
END DESCRIPTION:
XS GIS Cut Line= 3
      2376325.02     13607275.01      2376625.00     13607425.00
      2377225.03     13607475.00
#Sta/Elev= 30
  4660.3  339.86  4668.7  340.07  4674.3  339.62  4763.7  337.75  4847.6  335.23
  4914.6  332.11  4920.2  332.73  4945.8  330.82  4959.4  329.92  5003.7  328.67
  5004.0  328.17  5007.5  328.17  5007.7  328.67  5058.4  330.34  5065.9  331.22
  5076.0  331.50  5156.2  330.15  5178.8  330.70  5211.3  332.30  5321.7  335.39
  5336.9  336.26  5356.9  336.45  5397.7  338.55  5414.6  339.24  5419.7  338.92
  5477.4  341.89  5487.4  341.72  5517.5  343.06  5577.7  344.79  5597.8  346.01
#Mann=7,-1,0
  4660.3    0.07       0  4945.8     0.1       0  5003.7    0.05       0
  5007.7     0.1       0  5211.3    0.07       0  5321.7     0.1       0
  5397.7    0.07       0
Bank Sta=5003.7,5007.7
Exp/Cntr=0.3,0.1

Type RM Length L Ch R = 1,6469,411,411,411
BEGIN DESCRIPTION:
X18560
END DESCRIPTION:
XS GIS Cut Line= 3
      2375959.04     13607575.52      2376705.60     13607805.56
      2377404.36     13607888.02
#Sta/Elev= 30
  4250.3  342.61  4296.3  342.37  4350.7  339.88  4404.8  339.57  4453.3  337.68
  4502.8  336.60  4508.1  335.87  4540.7  334.66  4563.3  335.22  4672.3  333.28
  4716.9  331.96  4779.9  331.72  4832.1  330.47  4894.8  329.98  4943.3  327.17
  4966.1  327.03  4966.3  326.53  4969.8  326.53  4970.1  327.03  5055.4  327.61
  5121.5  330.55  5261.8  333.53  5396.8  337.81  5472.3  340.13  5492.5  341.12
  5497.6  340.71  5547.6  343.19  5656.7  348.25  5725.7  350.02  5735.1  351.42
#Mann=12,-1,0
  4250.3    0.05       0  4453.3   0.035       0  4563.3    0.07       0
  4672.3     0.1       0  4966.1    0.05       0  4970.1     0.1       0
  5055.4   0.033       0  5261.8    0.07       0  5396.8   0.035       0
  5472.3    0.07       0  5547.6   0.035       0  5656.7    0.05       0
Bank Sta=4966.1,4970.1
Exp/Cntr=0.3,0.1

Type RM Length L Ch R = 1,6058,691,691,691
BEGIN DESCRIPTION:
X18559
END DESCRIPTION:
XS GIS Cut Line= 3
      2375833.22     13607922.75      2376662.19     13608113.72
      2377426.10     13608135.42
#Sta/Elev= 30
  4422.3  342.07  4539.2  339.18  4567.8  337.95  4598.6  337.46  4690.9  334.49
  4759.0  333.19  4895.5  328.83  4916.7  327.26  5032.2  326.97  5032.4  326.47
  5035.9  326.47  5036.2  326.97  5077.0  327.05  5224.6  328.97  5258.4  328.59
  5271.9  327.75  5285.8  327.67  5315.8  328.90  5395.8  329.12  5425.9  328.52
  5435.4  328.88  5536.9  331.37  5635.2  334.72  5786.0  340.99  5836.0  344.80
  5976.1  344.22  5996.1  344.22  6006.1  344.74  6025.5  343.17  6037.2  343.23
#Mann=9,-1,0
  4422.3    0.05       0  4539.2   0.035       0  4759.0     0.1       0
  5032.2    0.05       0  5036.2     0.1       0  5435.4   0.033       0
  5536.9     0.1       0  5635.2    0.07       0  6025.5    0.05       0
Bank Sta=5032.2,5036.2
Exp/Cntr=0.3,0.1

Type RM Length L Ch R = 1,5367,500,500,500
BEGIN DESCRIPTION:
X18558
END DESCRIPTION:
XS GIS Cut Line= 3
      2375798.52     13608178.84      2377070.18     13608565.11
      2377429.26     13608850.65
#Sta/Elev= 30
  4137.1  340.99  4350.1  335.71  4426.1  334.33  4488.0  332.26  4590.0  328.53
  4645.5  327.05  5019.8  326.99  5020.0  326.49  5023.5  326.49  5023.8  326.99
  5085.0  329.17  5102.3  329.53  5168.1  328.82  5244.3  329.76  5262.1  329.20
  5342.9  329.68  5413.9  331.14  5446.8  332.82  5487.7  333.78  5511.6  334.51
  5519.6  335.30  5554.8  335.57  5569.2  334.99  5689.5  338.44  5726.2  338.26
  5753.4  339.85  5868.4  342.01  5881.6  343.07  5892.7  343.27  5924.9  344.05
#Mann=9,-1,0
  4137.1    0.05       0  4350.1   0.035       0  4488.0     0.1       0
  4590.0   0.033       0  5019.8   0.033       0  5023.8   0.033       0
  5085.0     0.1       0  5487.7   0.035       0  5892.7    0.07       0
Bank Sta=5019.8,5023.8
Exp/Cntr=0.3,0.1

Type RM Length L Ch R = 1,4867,464,464,464
BEGIN DESCRIPTION:
CORRAL CREEK 10.0
END DESCRIPTION:
XS GIS Cut Line= 3
      2375724.98     13608424.99      2376597.09     13608838.55
      2377125.04     13608975.01
#Sta/Elev= 30
  4098.2  343.55  4197.8  340.72  4286.4  339.00  4299.8  339.10  4308.5  338.51
  4345.3  337.73  4433.1  334.32  4474.5  332.02  4510.0  328.83  4518.8  327.24
  4527.2  327.07  4996.5  326.96  4996.7  326.46  5000.2  326.46  5000.5  326.96
  5027.9  327.02  5108.4  329.50  5124.6  329.63  5184.6  331.06  5189.7  330.67
  5247.2  332.55  5271.0  332.54  5329.8  334.46  5371.1  334.83  5392.2  335.54
  5428.4  336.35  5469.0  336.52  5492.9  337.60  5585.8  339.89  5608.7  340.84
#Mann=7,-1,0
  4098.2    0.05       0  4433.1   0.033       0  4996.5   0.033       0
  5000.5   0.033       0  5124.6     0.1       0  5392.2    0.05       0
  5492.9    0.07       0
Bank Sta=4996.5,5000.5
Exp/Cntr=0.3,0.1

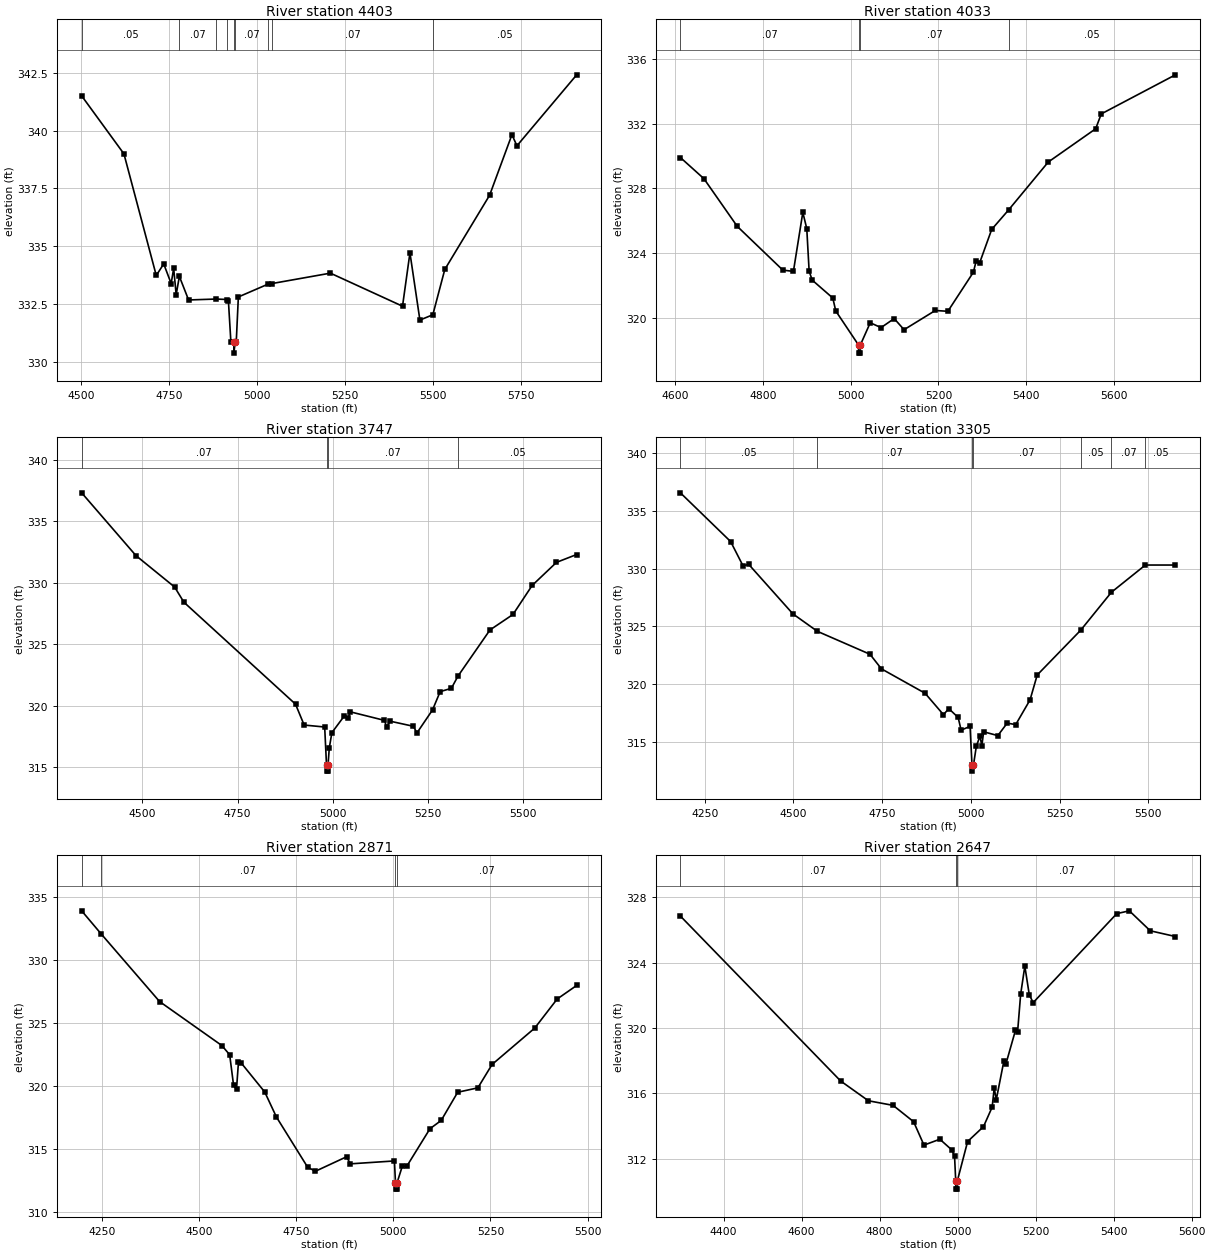
Type RM Length L Ch R = 1,4403,370,370,370
BEGIN DESCRIPTION:
CORRAL CREEK 9.0
END DESCRIPTION:
XS GIS Cut Line= 3
      2375825.03     13608575.03      2376132.68     13608881.95
      2376839.89     13609550.11
#Sta/Elev= 30
  4502.0  341.50  4622.2  338.99  4714.1  333.73  4735.3  334.23  4756.5  333.38
  4763.6  334.04  4770.7  332.90  4779.8  333.69  4806.0  332.67  4884.7  332.71
  4914.9  332.69  4919.2  332.64  4926.2  330.87  4934.6  330.87  4934.8  330.37
  4938.6  330.87  4941.6  330.87  4947.5  332.80  5031.2  333.35  5043.0  333.38
  5209.2  333.83  5414.3  332.40  5435.4  334.71  5463.7  331.80  5500.5  332.03
  5534.5  333.99  5661.9  337.20  5725.4  339.82  5739.6  339.34  5909.5  342.41
#Mann=9,-1,0
  4502.0    0.05       0  4779.8    0.07       0  4884.7    0.05       0
  4914.9    0.07       0  4934.6    0.05       0  4938.6    0.07       0
  5031.2    0.05       0  5043.0    0.07       0  5500.5    0.05       0
Bank Sta=4934.6,4938.6
Exp/Cntr=0.3,0.1

Type RM Length L Ch R = 1,4033,286,286,286
BEGIN DESCRIPTION:
CORRAL CREEK 8.0
END DESCRIPTION:
XS GIS Cut Line= 3
      2375875.01     13608825.02      2376054.55     13609289.94
      2376436.51     13609789.08
#Sta/Elev= 30
  4612.5  329.91  4666.1  328.60  4741.9  325.65  4845.7  322.94  4869.8  322.86
  4891.2  326.51  4900.2  325.51  4905.6  322.87  4912.6  322.32  4959.5  321.21
  4966.2  320.41  5018.1  318.30  5018.3  317.80  5021.8  317.80  5022.1  318.30
  5044.7  319.68  5069.3  319.38  5099.2  319.94  5121.7  319.25  5192.8  320.44
  5221.4  320.39  5279.5  322.81  5285.8  323.50  5293.5  323.37  5321.2  325.46
  5359.5  326.66  5449.9  329.63  5557.9  331.69  5570.6  332.61  5739.4  335.03
#Mann=4,-1,0
  4612.5    0.07       0  5018.1    0.05       0  5022.1    0.07       0
  5359.5    0.05       0
Bank Sta=5018.1,5022.1
Exp/Cntr=0.3,0.1

Type RM Length L Ch R = 1,3747,442,442,442
BEGIN DESCRIPTION:
CORRAL CREEK 7.0
END DESCRIPTION:
XS GIS Cut Line= 3
      2375529.38     13608712.68      2375775.00     13609325.00
      2375846.07     13609961.30
#Sta/Elev= 30
  4340.5  337.32  4483.1  332.21  4584.7  329.65  4608.9  328.42  4902.1  320.12
  4924.8  318.42  4978.7  318.26  4983.5  315.17  4983.7  314.67  4987.2  314.67
  4987.5  315.17  4990.8  316.56  4997.6  317.80  5030.4  319.17  5040.4  318.96
  5045.4  319.50  5135.7  318.80  5141.1  318.28  5151.2  318.73  5211.6  318.32
  5221.0  317.78  5261.9  319.65  5282.0  321.14  5311.4  321.41  5328.9  322.41
  5412.8  326.16  5473.2  327.42  5523.5  329.78  5587.4  331.66  5640.5  332.30
#Mann=4,-1,0
  4340.5    0.07       0  4983.5    0.05       0  4987.5    0.07       0
  5328.9    0.05       0
Bank Sta=4983.5,4987.5
Exp/Cntr=0.3,0.1

Type RM Length L Ch R = 1,3305,434,434,434
BEGIN DESCRIPTION:
CORRAL CREEK 6.0
END DESCRIPTION:
XS GIS Cut Line= 3
      2375264.62     13608738.72      2375475.00     13609525.00
      2375555.31     13610100.79
#Sta/Elev= 30
  4181.4  336.54  4323.0  332.33  4357.8  330.24  4374.2  330.35  4498.5  326.08
  4567.6  324.57  4715.8  322.59  4748.0  321.33  4871.1  319.22  4922.9  317.37
  4937.9  317.89  4964.3  317.13  4972.7  316.03  4997.9  316.36  5003.4  312.99
  5003.7  312.49  5007.4  312.99  5015.5  314.62  5025.6  315.51  5031.1  314.70
  5036.2  315.89  5076.1  315.56  5102.6  316.64  5126.6  316.51  5167.0  318.65
  5187.2  320.80  5309.5  324.66  5396.4  327.95  5492.0  330.30  5576.7  330.30
#Mann=7,-1,0
  4181.4    0.05       0  4567.6    0.07       0  5003.4    0.05       0
  5007.4    0.07       0  5309.5    0.05       0  5396.4    0.07       0
  5492.0    0.05       0
Bank Sta=5003.4,5007.4
Exp/Cntr=0.3,0.1

Type RM Length L Ch R = 1,2871,224,224,224
BEGIN DESCRIPTION:
CORRAL CREEK 5.0
END DESCRIPTION:
XS GIS Cut Line= 3
      2375025.00     13608825.01      2375075.00     13609625.00
      2375325.03     13610025.04
#Sta/Elev= 30
  4198.5  333.92  4248.5  332.09  4398.9  326.71  4559.2  323.21  4579.2  322.48
  4589.3  320.04  4596.8  319.74  4601.8  321.89  4609.3  321.81  4669.4  319.52
  4699.5  317.53  4779.6  313.55  4799.7  313.22  4879.8  314.37  4889.8  313.81
  5003.0  314.04  5005.7  312.30  5006.0  311.80  5009.5  311.80  5009.7  312.30
  5023.0  313.60  5035.4  313.65  5094.4  316.60  5123.3  317.26  5165.7  319.50
  5217.6  319.85  5254.2  321.71  5363.9  324.60  5421.6  326.91  5471.8  327.99
#Mann=4,-1,0
  4198.5    0.05       0  4248.5    0.07       0  5005.7    0.05       0
  5009.7    0.07       0
Bank Sta=5005.7,5009.7
Exp/Cntr=0.3,0.1

Type RM Length L Ch R = 1,2647,246,246,246
BEGIN DESCRIPTION:
X18557
END DESCRIPTION:
XS GIS Cut Line= 3
      2374769.82     13609051.18      2374917.40     13609836.81
      2375086.68     13610275.19
#Sta/Elev= 30
  4289.1  326.84  4700.0  316.76  4771.2  315.55  4834.5  315.27  4887.1  314.27
  4913.7  312.84  4954.4  313.20  4984.9  312.55  4992.1  312.17  4995.1  310.65
  4995.4  310.15  4998.9  310.15  4999.2  310.65  5025.6  313.06  5066.3  313.97
  5088.5  315.16  5093.8  316.32  5099.1  315.62  5118.4  317.96  5123.7  317.79
  5148.3  319.86  5153.7  319.75  5161.6  322.06  5172.3  323.78  5183.7  322.03
  5193.7  321.55  5408.1  326.99  5440.3  327.16  5493.9  325.94  5558.4  325.59
#Mann=3,-1,0
  4289.1    0.07       0  4995.1    0.05       0  4999.2    0.07       0
Bank Sta=4995.1,4999.2
Exp/Cntr=0.3,0.1

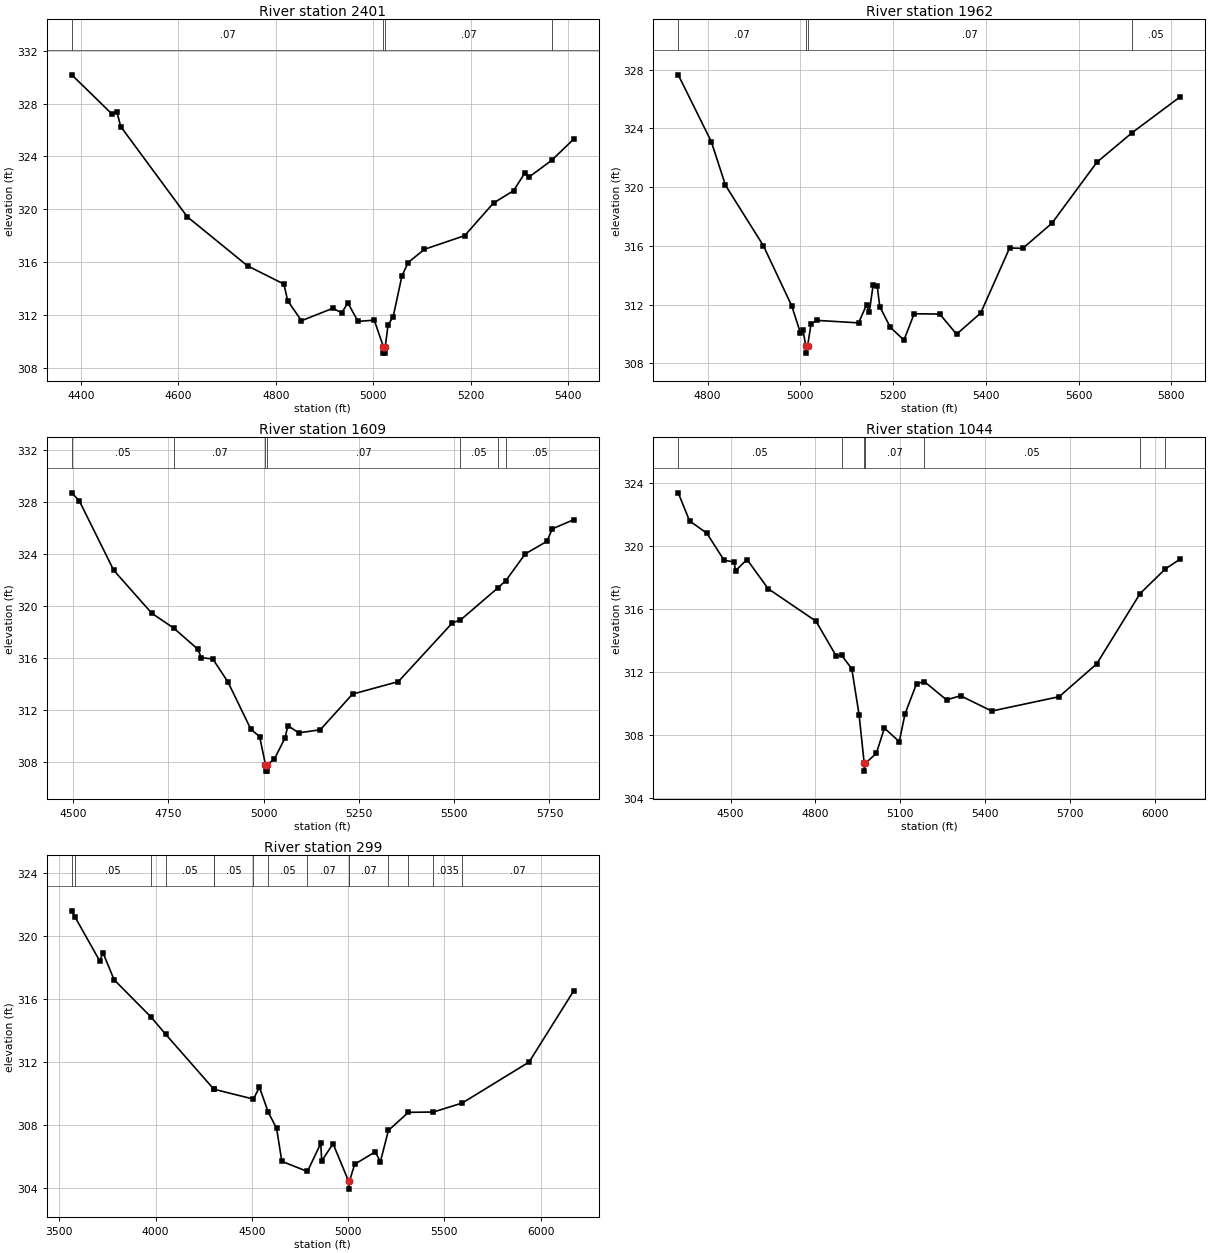
Type RM Length L Ch R = 1,2401,439,439,439
BEGIN DESCRIPTION:
CORRAL CREEK 4.0
END DESCRIPTION:
XS GIS Cut Line= 3
      2374525.00     13609124.98      2374675.00     13609725.00
      2374775.00     13610125.00
#Sta/Elev= 30
  4381.1  330.17  4463.6  327.21  4473.9  327.35  4481.6  326.26  4618.2  319.44
  4741.9  315.73  4816.6  314.35  4824.4  313.09  4852.7  311.58  4917.1  312.52
  4935.2  312.18  4948.0  312.92  4968.7  311.53  5002.2  311.62  5020.7  309.63
  5021.0  309.13  5024.6  309.13  5024.8  309.63  5030.5  311.28  5040.8  311.85
  5058.9  314.96  5071.7  315.98  5105.2  316.98  5187.7  318.01  5247.0  320.48
  5288.2  321.41  5311.4  322.76  5319.1  322.42  5366.2  323.70  5411.9  325.32
#Mann=4,-1,0
  4381.1    0.07       0  5020.7    0.05       0  5024.8    0.07       0
  5366.2    0.05       0
Bank Sta=5020.7,5024.8
Exp/Cntr=0.3,0.1

Type RM Length L Ch R = 1,1962,353,353,353
BEGIN DESCRIPTION:
CORRAL CREEK 3.0
END DESCRIPTION:
XS GIS Cut Line= 3
      2374275.01     13609225.04      2374325.00     13609475.00
      2374675.02     13610225.04
#Sta/Elev= 30
  4736.6  327.65  4807.9  323.10  4838.5  320.13  4920.1  316.02  4981.3  311.92
  5000.2  310.06  5005.7  310.28  5011.5  309.20  5011.8  308.70  5015.6  309.20
  5023.0  310.69  5035.7  310.93  5125.5  310.76  5142.9  312.01  5148.4  311.47
  5157.0  313.36  5165.7  313.25  5171.2  311.86  5194.1  310.45  5223.3  309.59
  5245.3  311.38  5300.5  311.36  5336.8  309.99  5388.8  311.43  5451.1  315.86
  5479.4  315.83  5542.5  317.55  5639.4  321.70  5715.3  323.71  5819.2  326.16
#Mann=4,-1,0
  4736.6    0.07       0  5011.5    0.05       0  5015.6    0.07       0
  5715.3    0.05       0
Bank Sta=5011.5,5015.6
Exp/Cntr=0.3,0.1

Type RM Length L Ch R = 1,1609,565,565,565
BEGIN DESCRIPTION:
CORRAL CREEK 2.0
END DESCRIPTION:
XS GIS Cut Line= 3
      2374075.00     13609225.01      2374066.71     13609715.28
      2374625.03     13610325.03
#Sta/Elev= 30
  4496.9  328.68  4516.9  328.05  4606.9  322.73  4706.9  319.42  4764.1  318.29
  4826.9  316.68  4836.9  316.01  4866.9  315.91  4907.0  314.12  4967.0  310.49
  4989.7  309.95  5005.0  307.79  5005.3  307.29  5008.9  307.29  5009.1  307.79
  5028.0  308.20  5056.4  309.84  5063.8  310.79  5092.2  310.23  5148.9  310.47
  5233.4  313.21  5353.6  314.17  5495.5  318.69  5516.4  318.90  5614.6  321.37
  5635.8  321.94  5686.6  323.99  5743.3  324.95  5757.5  325.91  5814.0  326.62
#Mann=7,-1,0
  4496.9    0.05       0  4764.1    0.07       0  5005.0    0.05       0
  5009.1    0.07       0  5516.4    0.05       0  5614.6    0.07       0
  5635.8    0.05       0
Bank Sta=5005,5009.1
Exp/Cntr=0.3,0.1

Type RM Length L Ch R = 1,1044,745,745,745
BEGIN DESCRIPTION:
X18556
END DESCRIPTION:
XS GIS Cut Line= 4
      2373793.26     13609055.58      2373650.04     13609893.24
      2373710.80     13610179.69      2374253.32     13610500.87
#Sta/Elev= 30
  4315.4  323.35  4355.4  321.57  4416.3  320.79  4477.1  319.08  4512.7  318.96
  4517.8  318.41  4558.3  319.12  4632.9  317.27  4801.8  315.21  4873.3  313.00
  4892.2  313.05  4928.3  312.19  4954.0  309.29  4972.1  306.20  4972.4  305.70
  4976.3  306.20  5014.8  306.82  5043.5  308.43  5096.0  307.57  5116.3  309.33
  5156.9  311.24  5184.4  311.38  5262.8  310.22  5312.4  310.48  5422.6  309.51
  5660.6  310.42  5793.2  312.50  5946.4  316.96  6036.0  318.53  6088.5  319.15
#Mann=7,-1,0
  4315.4    0.05       0  4892.2    0.07       0  4972.1    0.05       0
  4976.3    0.07       0  5184.4    0.05       0  5946.4    0.07       0
  6036.0    0.05       0
Bank Sta=4972.1,4976.3
Exp/Cntr=0.3,0.1

Type RM Length L Ch R = 1,299,0,0,0
BEGIN DESCRIPTION:
CORRAL CREEK 1.0
END DESCRIPTION:
XS GIS Cut Line= 4
      2373689.10     13608916.68      2373263.75     13609858.51
      2373402.64     13610492.19      2374257.68     13610848.10
#Sta/Elev= 30
  3564.8  321.61  3582.4  321.20  3709.7  318.44  3727.4  318.94  3784.6  317.24
  3976.1  314.88  4051.9  313.79  4301.2  310.32  4305.2  310.29  4508.5  309.67
  4539.7  310.42  4585.5  308.84  4628.9  307.81  4656.1  305.72  4789.1  305.08
  4858.3  306.86  4863.4  305.75  4922.2  306.84  5003.0  304.46  5003.3  303.96
  5007.2  304.46  5034.8  305.54  5141.8  306.33  5167.9  305.69  5209.7  307.68
  5313.3  308.83  5443.5  308.85  5593.1  309.42  5940.6  312.02  6173.1  316.55
#Mann=15,-1,0
  3564.8    0.07       0  3582.4    0.05       0  3976.1    0.07       0
  4051.9    0.05       0  4301.2    0.07       0  4305.2    0.05       0
  4508.5    0.07       0  4585.5    0.05       0  4789.1    0.07       0
  5003.0    0.05       0  5007.2    0.07       0  5209.7    0.05       0
  5313.3    0.07       0  5443.5   0.035       0  5593.1    0.07       0
Bank Sta=5003,5007.2
Exp/Cntr=0.3,0.1

Chan Stop Cuts=-1