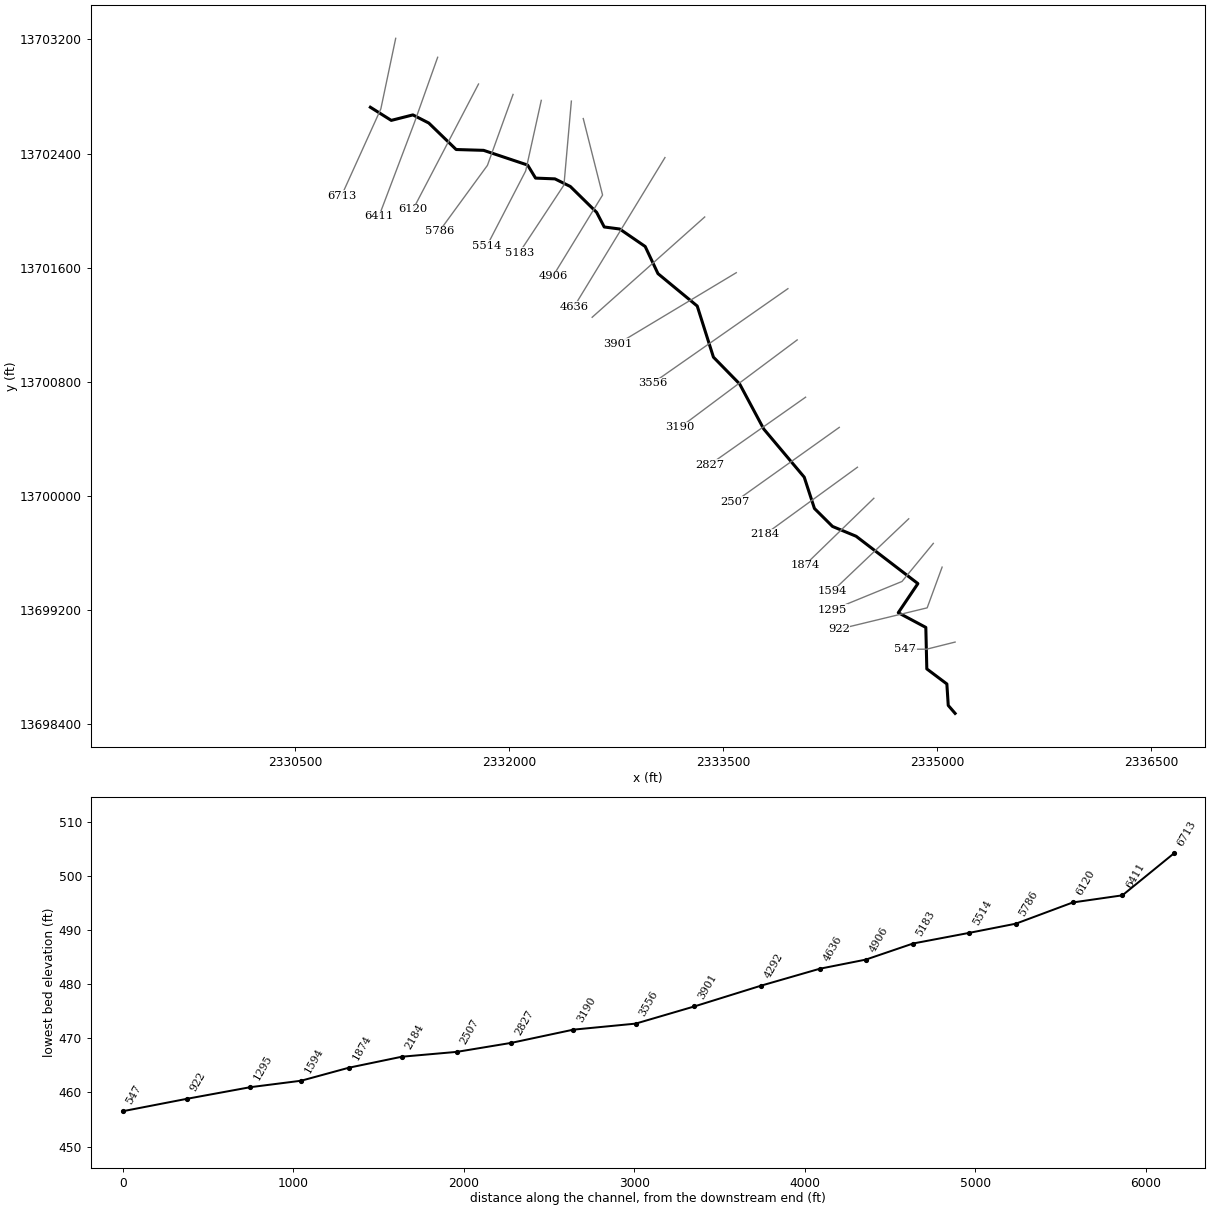
--- DUKES HOLLOW CREEK.prj (project) ---

Proj Title=DUKES HOLLOW CREEK Base Level Engineering
Current Plan=p01
Default Exp/Contr=0.3,0.1
English Units
Geom File=g01
Flow File=f01
Plan File=p01
BEGIN DESCRIPTION:
DUKES HOLLOW CREEK
END DESCRIPTION:

--- DUKES HOLLOW CREEK.p01 (plan) ---

Plan Title=Multiple Run
Short Identifier=Multiple
Geom File=g01
Flow File=f01
Subcritical Flow
K Sum by GR= 0
Std Step Tol= 0.01
Critical Tol= 0.01
Num of Std Step Trials= 20
Max Error Tol= 0.3
Flow Tol Ratio= 0.001
Split Flow NTrial= 30
Split Flow Tol= 0.02
Split Flow Ratio= 0.02
Log Output Level= 0
Friction Slope Method= 1
Unsteady Friction Slope Method= 2
Unsteady Bridges Friction Slope Method= 1
Parabolic Critical Depth
Global Vel Dist=  1 , 1 , 1
Global Log Level= 0
CheckData=True
Encroach Param= -1, 0, 0, 0
BEGIN DESCRIPTION:
Multiple Run
END DESCRIPTION:

--- DUKES HOLLOW CREEK.f01 (steady flow) ---

Flow Title=Multiple
Number of Profiles=7
Profile Names=10-year,25-year,50-year,1pct_min,100-year,1pct_plu,500-year
River Rch & RM= DUKES HOLLOW CRE,Reach-1,6713
     498     800    1071     696    1388    2769    2307
Boundary for River Rch & Prof#=DUKES HOLLOW CRE,Reach-1,1
Up Type=0
Dn Type=3
Dn Slope=0.005
Boundary for River Rch & Prof#=DUKES HOLLOW CRE,Reach-1,2
Up Type=0
Dn Type=3
Dn Slope=0.005
Boundary for River Rch & Prof#=DUKES HOLLOW CRE,Reach-1,3
Up Type=0
Dn Type=3
Dn Slope=0.005
Boundary for River Rch & Prof#=DUKES HOLLOW CRE,Reach-1,4
Up Type=0
Dn Type=3
Dn Slope=0.005
Boundary for River Rch & Prof#=DUKES HOLLOW CRE,Reach-1,5
Up Type=0
Dn Type=3
Dn Slope=0.005
Boundary for River Rch & Prof#=DUKES HOLLOW CRE,Reach-1,6
Up Type=0
Dn Type=3
Dn Slope=0.005
Boundary for River Rch & Prof#=DUKES HOLLOW CRE,Reach-1,7
Up Type=0
Dn Type=3
Dn Slope=0.005

--- DUKES HOLLOW CREEK.g01 (geometry) ---

Geom Title=Existing Conditions

River Reach=DUKES HOLLOW CRE,Reach-1
Reach XY= 30
      2331025.00     13702725.00      2331171.59     13702632.79
      2331323.41     13702671.32      2331434.68     13702614.24
      2331626.46     13702428.54      2331819.06     13702422.74
      2332127.66     13702319.54      2332183.32     13702228.11
      2332319.06     13702222.75      2332427.30     13702169.17
      2332611.36     13701988.20      2332664.90     13701885.39
      2332773.41     13701871.17      2332952.01     13701748.52
      2333041.63     13701558.29      2333316.86     13701331.06
      2333430.52     13700972.57      2333614.24     13700784.68
      2333783.16     13700468.95      2334067.14     13700131.17
      2334138.62     13699911.78      2334265.32     13699785.76
      2334431.06     13699716.86      2334864.06     13699385.02
      2334726.49     13699180.85      2334919.66     13699077.74
      2334926.62     13698786.83      2335067.19     13698681.21
      2335076.91     13698530.79      2335125.00     13698475.00

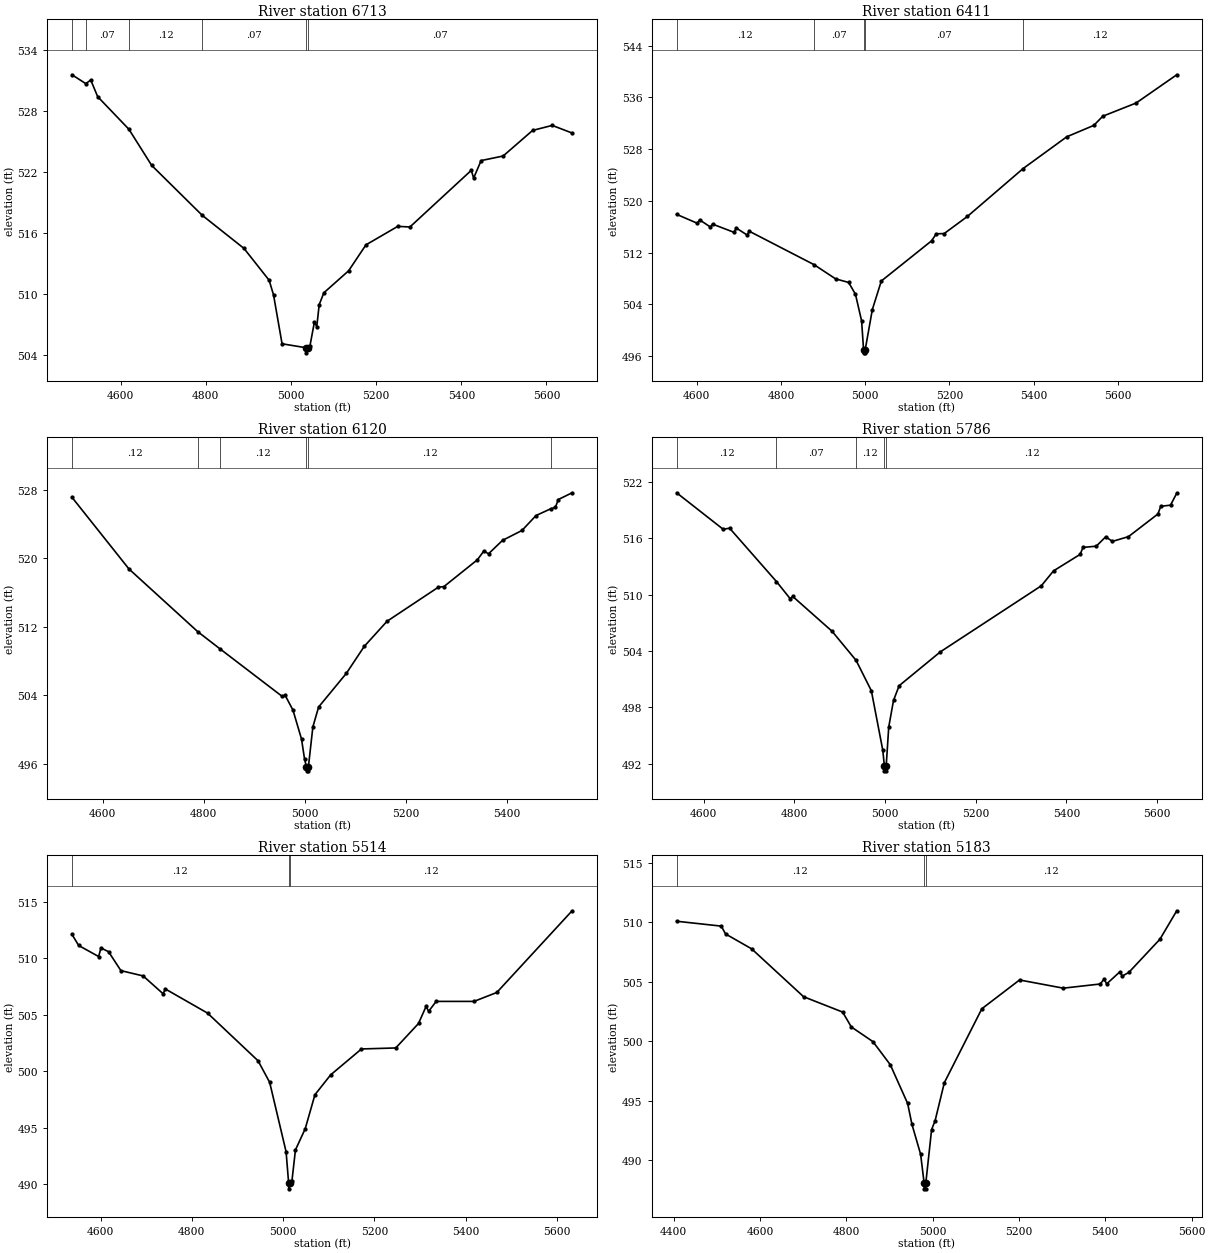
Type RM Length L Ch R = 1,6713,302,302,302
BEGIN DESCRIPTION:
X19079
END DESCRIPTION:
XS GIS Cut Line= 3
      2331202.63     13703208.11      2331098.46     13702713.32
      2330822.43     13702103.96
#Sta/Elev= 30
  4485.6  531.61  4518.0  530.74  4529.7  531.09  4545.9  529.46  4619.3  526.25
  4672.7  522.70  4791.4  517.79  4889.6  514.53  4948.6  511.40  4958.9  509.97
  4979.0  505.15  5035.4  504.76  5035.6  504.26  5039.4  504.76  5044.3  504.90
  5055.0  507.30  5060.5  506.83  5066.2  509.00  5077.2  510.17  5135.3  512.33
  5176.0  514.88  5250.7  516.70  5279.3  516.64  5423.4  522.21  5428.9  521.45
  5446.5  523.17  5498.2  523.62  5567.5  526.14  5613.6  526.63  5660.2  525.88
#Mann=6,-1,0
  4485.6   0.035       0  4518.0    0.07       0  4619.3    0.12       0
  4791.4    0.07       0  5035.4    0.05       0  5039.4    0.07       0
Bank Sta=5035.4,5039.4
Exp/Cntr=0.3,0.1

Type RM Length L Ch R = 1,6411,291,291,291
BEGIN DESCRIPTION:
X19078
END DESCRIPTION:
XS GIS Cut Line= 3
      2331496.90     13703075.30      2331332.84     13702614.36
      2331085.43     13701960.68
#Sta/Elev= 30
  4552.1  517.92  4601.3  516.54  4606.7  517.07  4632.2  515.97  4637.5  516.41
  4688.5  515.14  4693.8  515.81  4719.4  514.73  4724.7  515.31  4878.3  510.15
  4929.9  507.94  4960.7  507.39  4977.0  505.56  4991.6  501.43  4996.2  497.00
  4996.5  496.50  5000.0  496.50  5000.2  497.00  5017.1  503.20  5038.4  507.61
  5157.7  513.82  5169.0  514.91  5187.8  514.95  5242.8  517.59  5375.4  525.01
  5479.1  529.92  5543.2  531.68  5564.6  533.10  5643.7  535.14  5740.3  539.51
#Mann=5,-1,0
  4552.1    0.12       0  4878.3    0.07       0  4996.2    0.05       0
  5000.2    0.07       0  5375.4    0.12       0
Bank Sta=4996.2,5000.2
Exp/Cntr=0.3,0.1

Type RM Length L Ch R = 1,6120,334,334,334
BEGIN DESCRIPTION:
X19077
END DESCRIPTION:
XS GIS Cut Line= 2
      2331783.37     13702887.81      2331325.02     13702010.19
#Sta/Elev= 30
  4539.4  527.13  4652.2  518.76  4788.5  511.43  4831.5  509.47  4955.7  503.87
  4961.4  504.00  4976.9  502.27  4993.8  498.89  4999.9  496.52  5003.5  495.68
  5003.8  495.18  5007.3  495.18  5007.5  495.68  5016.3  500.32  5027.7  502.64
  5082.6  506.57  5117.9  509.71  5163.1  512.65  5264.9  516.64  5275.7  516.70
  5341.9  519.83  5354.8  520.86  5364.0  520.53  5391.7  522.10  5430.3  523.26
  5458.0  525.00  5486.8  525.78  5496.5  525.96  5502.1  526.87  5529.5  527.66
#Mann=6,-1,0
  4539.4    0.12       0  4788.5    0.07       0  4831.5    0.12       0
  5003.5    0.05       0  5007.5    0.12       0  5486.8    0.07       0
Bank Sta=5003.5,5007.5
Exp/Cntr=0.3,0.1

Type RM Length L Ch R = 1,5786,272,272,272
BEGIN DESCRIPTION:
X19076
END DESCRIPTION:
XS GIS Cut Line= 3
      2332025.53     13702814.84      2331845.86     13702317.48
      2331507.33     13701853.96
#Sta/Elev= 30
  4540.7  520.87  4643.4  516.98  4657.5  517.10  4760.9  511.41  4791.4  509.57
  4796.7  509.83  4883.4  506.12  4936.4  503.02  4970.1  499.78  4995.4  493.42
  4998.8  491.75  4999.0  491.25  5002.5  491.25  5002.8  491.75  5008.4  495.91
  5019.0  498.76  5031.4  500.32  5122.1  503.92  5344.8  510.96  5371.8  512.55
  5430.5  514.31  5436.7  515.05  5466.0  515.18  5486.9  516.18  5501.6  515.69
  5537.1  516.20  5602.0  518.61  5608.2  519.43  5629.8  519.55  5643.5  520.83
#Mann=5,-1,0
  4540.7    0.12       0  4760.9    0.07       0  4936.4    0.12       0
  4998.8    0.05       0  5002.8    0.12       0
Bank Sta=4998.8,5002.8
Exp/Cntr=0.3,0.1

Type RM Length L Ch R = 1,5514,331,331,331
BEGIN DESCRIPTION:
X19075
END DESCRIPTION:
XS GIS Cut Line= 3
      2332223.45     13702773.17      2332114.09     13702278.42
      2331843.28     13701755.03
#Sta/Elev= 30
  4537.4  512.13  4552.1  511.15  4595.8  510.17  4600.9  510.93  4617.5  510.60
  4644.6  508.92  4693.3  508.45  4737.0  506.87  4742.1  507.29  4834.5  505.15
  4945.2  500.92  4970.6  499.01  5006.6  492.85  5012.2  490.06  5012.5  489.56
  5016.2  490.06  5019.4  490.25  5027.1  493.01  5048.5  494.89  5069.8  497.91
  5104.2  499.67  5171.8  501.97  5246.9  502.06  5296.8  504.23  5313.3  505.74
  5319.0  505.31  5335.5  506.19  5418.4  506.19  5468.3  506.98  5633.4  514.23
#Mann=3,-1,0
  4537.4    0.12       0  5012.2    0.05       0  5016.2    0.12       0
Bank Sta=5012.2,5016.2
Exp/Cntr=0.3,0.1

Type RM Length L Ch R = 1,5183,277,277,277
BEGIN DESCRIPTION:
X19074
END DESCRIPTION:
XS GIS Cut Line= 3
      2332434.40     13702767.99      2332382.32     13702179.46
      2332069.89     13701705.62
#Sta/Elev= 30
  4407.1  510.09  4510.5  509.68  4520.5  509.02  4580.8  507.77  4701.2  503.74
  4791.6  502.45  4811.7  501.20  4861.9  499.96  4902.0  498.02  4942.2  494.76
  4952.2  493.00  4972.3  490.48  4980.3  488.08  4980.6  487.58  4984.1  487.58
  4984.3  488.08  4997.7  492.57  5005.7  493.30  5027.2  496.51  5114.1  502.73
  5201.4  505.15  5302.7  504.46  5388.1  504.81  5397.2  505.22  5403.2  504.82
  5433.3  505.82  5439.3  505.48  5454.4  505.78  5526.6  508.58  5565.5  510.97
#Mann=3,-1,0
  4407.1    0.12       0  4980.3    0.05       0  4984.3    0.12       0
Bank Sta=4980.3,4984.3
Exp/Cntr=0.3,0.1

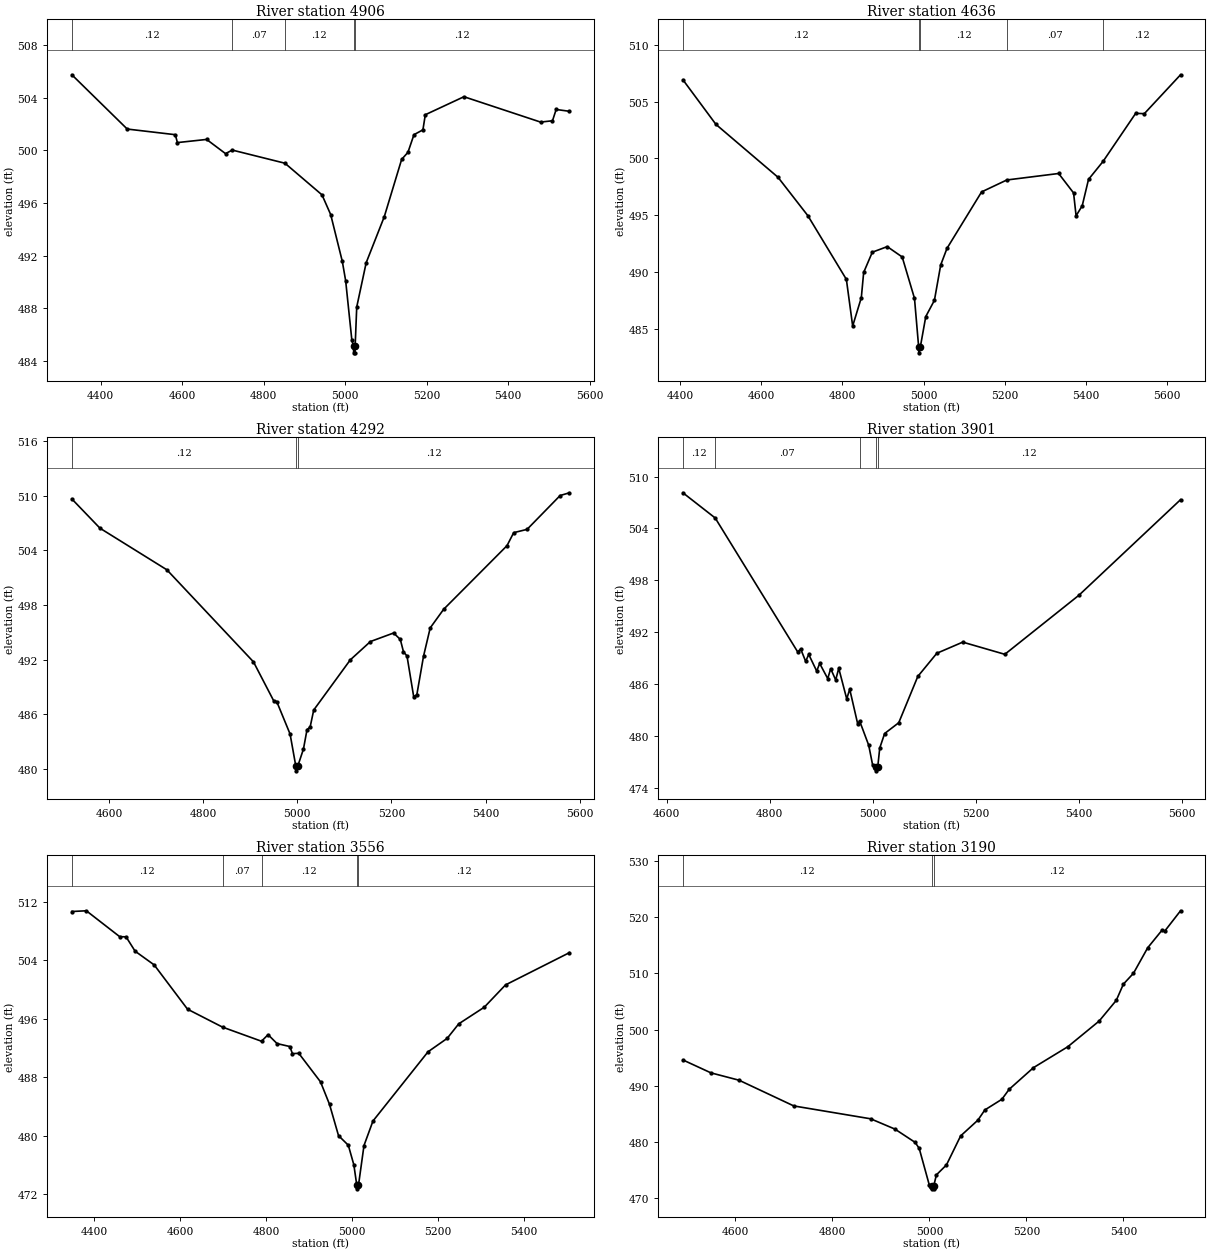
Type RM Length L Ch R = 1,4906,270,270,270
BEGIN DESCRIPTION:
X19073
END DESCRIPTION:
XS GIS Cut Line= 3
      2332517.73     13702645.64      2332653.15     13702109.15
      2332304.57     13701539.45
#Sta/Elev= 30
  4329.0  505.76  4464.9  501.63  4582.9  501.20  4588.0  500.60  4659.7  500.84
  4706.1  499.76  4722.7  500.03  4851.9  499.03  4942.9  496.62  4964.2  495.12
  4992.7  491.56  5000.9  490.09  5016.1  485.57  5020.2  485.10  5020.5  484.60
  5024.0  484.60  5024.2  485.10  5028.1  488.09  5051.3  491.46  5095.7  494.96
  5138.3  499.32  5153.8  499.86  5168.5  501.20  5190.5  501.57  5196.4  502.72
  5291.2  504.09  5479.2  502.16  5508.5  502.26  5517.5  503.12  5550.2  502.98
#Mann=5,-1,0
  4329.0    0.12       0  4722.7    0.07       0  4851.9    0.12       0
  5020.2    0.05       0  5024.2    0.12       0
Bank Sta=5020.2,5024.2
Exp/Cntr=0.3,0.1

Type RM Length L Ch R = 1,4636,344,344,344
BEGIN DESCRIPTION:
X19072
END DESCRIPTION:
XS GIS Cut Line= 2
      2333090.62     13702372.13      2332452.64     13701325.32
#Sta/Elev= 30
  4407.3  506.92  4488.6  503.00  4641.5  498.35  4715.1  494.97  4810.0  489.37
  4825.5  485.27  4846.8  487.76  4852.6  489.98  4873.9  491.76  4910.7  492.25
  4947.5  491.34  4977.8  487.70  4988.1  483.41  4988.4  482.91  4992.1  483.41
  5005.6  486.10  5026.9  487.53  5042.4  490.64  5057.9  492.10  5143.1  497.06
  5205.3  498.11  5332.9  498.68  5369.7  496.97  5375.9  494.96  5391.0  495.84
  5406.5  498.16  5442.3  499.74  5522.7  503.97  5544.0  503.94  5633.2  507.36
#Mann=5,-1,0
  4407.3    0.12       0  4988.1    0.05       0  4992.1    0.12       0
  5205.3    0.07       0  5442.3    0.12       0
Bank Sta=4988.1,4992.1
Exp/Cntr=0.3,0.1

Type RM Length L Ch R = 1,4292,391,391,391
BEGIN DESCRIPTION:
X19071
END DESCRIPTION:
XS GIS Cut Line= 2
      2333369.27     13701955.48      2332580.20     13701252.35
#Sta/Elev= 30
  4521.3  509.64  4581.0  506.43  4723.1  501.86  4907.0  491.75  4949.7  487.50
  4956.4  487.39  4984.8  483.82  4997.0  480.28  4997.3  479.78  5001.0  480.28
  5013.2  482.18  5020.7  484.29  5027.4  484.60  5035.0  486.46  5112.7  491.97
  5155.4  493.98  5204.7  494.92  5218.9  494.21  5225.6  492.86  5233.1  492.39
  5247.3  487.93  5254.0  488.14  5268.2  492.37  5282.4  495.48  5310.9  497.52
  5445.5  504.51  5459.7  505.94  5488.1  506.30  5558.4  510.02  5578.2  510.32
#Mann=3,-1,0
  4521.3    0.12       0  4997.0    0.05       0  5001.0    0.12       0
Bank Sta=4997,5001
Exp/Cntr=0.3,0.1

Type RM Length L Ch R = 1,3901,345,345,345
BEGIN DESCRIPTION:
X19070
END DESCRIPTION:
XS GIS Cut Line= 2
      2333590.67     13701564.89      2332762.57     13701067.51
#Sta/Elev= 30
  4631.8  508.13  4694.5  505.21  4854.6  489.71  4860.4  490.05  4870.1  488.61
  4876.0  489.42  4891.5  487.49  4897.3  488.37  4912.9  486.62  4918.7  487.76
  4928.4  486.46  4934.3  487.81  4949.8  484.27  4955.6  485.39  4971.2  481.35
  4974.8  481.72  4992.5  478.90  5000.0  476.64  5006.1  476.44  5006.3  475.94
  5010.1  476.44  5013.9  478.58  5023.4  480.26  5050.8  481.51  5087.8  486.87
  5124.7  489.55  5175.0  490.84  5256.7  489.43  5400.6  496.27  5597.8  507.33
#Mann=5,-1,0
  4631.8    0.12       0  4694.5    0.07       0  4974.8    0.12       0
  5006.1    0.05       0  5010.1    0.12       0
Bank Sta=5006.1,5010.1
Exp/Cntr=0.3,0.1

Type RM Length L Ch R = 1,3556,366,366,366
BEGIN DESCRIPTION:
X19069
END DESCRIPTION:
XS GIS Cut Line= 2
      2333952.63     13701452.90      2333002.94     13700789.42
#Sta/Elev= 30
  4347.7  510.65  4381.4  510.75  4459.1  507.21  4473.9  507.19  4494.9  505.23
  4539.4  503.35  4617.0  497.30  4698.5  494.85  4789.2  492.92  4804.5  493.82
  4825.4  492.60  4855.1  492.20  4861.2  491.23  4876.0  491.27  4926.6  487.37
  4947.5  484.30  4968.5  480.02  4991.3  478.71  5004.2  476.03  5011.0  473.25
  5011.2  472.75  5015.0  473.25  5027.8  478.67  5048.7  482.02  5176.9  491.48
  5221.4  493.31  5248.4  495.30  5307.8  497.57  5357.3  500.62  5506.2  505.03
#Mann=5,-1,0
  4347.7    0.12       0  4698.5    0.07       0  4789.2    0.12       0
  5011.0    0.05       0  5015.0    0.12       0
Bank Sta=5011,5015
Exp/Cntr=0.3,0.1

Type RM Length L Ch R = 1,3190,363,363,363
BEGIN DESCRIPTION:
X19068
END DESCRIPTION:
XS GIS Cut Line= 2
      2334017.75     13701093.54      2333195.54     13700479.48
#Sta/Elev= 30
  4491.6  494.58  4549.4  492.28  4607.4  490.97  4720.3  486.39  4878.8  484.10
  4928.8  482.27  4970.5  479.90  4978.9  478.83  4999.7  472.31  5004.8  472.13
  5005.0  471.63  5008.5  471.63  5008.8  472.13  5014.3  474.11  5035.1  475.89
  5064.3  481.05  5099.8  483.85  5114.3  485.68  5149.3  487.57  5164.4  489.35
  5214.4  493.20  5285.3  496.93  5349.9  501.50  5385.3  505.19  5399.9  508.07
  5420.8  510.02  5450.0  514.54  5479.2  517.64  5485.4  517.54  5517.8  521.14
#Mann=3,-1,0
  4491.6    0.12       0  5004.8    0.05       0  5008.8    0.12       0
Bank Sta=5004.8,5008.8
Exp/Cntr=0.3,0.1

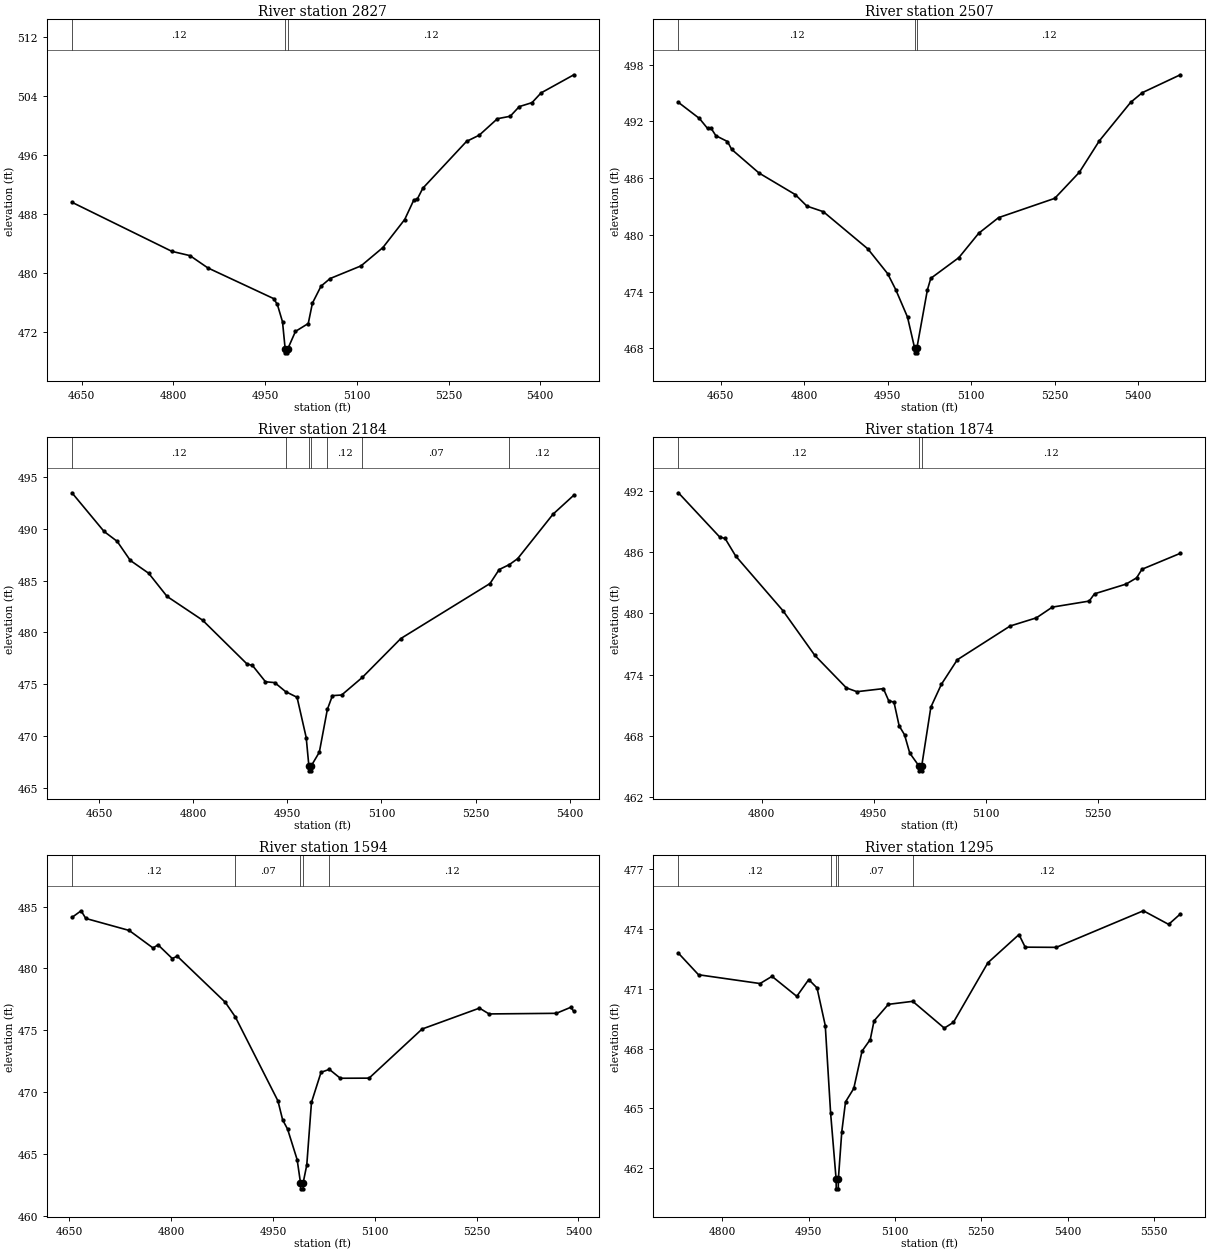
Type RM Length L Ch R = 1,2827,320,320,320
BEGIN DESCRIPTION:
X19067
END DESCRIPTION:
XS GIS Cut Line= 2
      2334076.65     13700691.90      2333405.37     13700219.74
#Sta/Elev= 30
  4634.2  489.62  4797.6  482.96  4827.2  482.38  4856.3  480.72  4964.0  476.55
  4970.1  475.75  4978.5  473.40  4982.9  469.69  4983.1  469.19  4986.6  469.19
  4986.9  469.69  4999.7  472.10  5020.6  473.17  5027.4  475.93  5041.5  478.24
  5056.3  479.27  5106.9  480.99  5142.6  483.47  5178.3  487.28  5193.1  489.91
  5199.2  490.10  5207.9  491.52  5279.4  497.88  5300.3  498.73  5329.9  500.96
  5350.8  501.29  5365.6  502.60  5386.5  503.14  5401.3  504.46  5454.9  506.92
#Mann=3,-1,0
  4634.2    0.12       0  4982.9    0.05       0  4986.9    0.12       0
Bank Sta=4982.9,4986.9
Exp/Cntr=0.3,0.1

Type RM Length L Ch R = 1,2507,323,323,323
BEGIN DESCRIPTION:
X19066
END DESCRIPTION:
XS GIS Cut Line= 2
      2334312.86     13700480.31      2333578.75     13699957.41
#Sta/Elev= 30
  4574.4  494.01  4612.1  492.31  4626.8  491.25  4633.2  491.26  4641.6  490.49
  4662.5  489.87  4670.0  489.04  4719.1  486.54  4784.2  484.26  4805.1  483.04
  4834.6  482.45  4914.5  478.52  4950.2  475.89  4964.7  474.20  4985.8  471.30
  4998.6  468.02  4998.8  467.52  5002.3  467.52  5002.6  468.02  5021.5  474.18
  5027.6  475.40  5078.0  477.59  5113.7  480.17  5149.3  481.82  5250.2  483.86
  5294.4  486.62  5330.1  489.93  5386.6  494.02  5407.5  495.04  5475.7  496.93
#Mann=3,-1,0
  4574.4    0.12       0  4998.6    0.05       0  5002.6    0.12       0
Bank Sta=4998.6,5002.6
Exp/Cntr=0.3,0.1

Type RM Length L Ch R = 1,2184,310,310,310
BEGIN DESCRIPTION:
X19065
END DESCRIPTION:
XS GIS Cut Line= 2
      2334440.21     13700200.93      2333793.13     13699730.52
#Sta/Elev= 30
  4606.6  493.50  4657.8  489.76  4678.6  488.81  4699.6  486.96  4728.9  485.72
  4758.2  483.48  4814.7  481.19  4885.8  476.94  4894.3  476.81  4915.1  475.23
  4929.8  475.15  4947.1  474.28  4965.4  473.73  4980.0  469.83  4984.2  467.12
  4984.5  466.62  4988.0  466.62  4988.2  467.12  5000.9  468.42  5013.7  472.56
  5021.8  473.89  5036.5  473.95  5069.4  475.65  5130.8  479.41  5273.0  484.73
  5287.6  486.08  5303.9  486.56  5317.0  487.13  5373.4  491.43  5406.6  493.27
#Mann=7,-1,0
  4606.6    0.12       0  4947.1    0.07       0  4984.2    0.05       0
  4988.2    0.07       0  5013.7    0.12       0  5069.4    0.07       0
  5303.9    0.12       0
Bank Sta=4984.2,4988.2
Exp/Cntr=0.3,0.1

Type RM Length L Ch R = 1,1874,280,280,280
BEGIN DESCRIPTION:
X19064
END DESCRIPTION:
XS GIS Cut Line= 2
      2334555.23     13699983.17      2334072.49     13699514.82
#Sta/Elev= 30
  4688.3  491.78  4743.8  487.44  4750.8  487.32  4765.0  485.60  4828.5  480.24
  4871.0  475.89  4913.4  472.70  4927.5  472.33  4963.0  472.63  4970.0  471.46
  4977.2  471.30  4984.1  468.99  4991.3  468.12  4998.3  466.33  5010.4  465.09
  5010.7  464.59  5014.2  464.59  5014.4  465.09  5026.6  470.82  5040.7  473.05
  5062.0  475.45  5132.8  478.75  5168.0  479.55  5189.4  480.60  5238.8  481.19
  5245.9  481.90  5288.2  482.85  5302.3  483.46  5309.5  484.30  5360.9  485.86
#Mann=3,-1,0
  4688.3    0.12       0  5010.4    0.05       0  5014.4    0.12       0
Bank Sta=5010.4,5014.4
Exp/Cntr=0.3,0.1

Type RM Length L Ch R = 1,1594,299,299,299
BEGIN DESCRIPTION:
X19063
END DESCRIPTION:
XS GIS Cut Line= 2
      2334799.69     13699839.40      2334263.61     13699330.02
#Sta/Elev= 30
  4653.7  484.12  4667.2  484.66  4674.1  484.04  4738.0  483.07  4773.2  481.65
  4780.5  481.91  4801.5  480.80  4808.8  480.99  4879.5  477.27  4894.4  476.08
  4957.2  469.29  4964.1  467.76  4971.4  467.01  4985.5  464.54  4990.4  462.68
  4990.7  462.18  4994.2  462.18  4994.4  462.68  4999.7  464.11  5006.6  469.17
  5020.7  471.60  5032.9  471.84  5049.1  471.12  5091.5  471.13  5169.6  475.10
  5254.1  476.79  5268.3  476.32  5367.4  476.37  5388.8  476.86  5393.2  476.52
#Mann=5,-1,0
  4653.7    0.12       0  4894.4    0.07       0  4990.4    0.05       0
  4994.4    0.07       0  5032.9    0.12       0
Bank Sta=4990.4,4994.4
Exp/Cntr=0.3,0.1

Type RM Length L Ch R = 1,1295,373,373,373
BEGIN DESCRIPTION:
X19062
END DESCRIPTION:
XS GIS Cut Line= 3
      2334972.24     13699666.84      2334752.46     13699399.82
      2334265.59     13699200.55
#Sta/Elev= 30
  4723.9  472.77  4758.8  471.69  4865.7  471.25  4886.5  471.61  4929.5  470.61
  4950.3  471.45  4964.7  471.03  4979.0  469.15  4988.3  464.77  4997.8  461.48
  4998.1  460.98  5001.6  460.98  5001.8  461.48  5007.7  463.84  5014.2  465.33
  5028.5  466.00  5042.9  467.87  5057.2  468.45  5063.7  469.38  5088.6  470.21
  5130.9  470.36  5185.8  469.02  5201.7  469.31  5261.5  472.29  5315.5  473.70
  5326.3  473.07  5380.3  473.06  5531.6  474.89  5575.5  474.21  5595.8  474.73
#Mann=5,-1,0
  4723.9    0.12       0  4988.3    0.07       0  4997.8    0.05       0
  5001.8    0.07       0  5130.9    0.12       0
Bank Sta=4997.8,5001.8
Exp/Cntr=0.3,0.1

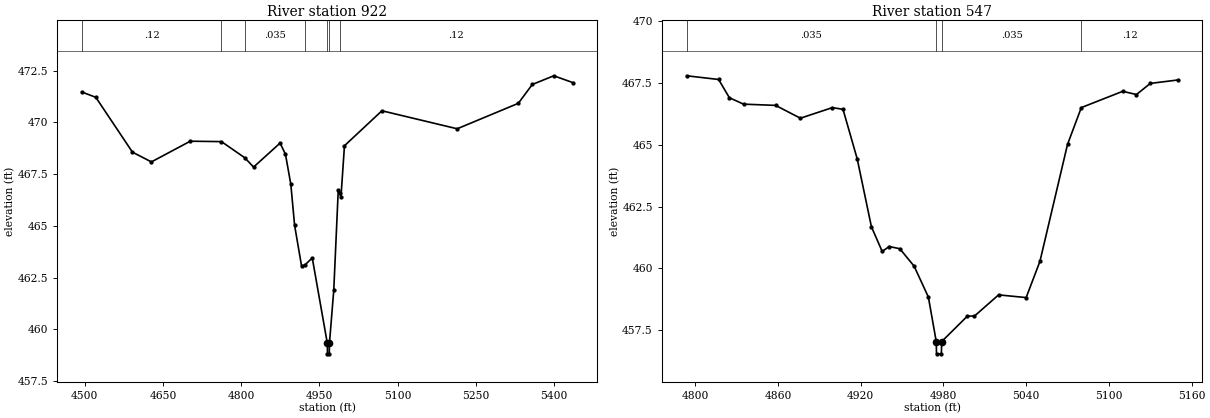
Type RM Length L Ch R = 1,922,375,375,375
BEGIN DESCRIPTION:
X19061
END DESCRIPTION:
XS GIS Cut Line= 3
      2335033.88     13699500.48      2334929.11     13699214.94
      2334309.41     13699065.15
#Sta/Elev= 30
  4494.2  471.47  4521.3  471.21  4591.6  468.56  4627.9  468.09  4702.4  469.09
  4762.2  469.07  4806.9  468.29  4823.8  467.84  4874.6  469.00  4884.9  468.46
  4895.2  467.00  4902.4  465.03  4915.7  463.07  4921.6  463.10  4936.3  463.45
  4965.2  459.32  4965.4  458.82  4968.9  458.82  4969.2  459.32  4977.5  461.90
  4986.1  466.73  4988.6  466.57  4991.3  466.40  4998.0  468.87  5069.8  470.56
  5214.1  469.69  5331.3  470.92  5358.1  471.83  5399.3  472.25  5435.9  471.92
#Mann=7,-1,0
  4494.2    0.12       0  4762.2    0.07       0  4806.9   0.035       0
  4921.6    0.07       0  4965.2    0.05       0  4969.2    0.07       0
  4988.6    0.12       0
Bank Sta=4965.2,4969.2
Exp/Cntr=0.3,0.1

Type RM Length L Ch R = 1,547,0,0,0
BEGIN DESCRIPTION:
DUKES HOLLOW CREEK 1.0
END DESCRIPTION:
XS GIS Cut Line= 3
      2335125.03     13698975.01      2334925.00     13698925.00
      2334774.99     13698925.00
#Sta/Elev= 30
  4793.8  467.80  4817.0  467.65  4824.8  466.91  4835.1  466.65  4858.3  466.60
  4876.3  466.08  4899.5  466.51  4907.2  466.44  4917.5  464.43  4927.8  461.68
  4935.6  460.68  4940.7  460.88  4948.4  460.79  4958.8  460.08  4969.1  458.83
  4974.8  457.03  4975.0  456.53  4978.5  456.53  4978.8  457.03  4997.4  458.06
  5002.5  458.06  5020.0  458.92  5040.0  458.81  5050.0  460.28  5070.0  465.02
  5080.0  466.51  5110.0  467.17  5120.0  467.04  5130.0  467.49  5150.0  467.63
#Mann=4,-1,0
  4793.8   0.035       0  4974.8   0.035       0  4978.8   0.035       0
  5080.0    0.12       0
Bank Sta=4974.8,4978.8
Exp/Cntr=0.3,0.1

Chan Stop Cuts=-1