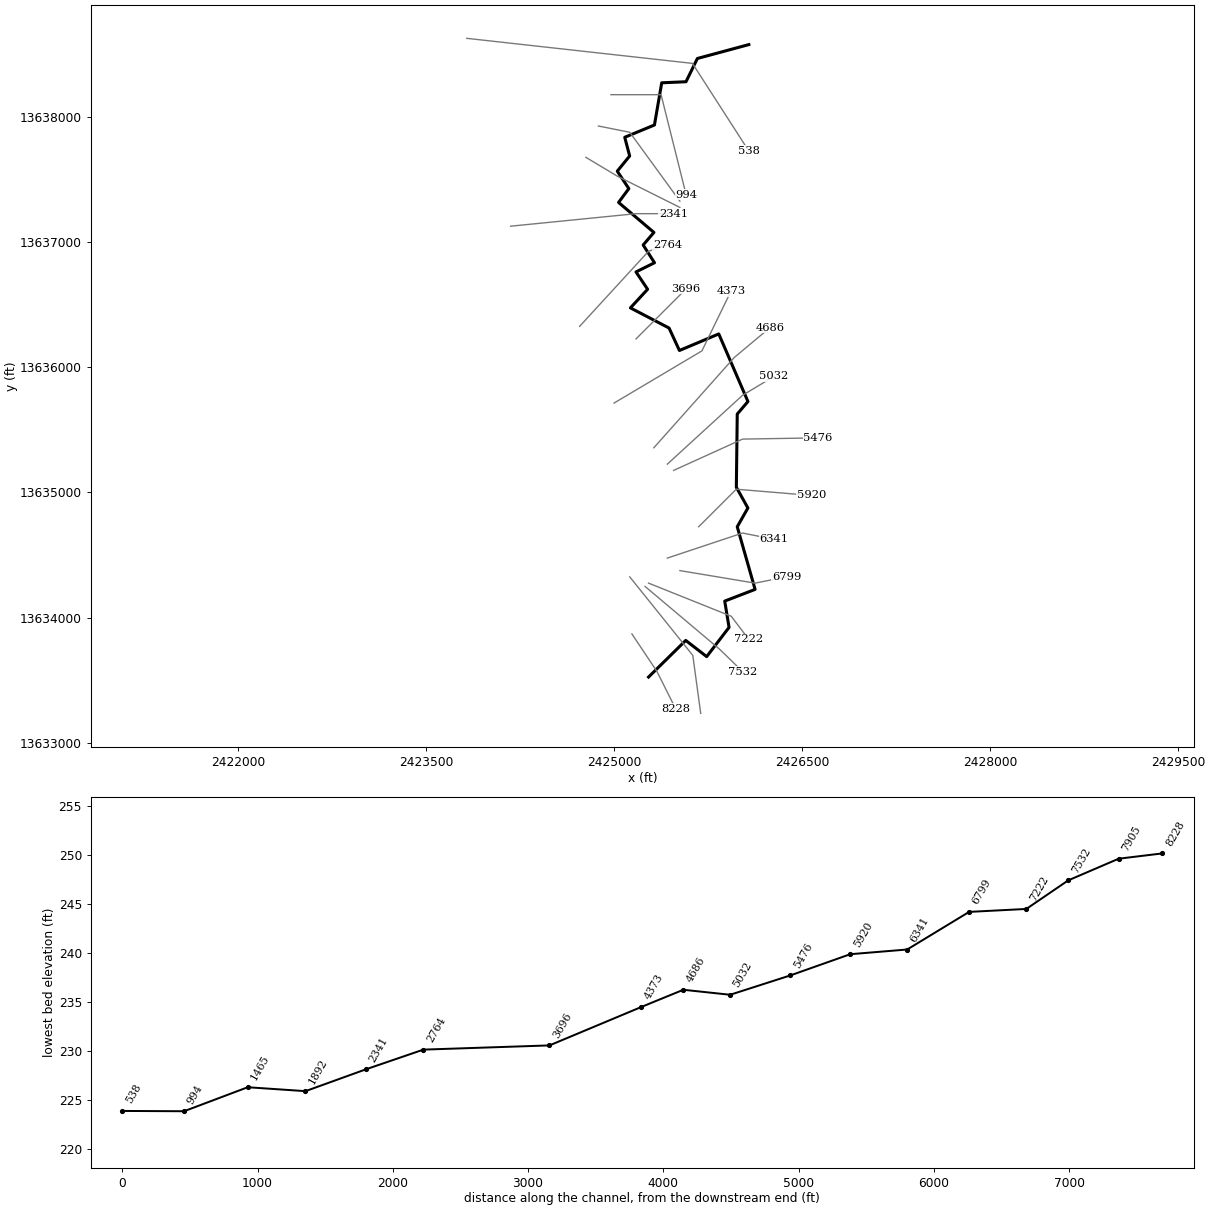
--- DYKES CREEK.prj (project) ---

Proj Title=DYKES CREEK Base Level Engineering
Current Plan=p01
Default Exp/Contr=0.3,0.1
English Units
Geom File=g01
Flow File=f01
Plan File=p01
BEGIN DESCRIPTION:
DYKES CREEK
END DESCRIPTION:

--- DYKES CREEK.p01 (plan) ---

Plan Title=Multiple Run
Short Identifier=Multiple
Geom File=g01
Flow File=f01
Subcritical Flow
K Sum by GR= 0
Std Step Tol= 0.01
Critical Tol= 0.01
Num of Std Step Trials= 20
Max Error Tol= 0.3
Flow Tol Ratio= 0.001
Split Flow NTrial= 30
Split Flow Tol= 0.02
Split Flow Ratio= 0.02
Log Output Level= 0
Friction Slope Method= 1
Unsteady Friction Slope Method= 2
Unsteady Bridges Friction Slope Method= 1
Parabolic Critical Depth
Global Vel Dist=  1 , 1 , 1
Global Log Level= 0
CheckData=True
Encroach Param= -1, 0, 0, 0
BEGIN DESCRIPTION:
Multiple Run
END DESCRIPTION:

--- DYKES CREEK.f01 (steady flow) ---

Flow Title=Multiple
Number of Profiles=7
Profile Names=10-year,25-year,50-year,1pct_min,100-year,1pct_plu,500-year
River Rch & RM= DYKES CREEK,Reach-1,8228
     352     547     717     456     909    1814    1448
River Rch & RM= DYKES CREEK,Reach-1,6799
     595     951    1270     820    1637    3265    2695
Boundary for River Rch & Prof#=DYKES CREEK,Reach-1,1
Up Type=0
Dn Type=3
Dn Slope=0.005
Boundary for River Rch & Prof#=DYKES CREEK,Reach-1,2
Up Type=0
Dn Type=3
Dn Slope=0.005
Boundary for River Rch & Prof#=DYKES CREEK,Reach-1,3
Up Type=0
Dn Type=3
Dn Slope=0.005
Boundary for River Rch & Prof#=DYKES CREEK,Reach-1,4
Up Type=0
Dn Type=3
Dn Slope=0.005
Boundary for River Rch & Prof#=DYKES CREEK,Reach-1,5
Up Type=0
Dn Type=3
Dn Slope=0.005
Boundary for River Rch & Prof#=DYKES CREEK,Reach-1,6
Up Type=0
Dn Type=3
Dn Slope=0.005
Boundary for River Rch & Prof#=DYKES CREEK,Reach-1,7
Up Type=0
Dn Type=3
Dn Slope=0.005

--- DYKES CREEK.g01 (geometry) ---

Geom Title=Existing Conditions

River Reach=DYKES CREEK,Reach-1
Reach XY= 30
      2425275.00     13633525.00      2425571.65     13633817.42
      2425738.68     13633688.26      2425917.21     13633921.58
      2425882.69     13634131.48      2426125.00     13634225.00
      2425982.53     13634725.01      2426067.50     13634875.00
      2425975.37     13635040.27      2425982.57     13635625.00
      2426067.88     13635725.00      2425835.16     13636264.72
      2425521.38     13636132.48      2425438.73     13636311.80
      2425130.37     13636472.64      2425267.52     13636621.38
      2425174.84     13636759.78      2425322.54     13636833.17
      2425232.11     13636975.00      2425317.96     13637075.20
      2425035.83     13637314.68      2425117.89     13637425.00
      2425025.56     13637564.36      2425124.39     13637685.63
      2425085.06     13637835.00      2425322.07     13637932.97
      2425380.08     13638269.97      2425573.78     13638278.44
      2425664.57     13638464.06      2426075.00     13638575.00

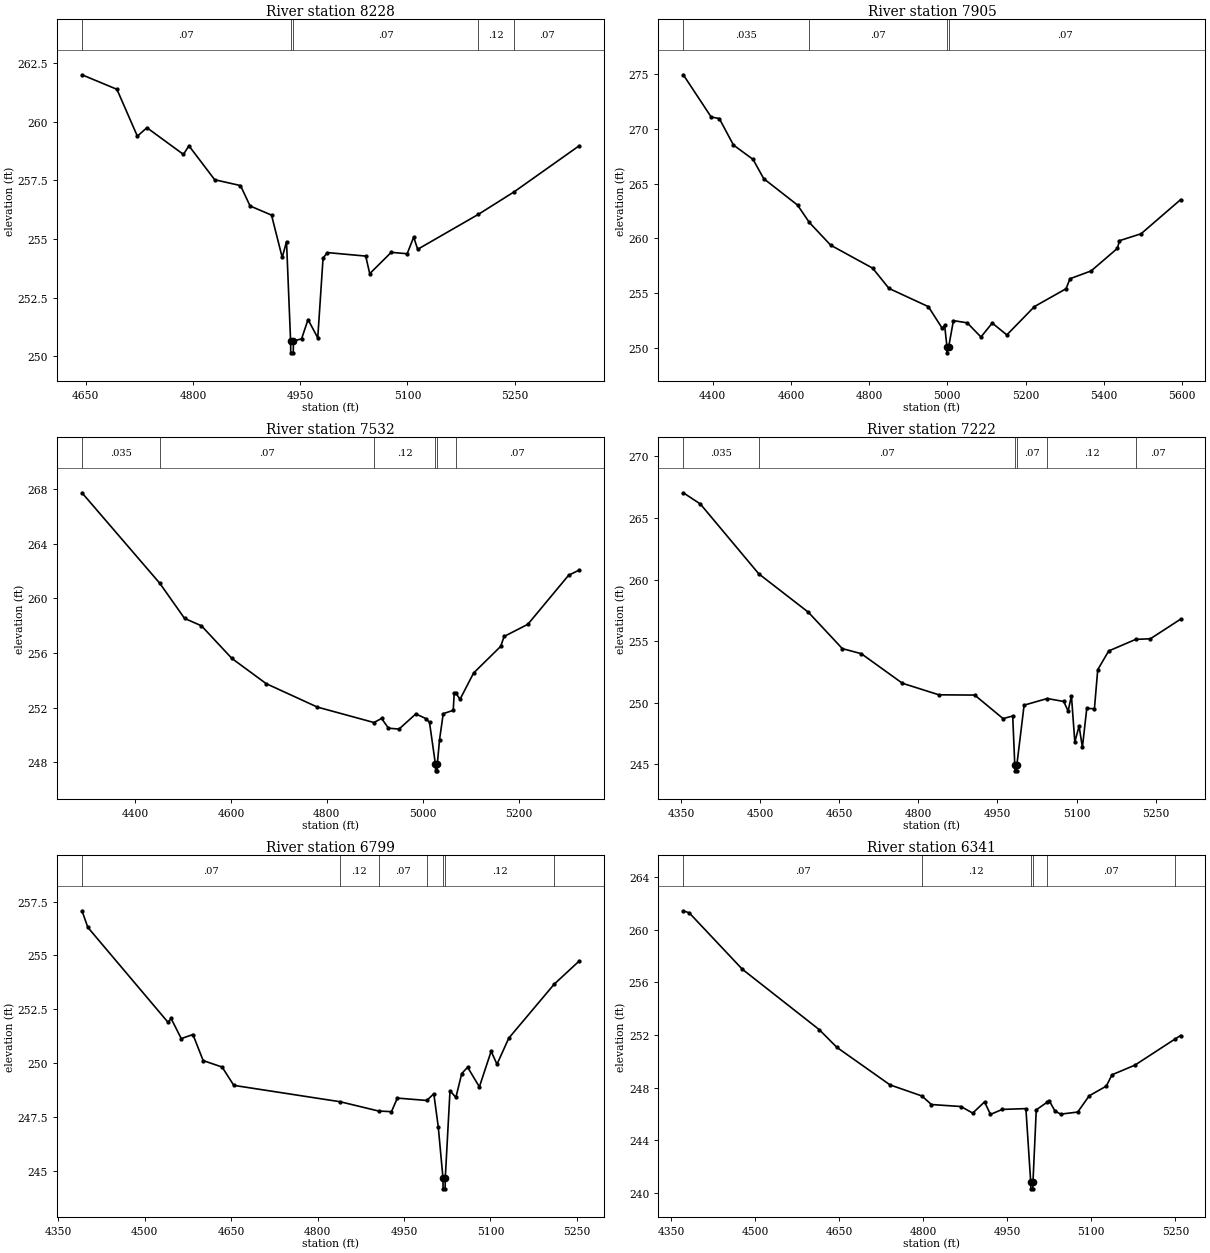
Type RM Length L Ch R = 1,8228,323,323,323
BEGIN DESCRIPTION:
DYKES CREEK 17.0
END DESCRIPTION:
XS GIS Cut Line= 3
      2425142.13     13633869.52      2425342.12     13633569.52
      2425492.01     13633269.75
#Sta/Elev= 30
  4644.6  262.01  4693.5  261.39  4722.1  259.39  4735.5  259.75  4786.6  258.61
  4794.2  258.98  4830.3  257.53  4866.4  257.28  4879.8  256.41  4909.8  256.02
  4924.8  254.21  4930.8  254.89  4936.5  250.64  4936.7  250.14  4940.2  250.14
  4940.5  250.64  4951.9  250.74  4960.9  251.56  4974.5  250.78  4981.9  254.18
  4987.9  254.42  5041.6  254.27  5047.2  253.52  5077.3  254.43  5099.6  254.37
  5108.7  255.08  5114.3  254.56  5199.1  256.05  5249.1  257.01  5340.3  258.98
#Mann=5,-1,0
  4644.6    0.07       0  4936.5    0.05       0  4940.5    0.07       0
  5199.1    0.12       0  5249.1    0.07       0
Bank Sta=4936.5,4940.5
Exp/Cntr=0.3,0.1

Type RM Length L Ch R = 1,7905,373,373,373
BEGIN DESCRIPTION:
DYKES CREEK 16.0
END DESCRIPTION:
XS GIS Cut Line= 3
      2425125.02     13634324.98      2425628.02     13633698.01
      2425691.04     13633234.99
#Sta/Elev= 30
  4325.0  274.89  4396.2  271.05  4417.0  270.91  4453.2  268.50  4503.4  267.19
  4530.6  265.44  4617.0  263.04  4647.1  261.46  4701.8  259.39  4809.1  257.30
  4850.7  255.46  4951.5  253.80  4986.7  251.84  4993.1  252.09  4999.1  250.10
  4999.3  249.60  5003.1  250.10  5015.5  252.53  5050.7  252.33  5085.9  251.04
  5114.7  252.31  5152.0  251.23  5222.7  253.81  5303.4  255.43  5313.5  256.34
  5367.5  257.05  5434.6  259.10  5439.9  259.80  5495.2  260.43  5596.1  263.53
#Mann=4,-1,0
  4325.0   0.035       0  4647.1    0.07       0  4999.1    0.05       0
  5003.1    0.07       0
Bank Sta=4999.1,5003.1
Exp/Cntr=0.3,0.1

Type RM Length L Ch R = 1,7532,310,310,310
BEGIN DESCRIPTION:
X19080
END DESCRIPTION:
XS GIS Cut Line= 3
      2425247.22     13634248.67      2425841.72     13633747.32
      2426028.02     13633566.50
#Sta/Elev= 30
  4289.2  267.71  4451.7  261.09  4503.2  258.53  4538.4  257.99  4602.1  255.60
  4673.6  253.76  4780.2  252.05  4898.4  250.92  4914.2  251.22  4928.5  250.51
  4950.5  250.44  4985.7  251.55  5006.5  251.21  5014.2  250.93  5026.5  247.89
  5026.8  247.39  5030.3  247.39  5030.5  247.89  5035.1  249.65  5042.8  251.57
  5063.7  251.81  5065.8  253.09  5068.7  253.09  5077.9  252.62  5106.2  254.54
  5162.8  256.49  5169.8  257.21  5219.4  258.10  5304.3  261.68  5326.5  262.06
#Mann=6,-1,0
  4289.2   0.035       0  4451.7    0.07       0  4898.4    0.12       0
  5026.5    0.05       0  5030.5    0.12       0  5068.7    0.07       0
Bank Sta=5026.5,5030.5
Exp/Cntr=0.3,0.1

Type RM Length L Ch R = 1,7222,423,423,423
BEGIN DESCRIPTION:
DYKES CREEK 15.0
END DESCRIPTION:
XS GIS Cut Line= 3
      2425274.99     13634275.01      2425934.87     13634010.33
      2426074.98     13633825.02
#Sta/Elev= 30
  4354.0  267.04  4386.3  266.13  4497.2  260.46  4591.1  257.35  4655.7  254.39
  4691.6  253.98  4769.6  251.58  4838.9  250.64  4906.8  250.62  4960.6  248.71
  4978.9  248.92  4982.8  244.97  4983.1  244.47  4986.6  244.47  4986.8  244.97
  5000.5  249.80  5044.4  250.34  5075.7  250.10  5084.0  249.32  5090.3  250.56
  5096.7  246.81  5104.8  248.10  5111.1  246.38  5119.4  249.54  5133.9  249.51
  5140.2  252.68  5161.0  254.20  5212.2  255.14  5240.1  255.19  5297.3  256.78
#Mann=6,-1,0
  4354.0   0.035       0  4497.2    0.07       0  4982.8    0.05       0
  4986.8    0.07       0  5044.4    0.12       0  5212.2    0.07       0
Bank Sta=4982.8,4986.8
Exp/Cntr=0.3,0.1

Type RM Length L Ch R = 1,6799,458,458,458
BEGIN DESCRIPTION:
DYKES CREEK 14.0
END DESCRIPTION:
XS GIS Cut Line= 3
      2425524.98     13634375.00      2426125.00     13634275.00
      2426374.96     13634324.99
#Sta/Elev= 30
  4391.0  257.07  4401.2  256.30  4540.6  251.89  4545.6  252.08  4563.4  251.14
  4583.6  251.33  4601.4  250.12  4634.3  249.82  4654.6  248.97  4839.4  248.21
  4905.9  247.78  4928.3  247.75  4938.5  248.38  4989.5  248.27  5001.8  248.58
  5009.5  247.05  5017.7  244.67  5017.9  244.17  5021.4  244.17  5021.7  244.67
  5029.9  248.72  5040.1  248.41  5050.3  249.52  5060.5  249.81  5080.9  248.90
  5101.3  250.55  5111.5  249.95  5131.9  251.16  5210.6  253.66  5254.2  254.74
#Mann=7,-1,0
  4391.0    0.07       0  4839.4    0.12       0  4905.9    0.07       0
  4989.5    0.12       0  5017.7    0.05       0  5021.7    0.12       0
  5210.6    0.07       0
Bank Sta=5017.7,5021.7
Exp/Cntr=0.3,0.1

Type RM Length L Ch R = 1,6341,421,421,421
BEGIN DESCRIPTION:
DYKES CREEK 13.0
END DESCRIPTION:
XS GIS Cut Line= 3
      2425424.97     13634474.99      2426025.00     13634675.00
      2426274.96     13634625.01
#Sta/Elev= 30
  4371.8  261.44  4382.4  261.28  4477.2  257.00  4614.3  252.42  4645.9  251.07
  4740.8  248.22  4797.6  247.38  4814.6  246.73  4867.3  246.58  4888.3  246.08
  4909.4  246.93  4920.0  245.98  4941.0  246.36  4983.2  246.42  4991.8  240.83
  4992.0  240.33  4995.5  240.33  4995.8  240.83  5001.7  246.33  5020.6  246.89
  5024.7  247.03  5034.9  246.25  5045.1  246.00  5075.7  246.16  5096.1  247.39
  5126.7  248.13  5136.9  248.99  5177.7  249.72  5249.6  251.71  5259.2  251.97
#Mann=6,-1,0
  4371.8    0.07       0  4797.6    0.12       0  4991.8    0.05       0
  4995.8    0.12       0  5020.6    0.07       0  5249.6    0.12       0
Bank Sta=4991.8,4995.8
Exp/Cntr=0.3,0.1

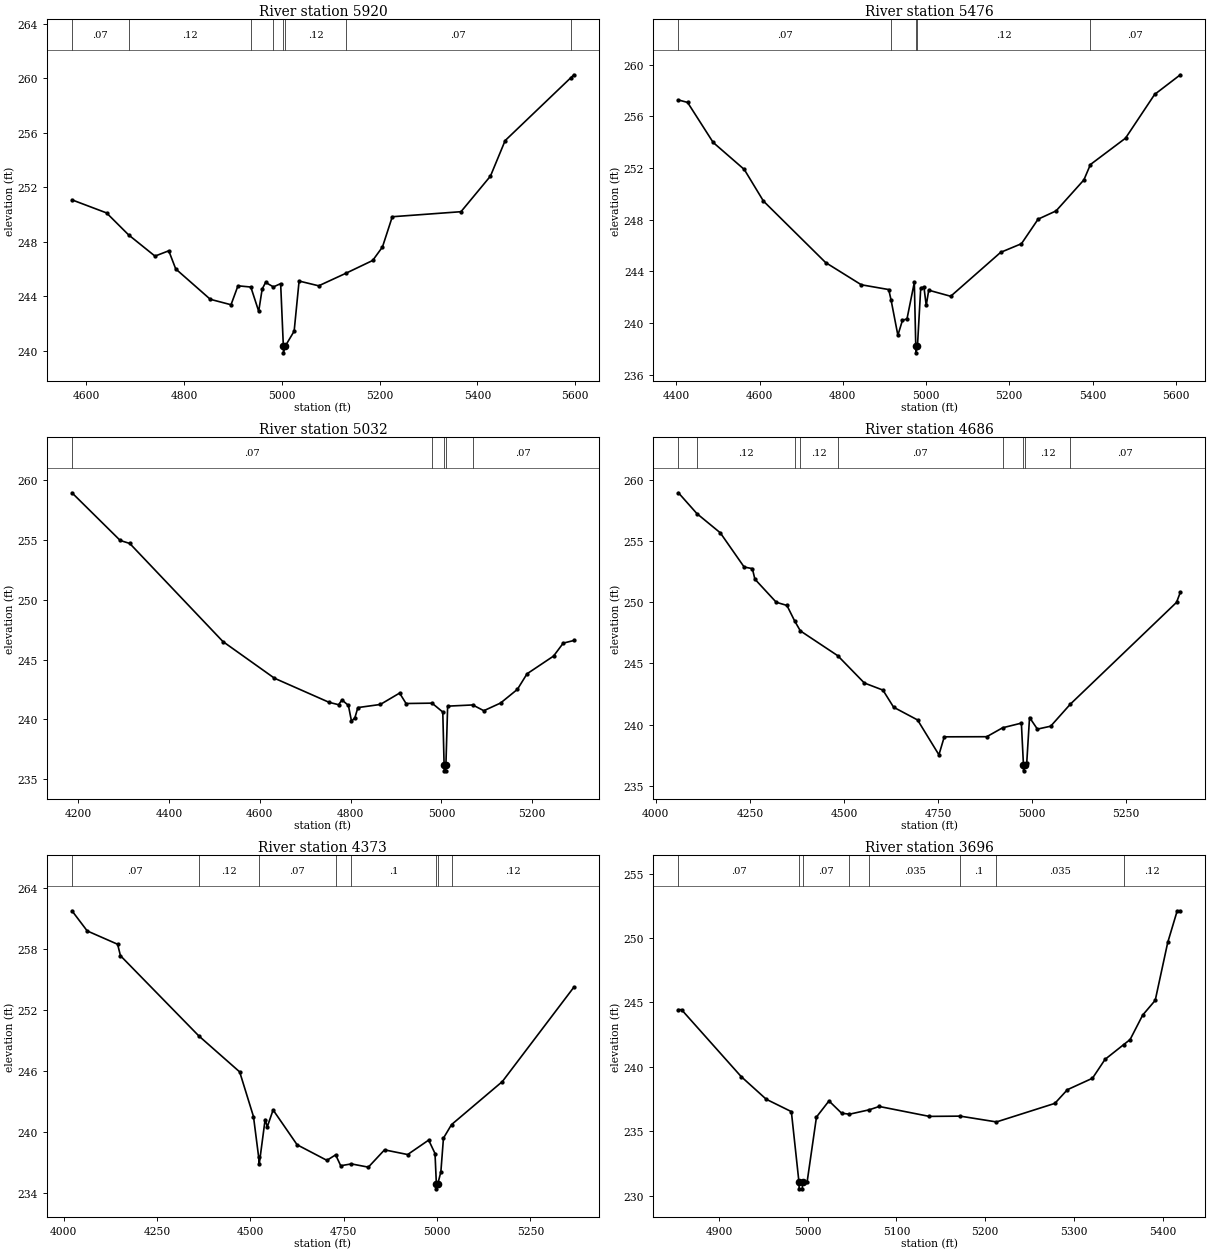
Type RM Length L Ch R = 1,5920,444,444,444
BEGIN DESCRIPTION:
DYKES CREEK 12.0
END DESCRIPTION:
XS GIS Cut Line= 3
      2425674.97     13634724.97      2425975.00     13635025.00
      2426575.01     13634975.00
#Sta/Elev= 30
  4571.0  251.08  4641.8  250.12  4686.8  248.51  4740.8  246.95  4769.0  247.34
  4783.2  246.01  4853.9  243.78  4896.3  243.38  4910.5  244.77  4936.8  244.68
  4952.9  242.90  4960.0  244.53  4967.0  245.02  4983.0  244.69  4997.8  244.93
  5003.3  240.35  5003.6  239.85  5007.3  240.35  5025.4  241.44  5035.5  245.12
  5075.6  244.77  5131.2  245.69  5186.0  246.63  5206.0  247.62  5226.1  249.84
  5366.6  250.21  5426.8  252.82  5456.9  255.43  5591.4  260.05  5597.4  260.26
#Mann=8,-1,0
  4571.0    0.07       0  4686.8    0.12       0  4936.8    0.07       0
  4983.0    0.12       0  5003.3    0.05       0  5007.3    0.12       0
  5131.2    0.07       0  5591.4    0.12       0
Bank Sta=5003.3,5007.3
Exp/Cntr=0.3,0.1

Type RM Length L Ch R = 1,5476,444,444,444
BEGIN DESCRIPTION:
DYKES CREEK 11.0
END DESCRIPTION:
XS GIS Cut Line= 3
      2425474.98     13635174.99      2426025.00     13635425.00
      2426626.65     13635434.98
#Sta/Elev= 30
  4405.0  257.26  4427.0  257.07  4488.5  253.97  4563.2  251.88  4609.3  249.43
  4758.7  244.67  4844.4  242.95  4910.3  242.58  4916.0  241.76  4932.3  239.04
  4943.3  240.20  4954.2  240.31  4971.8  243.13  4975.3  238.18  4975.6  237.68
  4979.3  238.18  4987.2  242.71  4994.9  242.77  5000.4  241.35  5006.4  242.53
  5059.2  242.06  5179.2  245.46  5229.2  246.13  5269.2  248.03  5312.4  248.67
  5379.2  251.07  5394.9  252.26  5479.2  254.30  5549.2  257.69  5610.9  259.21
#Mann=5,-1,0
  4405.0    0.07       0  4916.0    0.12       0  4975.3    0.05       0
  4979.3    0.12       0  5394.9    0.07       0
Bank Sta=4975.3,4979.3
Exp/Cntr=0.3,0.1

Type RM Length L Ch R = 1,5032,346,346,346
BEGIN DESCRIPTION:
DYKES CREEK 10.0
END DESCRIPTION:
XS GIS Cut Line= 3
      2425425.02     13635225.02      2426025.00     13635775.00
      2426275.04     13635925.02
#Sta/Elev= 30
  4186.1  258.92  4292.4  254.94  4313.4  254.69  4518.7  246.50  4632.2  243.44
  4752.4  241.43  4773.4  241.23  4780.8  241.63  4795.0  241.17  4801.8  239.86
  4809.2  240.13  4815.9  240.99  4865.3  241.25  4907.8  242.20  4922.0  241.33
  4979.2  241.36  5002.9  240.62  5005.8  236.21  5006.0  235.71  5009.5  235.71
  5009.8  236.21  5013.6  241.11  5068.8  241.21  5093.3  240.73  5130.2  241.37
  5167.2  242.51  5188.5  243.81  5246.9  245.29  5268.2  246.37  5291.6  246.59
#Mann=5,-1,0
  4186.1    0.07       0  4979.2    0.12       0  5005.8    0.05       0
  5009.8    0.12       0  5068.8    0.07       0
Bank Sta=5005.8,5009.8
Exp/Cntr=0.3,0.1

Type RM Length L Ch R = 1,4686,313,313,313
BEGIN DESCRIPTION:
DYKES CREEK 9.0
END DESCRIPTION:
XS GIS Cut Line= 3
      2425317.24     13635355.66      2425958.68     13636076.45
      2426241.55     13636313.28
#Sta/Elev= 30
  4060.1  258.95  4109.5  257.24  4171.3  255.68  4234.8  252.88  4256.6  252.75
  4263.3  251.89  4320.1  250.00  4348.5  249.74  4369.2  248.46  4384.2  247.66
  4483.6  245.63  4554.2  243.40  4603.6  242.82  4632.0  241.42  4695.6  240.38
  4752.4  237.53  4766.6  239.00  4879.5  239.01  4921.6  239.74  4971.5  240.12
  4977.0  236.72  4977.3  236.22  4981.0  236.72  4985.7  236.84  4993.2  240.58
  5014.1  239.63  5049.4  239.87  5101.6  241.67  5383.8  249.99  5393.9  250.81
#Mann=9,-1,0
  4060.1    0.07       0  4109.5    0.12       0  4369.2    0.07       0
  4384.2    0.12       0  4483.6    0.07       0  4921.6    0.12       0
  4977.0    0.05       0  4981.0    0.12       0  5101.6    0.07       0
Bank Sta=4977,4981
Exp/Cntr=0.3,0.1

Type RM Length L Ch R = 1,4373,677,677,677
BEGIN DESCRIPTION:
DYKES CREEK 8.0
END DESCRIPTION:
XS GIS Cut Line= 3
      2424999.80     13635712.74      2425700.77     13636129.36
      2425932.20     13636605.46
#Sta/Elev= 30
  4021.7  261.77  4062.6  259.79  4144.1  258.48  4151.6  257.36  4361.8  249.47
  4471.1  245.94  4508.1  241.55  4521.8  237.62  4523.7  236.92  4539.3  241.26
  4545.1  240.55  4560.7  242.20  4625.0  238.78  4704.8  237.25  4728.2  237.79
  4741.8  236.72  4770.4  236.90  4815.9  236.58  4859.2  238.28  4921.2  237.82
  4977.5  239.24  4994.5  237.92  4998.1  234.95  4998.3  234.45  5002.1  234.95
  5010.2  236.13  5017.1  239.43  5038.7  240.76  5174.9  244.99  5366.5  254.26
#Mann=8,-1,0
  4021.7    0.07       0  4361.8    0.12       0  4521.8    0.07       0
  4728.2    0.12       0  4770.4     0.1       0  4998.1    0.05       0
  5002.1     0.1       0  5038.7    0.12       0
Bank Sta=4998.1,5002.1
Exp/Cntr=0.3,0.1

Type RM Length L Ch R = 1,3696,932,932,932
BEGIN DESCRIPTION:
DYKES CREEK 7.0
END DESCRIPTION:
XS GIS Cut Line= 3
      2425175.00     13636225.00      2425275.00     13636325.00
      2425575.01     13636625.01
#Sta/Elev= 30
  4854.3  244.44  4857.8  244.44  4925.0  239.25  4953.3  237.49  4981.6  236.53
  4990.2  231.04  4990.4  230.54  4993.9  230.54  4994.2  231.04  4999.3  231.04
  5009.9  236.11  5024.0  237.36  5038.2  236.41  5047.1  236.33  5069.3  236.67
  5080.6  236.93  5137.1  236.16  5171.9  236.18  5212.8  235.73  5278.6  237.17
  5292.7  238.23  5321.0  239.12  5335.1  240.58  5356.2  241.73  5363.4  242.12
  5377.6  244.02  5391.7  245.16  5405.8  249.65  5416.5  252.11  5420.0  252.11
#Mann=8,-1,0
  4854.3    0.07       0  4990.2    0.05       0  4994.2    0.07       0
  5047.1     0.1       0  5069.3   0.035       0  5171.9     0.1       0
  5212.8   0.035       0  5356.2    0.12       0
Bank Sta=4990.2,4994.2
Exp/Cntr=0.3,0.1

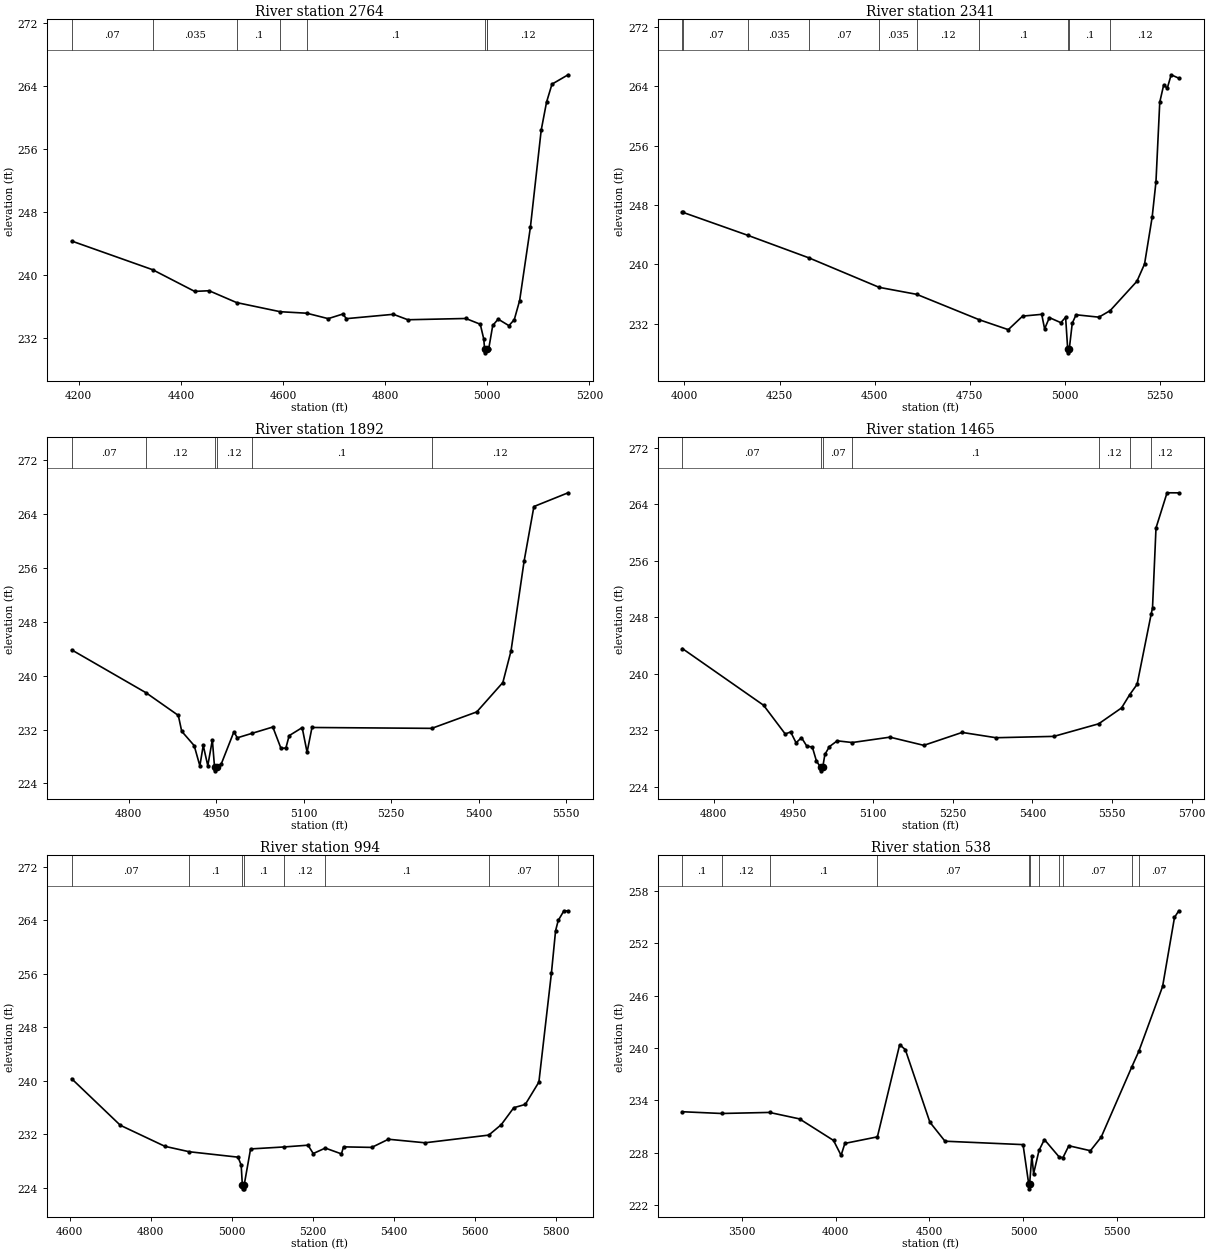
Type RM Length L Ch R = 1,2764,423,423,423
BEGIN DESCRIPTION:
DYKES CREEK 6.0
END DESCRIPTION:
XS GIS Cut Line= 3
      2424724.97     13636324.96      2425275.00     13636925.00
      2425425.00     13636975.00
#Sta/Elev= 30
  4186.1  244.30  4344.6  240.66  4426.9  237.91  4455.3  237.99  4509.0  236.49
  4594.4  235.33  4646.3  235.14  4688.4  234.45  4716.8  235.03  4724.2  234.45
  4816.0  235.00  4844.4  234.31  4957.9  234.47  4986.2  233.74  4993.0  231.87
  4994.7  230.61  4994.9  230.11  4998.7  230.61  4999.4  230.61  5002.7  230.61
  5010.6  233.58  5021.2  234.39  5042.3  233.56  5052.8  234.32  5063.3  236.75
  5084.4  246.07  5105.5  258.37  5116.0  261.93  5126.6  264.21  5158.2  265.40
#Mann=8,-1,0
  4186.1    0.07       0  4344.6   0.035       0  4509.0     0.1       0
  4594.4    0.07       0  4646.3     0.1       0  4994.7    0.05       0
  4998.7     0.1       0  4999.4    0.12       0
Bank Sta=4994.7,4998.7
Exp/Cntr=0.3,0.1

Type RM Length L Ch R = 1,2341,449,449,449
BEGIN DESCRIPTION:
DYKES CREEK 5.0
END DESCRIPTION:
XS GIS Cut Line= 3
      2424174.96     13637125.00      2425175.00     13637225.00
      2425474.97     13637225.00
#Sta/Elev= 30
  3994.4  247.02  3995.9  247.01  4167.6  243.90  4327.5  240.88  4511.9  236.92
  4610.5  235.98  4775.0  232.56  4851.2  231.23  4888.9  233.05  4939.1  233.29
  4946.7  231.33  4959.2  232.85  4989.4  232.17  5001.9  232.90  5007.4  228.61
  5007.6  228.11  5011.5  228.61  5019.4  232.10  5029.4  233.23  5089.4  232.91
  5119.0  233.79  5189.4  237.74  5209.4  240.06  5229.4  246.36  5239.4  251.11
  5249.4  261.84  5259.4  264.08  5269.4  263.76  5279.4  265.52  5299.4  265.06
#Mann=10,-1,0
  3994.4   0.035       0  3995.9    0.07       0  4167.6   0.035       0
  4327.5    0.07       0  4511.9   0.035       0  4610.5    0.12       0
  4775.0     0.1       0  5007.4    0.05       0  5011.5     0.1       0
  5119.0    0.12       0
Bank Sta=5007.4,5011.5
Exp/Cntr=0.3,0.1

Type RM Length L Ch R = 1,1892,427,427,427
BEGIN DESCRIPTION:
DYKES CREEK 4.0
END DESCRIPTION:
XS GIS Cut Line= 3
      2424775.01     13637674.99      2425025.00     13637525.00
      2425524.96     13637275.02
#Sta/Elev= 30
  4702.5  243.81  4829.7  237.46  4885.2  234.09  4891.0  231.74  4912.4  229.61
  4922.1  226.61  4927.9  229.64  4935.7  226.63  4943.5  230.46  4947.3  226.37
  4947.5  225.87  4951.4  226.37  4959.0  226.94  4980.4  231.65  4986.3  230.77
  5011.0  231.42  5047.1  232.37  5061.1  229.20  5069.5  229.26  5075.1  231.09
  5097.4  232.28  5105.8  228.63  5114.2  232.30  5319.4  232.17  5396.5  234.61
  5441.2  238.97  5455.2  243.66  5477.6  256.97  5494.4  265.07  5553.0  267.11
#Mann=6,-1,0
  4702.5    0.07       0  4829.7    0.12       0  4947.3    0.05       0
  4951.4    0.12       0  5011.0     0.1       0  5319.4    0.12       0
Bank Sta=4947.3,4951.4
Exp/Cntr=0.3,0.1

Type RM Length L Ch R = 1,1465,471,471,471
BEGIN DESCRIPTION:
DYKES CREEK 3.0
END DESCRIPTION:
XS GIS Cut Line= 3
      2424874.95     13637925.01      2425125.00     13637875.00
      2425525.02     13637324.98
#Sta/Elev= 30
  4740.7  243.59  4893.7  235.56  4934.5  231.49  4944.7  231.78  4954.9  230.24
  4965.1  230.97  4975.3  229.75  4985.5  229.65  4993.2  227.68  5001.0  226.77
  5001.2  226.27  5005.1  226.77  5009.2  228.59  5017.7  229.70  5032.4  230.52
  5060.8  230.28  5131.7  231.04  5195.5  229.88  5267.7  231.71  5331.5  230.96
  5440.5  231.15  5524.9  232.93  5568.0  235.18  5583.3  237.05  5597.3  238.52
  5623.9  248.51  5626.3  249.33  5632.9  260.67  5653.7  265.65  5675.8  265.64
#Mann=7,-1,0
  4740.7    0.07       0  5001.0    0.05       0  5005.1    0.07       0
  5060.8     0.1       0  5524.9    0.12       0  5583.3    0.07       0
  5623.9    0.12       0
Bank Sta=5001,5005.1
Exp/Cntr=0.3,0.1

Type RM Length L Ch R = 1,994,456,456,456
BEGIN DESCRIPTION:
DYKES CREEK 2.0
END DESCRIPTION:
XS GIS Cut Line= 3
      2424974.98     13638175.00      2425375.00     13638175.00
      2425574.99     13637375.04
#Sta/Elev= 30
  4604.7  240.29  4724.7  233.33  4834.7  230.18  4894.7  229.37  5015.0  228.56
  5022.8  227.38  5025.8  224.32  5026.1  223.82  5029.7  223.82  5030.0  224.32
  5046.0  229.79  5129.5  230.09  5187.7  230.35  5200.6  229.10  5230.3  229.92
  5270.1  229.05  5275.3  230.10  5344.9  230.02  5386.1  231.24  5476.3  230.71
  5633.6  231.86  5664.4  233.42  5695.3  235.96  5723.7  236.45  5757.2  239.79
  5788.1  256.08  5798.4  262.44  5804.9  263.97  5819.0  265.42  5829.3  265.40
#Mann=8,-1,0
  4604.7    0.07       0  4894.7     0.1       0  5025.8    0.05       0
  5030.0     0.1       0  5129.5    0.12       0  5230.3     0.1       0
  5633.6    0.07       0  5804.9    0.12       0
Bank Sta=5025.8,5030
Exp/Cntr=0.3,0.1

Type RM Length L Ch R = 1,538,0,0,0
BEGIN DESCRIPTION:
DYKES CREEK 1.0
END DESCRIPTION:
XS GIS Cut Line= 3
      2423825.01     13638625.00      2425625.00     13638425.00
      2426074.98     13637725.02
#Sta/Elev= 30
  3184.1  232.69  3392.8  232.49  3648.2  232.61  3807.9  231.87  3989.0  229.40
  4029.3  227.69  4049.4  229.06  4222.6  229.81  4341.2  240.38  4371.3  239.81
  4502.1  231.49  4582.6  229.31  4998.1  228.92  5028.7  224.35  5029.0  223.85
  5032.9  224.35  5045.0  227.67  5054.3  225.59  5083.0  228.25  5111.7  229.50
  5190.9  227.49  5210.7  227.43  5241.8  228.79  5356.8  228.22  5414.2  229.78
  5578.0  237.87  5614.7  239.63  5741.1  247.05  5804.5  254.97  5827.3  255.73
#Mann=11,-1,0
  3184.1     0.1       0  3392.8    0.12       0  3648.2     0.1       0
  4222.6    0.07       0  5028.7    0.05       0  5032.9    0.07       0
  5083.0     0.1       0  5190.9    0.12       0  5210.7    0.07       0
  5578.0     0.1       0  5614.7    0.07       0
Bank Sta=5028.7,5032.9
Exp/Cntr=0.3,0.1

Chan Stop Cuts=-1