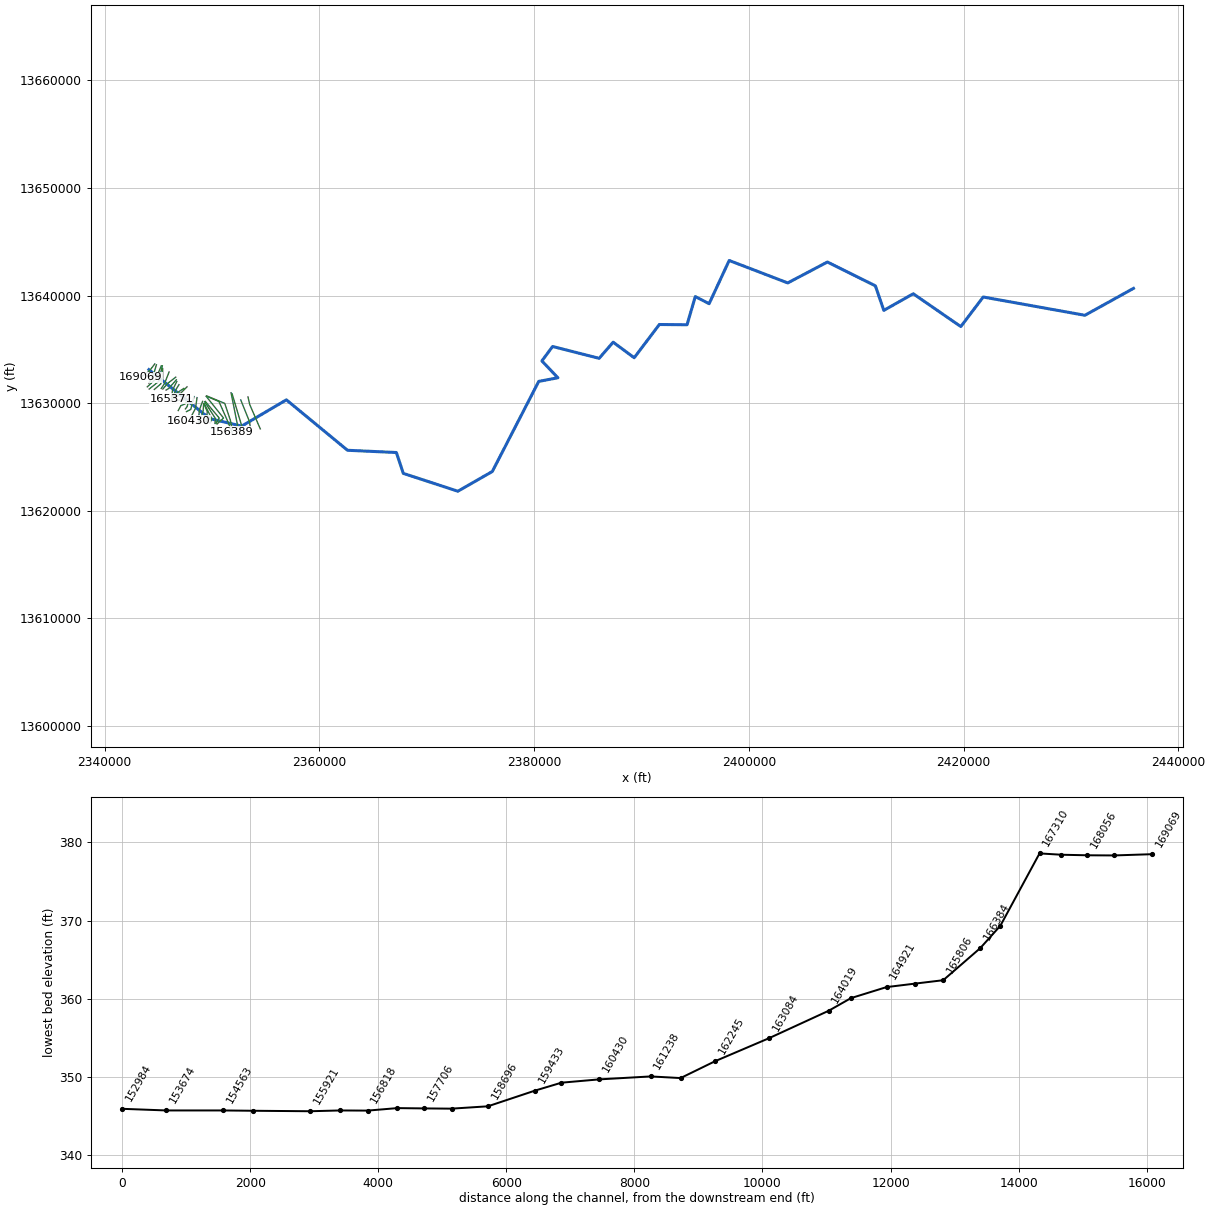
--- ELM CREEK.prj (project) ---

Proj Title=ELM CREEK Base Level Engineering
Current Plan=p01
Default Exp/Contr=0.3,0.1
English Units
Geom File=g01
Flow File=f01
Plan File=p01
Y Axis Title=Elevation
X Axis Title(PF)=Main Channel Distance
X Axis Title(XS)=Station
BEGIN DESCRIPTION:
ELM CREEK
END DESCRIPTION:
DSS Export Rating Curves= 0
DSS Export Rating Curve Sorted= 0
DSS Export Volume Flow Curves= 0
DXF OffsetX= 0
DXF OffsetY= 0
DXF ScaleX= 1
DXF ScaleY= 10

--- ELM CREEK.p01 (plan) ---

Plan Title=Multiple Run
Short Identifier=Multiple
Geom File=g01
Flow File=f01
Subcritical Flow
K Sum by GR= 0
Std Step Tol= 0.01
Critical Tol= 0.01
Num of Std Step Trials= 20
Max Error Tol= 0.3
Flow Tol Ratio= 0.001
Split Flow NTrial= 30
Split Flow Tol= 0.02
Split Flow Ratio= 0.02
Log Output Level= 0
Friction Slope Method= 1
Unsteady Friction Slope Method= 2
Unsteady Bridges Friction Slope Method= 1
Parabolic Critical Depth
Global Vel Dist=  1 , 1 , 1
Global Log Level= 0
CheckData=True
Encroach Param= -1, 0, 0, 0
BEGIN DESCRIPTION:
Multiple Run
END DESCRIPTION:

--- ELM CREEK.f01 (steady flow) ---

Flow Title=Multiple
Number of Profiles=7
Profile Names=10-year,25-year,50-year,1pct_min,100-year,1pct_plu,500-year
River Rch & RM= ELM CREEK,Reach-1,169069
     710    1156    1561    1020    2035    4061    3430
River Rch & RM= ELM CREEK,Reach-1,165371
     838    1379    1875    1232    2458    4905    4195
River Rch & RM= ELM CREEK,Reach-1,162245
    1096    1814    2475    1630    3253    6490    5577
River Rch & RM= ELM CREEK,Reach-1,157282
    1276    2125    2912    1925    3842    7666    6638
River Rch & RM= ELM CREEK,Reach-1,155028
    2129    3626    5044    3381    6746   13461   11978
River Rch & RM= ELM CREEK,Reach-1,150453
    2413    4140    5788    3899    7779   15522   13949
River Rch & RM= ELM CREEK,Reach-1,146963
    2349    4000    5564    3728    7438   14840   13190
River Rch & RM= ELM CREEK,Reach-1,137147
    3559    6144    8628    5828   11629   23203   20966
River Rch & RM= ELM CREEK,Reach-1,132509
    4921    8558   12079    8194   16349   32620   29718
River Rch & RM= ELM CREEK,Reach-1,121627
    4999    8694   12271    8324   16608   33138   30185
River Rch & RM= ELM CREEK,Reach-1,118669
    8153   14363   20459   13994   27922   55711   51570
River Rch & RM= ELM CREEK,Reach-1,114841
    7979   14016   19924   13599   27134   54139   49904
River Rch & RM= ELM CREEK,Reach-1,113678
    8143   14304   20334   13879   27691   55252   50924
River Rch & RM= ELM CREEK,Reach-1,109745
    8105   14159   20051   13631   27197   54266   49611
River Rch & RM= ELM CREEK,Reach-1,100465
    8866   15499   21960   14933   29795   59450   54377
River Rch & RM= ELM CREEK,Reach-1,93710
    8737   15215   21501   14581   29092   58046   52797
River Rch & RM= ELM CREEK,Reach-1,86530
    8737   15201   21468   14549   29029   57920   52612
River Rch & RM= ELM CREEK,Reach-1,84360
    8821   15347   21674   14688   29307   58475   53115
River Rch & RM= ELM CREEK,Reach-1,80629
    9286   16102   22695   15348   30623   61101   55241
River Rch & RM= ELM CREEK,Reach-1,71214
    9295   16105   22685   15332   30590   61036   55112
River Rch & RM= ELM CREEK,Reach-1,56785
    9865   17016   23898   16099   32121   64090   57483
River Rch & RM= ELM CREEK,Reach-1,51047
    9612   16494   23083   15492   30910   61674   54903
River Rch & RM= ELM CREEK,Reach-1,36781
    9697   16639   23283   15624   31174   62201   55358
River Rch & RM= ELM CREEK,Reach-1,33566
    9940   17018   23779   15933   31790   63429   56270
River Rch & RM= ELM CREEK,Reach-1,25476
   10331   17700   24744   16587   33095   66033   58629
River Rch & RM= ELM CREEK,Reach-1,19823
   10344   17706   24736   16570   33062   65968   58493
River Rch & RM= ELM CREEK,Reach-1,13215
   10636   18138   25282   16896   33712   67265   59336
River Rch & RM= ELM CREEK,Reach-1,5182
   11462   19559   27278   18239   36391   72610   64101
Boundary for River Rch & Prof#=ELM CREEK,Reach-1,1
Up Type=0
Dn Type=3
Dn Slope=0.0006
Boundary for River Rch & Prof#=ELM CREEK,Reach-1,2
Up Type=0
Dn Type=3
Dn Slope=0.0006
Boundary for River Rch & Prof#=ELM CREEK,Reach-1,3
Up Type=0
Dn Type=3
Dn Slope=0.0006
Boundary for River Rch & Prof#=ELM CREEK,Reach-1,4
Up Type=0
Dn Type=3
Dn Slope=0.0006
Boundary for River Rch & Prof#=ELM CREEK,Reach-1,5
Up Type=0
Dn Type=3
Dn Slope=0.0006
Boundary for River Rch & Prof#=ELM CREEK,Reach-1,6
Up Type=0
Dn Type=3
Dn Slope=0.0006
Boundary for River Rch & Prof#=ELM CREEK,Reach-1,7
Up Type=0
Dn Type=3
Dn Slope=0.0006

--- ELM CREEK.g01 (geometry) ---

Geom Title=Existing Conditions
Program Version=4.10

River Reach=ELM CREEK       ,Reach-1
Reach XY= 30
        2344125.       13633125.      2349776.59     13628578.68
      2352769.11     13627876.96      2356928.33     13630317.41
      2362622.29     13625630.28      2367173.53     13625421.47
      2367818.52     13623482.69      2372900.21     13621824.64
      2376108.72     13623658.26        2380433.     13632031.39
      2382216.86     13632368.94      2380725.41     13633935.53
        2381725.       13635275.      2386059.79      13634174.9
      2387364.48     13635674.54      2389323.54     13634228.54
      2391668.43     13637317.31      2394245.97     13637294.91
      2395014.68     13639914.18      2396302.14      13639250.9
      2398171.59     13643267.19      2403625.01     13641181.96
      2407318.95     13643123.34      2411788.32     13640911.63
      2412572.41     13638630.14      2415314.36     13640174.45
      2419744.87     13637124.68      2421830.65     13639873.03
      2431304.86      13638174.6        2435825.       13640675.

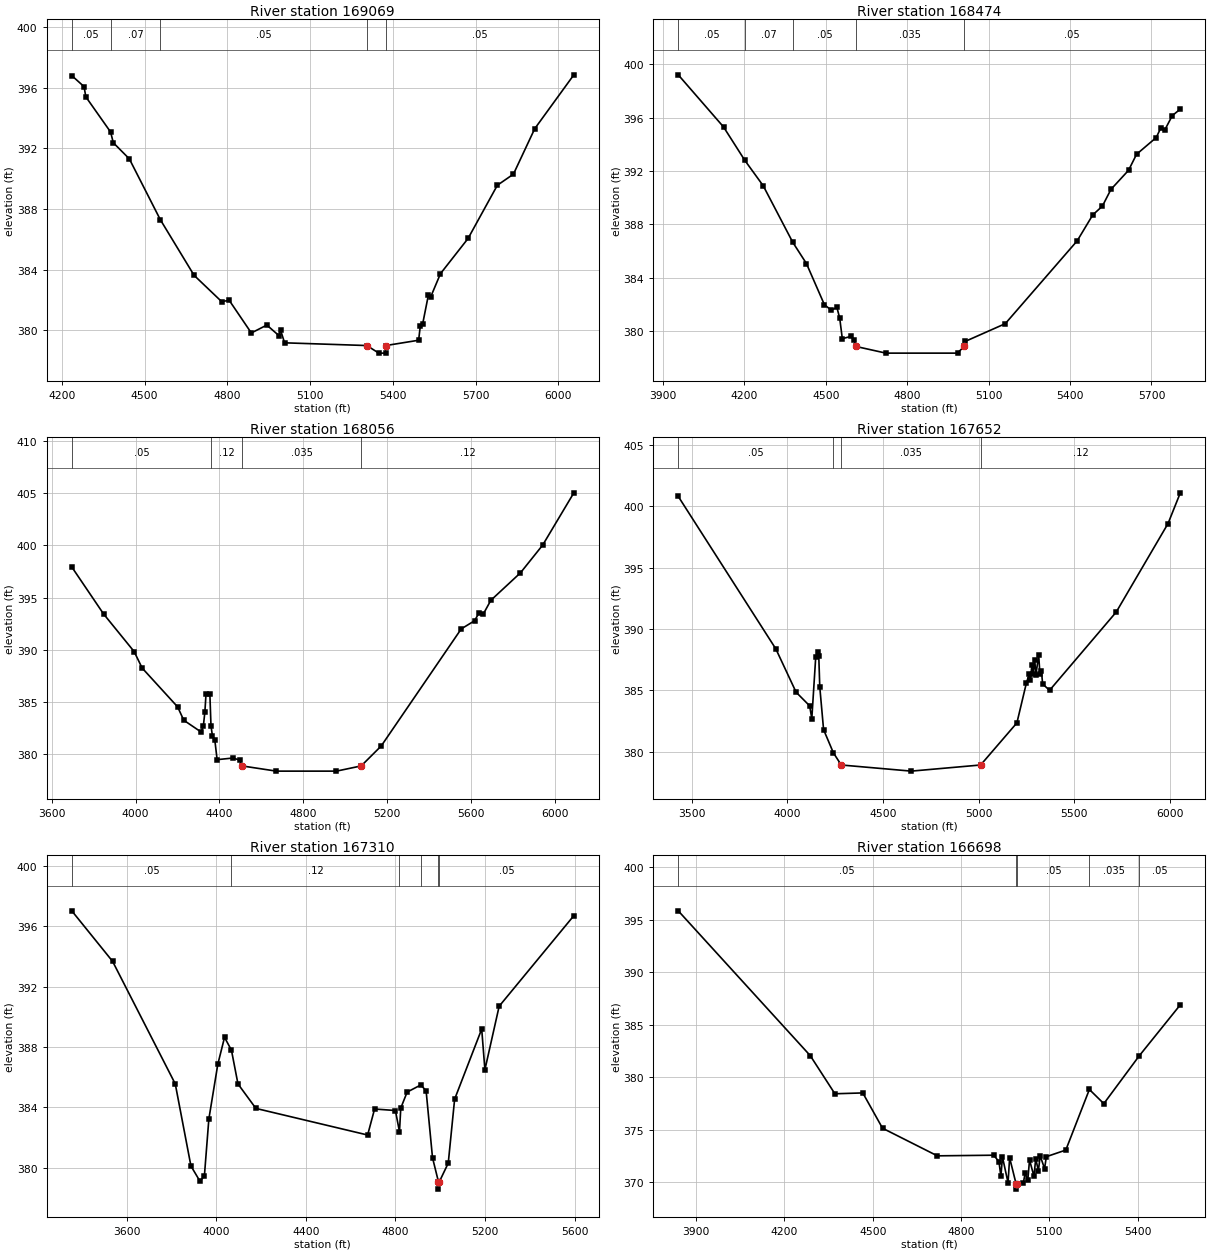
Type RM Length L Ch R = 1 ,169069  ,595,595,595
BEGIN DESCRIPTION:
ELM CREEK 116.0
END DESCRIPTION:
XS GIS Cut Line= 3
      2344669.51     13633652.35      2344169.51     13633002.36
      2343369.79     13632402.57
#Sta/Elev= 30
    4236   396.8  4280.6  396.07  4286.9   395.4  4376.7  393.08  4386.6  392.37
  4444.6  391.31  4556.9   387.3  4679.3  383.63    4779   381.9  4806.7  381.98
  4886.8  379.83    4943  380.35  4986.5  379.66  4992.8  380.01  5007.3  379.18
  5305.4     379  5348.9   378.5  5374.2   378.5  5374.4     379  5493.1  379.35
  5499.4  380.32  5507.7  380.42  5528.5  382.33  5536.7   382.2  5572.3  383.74
  5672.3  386.06  5778.5  389.57  5836.7   390.3    5914   393.3  6055.7  396.85
#Mann= 5 ,-1 , 0
    4236     .05       0  4376.7     .07       0  4556.9     .05       0
  5305.4    .035       0  5374.4     .05       0
Bank Sta=5305.4,5374.4
XS Rating Curve= 0 ,0
Exp/Cntr=0.3,0.1

Type RM Length L Ch R = 1 ,168474  ,418,418,418
BEGIN DESCRIPTION:
ELM CREEK 115.0
END DESCRIPTION:
XS GIS Cut Line= 3
        2344825.       13633575.        2344525.       13632575.
      2344124.98     13631874.96
#Sta/Elev= 30
    3956  399.21    4123   395.3  4201.6  392.79  4269.2  390.89  4378.1  386.65
  4428.4  385.06  4494.5  381.98  4519.8  381.56  4540.7  381.77  4551.1  380.96
  4560.7  379.42  4592.9   379.6  4604.2  379.36  4610.8  378.84  4721.4  378.34
  4985.4  378.34    5009  378.84  5013.7  379.22  5161.3  380.55  5426.2  386.76
  5483.8  388.71    5519  389.36  5550.7  390.62  5615.5  392.05    5645  393.25
  5717.7  394.51  5733.5  395.19  5748.7  395.06  5776.7  396.15  5806.3  396.64
#Mann= 5 ,-1 , 0
    3956     .05       0  4201.6     .07       0  4378.1     .05       0
  4610.8    .035       0    5009     .05       0
Bank Sta=4610.8,5009
XS Rating Curve= 0 ,0
Exp/Cntr=0.3,0.1

Type RM Length L Ch R = 1 ,168056  ,404,404,404
BEGIN DESCRIPTION:
ELM CREEK 114.0
END DESCRIPTION:
XS GIS Cut Line= 3
      2345274.99     13633474.97        2344775.       13632275.
      2343975.04     13631525.03
#Sta/Elev= 30
  3695.3  397.94  3846.9  393.44  3993.2  389.82  4031.1  388.25  4200.6  384.52
  4229.9  383.24  4312.8  382.11  4323.6  382.72  4330.6  384.03  4336.1  385.76
  4354.5  385.74  4359.8  382.71  4366.9   381.7  4377.8  381.39  4389.1  379.46
  4466.1  379.62  4496.9  379.41  4507.8  378.86  4671.7  378.36  4958.8  378.36
  5076.8  378.86  5172.3  380.77  5554.3     392  5617.8  392.78  5639.3  393.54
  5660.3  393.45  5695.5  394.74  5837.1  397.38  5943.1  400.04  6091.8  405.05
#Mann= 4 ,-1 , 0
  3695.3     .05       0  4359.8     .12       0  4507.8    .035       0
  5076.8     .12       0
Bank Sta=4507.8,5076.8
XS Rating Curve= 0 ,0
Exp/Cntr=0.3,0.1

Type RM Length L Ch R = 1 ,167652  ,342,342,342
BEGIN DESCRIPTION:
ELM CREEK 113.0
END DESCRIPTION:
XS GIS Cut Line= 3
      2345375.01     13633475.05      2345041.82     13632028.69
      2344150.31      13631319.7
#Sta/Elev= 30
  3430.5  400.81  3940.7  388.38  4046.3  384.86    4117  383.75  4128.4  382.71
  4148.9  387.73  4159.1   388.1  4164.9  387.77    4170  385.29  4189.9  381.81
  4241.2  379.92  4282.1  378.93  4648.1  378.43  5010.5  378.93    5200  382.36
  5249.6  385.61  5264.1  386.32  5270.4  385.82  5278.5  387.11  5284.9  386.33
  5292.9  387.52  5299.3  386.26  5313.7   387.9  5320.1  386.38  5328.1  386.59
  5334.5  385.53  5370.6  385.01    5719  391.39  5989.7   398.6  6053.8   401.1
#Mann= 4 ,-1 , 0
  3430.5     .05       0  4241.2     .12       0  4282.1    .035       0
  5010.5     .12       0
Bank Sta=4282.1,5010.5
XS Rating Curve= 0 ,0
Exp/Cntr=0.3,0.1

Type RM Length L Ch R = 1 ,167310  ,612,612,612
BEGIN DESCRIPTION:
ELM CREEK 112.0
END DESCRIPTION:
XS GIS Cut Line= 4
      2345407.51     13633217.22      2345407.51     13632309.99
      2345224.67     13631789.58      2344626.91     13631283.25
#Sta/Elev= 30
  3354.7  397.01  3536.9  393.67  3816.9  385.56  3886.9  380.13  3926.9  379.13
  3946.9  379.46  3966.9  383.24  4006.9  386.86  4036.9  388.64  4067.8  387.79
  4096.9  385.56  4176.9  383.94    4676  382.18    4707   383.9    4800   383.8
  4818.2   382.4    4824  383.96  4852.4  385.02  4913.3  385.49  4937.1  385.11
  4965.7  380.68    4992   379.1  4992.3   378.6  4996.6   379.1    5036  380.32
  5064.5  384.55  5185.4  389.19  5199.7   386.5  5263.4   390.7  5596.9  396.69
#Mann= 6 ,-1 , 0
  3354.7     .05       0  4067.8     .12       0  4818.2    .035       0
  4913.3     .05       0    4992     .05       0  4996.6     .05       0
Bank Sta=4992,4996.6
XS Rating Curve= 0 ,0
Exp/Cntr=0.3,0.1

Type RM Length L Ch R = 1 ,166698  ,314,314,314
BEGIN DESCRIPTION:
ELM CREEK 111.0
END DESCRIPTION:
XS GIS Cut Line= 3
       2346005.3     13632907.81        2345575.       13631825.
        2345275.       13631375.
#Sta/Elev= 30
  3839.1  395.85  4287.7  382.06  4371.4  378.43  4466.2  378.51  4533.3  375.15
  4719.5  372.52  4911.2  372.58  4928.9  371.96  4935.5  370.56  4940.8  372.41
  4959.8  369.95  4965.1  372.34  4987.1  369.85  4987.4  369.35  4991.8  369.85
  5011.8  369.95  5017.8  370.87  5026.8   370.2  5032.8  372.13  5047.8  370.57
  5053.8  372.25  5062.9  371.09  5068.9  372.52  5083.9   371.3  5089.9  372.44
    5156  373.07  5236.1  378.84  5285.2  377.49    5406  382.06  5545.1   386.9
#Mann= 5 ,-1 , 0
  3839.1     .05       0  4987.1     .05       0  4991.8     .05       0
  5236.1    .035       0    5406     .05       0
Bank Sta=4987.1,4991.8
XS Rating Curve= 0 ,0
Exp/Cntr=0.3,0.1

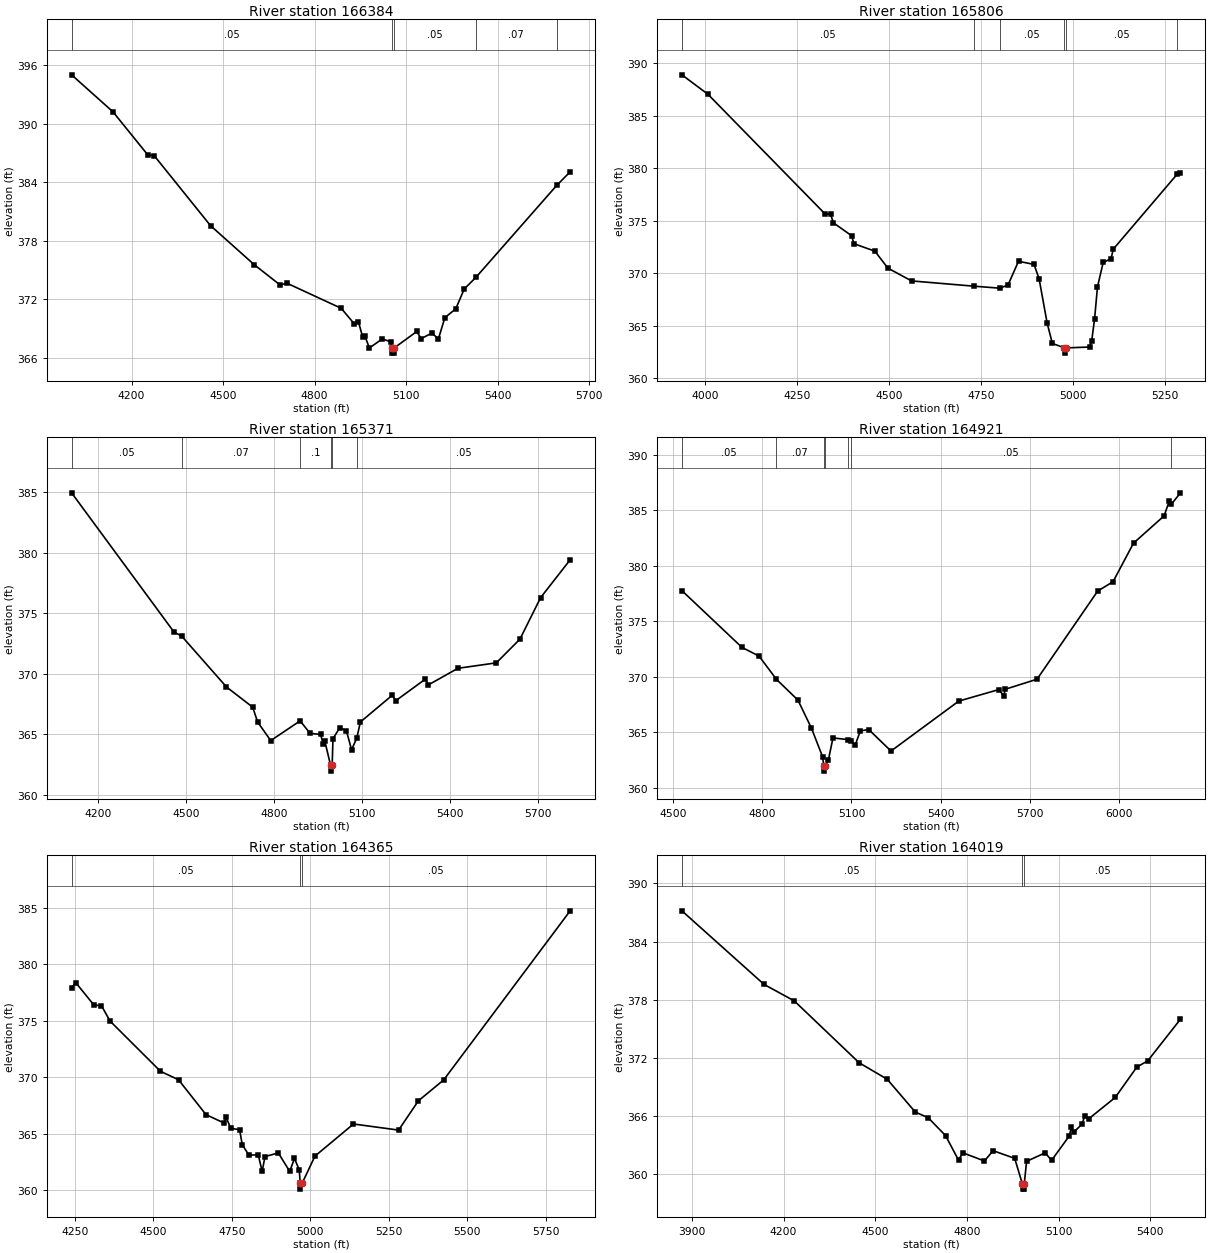
Type RM Length L Ch R = 1 ,166384  ,578,578,578
BEGIN DESCRIPTION:
ELM CREEK 110.0
END DESCRIPTION:
XS GIS Cut Line= 3
      2346624.98     13632424.99      2345920.89     13631881.01
      2345424.98     13631324.98
#Sta/Elev= 30
  4003.3  395.04  4139.1  391.24  4253.3  386.82  4274.1  386.75  4458.8  379.57
  4601.9  375.57    4687  373.48  4709.7  373.66  4887.3  371.09  4929.5  369.52
  4943.7  369.72  4957.9  368.12  4965.5  368.21  4979.7  367.02  5021.7  367.94
  5049.9  367.66  5055.1  366.99  5055.4  366.49  5059.4  366.49  5059.8  366.99
  5135.2  368.71  5149.4  367.98  5184.5  368.54  5206.2  367.96  5227.2  370.13
  5262.9  371.03  5290.7  373.07  5328.7  374.25  5593.8  383.69  5638.1  385.09
#Mann= 5 ,-1 , 0
  4003.3     .05       0  5055.1     .05       0  5059.8     .05       0
  5328.7     .07       0  5593.8    .035       0
Bank Sta=5055.1,5059.8
XS Rating Curve= 0 ,0
Exp/Cntr=0.3,0.1

Type RM Length L Ch R = 1 ,165806  ,435,435,435
BEGIN DESCRIPTION:
ELM CREEK 109.0
END DESCRIPTION:
XS GIS Cut Line= 3
        2346675.       13632175.        2345975.       13631375.
      2345724.96     13631224.98
#Sta/Elev= 30
  3937.2  388.87  4007.9  387.02  4326.8  375.61    4341  375.64  4348.6  374.79
    4398  373.57  4404.6   372.8  4461.6  372.09  4496.7  370.48  4561.2  369.26
  4730.7  368.76  4800.8  368.57  4823.2  368.87  4851.7  371.13  4893.9  370.83
  4907.7  369.46  4929.5  365.25  4943.7  363.31  4976.5  362.89  4976.8  362.39
  4981.3  362.89  5044.9  362.97  5050.7  363.59  5058.5  365.68  5066.3   368.7
  5081.8  371.02  5103.2  371.38  5109.1  372.28  5282.9  379.42  5291.8  379.55
#Mann= 6 ,-1 , 0
  3937.2     .05       0  4730.7     .07       0  4800.8     .05       0
  4976.5     .05       0  4981.3     .05       0  5282.9     .07       0
Bank Sta=4976.5,4981.3
XS Rating Curve= 0 ,0
Exp/Cntr=0.3,0.1

Type RM Length L Ch R = 1 ,165371  ,450,450,450
BEGIN DESCRIPTION:
ELM CREEK 108.0
END DESCRIPTION:
XS GIS Cut Line= 3
        2346725.       13632025.        2346325.       13631225.
      2346225.01     13630425.05
#Sta/Elev= 30
  4109.6  384.94    4459  373.44  4484.7  373.12  4637.9  368.91  4727.3  367.24
  4744.1  366.02  4788.8  364.48  4889.1  366.11    4923  365.08  4959.3  364.99
  4967.7  364.17  4973.3  364.44  4992.8  362.46  4993.3  361.96  4998.4  362.46
  5001.2  364.64  5024.2  365.54  5046.9   365.3  5064.5  363.73  5082.3  364.68
  5094.7  366.02  5203.1  368.22  5215.7  367.78  5316.4  369.56  5326.5  369.08
  5427.3  370.45  5558.3   370.9  5638.9  372.86  5709.5  376.29  5810.2  379.41
#Mann= 6 ,-1 , 0
  4109.6     .05       0  4484.7     .07       0  4889.1      .1       0
  4992.8     .05       0  4998.4      .1       0  5082.3     .05       0
Bank Sta=4992.8,4998.4
XS Rating Curve= 0 ,0
Exp/Cntr=0.3,0.1

Type RM Length L Ch R = 1 ,164921  ,556,556,556
BEGIN DESCRIPTION:
ELM CREEK 107.0
END DESCRIPTION:
XS GIS Cut Line= 3
      2346924.98     13631724.96        2346675.       13631325.
      2346174.98     13630224.96
#Sta/Elev= 30
  4528.6  377.77  4730.8  372.66  4788.6  371.87  4847.1  369.78  4919.5  367.91
  4964.9  365.39    5003  362.78  5006.2  362.01  5006.7  361.51  5011.8  362.01
  5022.2  362.52  5037.6   364.5  5088.5  364.35  5098.2  364.23  5112.3  363.84
  5129.9  365.14  5158.4  365.25  5233.1  363.32  5461.6  367.82  5595.6  368.85
  5613.2  368.32  5618.7  368.89  5725.2  369.79  5929.6  377.73  5981.2  378.57
  6050.4  382.05  6153.6  384.51  6171.2  385.87  6178.3  385.57  6208.6  386.58
#Mann= 7 ,-1 , 0
  4528.6     .05       0  4847.1     .07       0  5006.2     .05       0
  5011.8     .07       0  5088.5      .1       0  5098.2     .05       0
  6178.3    .035       0
Bank Sta=5006.2,5011.8
XS Rating Curve= 0 ,0
Exp/Cntr=0.3,0.1

Type RM Length L Ch R = 1 ,164365  ,346,346,346
BEGIN DESCRIPTION:
ELM CREEK 106.0
END DESCRIPTION:
XS GIS Cut Line= 3
      2347375.01     13631375.01      2346750.73     13630973.81
      2346274.97     13630274.96
#Sta/Elev= 30
  4239.7  377.92  4253.2  378.35    4311  376.37  4334.8  376.32  4362.2  374.96
  4522.7  370.52  4580.2  369.77  4667.6  366.69  4725.5  365.94  4731.4  366.47
  4746.6  365.47  4774.6  365.36    4783  364.04  4804.1  363.11  4834.1  363.13
  4846.4  361.67  4855.6  362.98  4897.9   363.3  4934.2  361.67  4949.4  362.81
  4964.6   361.8  4967.7   360.6  4968.1   360.1  4973.4   360.6  5014.6  363.02
  5137.3  365.86  5280.9  365.32  5343.9  367.91  5424.6  369.76  5827.2  384.71
#Mann= 3 ,-1 , 0
  4239.7     .05       0  4967.7     .05       0  4973.4     .05       0
Bank Sta=4967.7,4973.4
XS Rating Curve= 0 ,0
Exp/Cntr=0.3,0.1

Type RM Length L Ch R = 1 ,164019  ,935,935,935
BEGIN DESCRIPTION:
ELM CREEK 105.0
END DESCRIPTION:
XS GIS Cut Line= 3
        2347675.       13631525.        2346875.       13630725.
      2346474.97     13630424.98
#Sta/Elev= 30
  3867.6  387.16  4136.3  379.58  4235.3  377.88  4447.4  371.51  4539.3  369.81
  4631.3  366.43  4673.7  365.84  4730.3     364  4772.7  361.48  4786.8  362.23
  4857.5  361.39  4885.8  362.45  4956.5  361.66    4982  358.99  4982.4  358.49
  4987.2  358.49  4987.7  358.99  4995.4  361.35  5056.3  362.23  5077.1  361.45
  5135.4  363.98  5141.7  364.85    5149  364.33  5177.1   365.2  5185.4  366.01
    5199  365.74  5285.4  367.93  5356.3  371.07  5391.7   371.7    5499     376
#Mann= 3 ,-1 , 0
  3867.6     .05       0    4982     .05       0  4987.7     .05       0
Bank Sta=4982,4987.7
XS Rating Curve= 0 ,0
Exp/Cntr=0.3,0.1

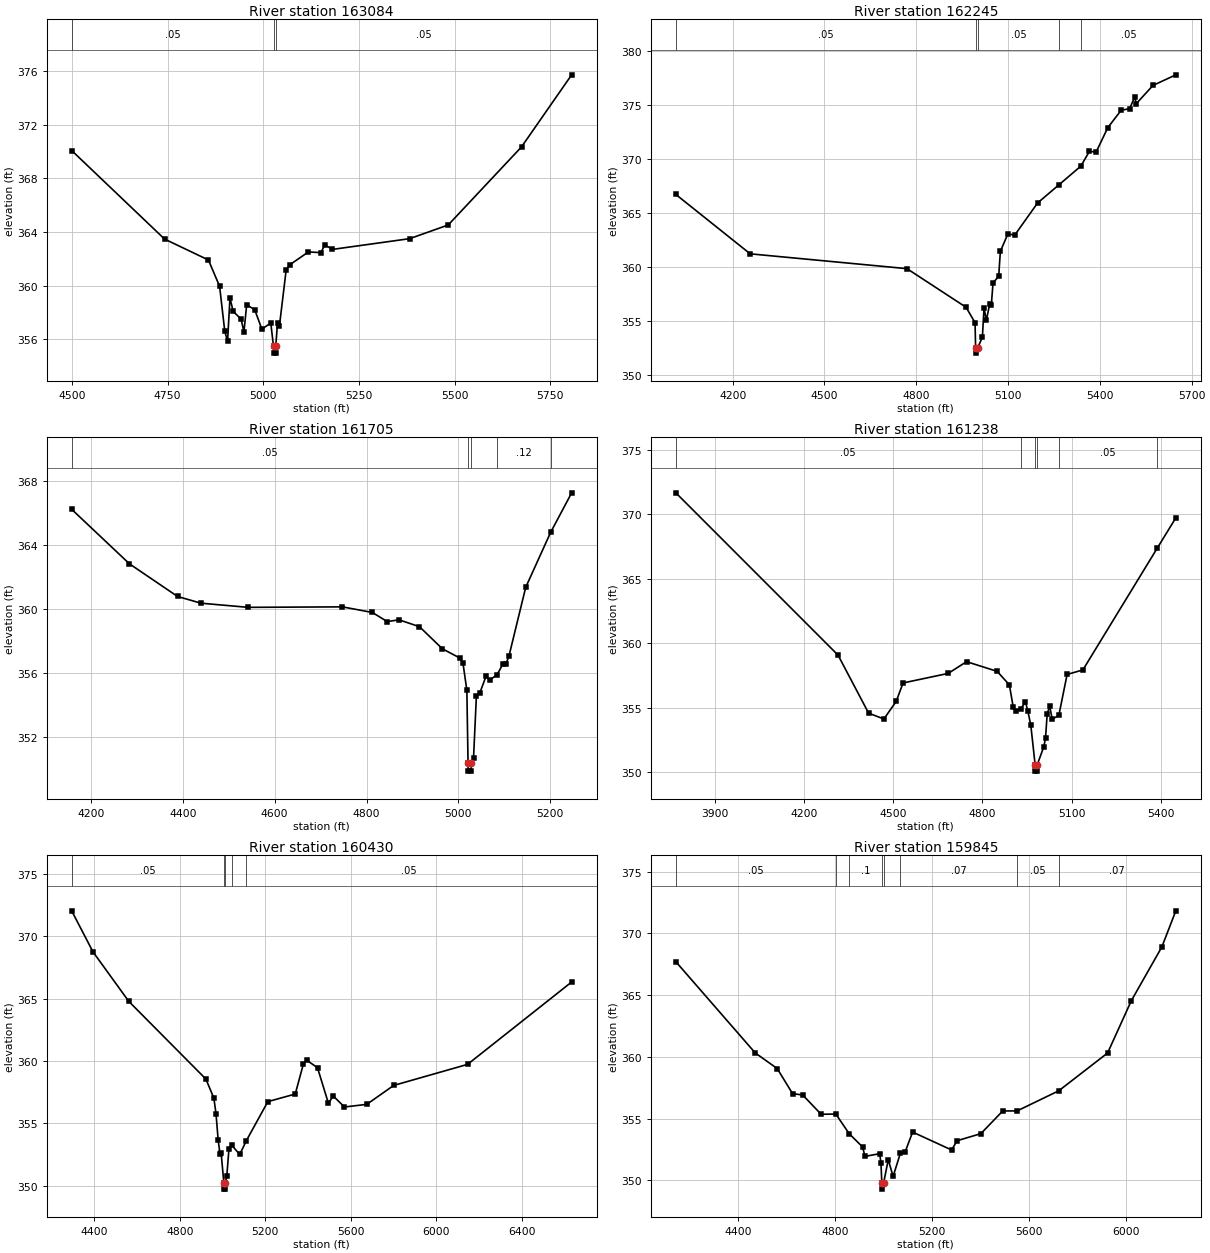
Type RM Length L Ch R = 1 ,163084  ,839,839,839
BEGIN DESCRIPTION:
ELM CREEK 104.0
END DESCRIPTION:
XS GIS Cut Line= 3
      2347675.02     13630725.03        2347375.       13630325.
      2346574.96       13630225.
#Sta/Elev= 30
  4499.3  370.07    4742  363.47  4856.6  361.91  4885.8  359.95  4899.3   356.6
  4906.6  355.86  4912.9  359.09  4921.2  358.08    4942  357.51  4949.3  356.55
  4956.6  358.57  4977.5  358.21  4996.2  356.76  5019.5  357.21  5026.7  355.47
  5027.1  354.97    5032  354.97  5032.5  355.47  5037.1  357.23  5042.2  357.02
  5059.8  361.19  5069.9  361.57  5117.8  362.51  5150.5  362.46  5160.6  363.04
  5180.7   362.7  5382.3   363.5  5483.1  364.52  5674.6  370.34  5805.6  375.71
#Mann= 3 ,-1 , 0
  4499.3     .05       0  5026.7     .05       0  5032.5     .05       0
Bank Sta=5026.7,5032.5
XS Rating Curve= 0 ,0
Exp/Cntr=0.3,0.1

Type RM Length L Ch R = 1 ,162245  ,540,540,540
BEGIN DESCRIPTION:
X19133
END DESCRIPTION:
XS GIS Cut Line= 4
      2347904.06     13630495.58      2347496.18     13629940.02
      2347102.36     13629778.27      2346856.23     13629321.18
#Sta/Elev= 30
  4014.2  366.71  4257.2  361.22  4769.6  359.85  4962.7  356.28  4992.1  354.86
  4993.9  352.54  4994.4  352.04    5001  352.54  5016.1  353.52  5021.5  356.23
    5029  355.07  5039.8  356.56  5045.4  356.53  5050.8  358.51  5069.4  359.16
  5074.8  361.45  5098.8  363.02  5122.8  362.99  5196.4  365.92  5267.5  367.63
  5337.9  369.33  5365.9   370.7  5387.8  370.63    5426  372.89  5469.8   374.5
  5497.4  374.64  5513.6  375.71  5519.3  375.11  5573.6  376.79  5648.3  377.77
#Mann= 5 ,-1 , 0
  4014.2     .05       0  4993.9     .05       0    5001     .05       0
  5267.5    .035       0  5337.9     .05       0
Bank Sta=4993.9,5001
XS Rating Curve= 0 ,0
Exp/Cntr=0.3,0.1

Type RM Length L Ch R = 1 ,161705  ,467,467,467
BEGIN DESCRIPTION:
ELM CREEK 103.0
END DESCRIPTION:
XS GIS Cut Line= 3
      2347925.01     13630475.03        2347675.       13629675.
      2347524.99     13629474.99
#Sta/Elev= 30
  4158.3  366.25  4284.1  362.84  4388.8   360.8  4439.6  360.38  4542.3  360.12
  4747.7  360.15  4812.6   359.8  4845.1  359.23  4870.8  359.34  4915.3  358.91
  4965.1  357.53  5003.8  356.94    5010  356.62  5018.4  354.94    5021  350.38
  5021.5  349.88  5027.7  349.88  5028.2  350.38  5032.9  350.68  5039.2   354.6
  5046.5  354.76    5060   355.8  5068.4  355.58  5084.3  355.91  5096.5  356.56
  5103.8   356.6    5110  357.07  5146.5  361.37  5200.6   364.8  5246.5  367.28
#Mann= 5 ,-1 , 0
  4158.3     .05       0    5021     .05       0  5028.2     .05       0
  5084.3     .12       0  5200.6     .05       0
Bank Sta=5021,5028.2
XS Rating Curve= 0 ,0
Exp/Cntr=0.3,0.1

Type RM Length L Ch R = 1 ,161238  ,808,808,808
BEGIN DESCRIPTION:
ELM CREEK 102.0
END DESCRIPTION:
XS GIS Cut Line= 3
        2348325.     13630625.02        2348025.       13629425.
      2347624.97     13629224.98
#Sta/Elev= 30
  3767.2  371.65  4313.5  359.08  4416.6  354.58  4468.1  354.13  4509.4  355.49
  4532.6  356.92  4684.6  357.66  4746.5  358.57  4849.5  357.82  4890.8  356.77
  4903.6  355.05  4911.4  354.72    4929  354.92  4944.9  355.44  4952.6  354.78
  4962.9  353.65  4977.4  350.59  4977.9  350.09  4984.1  350.09  4984.6  350.59
  5006.9  351.99  5012.5  352.67  5018.1  354.53  5026.5  355.12  5034.9  354.12
  5057.2   354.4  5085.2  357.58  5138.3  357.93  5389.2  367.38  5451.4  369.71
#Mann= 6 ,-1 , 0
  3767.2     .05       0    4929      .1       0  4977.4     .05       0
  4984.6      .1       0  5057.2     .05       0  5389.2    .035       0
Bank Sta=4977.4,4984.6
XS Rating Curve= 0 ,0
Exp/Cntr=0.3,0.1

Type RM Length L Ch R = 1 ,160430  ,585,585,585
BEGIN DESCRIPTION:
X19132
END DESCRIPTION:
XS GIS Cut Line= 3
      2348607.33     13630523.72      2348466.68      13629525.1
      2347840.77     13628350.65
#Sta/Elev= 30
  4294.3  372.04    4394  368.75  4561.3  364.78  4922.3  358.54  4959.5  357.02
  4969.6  355.77  4979.7  353.65  4988.5  352.52  4993.5  352.62  5006.4  350.21
  5006.9  349.71  5013.2  349.71  5013.7  350.21  5020.1  350.75  5030.2  352.95
  5043.3  353.23  5080.7  352.49    5111  353.58  5212.1  356.73  5340.4  357.34
  5378.7  359.77  5393.5  360.06  5444.5  359.45  5495.5   356.6  5518.2  357.18
  5570.6   356.3  5674.8  356.51  5800.9  358.03  6146.6  359.72  6633.6  366.33
#Mann= 5 ,-1 , 0
  4294.3     .05       0  5006.4     .05       0  5013.7     .05       0
  5043.3      .1       0    5111     .05       0
Bank Sta=5006.4,5013.7
XS Rating Curve= 0 ,0
Exp/Cntr=0.3,0.1

Type RM Length L Ch R = 1 ,159845  ,412,412,412
BEGIN DESCRIPTION:
ELM CREEK 99.0
END DESCRIPTION:
XS GIS Cut Line= 3
      2349125.01     13630175.03        2348825.       13629375.
        2348725.     13628174.99
#Sta/Elev= 30
  4145.2   367.7  4471.9  360.32  4562.6  359.05  4625.8  357.02  4667.7  356.91
  4743.3  355.35  4803.9  355.37  4858.8  353.78  4914.2   352.7    4924  351.94
  4984.5  352.16  4989.8  351.37  4993.3  349.79  4993.8  349.29  5000.7  349.79
  5019.7  351.67  5039.8  350.32  5069.7   352.2  5089.9  352.33    5120  353.91
  5280.6  352.46  5303.2  353.21    5401  353.78  5491.3  355.62  5550.1  355.62
  5721.7  357.25  5922.8  360.31  6020.7  364.55  6146.1  368.89  6203.8  371.82
#Mann= 8 ,-1 , 0
  4145.2     .05       0  4803.9     .07       0  4858.8      .1       0
  4993.3     .05       0  5000.7      .1       0  5069.7     .07       0
  5550.1     .05       0  5721.7     .07       0
Bank Sta=4993.3,5000.7
XS Rating Curve= 0 ,0
Exp/Cntr=0.3,0.1

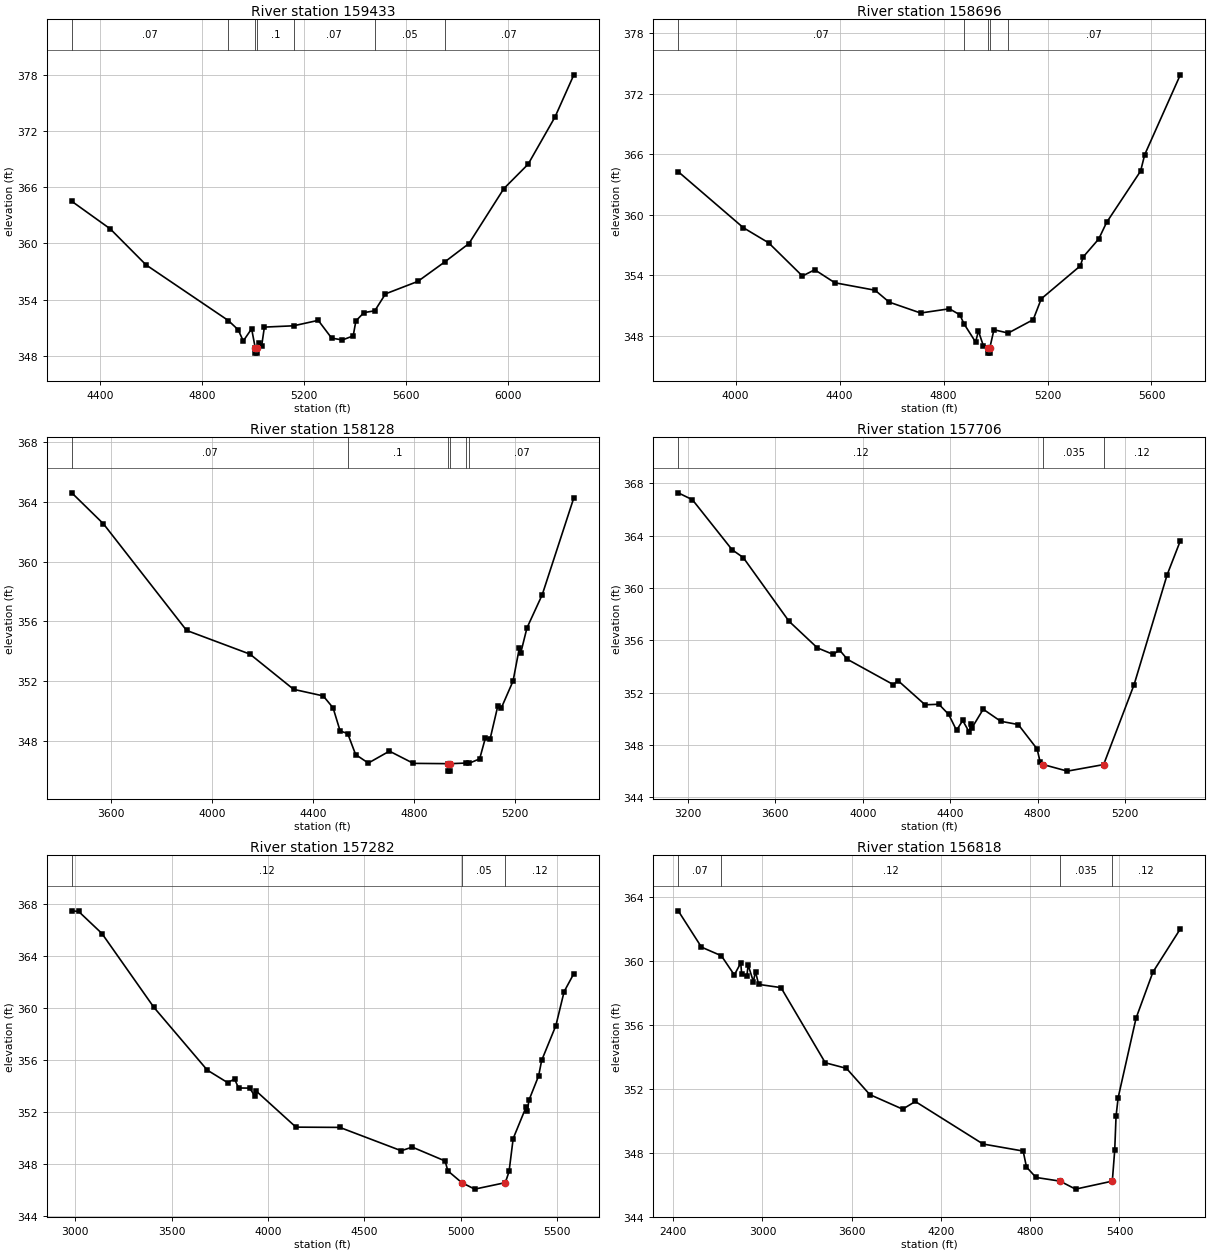
Type RM Length L Ch R = 1 ,159433  ,737,737,737
BEGIN DESCRIPTION:
ELM CREEK 98.0
END DESCRIPTION:
XS GIS Cut Line= 3
        2349225.     13629975.04        2349175.       13629275.
      2348775.01     13628075.04
#Sta/Elev= 30
  4289.5   364.5  4439.9  361.56  4580.3  357.71  4902.8  351.76  4941.2  350.78
  4961.3  349.58    4994  350.88  5008.6  348.78  5009.1  348.28  5015.7  348.28
  5016.2  348.78  5022.9  349.36  5033.5  349.09    5044  351.06  5158.4   351.2
  5254.9  351.78  5307.6  349.88  5349.7  349.69  5391.9  350.12  5402.4  351.72
    5434  352.61  5476.4   352.8  5518.4  354.61  5644.9  355.94  5749.9  358.01
  5845.1  359.98  5982.2  365.86    6077  368.46  6182.5  373.51  6256.2  378.01
#Mann= 7 ,-1 , 0
  4289.5     .07       0  4902.8      .1       0  5008.6     .05       0
  5016.2      .1       0  5158.4     .07       0  5476.4     .05       0
  5749.9     .07       0
Bank Sta=5008.6,5016.2
XS Rating Curve= 0 ,0
Exp/Cntr=0.3,0.1

Type RM Length L Ch R = 1 ,158696  ,568,568,568
BEGIN DESCRIPTION:
X19131
END DESCRIPTION:
XS GIS Cut Line= 3
      2349261.37     13629947.02      2349563.75     13629208.64
       2349423.1      13628083.4
#Sta/Elev= 30
    3779  364.27  4029.7  358.71    4127  357.21  4256.7  353.92  4304.2  354.54
  4381.6  353.25  4536.4  352.51  4590.6  351.33  4711.6  350.25  4822.4  350.67
  4862.7  350.07  4878.7  349.17  4923.2  347.37    4934  348.47  4953.4  346.97
  4969.5  346.77    4970  346.27  4977.2  346.27  4977.7  346.77  4993.8  348.59
  5048.6  348.26  5144.9  349.59  5175.9  351.66  5326.3  354.93  5337.1  355.81
  5396.9  357.59  5427.1  359.23  5558.1  364.33  5573.9  365.96  5710.9  373.88
#Mann= 5 ,-1 , 0
    3779     .07       0  4878.7      .1       0  4969.5     .05       0
  4977.7      .1       0  5048.6     .07       0
Bank Sta=4969.5,4977.7
XS Rating Curve= 0 ,0
Exp/Cntr=0.3,0.1

Type RM Length L Ch R = 1 ,158128  ,422,422,422
BEGIN DESCRIPTION:
ELM CREEK 97.0
END DESCRIPTION:
XS GIS Cut Line= 3
      2349274.98     13629975.03        2349975.       13628575.
        2349825.     13628174.99
#Sta/Elev= 30
  3442.8  364.62  3568.6  362.54  3898.4   355.4    4150  353.81  4323.3  351.45
  4440.7  351.01  4479.8  350.21  4507.8  348.66  4537.8  348.49  4569.3  347.08
  4619.6  346.51  4703.4  347.31  4798.5  346.49  4936.9  346.47  4937.4  345.97
  4944.6  345.97  4945.1  346.47  5006.8  346.51  5018.5  346.49  5061.5  346.79
  5083.7  348.16  5103.3  348.15  5133.6  350.34  5146.9  350.18  5194.1  352.01
    5219  354.22  5224.4  353.88  5249.3  355.57  5309.8  357.79  5435.3  364.29
#Mann= 6 ,-1 , 0
  3442.8     .07       0  4537.8      .1       0  4936.9     .05       0
  4945.1      .1       0  5006.8    .033       0  5018.5     .07       0
Bank Sta=4936.9,4945.1
XS Rating Curve= 0 ,0
Exp/Cntr=0.3,0.1

Type RM Length L Ch R = 1 ,157706  ,424,424,424
BEGIN DESCRIPTION:
ELM CREEK 96.0
END DESCRIPTION:
XS GIS Cut Line= 3
      2349324.98     13630125.03        2350325.       13628575.
        2350275.     13628124.99
#Sta/Elev= 30
  3155.7  367.27  3220.7  366.74  3402.2  362.92  3453.3  362.32  3662.3  357.46
  3792.3  355.42  3864.9  354.92  3893.6  355.26  3929.3  354.55  4140.1  352.61
  4161.2  352.92  4285.3  351.07  4348.6  351.11  4393.4  350.33  4429.1  349.12
  4457.5  349.87  4487.9  348.96  4493.8  349.58  4500.5  349.33  4551.2  350.73
  4631.4  349.81  4711.6  349.56    4798  347.69  4811.3  346.72  4826.4   346.5
  4936.2     346  5102.2   346.5  5241.8  352.62  5392.7     361  5453.1   363.6
#Mann= 3 ,-1 , 0
  3155.7     .12       0  4826.4    .035       0  5102.2     .12       0
Bank Sta=4826.4,5102.2
XS Rating Curve= 0 ,0
Exp/Cntr=0.3,0.1

Type RM Length L Ch R = 1 ,157282  ,464,464,464
BEGIN DESCRIPTION:
ELM CREEK 95.0
END DESCRIPTION:
XS GIS Cut Line= 3
      2349374.99     13630175.01        2350675.       13628625.
        2350375.       13628125.
#Sta/Elev= 30
  2981.3   367.5  3017.1  367.45  3137.9  365.75  3407.4  360.06  3684.5  355.22
  3790.5  354.25  3826.3  354.53  3847.1  353.84  3904.3  353.83  3932.9   353.2
  3939.5  353.59    4145  350.82  4372.7   350.8  4691.4     349  4748.7  349.28
  4919.1  348.21  4933.4  347.45  5005.6  346.54  5072.8  346.04  5231.8  346.54
  5251.1   347.4  5272.5  349.94  5340.6  352.41  5346.4   352.1  5354.2  352.89
  5404.7  354.78  5420.2  355.96  5494.1  358.65  5536.9  361.27  5587.4  362.66
#Mann= 3 ,-1 , 0
  2981.3     .12       0  5005.6     .05       0  5231.8     .12       0
Bank Sta=5005.6,5231.8
XS Rating Curve= 0 ,0
Exp/Cntr=0.3,0.1

Type RM Length L Ch R = 1 ,156818  ,429,429,429
BEGIN DESCRIPTION:
ELM CREEK 94.0
END DESCRIPTION:
XS GIS Cut Line= 3
      2349475.01     13630624.99        2351075.       13628625.
      2350474.98     13628074.99
#Sta/Elev= 30
    2434  363.12  2590.1  360.85  2724.1  360.31    2811  359.11  2854.2  359.86
  2860.6  359.15  2895.8  359.07  2903.8  359.74    2939   358.7  2953.4  359.32
  2974.3  358.52  3124.7  358.32  3422.5  353.62  3564.9  353.27  3721.8  351.63
  3942.7  350.72  4027.6   351.2    4483  348.54  4752.7   348.1  4775.1   347.1
  4839.2  346.45  5000.5  346.22  5104.8  345.72  5352.1  346.22  5368.3  348.16
  5377.2  350.28  5391.4  351.44  5511.7  356.41  5625.1  359.29  5809.2  361.99
#Mann= 4 ,-1 , 0
    2434     .07       0  2724.1     .12       0  5000.5    .035       0
  5352.1     .12       0
Bank Sta=5000.5,5352.1
XS Rating Curve= 0 ,0
Exp/Cntr=0.3,0.1

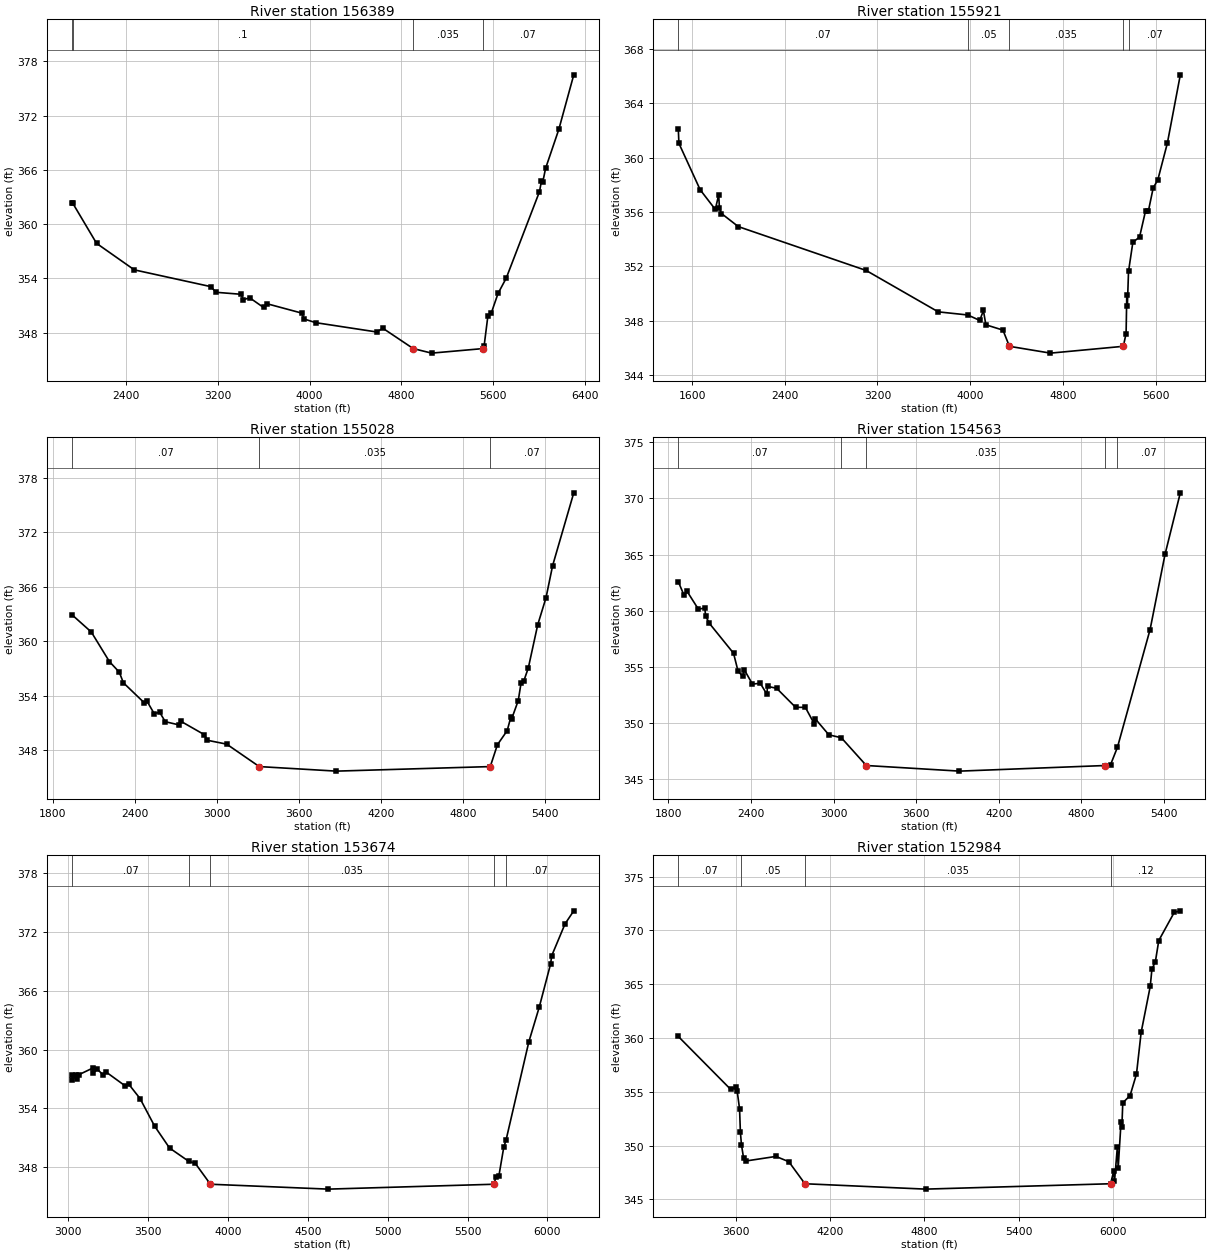
Type RM Length L Ch R = 1 ,156389  ,468,468,468
BEGIN DESCRIPTION:
ELM CREEK 93.0
END DESCRIPTION:
XS GIS Cut Line= 4
      2349472.04     13630665.14      2350647.07     13630162.85
        2351375.       13628525.        2351875.     13627325.01
#Sta/Elev= 30
  1929.8  362.34  1939.3   362.3  2145.8  357.88  2474.2  354.95  3142.1  353.09
  3183.7  352.47  3402.3  352.25  3424.2  351.65  3478.9  351.86  3599.3  350.79
  3630.1   351.2    3931  350.17  3954.3  349.51  4052.7  349.11  4584.2  348.08
  4638.2  348.49  4902.8  346.24  5062.8  345.74    5508  346.24    5520  346.58
  5552.5  349.86  5582.3  350.19  5640.8  352.34  5712.3  354.04  6001.6   363.6
  6018.3  364.75  6030.8  364.69  6054.6  366.17    6170  370.49    6300  376.52
#Mann= 4 ,-1 , 0
  1929.8     .05       0  1939.3      .1       0  4902.8    .035       0
    5508     .07       0
Bank Sta=4902.8,5508
XS Rating Curve= 0 ,0
Exp/Cntr=0.3,0.1

Type RM Length L Ch R = 1 ,155921  ,893,893,893
BEGIN DESCRIPTION:
ELM CREEK 92.0
END DESCRIPTION:
XS GIS Cut Line= 4
      2349506.99     13630682.62      2351187.19     13629988.42
        2351725.       13628375.        2351875.       13627575.
#Sta/Elev= 30
  1481.3  362.08  1486.4  361.04    1670  357.63  1800.4  356.19  1829.7  357.26
  1836.2  356.29  1853.6  355.89  1998.5  354.93  3102.1  351.71  3724.5  348.67
  3979.9  348.44  4082.9  348.04  4114.5  348.77  4135.6  347.72  4283.2  347.33
  4338.8  346.14  4693.1  345.64  5321.9  346.14  5345.9  347.08  5351.8  349.89
  5356.9  349.12  5366.9  351.64  5404.4  353.78    5462  354.16  5514.6  356.11
  5539.2  356.11  5579.9  357.77  5619.7  358.36    5702  361.05  5813.9  366.07
#Mann= 5 ,-1 , 0
  1481.3     .07       0  3979.9     .05       0  4338.8    .035       0
  5321.9    .033       0  5366.9     .07       0
Bank Sta=4338.8,5321.9
XS Rating Curve= 0 ,0
Exp/Cntr=0.3,0.1

Type RM Length L Ch R = 1 ,155028  ,465,465,465
BEGIN DESCRIPTION:
ELM CREEK 91.0
END DESCRIPTION:
XS GIS Cut Line= 3
      2351774.99     13630975.03        2352375.       13627975.
        2352275.     13627375.02
#Sta/Elev= 30
  1940.5  362.93  2083.3  361.01  2215.9  357.75  2287.3   356.6  2317.9  355.42
  2470.8  353.21  2491.2  353.37  2542.2  352.04    2583  352.17  2623.8  351.14
  2725.8  350.78    2736   351.2  2909.3  349.71  2929.7   349.1  3072.5  348.67
  3310.4   346.2    3873   345.7  4998.1   346.2  5050.6  348.61  5121.6  350.15
  5149.5   351.7  5154.5  351.45  5202.7  353.47    5223  355.39  5243.3  355.63
  5276.2  357.06  5344.6  361.79  5405.5  364.79  5453.6  368.31  5608.2  376.33
#Mann= 3 ,-1 , 0
  1940.5     .07       0  3310.4    .035       0  4998.1     .07       0
Bank Sta=3310.4,4998.1
XS Rating Curve= 0 ,0
Exp/Cntr=0.3,0.1

Type RM Length L Ch R = 1 ,154563  ,889,889,889
BEGIN DESCRIPTION:
ELM CREEK 90.0
END DESCRIPTION:
XS GIS Cut Line= 3
      2351874.99     13630875.02        2352775.       13627875.
        2352525.       13627425.
#Sta/Elev= 30
  1871.7  362.59  1913.5  361.38  1934.4  361.75  2017.9  360.14    2064  360.26
  2070.1  359.54  2097.1  358.89  2272.8  356.23  2305.9  354.62  2338.9  354.19
    2352  354.74  2410.3  353.48  2466.8  353.56  2514.7  352.59  2519.9  353.28
    2586  353.11  2723.5  351.42  2794.8  351.41  2860.9  349.91  2866.2   350.4
  2965.3  348.97  3055.9  348.71  3237.4  346.24  3914.3  345.74  4974.6  346.24
  5011.8  346.31  5062.1  347.87    5299  358.34  5407.6  365.03  5518.6   370.5
#Mann= 5 ,-1 , 0
  1871.7     .07       0  3055.9     .05       0  3237.4    .035       0
  4974.6     .05       0  5062.1     .07       0
Bank Sta=3237.4,4974.6
XS Rating Curve= 0 ,0
Exp/Cntr=0.3,0.1

Type RM Length L Ch R = 1 ,153674  ,690,690,690
BEGIN DESCRIPTION:
X19130
END DESCRIPTION:
XS GIS Cut Line= 3
      2352679.18     13630305.71      2353494.96      13628294.4
      2353628.57     13627330.97
#Sta/Elev= 30
  3021.9  357.38  3026.1  356.87  3050.2  357.43  3055.6  356.98  3065.8  357.43
  3151.9   358.1  3157.3  357.61  3181.4  357.99  3216.9  357.44    3235  357.73
  3357.2  356.28  3378.8  356.46  3449.3     355  3540.6  352.18  3634.2  349.94
  3755.4  348.57  3794.9  348.38  3890.1  346.24  4627.6  345.74  5667.4  346.24
  5676.3  347.01  5696.5  347.12  5726.8  350.03  5740.8  350.74  5883.8   360.8
  5948.9  364.34  6019.6  368.73  6027.2   369.6  6110.5  372.85    6165  374.18
#Mann= 5 ,-1 , 0
  3021.9     .07       0  3755.4     .05       0  3890.1    .035       0
  5667.4     .05       0  5740.8     .07       0
Bank Sta=3890.1,5667.4
XS Rating Curve= 0 ,0
Exp/Cntr=0.3,0.1

Type RM Length L Ch R = 1 ,152984  ,96,96,96
BEGIN DESCRIPTION:
F21665
END DESCRIPTION:
XS GIS Cut Line= 3
      2353351.29     13630589.45      2353520.21     13629867.15
       2354498.5      13627619.4
#Sta/Elev= 30
  3234.5  360.14  3567.7  355.22  3598.5  355.41  3608.8  355.07  3624.1   353.4
  3629.3  351.25  3636.1  350.08  3649.9  348.81  3666.6  348.57  3855.3  348.99
  3937.4   348.5  4039.8  346.45  4807.3  345.95  5984.3  346.45  6003.6   347.6
    6009  346.67    6027  349.82  6032.5  347.91  6050.5  352.15  6055.9  351.73
  6061.7  353.97  6108.2  354.65  6148.9  356.65  6178.5  360.52  6236.3  364.79
  6247.1   366.4  6268.9  367.08  6290.7  369.06  6388.9  371.67  6427.7  371.82
#Mann= 4 ,-1 , 0
  3234.5     .07       0  3636.1     .05       0  4039.8    .035       0
  5984.3     .12       0
Bank Sta=4039.8,5984.3
XS Rating Curve= 0 ,0
Exp/Cntr=0.3,0.1