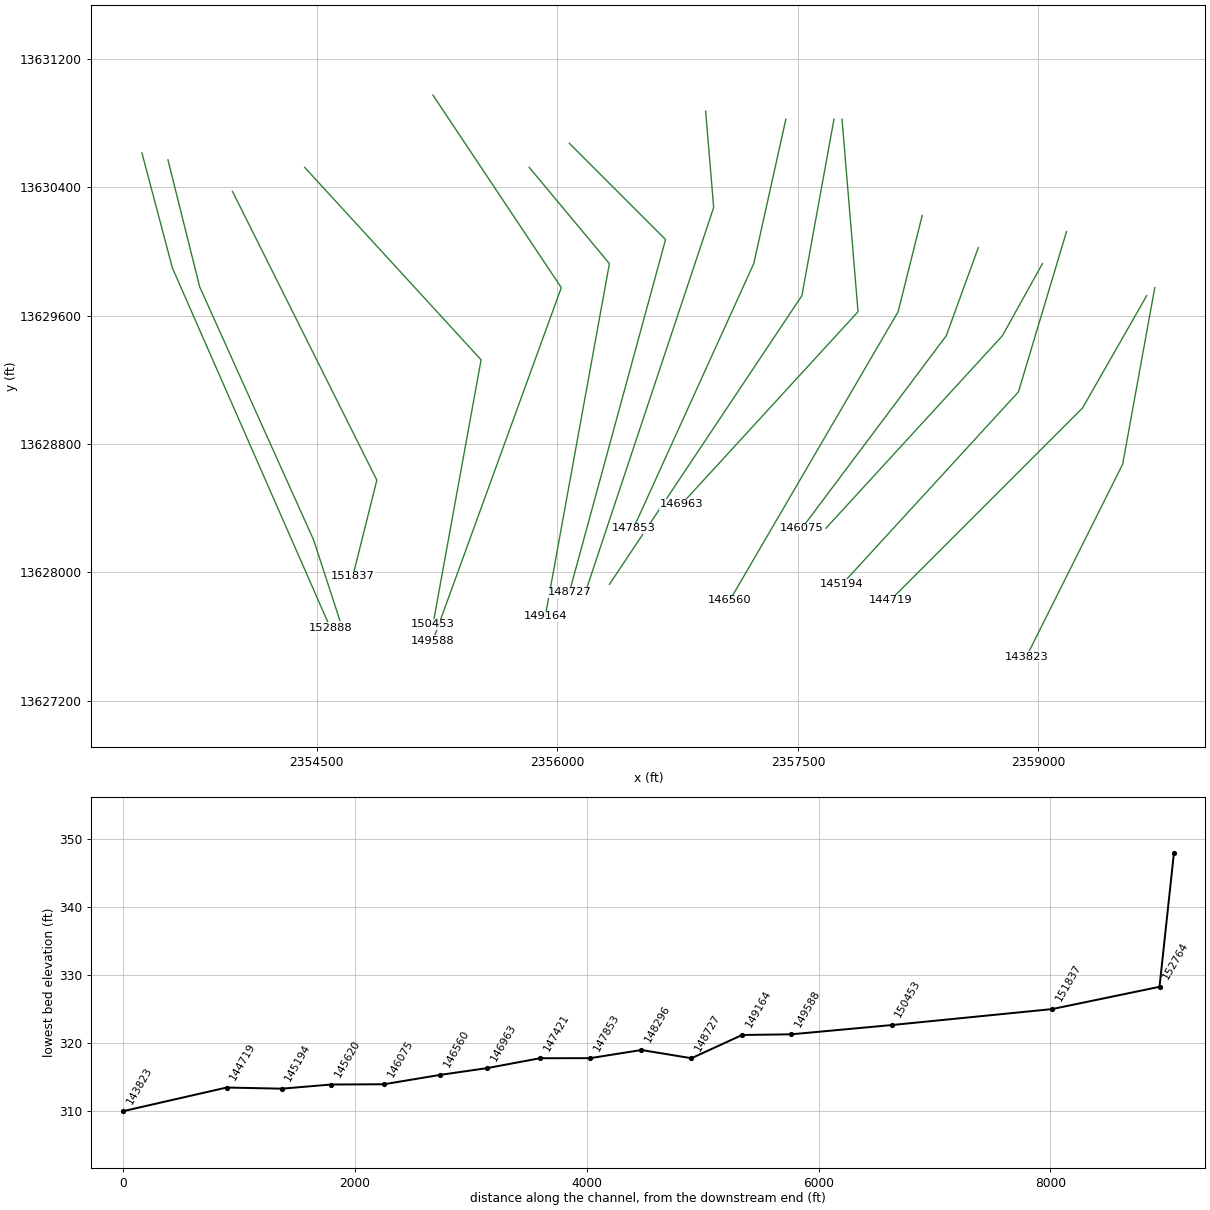
HEC-RAS study ELM CREEK.prj: ELM CREEK Base Level Engineering

--- ELM CREEK.g01 (geometry) --- (continued)

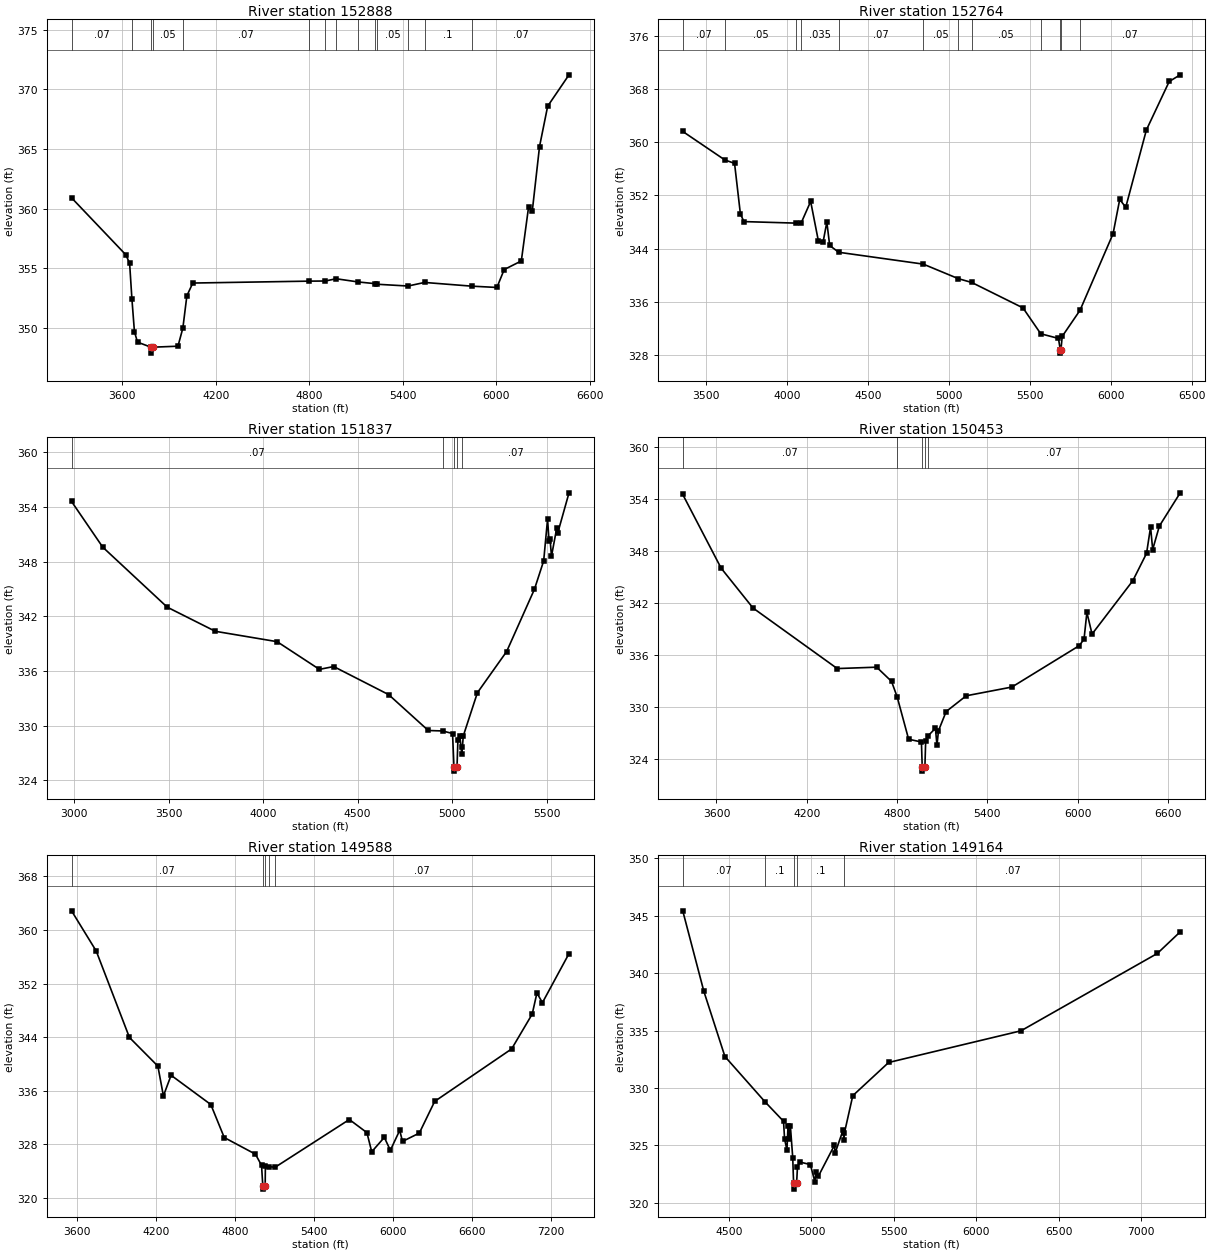
Type RM Length L Ch R = 1 ,152888  ,124,124,124
BEGIN DESCRIPTION:
X19129
END DESCRIPTION:
XS GIS Cut Line= 3
      2353410.56     13630615.16      2353600.44     13629897.83
      2354585.02     13627654.41
#Sta/Elev= 30
  3273.8  360.92  3621.9  356.15  3646.4  355.44  3661.3  352.43  3677.4   349.7
  3697.2  348.83    3783  348.41  3783.5  347.91  3799.3  348.41  3956.7  348.49
  3988.1  350.01  4013.8  352.71  4051.7  353.78  4799.7  353.94  4901.8  353.95
  4971.2  354.14  5114.2  353.87  5220.5  353.73  5233.4  353.68  5432.9  353.53
  5539.1  353.83  5840.9  353.52  6003.2  353.41  6049.9  354.91  6159.8  355.63
  6206.5  360.16  6229.9  359.78  6276.6  365.21  6328.8  368.59  6465.8  371.22
#Mann= 14 ,-1 , 0
  3273.8     .07       0  3661.3     .05       0    3783     .05       0
  3799.3     .05       0  3988.1     .07       0  4799.7     .05       0
  4901.8     .07       0  4971.2     .05       0  5114.2     .07       0
  5220.5    .033       0  5233.4     .05       0  5432.9     .07       0
  5539.1      .1       0  5840.9     .07       0
Bank Sta=3783,3799.3
XS Rating Curve= 0 ,0
Exp/Cntr=0.3,0.1

Type RM Length L Ch R = 1 ,152764  ,927,927,927
BEGIN DESCRIPTION:
F21664
END DESCRIPTION:
XS GIS Cut Line= 4
      2353572.64     13630571.89      2353770.67     13629779.78
      2354481.28      13628201.3      2354644.35     13627700.42
#Sta/Elev= 30
  3355.2   361.6  3615.1  357.32  3675.4   356.8  3711.5   349.2  3733.4  348.05
  4054.6  347.82  4086.9  347.84  4145.7  351.08  4193.9  345.08  4222.5  344.97
  4245.7  347.98  4263.3  344.46  4318.9  343.44  4841.5  341.66  5058.5  339.47
  5141.2   338.9  5457.8  335.08  5567.7  331.19  5677.1  330.49  5688.3  328.78
  5688.6  328.28  5692.3  328.78  5700.3   330.8  5810.3  334.72  6014.5  346.22
  6055.7  351.38  6092.9   350.2  6220.6  361.83  6361.6  369.11  6429.5  370.11
#Mann= 12 ,-1 , 0
  3355.2     .07       0  3615.1     .05       0  4054.6     .07       0
  4086.9    .035       0  4318.9     .07       0  4841.5     .05       0
  5058.5     .07       0  5141.2     .05       0  5567.7      .1       0
  5688.3     .05       0  5692.3      .1       0  5810.3     .07       0
Bank Sta=5688.3,5692.3
XS Rating Curve= 0 ,0
Exp/Cntr=0.3,0.1

Type RM Length L Ch R = 1 ,151837  ,1384,1384,1384
BEGIN DESCRIPTION:
ELM CREEK 85.0
END DESCRIPTION:
XS GIS Cut Line= 3
        2353975.       13630375.        2354875.       13628575.
      2354725.01     13627975.02
#Sta/Elev= 30
  2987.1   354.6    3152  349.59    3493     343  3747.4  340.35  4074.4  339.21
    4298  336.17  4373.5  336.48  4664.1   333.4  4873.8  329.46  4949.1  329.41
  5002.1  329.13  5009.4   325.5  5009.9     325  5025.8   325.5  5030.5  328.46
  5040.8  328.84  5051.1  326.83  5054.3  327.67  5058.8  328.86  5133.6  333.61
  5288.2  338.13  5435.1  344.96    5484  348.08  5504.6  352.66  5512.4  350.24
  5517.5  350.53  5525.3   348.6  5553.6  351.72  5558.8  351.17    5618  355.55
#Mann= 5 ,-1 , 0
  2987.1     .07       0  4949.1      .1       0  5009.4     .05       0
  5025.8      .1       0  5054.3     .07       0
Bank Sta=5009.4,5025.8
XS Rating Curve= 0 ,0
Exp/Cntr=0.3,0.1

Type RM Length L Ch R = 1 ,150453  ,865,865,865
BEGIN DESCRIPTION:
ELM CREEK 84.0
END DESCRIPTION:
XS GIS Cut Line= 3
      2354424.99     13630525.01        2355525.       13629325.
      2355225.01     13627675.04
#Sta/Elev= 30
  3376.2  354.56  3631.2  346.06  3843.3  341.46  4402.6  334.48  4664.6  334.64
  4763.3     333  4800.9   331.2  4876.8  326.33  4961.9  326.01  4967.1  323.15
  4967.6  322.65    4985  323.15  4990.2  326.18  5004.2  326.69  5054.9  327.59
  5065.1  325.63  5075.2  327.31  5126.1  329.52  5259.5  331.34  5563.1  332.35
  6010.3  337.12  6042.1  337.87  6061.1  340.95  6095.4  338.46  6366.1  344.61
  6457.5  347.77  6484.2   350.8  6498.2  348.21  6542.7  350.92  6681.1  354.75
#Mann= 5 ,-1 , 0
  3376.2     .07       0  4800.9      .1       0  4967.1     .05       0
    4985      .1       0  5004.2     .07       0
Bank Sta=4967.1,4985
XS Rating Curve= 0 ,0
Exp/Cntr=0.3,0.1

Type RM Length L Ch R = 1 ,149588  ,424,424,424
BEGIN DESCRIPTION:
ELM CREEK 83.0
END DESCRIPTION:
XS GIS Cut Line= 3
      2355225.01     13630974.98        2356025.       13629775.
      2355225.01     13627575.04
#Sta/Elev= 30
  3557.5  362.87  3745.3  356.86  3997.7  343.95    4214  339.67  4256.1  335.22
  4314.6   338.3  4616.6  333.93  4718.8     329  4956.1  326.51  5002.4  324.84
  5011.9  321.79  5012.4  321.29  5030.1  321.79  5031.6  324.77  5060.5  324.64
  5105.8  324.56  5670.1  331.69  5803.7  329.73  5840.3  326.87  5936.1  329.02
    5982  327.09  6053.1  330.07  6074.4  328.42  6202.1  329.66  6319.1   334.4
  6904.4  342.24  7060.7  347.44  7096.6  350.59  7138.5  349.15  7340.6  356.48
#Mann= 5 ,-1 , 0
  3557.5     .07       0  5011.9     .05       0  5030.1     .07       0
  5060.5      .1       0  5105.8     .07       0
Bank Sta=5011.9,5030.1
XS Rating Curve= 0 ,0
Exp/Cntr=0.3,0.1

Type RM Length L Ch R = 1 ,149164  ,437,437,437
BEGIN DESCRIPTION:
ELM CREEK 82.0
END DESCRIPTION:
XS GIS Cut Line= 3
      2355824.99     13630525.01        2356325.       13629925.
        2355925.       13627725.
#Sta/Elev= 30
  4219.4  345.43  4347.6  338.41  4475.2  332.74  4719.3  328.78  4830.6   327.1
  4837.1  325.55  4851.4  324.59  4857.9  326.69  4865.7  325.52  4872.2  326.69
  4886.5  323.93  4891.7  321.69  4892.2  321.19    4910  321.69  4915.2  323.13
  4929.5  323.55  4993.3  323.33  5020.8  321.83  5027.1  322.68  5041.1  322.29
  5138.9     325    5144  324.35  5192.3  326.35  5197.4  325.48  5200.3  326.11
  5250.7  329.33    5468  332.22  6270.9  334.98    7098  341.72  7236.5   343.6
#Mann= 5 ,-1 , 0
  4219.4     .07       0  4719.3      .1       0  4891.7     .05       0
    4910      .1       0  5200.3     .07       0
Bank Sta=4891.7,4910
XS Rating Curve= 0 ,0
Exp/Cntr=0.3,0.1

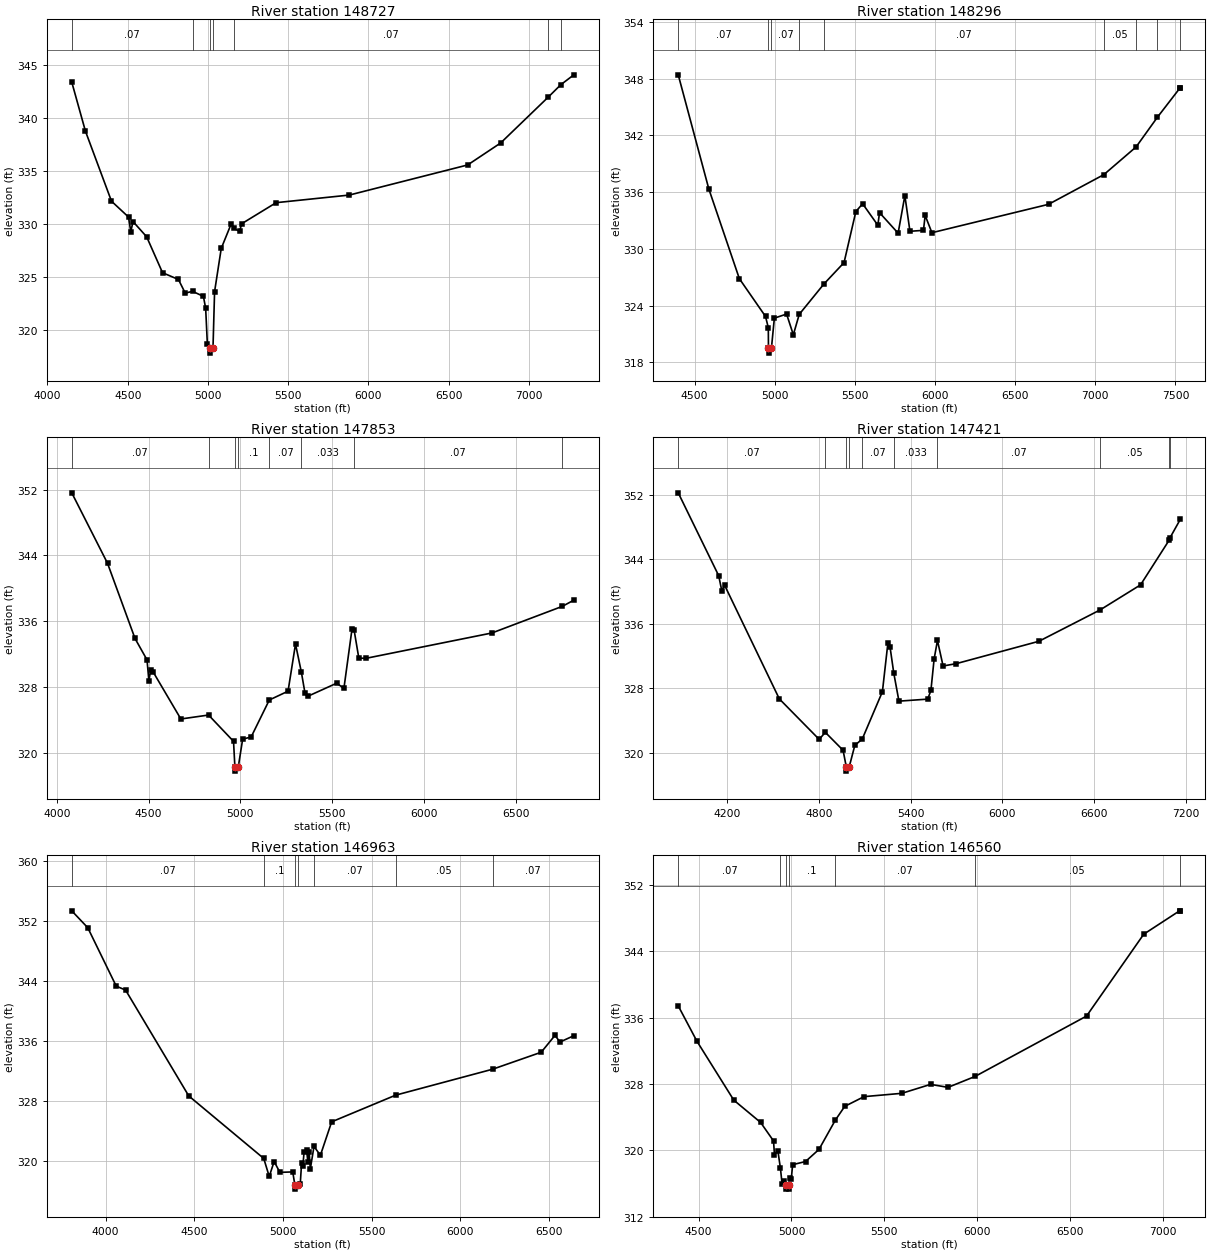
Type RM Length L Ch R = 1 ,148727  ,431,431,431
BEGIN DESCRIPTION:
ELM CREEK 81.0
END DESCRIPTION:
XS GIS Cut Line= 3
      2356074.99     13630675.01        2356675.       13630075.
        2356075.     13627874.99
#Sta/Elev= 30
  4151.3  343.42  4236.2  338.79  4398.8  332.15  4504.9  330.65    4519  329.27
  4533.1  330.22    4618  328.78    4717  325.38    4816  324.74  4858.4  323.45
  4904.1  323.62  4971.6  323.14  4985.7  322.02  4996.3  318.63  5013.1  318.27
  5013.6  317.77  5031.4  318.27  5041.3  323.59  5082.8  327.68    5145  330.01
  5159.3  329.59  5196.8   329.3  5210.6  330.02  5424.8  332.01  5880.9  332.73
  6618.5  335.58  6824.1  337.66  7119.2  341.98  7199.4  343.18  7280.2  344.11
#Mann= 7 ,-1 , 0
  4151.3     .07       0  4904.1      .1       0  5013.1     .05       0
  5031.4      .1       0  5159.3     .07       0  7119.2     .05       0
  7199.4     .07       0
Bank Sta=5013.1,5031.4
XS Rating Curve= 0 ,0
Exp/Cntr=0.3,0.1

Type RM Length L Ch R = 1 ,148296  ,443,443,443
BEGIN DESCRIPTION:
ELM CREEK 80.0
END DESCRIPTION:
XS GIS Cut Line= 3
        2356925.       13630875.        2356975.       13630275.
        2356175.       13627875.
#Sta/Elev= 30
  4398.5   348.4  4589.2  336.34  4779.8  326.85  4942.9  322.86  4960.4  321.67
  4961.3  319.48  4961.8  318.98  4979.7  319.48  4998.1  322.68  5074.4  323.11
  5116.5  320.92  5153.3  323.08  5307.3  326.29  5432.8  328.55  5506.5  333.95
  5548.7  334.77  5643.6   332.5  5654.1  333.83  5770.1  331.66  5812.2  335.63
  5843.9  331.86  5928.2  331.96  5938.7  333.54  5980.9  331.71  6708.2  334.71
  7053.5  337.85  7254.7  340.78  7387.7  343.92  7529.7  347.04  7530.4  347.03
#Mann= 9 ,-1 , 0
  4398.5     .07       0  4961.3     .05       0  4979.7     .07       0
  5153.3      .1       0  5307.3     .07       0  7053.5     .05       0
  7254.7     .07       0  7387.7     .05       0  7529.7     .07       0
Bank Sta=4961.3,4979.7
XS Rating Curve= 0 ,0
Exp/Cntr=0.3,0.1

Type RM Length L Ch R = 1 ,147853  ,432,432,432
BEGIN DESCRIPTION:
ELM CREEK 79.0
END DESCRIPTION:
XS GIS Cut Line= 3
        2357425.     13630824.99        2357225.       13629925.
        2356475.     13628275.01
#Sta/Elev= 30
  4081.8  351.62  4276.4  343.06  4426.2  333.91  4491.6  331.31  4501.8  328.76
    4512  330.12  4523.6  329.89  4675.9  324.12  4826.8   324.6  4962.8   321.4
  4970.2  318.28  4970.7  317.78  4988.6  318.28  5012.5  321.67  5058.7  321.93
  5157.6  326.43  5259.7   327.5  5300.3  333.23  5332.1  329.83    5352  327.26
  5366.2  326.87  5524.4  328.47    5564  327.85  5607.9  335.04  5619.2  334.96
  5645.2  331.52  5684.8   331.5  6370.2  334.58  6753.9  337.82  6816.2  338.57
#Mann= 8 ,-1 , 0
  4081.8     .07       0  4826.8      .1       0  4970.2     .05       0
  4988.6      .1       0  5157.6     .07       0  5332.1    .033       0
  5619.2     .07       0  6753.9     .05       0
Bank Sta=4970.2,4988.6
XS Rating Curve= 0 ,0
Exp/Cntr=0.3,0.1

Type RM Length L Ch R = 1 ,147421  ,458,458,458
BEGIN DESCRIPTION:
ELM CREEK 78.0
END DESCRIPTION:
XS GIS Cut Line= 3
        2357725.       13630825.        2357525.       13629725.
      2356324.98     13627924.97
#Sta/Elev= 30
  3881.7  352.21    4146  341.96  4166.3   340.1  4185.4  340.75  4542.4  326.71
  4802.8   321.7  4842.9  322.57  4959.1  320.35  4980.3  318.27  4980.8  317.77
  4998.8  318.27  5035.8  320.96  5084.3  321.74  5216.1   327.6  5252.1  333.65
  5265.6  333.18  5290.4   329.9  5324.2  326.43    5512  326.68  5533.1  327.75
  5554.1  331.65  5575.9  333.94  5612.7  330.78  5698.3  331.07  6239.1  333.84
    6639  337.72  6903.2  340.82  7089.1  346.32  7093.8  346.58  7163.1  348.93
#Mann= 10 ,-1 , 0
  3881.7     .07       0  4842.9      .1       0  4980.3     .05       0
  4998.8      .1       0  5084.3     .07       0  5290.4    .033       0
  5575.9     .07       0    6639     .05       0  7089.1     .07       0
  7093.8     .05       0
Bank Sta=4980.3,4998.8
XS Rating Curve= 0 ,0
Exp/Cntr=0.3,0.1

Type RM Length L Ch R = 1 ,146963  ,403,403,403
BEGIN DESCRIPTION:
ELM CREEK 77.0
END DESCRIPTION:
XS GIS Cut Line= 3
        2357775.     13630824.97        2357875.       13629625.
      2356775.01     13628425.01
#Sta/Elev= 30
  3809.1  353.33  3899.4  351.08  4059.9  343.31  4112.6  342.79  4468.9  328.71
    4892  320.39  4922.9  317.99  4950.5  319.98  4983.1  318.54  5055.5   318.6
  5067.8  316.81  5068.3  316.31  5086.3  316.81    5098  317.05  5105.4  319.74
  5112.2  319.32  5119.6  321.27  5133.8  321.53  5140.6  319.94    5148  321.28
  5154.7     319  5175.4  321.99  5211.5  320.81    5275  325.26    5636  328.81
  6182.7  332.26  6457.1  334.52  6534.7  336.76  6563.1  335.88  6641.1  336.72
#Mann= 7 ,-1 , 0
  3809.1     .07       0    4892      .1       0  5067.8     .05       0
  5086.3      .1       0  5175.4     .07       0    5636     .05       0
  6182.7     .07       0
Bank Sta=5067.8,5086.3
XS Rating Curve= 0 ,0
Exp/Cntr=0.3,0.1

Type RM Length L Ch R = 1 ,146560  ,485,485,485
BEGIN DESCRIPTION:
ELM CREEK 76.0
END DESCRIPTION:
XS GIS Cut Line= 3
        2358275.     13630224.99        2358125.       13629625.
      2357075.01     13627825.02
#Sta/Elev= 30
  4390.5  337.43    4491  333.17  4689.4  326.06  4833.7  323.37  4903.3  321.14
  4908.5  319.47  4926.5  319.98  4940.6  317.83  4949.7  315.89  4957.4  316.35
  4968.8  315.82  4969.3  315.32  4986.8  315.32  4987.3  315.82  4990.9  316.67
  4998.6  316.51  5006.4  318.27  5075.5  318.65  5147.9  320.11  5236.2  323.65
  5286.8  325.31  5390.6  326.48    5594  326.88  5748.6  327.96  5842.5   327.6
  5987.5  328.91    6588   336.2    6896  346.08  7088.8   348.9  7092.8   348.9
#Mann= 7 ,-1 , 0
  4390.5     .07       0  4940.6      .1       0  4968.8     .05       0
  4987.3      .1       0  5236.2     .07       0  5987.5     .05       0
  7088.8     .07       0
Bank Sta=4968.8,4987.3
XS Rating Curve= 0 ,0
Exp/Cntr=0.3,0.1

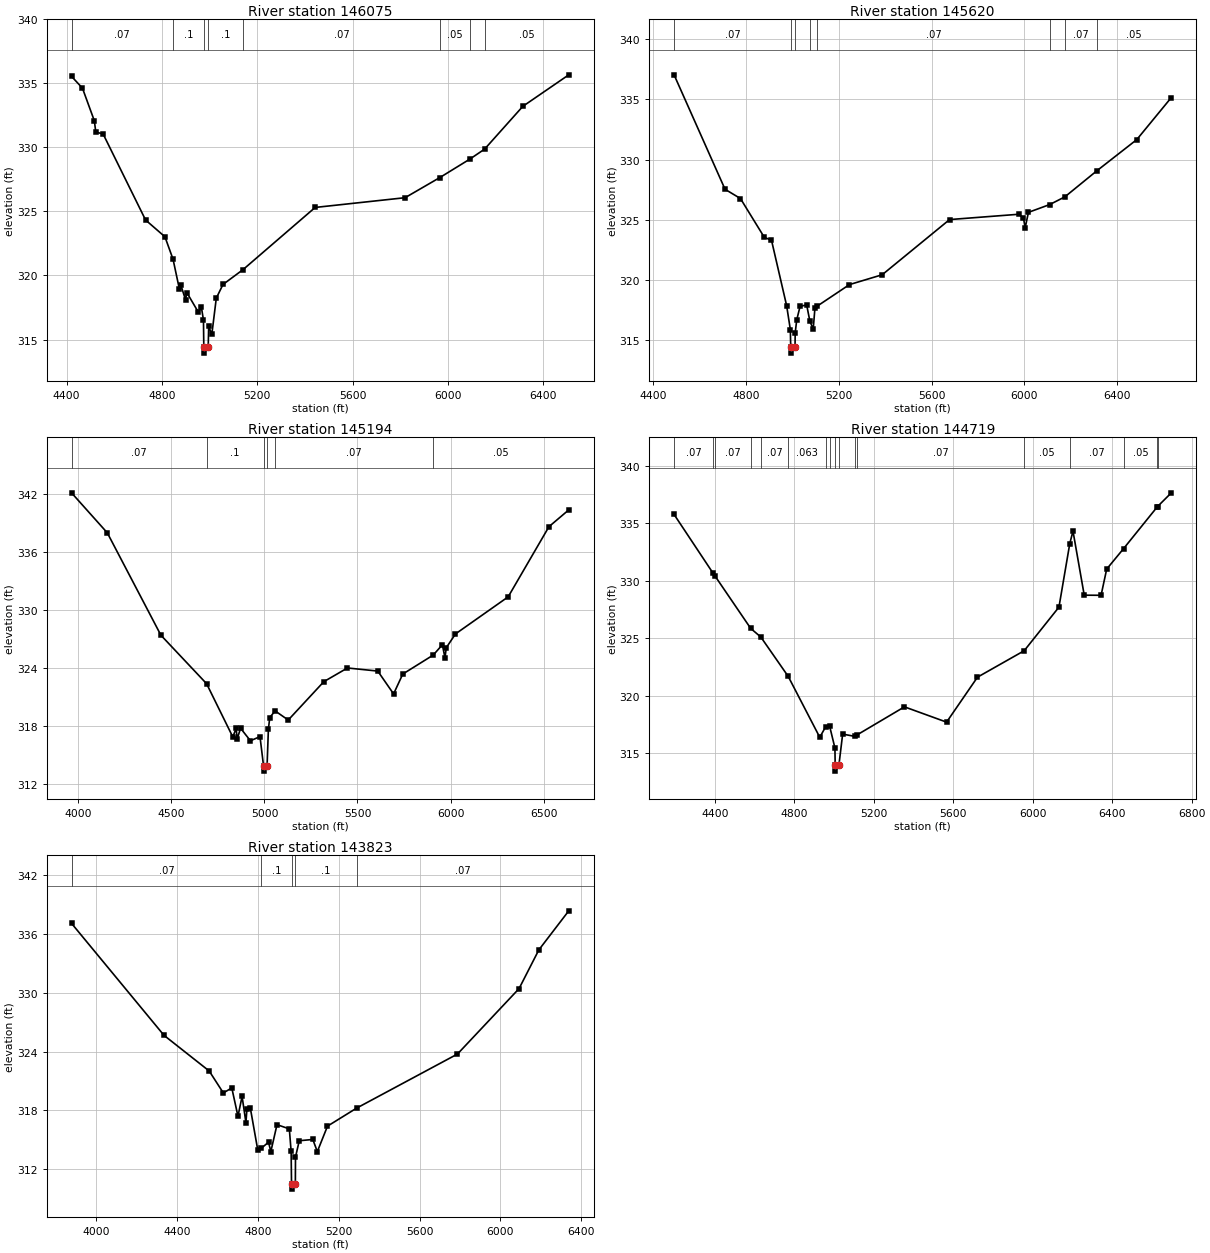
Type RM Length L Ch R = 1 ,146075  ,455,455,455
BEGIN DESCRIPTION:
ELM CREEK 75.0
END DESCRIPTION:
XS GIS Cut Line= 3
      2358624.99     13630024.96        2358425.       13629475.
        2357525.       13628275.
#Sta/Elev= 30
  4420.9  335.54  4466.7  334.62  4516.6  332.07  4522.6  331.19  4553.2  331.05
  4731.4  324.33  4812.6  323.02  4846.7  321.26  4873.1  318.95  4879.1  319.26
    4899   318.1  4904.3  318.67  4952.9  317.13  4965.5  317.52  4974.2  316.52
  4975.6  314.44  4976.1  313.94  4994.1  314.44  4996.1  316.03  5009.2   315.4
    5028  318.23  5056.1   319.3  5140.3  320.46  5442.6  325.31  5819.6  326.07
  5965.2  327.64  6091.1  329.08  6153.1  329.86  6313.4   333.2  6506.1  335.66
#Mann= 8 ,-1 , 0
  4420.9     .07       0  4846.7      .1       0  4975.6     .05       0
  4994.1      .1       0  5140.3     .07       0  5965.2     .05       0
  6091.1     .07       0  6153.1     .05       0
Bank Sta=4975.6,4994.1
XS Rating Curve= 0 ,0
Exp/Cntr=0.3,0.1

Type RM Length L Ch R = 1 ,145620  ,426,426,426
BEGIN DESCRIPTION:
ELM CREEK 74.0
END DESCRIPTION:
XS GIS Cut Line= 3
      2359024.99     13629924.99        2358775.       13629475.
      2357675.03     13628275.03
#Sta/Elev= 30
  4490.1  337.05  4709.7  327.53  4776.1  326.76    4879  323.53  4909.9  323.29
  4975.1  317.85  4991.1  315.86  4992.7   314.4  4993.2   313.9  5011.3   314.4
    5012  315.58  5018.7  316.67  5032.9  317.78  5061.3  317.92  5075.5  316.54
  5089.7  315.91    5097  317.63  5107.7  317.82  5245.7   319.6  5386.9  320.42
  5677.3  325.01  5974.5  325.45  5995.5  325.16  6002.9  324.32    6017  325.61
  6108.9  326.26  6174.1   326.9  6311.4  329.06  6483.8  331.66  6632.7  335.16
#Mann= 8 ,-1 , 0
  4490.1     .07       0  4992.7     .05       0  5011.3     .07       0
  5075.5      .1       0  5107.7     .07       0  6108.9     .05       0
  6174.1     .07       0  6311.4     .05       0
Bank Sta=4992.7,5011.3
XS Rating Curve= 0 ,0
Exp/Cntr=0.3,0.1

Type RM Length L Ch R = 1 ,145194  ,475,475,475
BEGIN DESCRIPTION:
ELM CREEK 73.0
END DESCRIPTION:
XS GIS Cut Line= 3
      2359174.99     13630124.96        2358875.       13629125.
      2357774.98     13627924.98
#Sta/Elev= 30
  3963.4  342.16  4155.6  338.01  4443.6  327.39  4689.1  322.36  4829.9  316.84
  4848.2  317.72  4853.4  316.61  4871.7  317.74  4924.7  316.44  4976.1  316.87
  4995.5  313.79    4996  313.29  5014.1  313.79  5021.3  317.66  5028.7  318.85
  5057.3  319.54  5127.9  318.59  5319.1  322.57  5446.1  323.99  5608.9  323.67
    5694   321.3  5743.3  323.36    5907  325.33  5956.1   326.4  5970.2  325.04
    5977  326.09  6026.4  327.52  6309.7  331.37  6528.9  338.65  6635.3  340.39
#Mann= 6 ,-1 , 0
  3963.4     .07       0  4689.1      .1       0  4995.5     .05       0
  5014.1      .1       0  5057.3     .07       0    5907     .05       0
Bank Sta=4995.5,5014.1
XS Rating Curve= 0 ,0
Exp/Cntr=0.3,0.1

Type RM Length L Ch R = 1 ,144719  ,896,896,896
BEGIN DESCRIPTION:
ELM CREEK 72.0
END DESCRIPTION:
XS GIS Cut Line= 3
        2359675.     13629725.01        2359275.       13629025.
      2358074.99     13627824.99
#Sta/Elev= 30
  4194.3  335.78  4391.4  330.65  4400.3  330.43  4580.1  325.87  4631.1  325.12
  4768.8   321.7  4927.8   316.4  4957.5  317.32  4977.3  317.38  5004.1  315.47
  5005.4  313.96  5005.9  313.46    5024  313.96    5043  316.68  5104.9  316.48
  5113.6  316.59  5354.1  319.05  5566.2  317.72  5721.8  321.63    5957  323.93
  6131.9  327.72  6186.5  333.25  6202.6  334.33  6259.2  328.76    6344  328.75
  6372.3  331.03  6456.9   332.8  6627.9  336.46  6628.5  336.47  6697.6  337.66
#Mann= 17 ,-1 , 0
  4194.3     .07       0  4391.4    .035       0  4400.3     .07       0
  4580.1    .063       0  4631.1     .07       0  4768.8    .063       0
  4957.5      .1       0  4977.3    .063       0  5005.4     .05       0
    5024    .063       0  5104.9      .1       0  5113.6     .07       0
    5957     .05       0  6186.5     .07       0  6456.9     .05       0
  6627.9     .07       0  6628.5     .05       0
Bank Sta=5005.4,5024
XS Rating Curve= 0 ,0
Exp/Cntr=0.3,0.1

Type RM Length L Ch R = 1 ,143823  ,478,478,478
BEGIN DESCRIPTION:
ELM CREEK 71.0
END DESCRIPTION:
XS GIS Cut Line= 3
      2359725.01     13629775.05        2359525.       13628675.
      2358925.01     13627475.02
#Sta/Elev= 30
  3878.6   337.1    4336  325.67  4559.6  322.03  4629.5  319.79  4671.4   320.3
  4701.9  317.41  4722.3  319.43  4741.3  316.77  4746.4  318.17  4762.9  318.27
  4799.8  313.97  4816.5  314.13  4853.1  314.76  4864.6  313.81    4895  316.55
    4956  316.12  4964.9  313.82  4966.9  310.47  4967.4  309.97  4985.8  310.47
  4986.5  313.24  5005.1  314.91  5072.2  315.04  5094.5   313.8  5144.8   316.4
  5288.9  318.24  5787.7  323.76  6092.4  330.44  6190.2  334.39  6338.3  338.38
#Mann= 5 ,-1 , 0
  3878.6     .07       0  4816.5      .1       0  4966.9     .05       0
  4985.8      .1       0  5288.9     .07       0
Bank Sta=4966.9,4985.8
XS Rating Curve= 0 ,0
Exp/Cntr=0.3,0.1