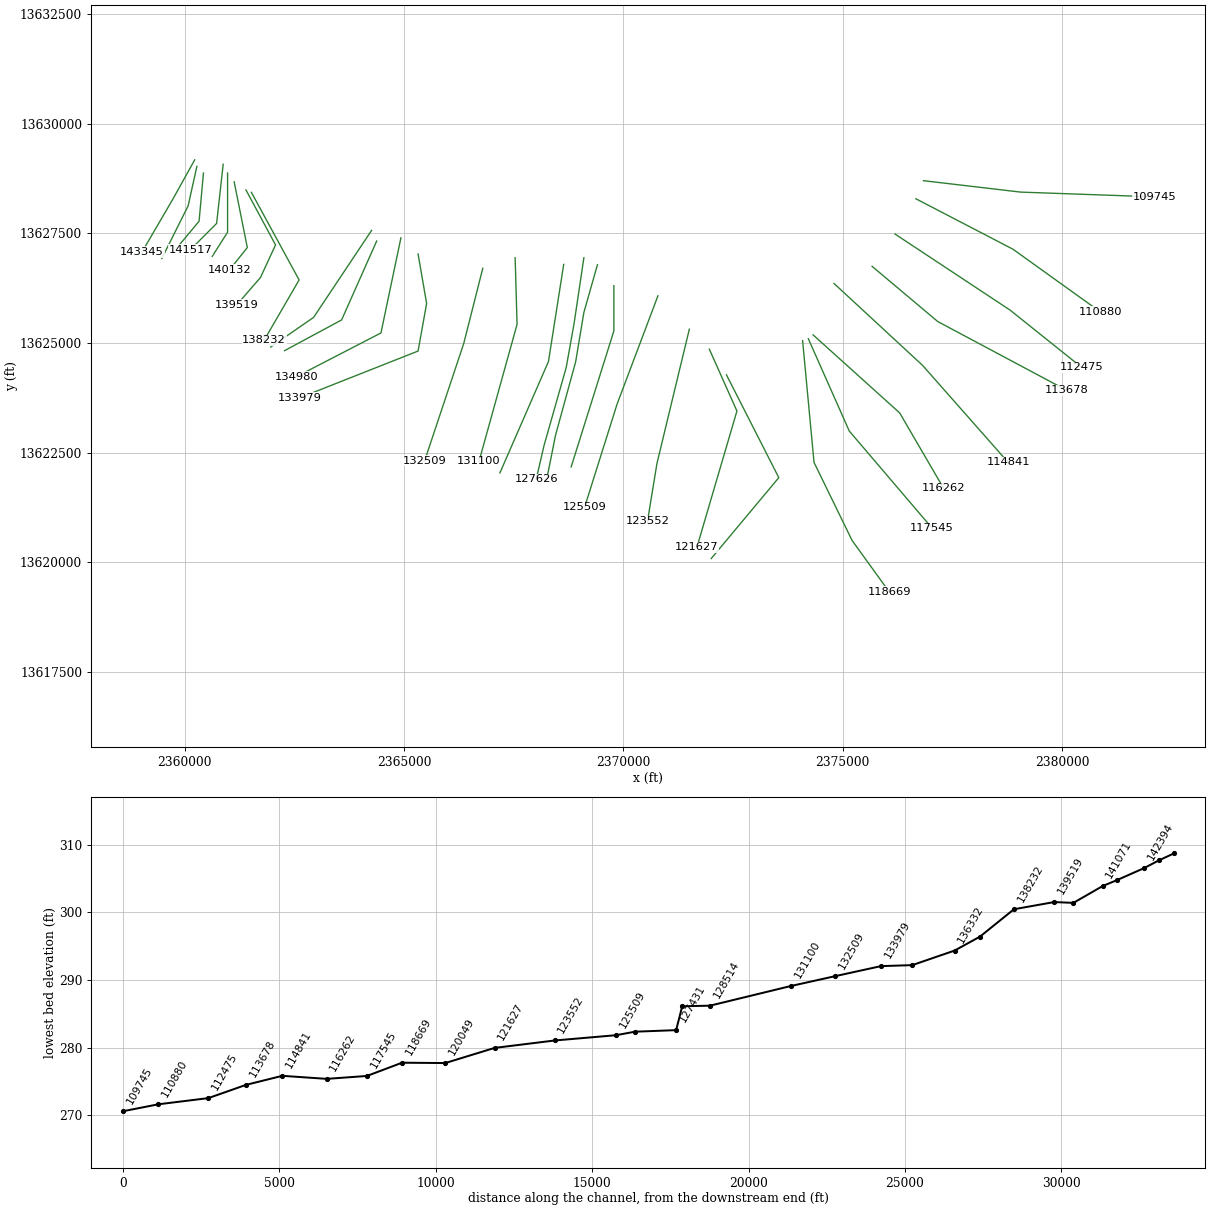
HEC-RAS study ELM CREEK.prj: ELM CREEK Base Level Engineering

--- ELM CREEK.g01 (geometry) --- (continued)

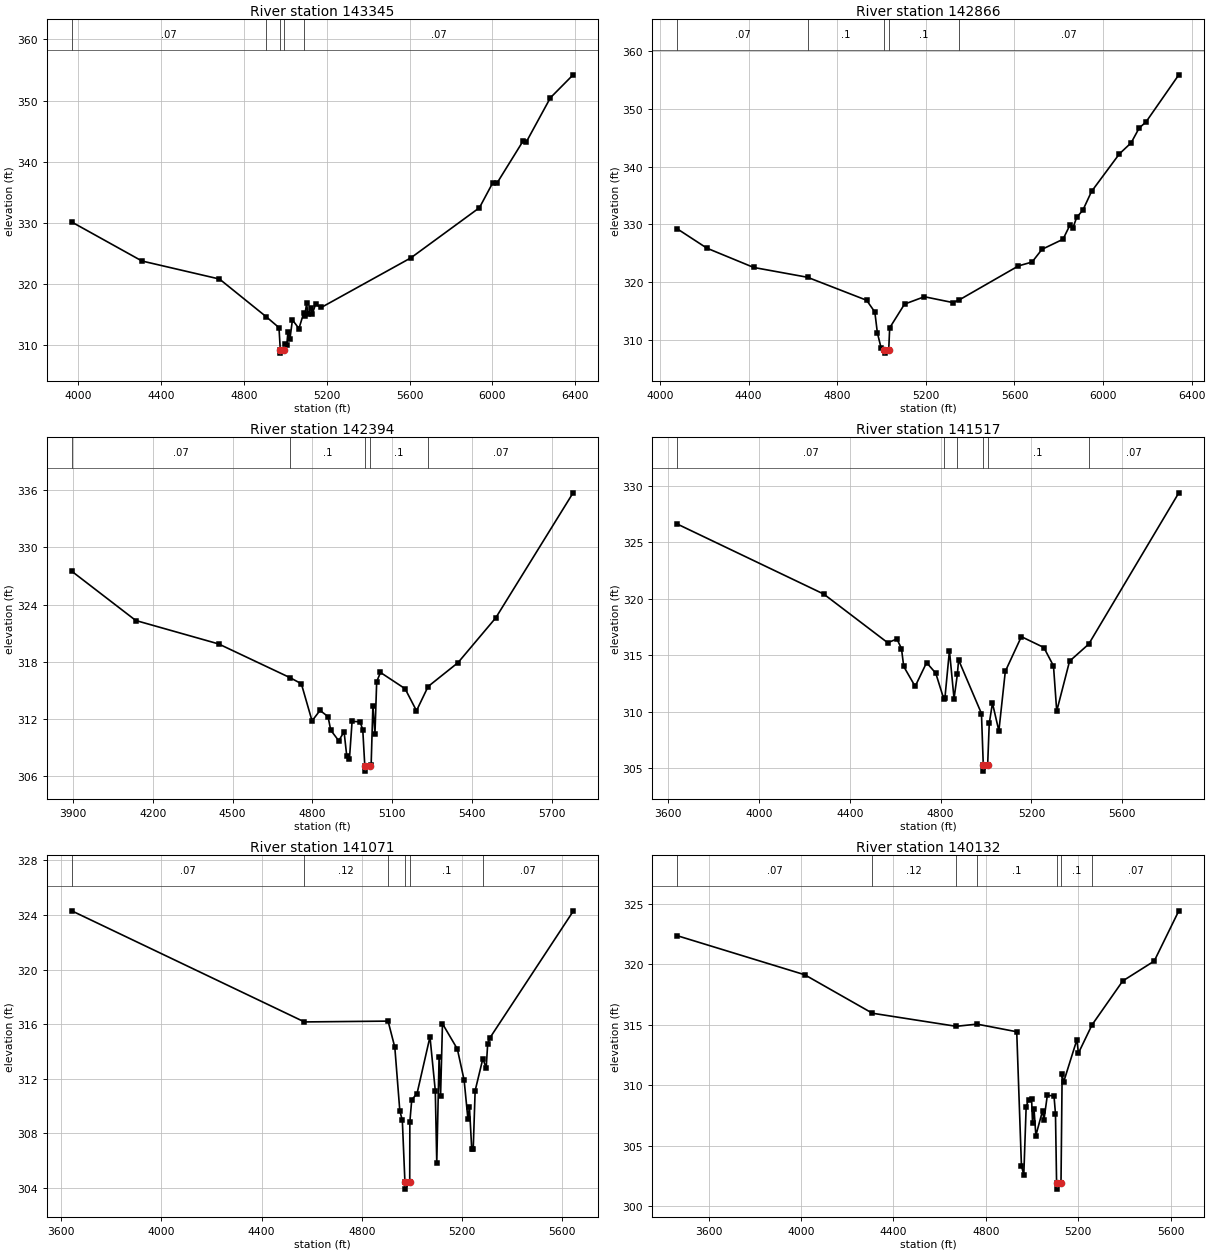
Type RM Length L Ch R = 1 ,143345  ,479,479,479
BEGIN DESCRIPTION:
ELM CREEK 70.0
END DESCRIPTION:
XS GIS Cut Line= 3
        2360225.       13629175.        2359725.       13628275.
      2359025.01     13627075.01
#Sta/Elev= 30
  3970.4  330.16    4309  323.79  4683.1  320.84    4910  314.64  4970.2   312.9
  4976.7  309.23  4977.2  308.73  4995.7  309.23  4997.1  310.24  5007.8  310.05
  5013.6  312.24  5023.1  311.06  5035.1  314.16  5066.5  312.75  5089.1  315.24
  5093.8  314.73  5103.7  316.85  5109.5  315.09  5125.2  316.15    5131  315.16
  5146.7  316.71    5174  316.19  5606.5   324.3  5937.3   332.5  6001.8  336.59
  6023.3  336.59  6146.5  343.33  6162.2  343.17  6279.6  350.47  6389.2  354.22
#Mann= 5 ,-1 , 0
  3970.4     .07       0    4910      .1       0  4976.7     .05       0
  4995.7      .1       0  5089.1     .07       0
Bank Sta=4976.7,4995.7
XS Rating Curve= 0 ,0
Exp/Cntr=0.3,0.1

Type RM Length L Ch R = 1 ,142866  ,472,472,472
BEGIN DESCRIPTION:
ELM CREEK 69.0
END DESCRIPTION:
XS GIS Cut Line= 3
      2360274.99     13629024.98        2360075.       13628125.
      2359474.99     13626924.97
#Sta/Elev= 30
  4078.5  329.21  4211.6  325.88  4422.9  322.54  4665.8  320.84  4932.6  316.86
  4969.7  314.82  4981.2  311.21  4997.9  308.61  5013.3   308.2  5013.8   307.7
  5032.3   308.2  5036.8  312.08  5103.8  316.19  5193.3  317.47  5321.9  316.46
  5349.5  316.89  5618.1  322.81  5679.6  323.48  5724.4  325.68  5819.4  327.43
  5850.1  329.85  5864.1  329.39  5880.9  331.21  5908.8  332.45    5948   335.7
  6073.7  342.21  6126.8  344.13  6163.2   346.7  6193.9  347.74  6342.1  355.91
#Mann= 5 ,-1 , 0
  4078.5     .07       0  4665.8      .1       0  5013.3     .05       0
  5032.3      .1       0  5349.5     .07       0
Bank Sta=5013.3,5032.3
XS Rating Curve= 0 ,0
Exp/Cntr=0.3,0.1

Type RM Length L Ch R = 1 ,142394  ,877,877,877
BEGIN DESCRIPTION:
ELM CREEK 68.0
END DESCRIPTION:
XS GIS Cut Line= 3
        2360425.     13628874.98        2360325.       13627775.
      2359825.03     13627175.03
#Sta/Elev= 30
  3895.4  327.49  4136.4  322.33  4447.6  319.88  4716.1  316.35  4758.9  315.71
  4799.1  311.82  4829.2  312.92  4859.3  312.26  4869.4  310.85  4899.5  309.74
  4919.6  310.68  4929.6  308.16  4939.7  307.82  4949.7  311.77  4979.8  311.73
  4989.9  310.88  4997.6  307.06  4998.1  306.56  5016.6  307.06  5021.4  307.23
  5027.9  313.39  5035.7  310.46  5042.2  315.93  5056.5  316.89    5149  315.19
  5191.9  312.88  5235.6  315.42  5348.1  317.92    5490  322.61  5780.9   335.7
#Mann= 5 ,-1 , 0
  3895.4     .07       0  4716.1      .1       0  4997.6     .05       0
  5016.6      .1       0  5235.6     .07       0
Bank Sta=4997.6,5016.6
XS Rating Curve= 0 ,0
Exp/Cntr=0.3,0.1

Type RM Length L Ch R = 1 ,141517  ,446,446,446
BEGIN DESCRIPTION:
ELM CREEK 67.0
END DESCRIPTION:
XS GIS Cut Line= 3
        2360875.     13629075.02        2360725.       13627725.
      2360124.97     13627124.97
#Sta/Elev= 30
  3641.6  326.62  4285.6  320.43  4567.3  316.12  4607.5  316.46  4627.7  315.61
  4637.7  314.02    4688  312.26  4738.3  314.36  4778.6  313.43  4813.5  311.18
  4818.8  311.19  4838.9  315.43  4859.1  311.17  4873.7  313.32  4879.2   314.6
  4979.8  309.86  4987.9  305.26  4988.4  304.76    5007  305.26  5014.1  308.98
  5028.2  310.78  5056.5  308.32  5084.8  313.59  5155.5  316.66  5254.5   315.7
  5296.9  314.07  5311.1  310.07  5367.6  314.49  5451.9     316  5848.5  329.39
#Mann= 6 ,-1 , 0
  3641.6     .07       0  4813.5     .12       0  4873.7      .1       0
  4987.9     .05       0    5007      .1       0  5451.9     .07       0
Bank Sta=4987.9,5007
XS Rating Curve= 0 ,0
Exp/Cntr=0.3,0.1

Type RM Length L Ch R = 1 ,141071  ,939,939,939
BEGIN DESCRIPTION:
ELM CREEK 66.0
END DESCRIPTION:
XS GIS Cut Line= 3
        2360975.     13628874.96        2360975.       13627525.
      2360624.99     13626974.98
#Sta/Elev= 30
  3641.6   324.3  4570.7  316.16  4904.7  316.22  4931.6   314.3  4951.6  309.64
  4961.6  308.95    4972  304.41  4972.5  303.91  4991.1  304.41  4991.6  308.83
  4999.2  310.46  5020.3  310.91    5072  315.07  5093.2  311.12  5099.1  305.85
  5108.4   313.6  5114.3  310.74  5121.9  316.03  5181.2  314.18  5208.3   311.9
  5223.5  309.05  5229.5  309.93  5238.8  306.82  5244.7  306.86  5252.3  311.12
  5283.3  313.48  5296.4  312.77  5302.3  314.53  5311.6     315  5643.5  324.26
#Mann= 6 ,-1 , 0
  3641.6     .07       0  4570.7     .12       0  4904.7      .1       0
    4972     .05       0  4991.1      .1       0  5283.3     .07       0
Bank Sta=4972,4991.1
XS Rating Curve= 0 ,0
Exp/Cntr=0.3,0.1

Type RM Length L Ch R = 1 ,140132  ,613,613,613
BEGIN DESCRIPTION:
ELM CREEK 65.0
END DESCRIPTION:
XS GIS Cut Line= 3
        2361125.       13628675.        2361425.       13627175.
      2361025.01     13626675.02
#Sta/Elev= 30
  3465.3  322.34    4016  319.12  4309.1  315.94  4671.7  314.86  4762.1  315.04
  4933.8  314.41  4954.2  303.32  4964.4   302.6  4974.6   308.2  4984.8  308.81
  4998.2  308.84  5002.2  306.87  5008.6  308.03  5016.6  305.84  5045.4  307.87
  5051.8  307.15  5066.2  309.16  5095.1  309.11  5101.5  307.63  5106.3  301.91
  5106.8  301.41  5125.4  301.91  5130.3  310.88  5136.7  310.25  5194.3  313.76
  5200.7  312.64  5259.7  314.98  5392.8  318.61  5528.9  320.25  5635.3   324.4
#Mann= 7 ,-1 , 0
  3465.3     .07       0  4309.1     .12       0  4671.7     .07       0
  4762.1      .1       0  5106.3     .05       0  5125.4      .1       0
  5259.7     .07       0
Bank Sta=5106.3,5125.4
XS Rating Curve= 0 ,0
Exp/Cntr=0.3,0.1

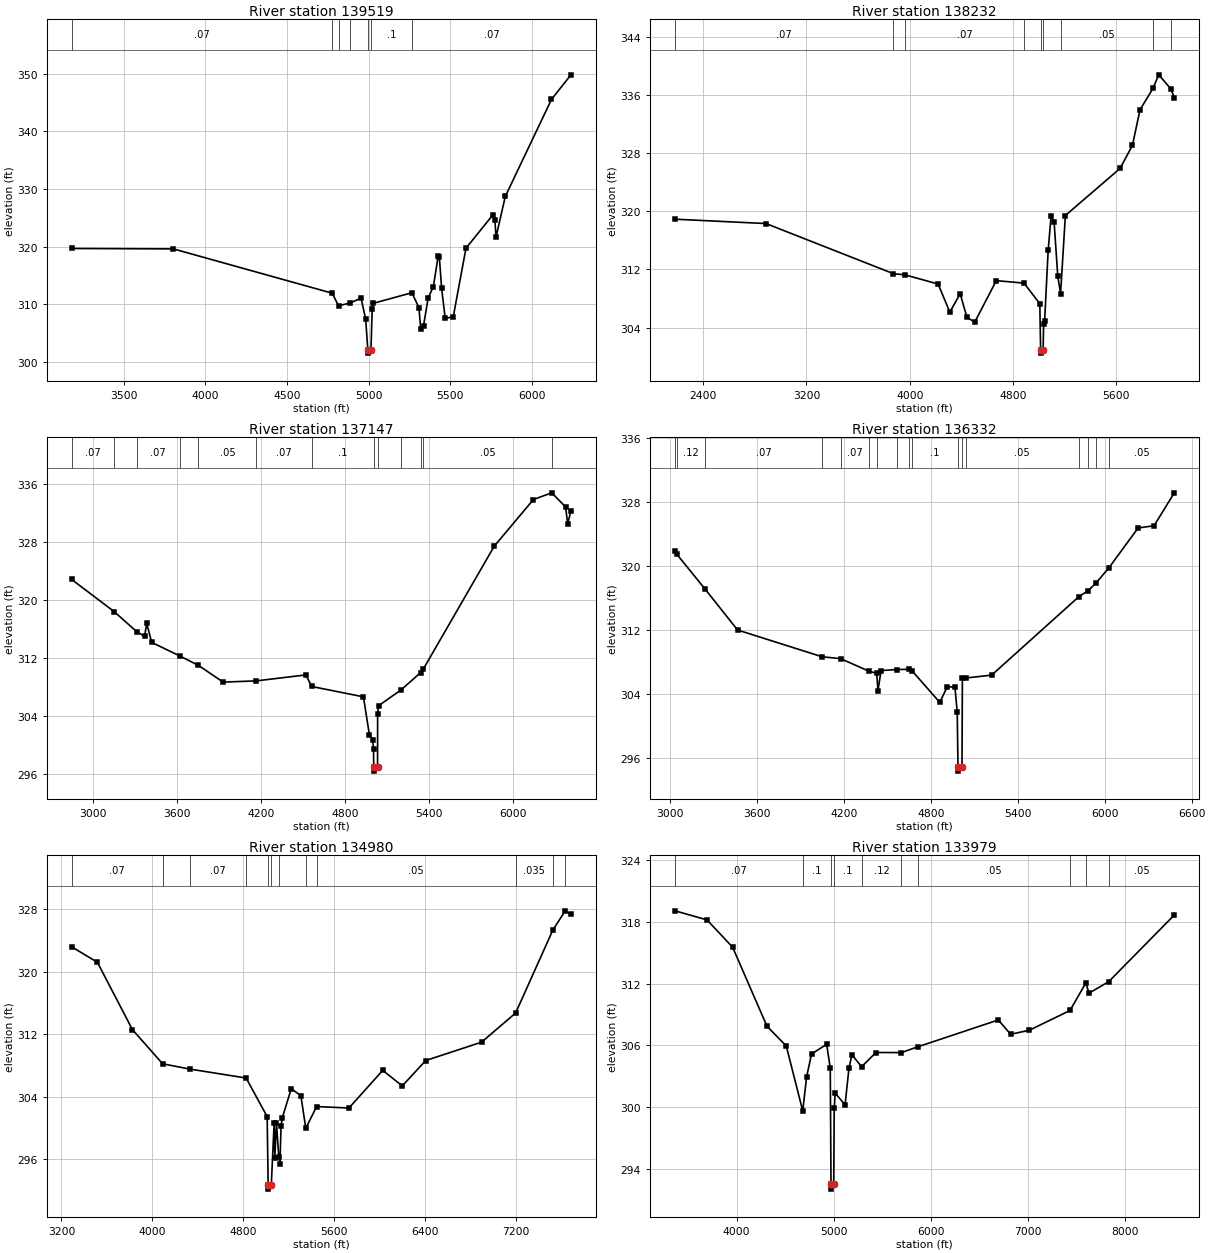
Type RM Length L Ch R = 1 ,139519  ,1287,1287,1287
BEGIN DESCRIPTION:
X19128
END DESCRIPTION:
XS GIS Cut Line= 4
      2361394.06     13628488.62       2362068.8     13627235.54
      2361724.55     13626491.95      2361188.75     13625873.73
#Sta/Elev= 30
  3179.4  319.69  3803.1  319.62  4776.9  311.93  4815.6  309.75    4884  310.21
  4953.5  311.08    4982  307.43  4995.3  302.03  4995.8  301.53  5014.4  302.03
  5021.9  309.21  5027.8  310.17  5265.1  312.01  5308.4  309.43  5319.5  305.71
  5336.8  306.31  5365.2  311.13  5396.6  313.03  5426.8  318.43  5433.4  318.26
  5447.6  312.75  5469.5  307.57  5518.9  307.83  5596.8  319.74  5760.1  325.46
  5774.4  324.56    5781  321.67    5838  328.73    6121  345.56  6240.1  349.83
#Mann= 7 ,-1 , 0
  3179.4     .07       0  4776.9      .1       0  4815.6     .07       0
    4884      .1       0  4995.3     .05       0  5014.4      .1       0
  5265.1     .07       0
Bank Sta=4995.3,5014.4
XS Rating Curve= 0 ,0
Exp/Cntr=0.3,0.1

Type RM Length L Ch R = 1 ,138232  ,1085,1085,1085
BEGIN DESCRIPTION:
ELM CREEK 64.0
END DESCRIPTION:
XS GIS Cut Line= 3
        2361518.     13628433.54      2362605.83     13626436.87
      2361807.19     13625059.89
#Sta/Elev= 30
  2182.8  318.93  2887.2  318.33  3873.8  311.42  3964.2  311.26  4219.9  309.99
  4310.7  306.11  4390.4  308.67    4443  305.39  4503.6  304.75  4670.1  310.46
    4885  310.12  5007.1  307.28  5013.3  300.97  5013.8  300.47  5032.5  300.97
  5036.8  304.53  5044.4  304.89  5071.7  314.62  5094.6  319.39  5117.7  318.58
  5146.2  311.07  5167.9  308.68    5205  319.44  5628.2  325.92  5724.2   329.1
    5783  334.01  5883.8  336.98  5927.9  338.83  6021.6   336.9  6048.4  335.67
#Mann= 9 ,-1 , 0
  2182.8     .07       0  3873.8     .12       0  3964.2     .07       0
    4885      .1       0  5013.3     .05       0  5032.5      .1       0
  5167.9     .05       0  5883.8     .07       0  6021.6    .035       0
Bank Sta=5013.3,5032.5
XS Rating Curve= 0 ,0
Exp/Cntr=0.3,0.1

Type RM Length L Ch R = 1 ,137147  ,815,815,815
BEGIN DESCRIPTION:
ELM CREEK 63.0
END DESCRIPTION:
XS GIS Cut Line= 3
      2364258.25     13627566.03      2362936.32     13625583.13
      2361958.68     13624908.42
#Sta/Elev= 30
  2845.8  322.82  3149.3   318.4  3311.9  315.62  3367.6  314.98  3382.7  316.76
  3418.7  314.15  3618.5  312.29  3753.1  310.98  3929.5  308.68  4166.7  308.85
  4521.4  309.67  4562.7  308.08  4933.1  306.65  4975.1  301.46  4998.3  300.73
  5005.2  299.53  5006.4  296.92  5006.9  296.42  5033.9  296.92  5034.4  304.33
  5041.2  305.43  5202.1  307.61    5342  309.99  5361.9   310.5  5868.3   327.4
  6148.9  333.83  6279.6  334.75  6378.8  332.81  6393.7  330.49  6416.8  332.25
#Mann= 13 ,-1 , 0
  2845.8     .07       0  3149.3     .12       0  3311.9     .07       0
  3618.5     .12       0  3753.1     .05       0  4166.7     .07       0
  4562.7      .1       0  5006.4     .05       0  5033.9      .1       0
  5202.1     .07       0    5342      .1       0  5361.9     .05       0
  6279.6    .035       0
Bank Sta=5006.4,5033.9
XS Rating Curve= 0 ,0
Exp/Cntr=0.3,0.1

Type RM Length L Ch R = 1 ,136332  ,1352,1352,1352
BEGIN DESCRIPTION:
ELM CREEK 62.0
END DESCRIPTION:
XS GIS Cut Line= 3
      2364375.01     13627325.01        2363575.       13625525.
      2362274.97     13624824.99
#Sta/Elev= 30
  3033.9   321.8  3047.6  321.41  3241.3  317.09  3465.5  311.98  4049.6  308.63
    4177   308.4  4372.6  306.83  4426.1  306.57  4434.6  304.41  4456.5  306.91
  4566.6  307.04  4648.8  307.07  4668.3  306.91  4861.4  302.94  4914.1  304.92
  4966.1  304.81  4981.8  301.76  4987.2  294.85  4987.7  294.35  5014.7  294.85
  5017.5  305.92  5039.1  305.98  5219.5  306.34  5822.2  316.15  5882.1  316.84
  5940.4  317.85  6029.9  319.77  6230.3  324.72  6340.6     325  6480.2  329.11
#Mann= 17 ,-1 , 0
  3033.9     .07       0  3047.6     .12       0  3241.3     .07       0
  4049.6     .12       0    4177     .07       0  4372.6     .12       0
  4426.1     .07       0  4566.6     .12       0  4648.8     .07       0
  4668.3      .1       0  4987.2     .05       0  5014.7      .1       0
  5039.1     .05       0  5822.2     .07       0  5882.1     .05       0
  5940.4     .07       0  6029.9     .05       0
Bank Sta=4987.2,5014.7
XS Rating Curve= 0 ,0
Exp/Cntr=0.3,0.1

Type RM Length L Ch R = 1 ,134980  ,1001,1001,1001
BEGIN DESCRIPTION:
X19127
END DESCRIPTION:
XS GIS Cut Line= 3
      2364927.42     13627398.04       2364471.7     13625227.95
      2362540.61     13624229.86
#Sta/Elev= 30
  3289.5  323.22  3516.3  321.23    3824  312.62  4089.8  308.24  4327.2  307.57
  4824.1  306.42  5009.3  301.48  5017.9   292.7  5018.4   292.2  5045.5   292.7
  5070.6  300.67  5076.5  296.23    5091  300.69  5111.1  296.32  5121.2  295.47
  5131.9   300.3  5142.1  301.32    5221  305.04  5305.6  304.17    5349  299.98
  5444.1  302.77  5728.3  302.58  6025.9   307.4  6197.5  305.41  6403.8  308.66
  6894.9  311.01  7194.4  314.74  7521.7  325.35  7630.8  327.82  7680.7  327.38
#Mann= 12 ,-1 , 0
  3289.5     .07       0  4089.8     .12       0  4327.2     .07       0
  4824.1      .1       0  5017.9     .05       0  5045.5      .1       0
  5111.1     .05       0    5349     .07       0  5444.1     .05       0
  7194.4    .035       0  7521.7     .05       0  7630.8    .035       0
Bank Sta=5017.9,5045.5
XS Rating Curve= 0 ,0
Exp/Cntr=0.3,0.1

Type RM Length L Ch R = 1 ,133979  ,1470,1470,1470
BEGIN DESCRIPTION:
X19126
END DESCRIPTION:
XS GIS Cut Line= 4
      2365318.06     13627029.14      2365513.37     13625900.69
      2365318.06     13624815.62      2362628.56     13623752.84
#Sta/Elev= 30
  3366.2  319.08  3695.2   318.2  3958.9  315.55  4312.5  307.88  4511.4  305.95
  4681.2  299.64  4720.4  302.93  4771.2  305.17  4927.1  306.12  4964.3   303.8
  4971.9  292.55  4972.4  292.05  4999.8  292.55  5004.9  299.92  5015.1  301.37
  5116.7  300.24  5157.3  303.84  5187.8   305.1  5286.5  303.94  5435.2  305.32
  5695.6  305.31  5864.5  305.87  6694.1  308.48  6821.3  307.09  7013.3  307.48
  7432.1   309.4  7595.4  312.08  7627.9  311.08  7830.4   312.2  8505.8  318.67
#Mann= 10 ,-1 , 0
  3366.2     .07       0  4681.2      .1       0  4971.9     .05       0
  4999.8      .1       0  5286.5     .12       0  5695.6     .07       0
  5864.5     .05       0  7432.1    .035       0  7595.4     .07       0
  7830.4     .05       0
Bank Sta=4971.9,4999.8
XS Rating Curve= 0 ,0
Exp/Cntr=0.3,0.1

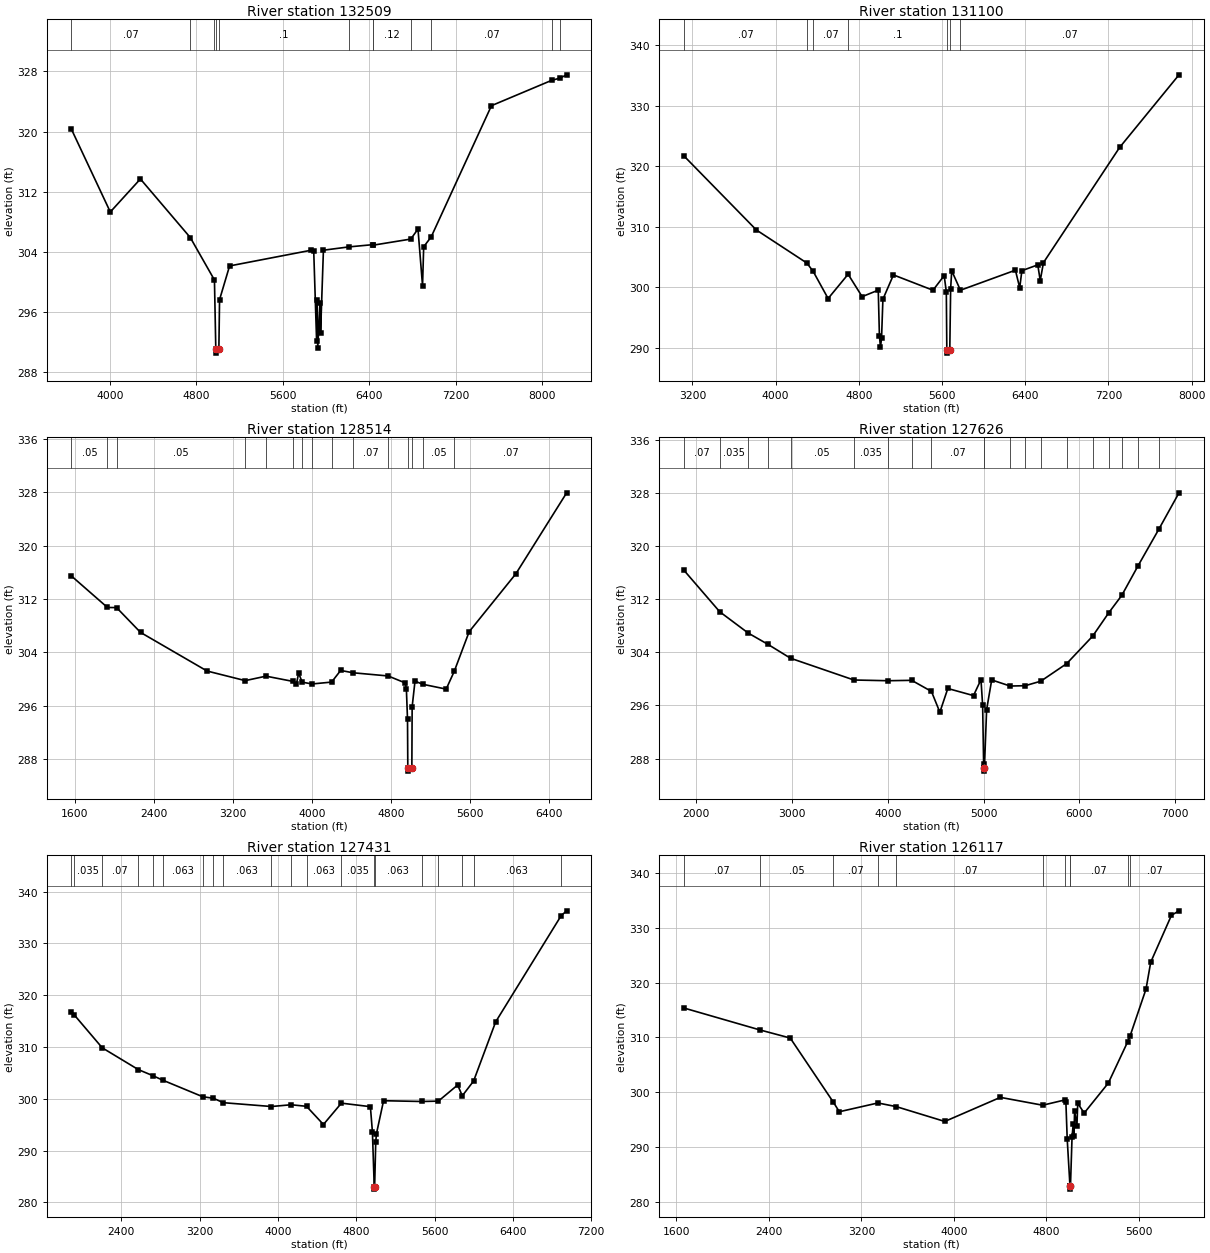
Type RM Length L Ch R = 1 ,132509  ,1409,1409,1409
BEGIN DESCRIPTION:
ELM CREEK 61.0
END DESCRIPTION:
XS GIS Cut Line= 3
      2366793.76     13626703.68      2366359.72     13624989.23
      2365469.99     13622320.05
#Sta/Elev= 30
  3644.6  320.32  4004.3  309.32  4282.8  313.71  4744.5  305.92  4967.9  300.28
  4980.5  291.06    4981  290.56  5008.7  291.06  5015.2  297.67    5108  302.15
  5860.3  304.23  5886.6  304.09    5913  292.23  5918.3  297.68  5923.6  291.24
  5944.6  297.22  5949.9  293.26  5976.2  304.24  6212.3  304.68  6434.9  304.98
  6437.3  304.91  6784.2  305.72  6851.2  307.05  6893.3  299.51  6903.9   304.7
  6973.4  306.01    7531  323.45  8086.9  326.81  8163.8  327.11  8226.7  327.55
#Mann= 12 ,-1 , 0
  3644.6     .07       0  4744.5     .12       0  4967.9      .1       0
  4980.5     .05       0  5008.7      .1       0  6212.3     .12       0
  6434.9     .07       0  6437.3     .12       0  6784.2      .1       0
  6973.4     .07       0  8086.9     .05       0  8163.8     .07       0
Bank Sta=4980.5,5008.7
XS Rating Curve= 0 ,0
Exp/Cntr=0.3,0.1

Type RM Length L Ch R = 1 ,131100  ,2586,2586,2586
BEGIN DESCRIPTION:
ELM CREEK 60.0
END DESCRIPTION:
XS GIS Cut Line= 3
       2367531.6     13626942.36        2367575.     13625423.26
       2366707.2     13622299.17
#Sta/Elev= 30
  3116.4  321.71    3814  309.46  4300.1  303.99  4360.4  302.62  4504.3  298.13
  4696.7  302.14  4831.5  298.44  4986.5  299.51  4997.6     292  5007.9  290.06
  5018.3  291.64  5031.2  298.01  5132.5  302.03  5512.7   299.5  5620.3  301.91
    5641  299.26  5645.9  289.61  5646.4  289.11  5674.3  289.61  5682.6  299.74
  5692.9  302.72  5776.6   299.5  6305.3  302.81  6346.8   299.9  6367.6  302.73
  6520.5  303.69    6544  301.09  6575.1  304.06  7307.2  323.08  7878.5  335.08
#Mann= 7 ,-1 , 0
  3116.4     .07       0  4300.1     .12       0  4360.4     .07       0
  4696.7      .1       0  5645.9     .05       0  5674.3      .1       0
  5776.6     .07       0
Bank Sta=5645.9,5674.3
XS Rating Curve= 0 ,0
Exp/Cntr=0.3,0.1

Type RM Length L Ch R = 1 ,128514  ,888,888,888
BEGIN DESCRIPTION:
X19125
END DESCRIPTION:
XS GIS Cut Line= 3
      2368638.36      13626790.4      2368291.15     13624576.91
      2367184.84     13622038.91
#Sta/Elev= 30
  1568.4  315.46  1932.8  310.74    2025  310.72  2267.4     307  2940.4  301.21
  3326.4  299.77  3536.8  300.44  3810.7  299.65  3843.8  299.24  3866.5  300.88
  3902.8  299.54  4001.8  299.27  4199.9  299.55  4291.9   301.3  4415.3  300.95
  4771.8  300.47  4945.6  299.42  4956.5   298.5  4967.9  293.98  4970.9   286.7
  4971.9   286.2  5011.8   286.7  5014.8  295.84  5043.7   299.7  5119.6  299.23
    5359   298.5  5440.8  301.17  5591.6  307.11  6063.9  315.79  6577.6  327.93
#Mann= 15 ,-1 , 0
  1568.4     .05       0  1932.8    .035       0    2025     .05       0
  3326.4     .07       0  3536.8     .05       0  3810.7     .07       0
  3902.8     .05       0  4001.8     .07       0  4199.9     .05       0
  4415.3     .07       0  4771.8      .1       0  4970.9     .05       0
  5011.8     .05       0  5119.6     .05       0  5440.8     .07       0
Bank Sta=4970.9,5011.8
XS Rating Curve= 0 ,0
Exp/Cntr=0.3,0.1

Type RM Length L Ch R = 1 ,127626  ,195,195,195
BEGIN DESCRIPTION:
F21662
END DESCRIPTION:
XS GIS Cut Line= 5
      2369098.51     13626942.76       2368873.6     13625433.98
      2368695.55     13624440.64      2368189.51     13622660.13
      2368011.47     13621891.74
#Sta/Elev= 30
  1868.2   316.4  2243.9  310.12  2541.5  306.91  2744.1  305.24  2983.6  303.12
  3645.9  299.84  4000.9  299.73  4249.6  299.79  4455.9  298.12  4543.8  294.99
    4627  298.56  4895.4  297.49  4973.5   299.9  4990.9  296.03  5001.3  287.19
  5005.4  286.61  5005.7  286.11  5009.4  286.61  5032.5  295.37  5085.6  299.85
  5278.3  298.93  5435.3  298.98  5598.5  299.66  5869.3  302.31  6140.5  306.45
  6310.2     310  6444.7  312.59  6615.7  317.07    6832  322.56  7042.6  328.04
#Mann= 20 ,-1 , 0
  1868.2     .07       0  2243.9    .035       0  2541.5     .05       0
  2744.1    .035       0  2983.6     .05       0  3645.9    .035       0
  4000.9     .07       0  4249.6    .035       0  4455.9     .07       0
  5005.4     .05       0  5009.4      .1       0  5278.3    .035       0
  5435.3     .05       0  5598.5     .07       0  5869.3    .035       0
  6140.5     .07       0  6310.2    .035       0  6444.7     .07       0
  6615.7    .035       0    6832    .035       0
Bank Sta=5005.4,5009.4
XS Rating Curve= 0 ,0
Exp/Cntr=0.3,0.1

Type RM Length L Ch R = 1 ,127431  ,1314,1314,1314
BEGIN DESCRIPTION:
F21661a
END DESCRIPTION:
XS GIS Cut Line= 5
      2369407.77     13626783.46      2369098.51     13625696.37
      2368911.09     13624571.84       2368451.9     13622894.41
      2368245.75     13621863.63
#Sta/Elev= 30
  1889.1  316.78  1919.6  316.16  2203.8  309.85  2572.1  305.65  2720.2  304.48
  2820.5  303.62  3230.5  300.41  3339.9  300.11  3441.2  299.26    3933  298.52
  4133.8  298.86  4291.4  298.56  4464.2  295.05  4647.9  299.17  4944.1  298.49
  4964.8  293.65  4983.5  283.08  4983.8  282.58  4987.5  283.08  4998.9   291.7
  5006.3  293.29  5078.8  299.64  5471.6  299.49  5638.8  299.56  5835.7  302.67
  5883.5  300.59  5998.8  303.44  6224.2  314.85  6894.4  335.37  6949.7  336.28
#Mann= 20 ,-1 , 0
  1889.1     .07       0  1919.6    .035       0  2203.8     .07       0
  2572.1    .063       0  2720.2     .07       0  2820.5    .063       0
  3230.5    .035       0  3339.9    .035       0  3441.2    .063       0
    3933    .063       0  4133.8    .035       0  4291.4    .063       0
  4647.9    .035       0  4983.5     .05       0  4987.5    .063       0
  5471.6    .035       0  5638.8    .063       0  5883.5    .035       0
  5998.8    .063       0  6894.4     .07       0
Bank Sta=4983.5,4987.5
XS Rating Curve= 0 ,0
Exp/Cntr=0.3,0.1

Type RM Length L Ch R = 1 ,126117  ,608,608,608
BEGIN DESCRIPTION:
F21663
END DESCRIPTION:
XS GIS Cut Line= 3
       2369782.6     13626305.54       2369782.6     13625274.67
      2368808.01     13622172.84
#Sta/Elev= 30
  1664.3  315.36  2320.3  311.37  2584.8  309.88    2958  298.18  3009.3  296.45
  3342.9  298.05  3502.4  297.38  3921.2  294.68  4401.7  299.07  4767.6  297.64
  4961.6  298.61  4968.3  298.27  4979.9  291.45  5003.9  282.85  5004.2  282.35
  5007.9  282.85  5021.8  291.91  5032.3  294.26  5038.3  292.04  5043.6  296.62
  5063.8   293.8  5070.7  297.99  5126.6  296.21  5335.2  301.67  5501.4  309.14
  5523.8  310.28  5661.2   318.8  5702.1  323.71  5881.3  332.25  5946.5  333.06
#Mann= 11 ,-1 , 0
  1664.3     .07       0  2320.3     .05       0    2958     .07       0
  3342.9     .05       0  3502.4     .07       0  4767.6      .1       0
  4961.6     .07       0  5003.9     .05       0  5007.9     .07       0
  5501.4      .1       0  5523.8     .07       0
Bank Sta=5003.9,5007.9
XS Rating Curve= 0 ,0
Exp/Cntr=0.3,0.1

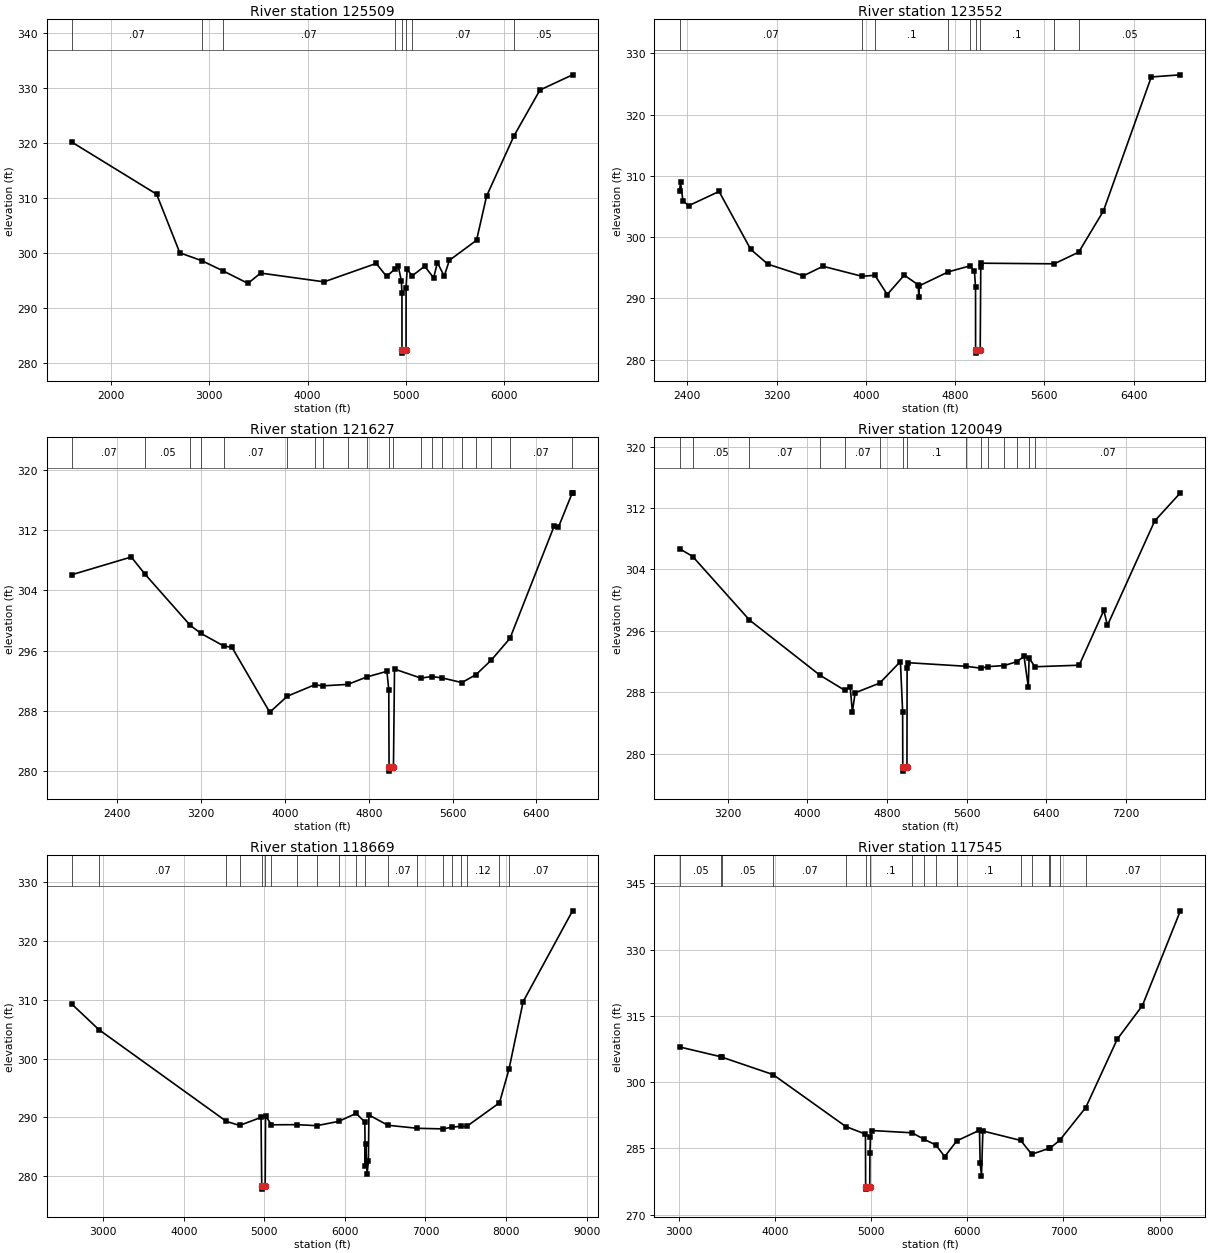
Type RM Length L Ch R = 1 ,125509  ,1957,1957,1957
BEGIN DESCRIPTION:
ELM CREEK 59.0
END DESCRIPTION:
XS GIS Cut Line= 3
      2370786.82     13626074.34      2369853.65     13623600.35
      2369116.33      13621258.3
#Sta/Elev= 30
  1599.1  320.15  2463.6  310.68  2699.9  300.04  2923.7  298.61  3136.6  296.79
  3393.9  294.49  3522.2  296.36  4168.7  294.77  4699.6  298.11  4804.5  295.76
  4891.6   297.1  4923.2  297.71  4955.6  294.94  4961.7  292.74    4962  282.33
    4963  281.83  5003.4  282.33  5003.7  293.69  5014.2  297.02    5066  295.87
  5192.7   297.6  5284.6   295.5  5322.2  298.27  5392.2   295.8    5444  298.67
  5721.2  302.32  5823.6  310.35  6103.6  321.31  6366.6  329.59  6698.6  332.35
#Mann= 8 ,-1 , 0
  1599.1     .07       0  2923.7     .12       0  3136.6     .07       0
  4891.6      .1       0    4962     .05       0  5003.4      .1       0
    5066     .07       0  6103.6     .05       0
Bank Sta=4962,5003.4
XS Rating Curve= 0 ,0
Exp/Cntr=0.3,0.1

Type RM Length L Ch R = 1 ,123552  ,1925,1925,1925
BEGIN DESCRIPTION:
ELM CREEK 58.0
END DESCRIPTION:
XS GIS Cut Line= 3
      2371502.94     13625314.71       2370765.1     13622254.86
      2370548.09     13620931.08
#Sta/Elev= 30
  2329.9  307.48  2338.6  308.93  2360.5  305.91  2411.9  305.12  2684.1  307.44
  2967.4     298  3121.7  295.57  3440.6  293.67  3615.4  295.23  3966.1  293.59
  4081.1  293.76  4191.5  290.62    4344  293.78  4469.2  292.19  4474.9  290.19
    4480  292.05  4739.7  294.32  4934.3   295.3  4973.3  294.38  4982.9  291.79
  4983.4  281.55  4984.4  281.05  5024.8  281.55  5029.9  295.19  5035.1  295.73
  5688.6  295.63  5907.4  297.53    6129  304.25  6558.2  326.13  6818.9  326.48
#Mann= 9 ,-1 , 0
  2329.9     .07       0  3966.1     .12       0  4081.1      .1       0
  4739.7     .12       0  4934.3      .1       0  4983.4     .05       0
  5024.8      .1       0  5688.6     .07       0  5907.4     .05       0
Bank Sta=4983.4,5024.8
XS Rating Curve= 0 ,0
Exp/Cntr=0.3,0.1

Type RM Length L Ch R = 1 ,121627  ,1578,1578,1578
BEGIN DESCRIPTION:
ELM CREEK 57.0
END DESCRIPTION:
XS GIS Cut Line= 3
      2371958.67     13624859.06      2372588.02     13623448.44
      2371676.57     13620345.17
#Sta/Elev= 30
  1966.2  306.08  2534.3  308.44  2666.1  306.15  3097.8  299.34  3199.3  298.28
  3420.6  296.57  3494.7  296.44  3855.9  287.78  4022.3  289.91  4283.4  291.43
  4365.8   291.3  4601.1  291.49  4780.1  292.47  4973.6  293.23  4991.7  290.79
  4994.3  280.45  4995.3  279.95  5036.3  280.45  5046.5  293.53  5297.9  292.33
  5401.5  292.53  5499.2  292.36  5689.4  291.73  5825.1   292.8  5971.7  294.75
  6148.3  297.62  6568.2   312.5  6609.9  312.39  6741.7  316.94  6745.2  316.98
#Mann= 20 ,-1 , 0
  1966.2     .07       0  2666.1     .05       0  3097.8     .07       0
  3199.3     .05       0  3420.6     .07       0  4022.3     .07       0
  4283.4     .12       0  4365.8     .07       0  4601.1     .12       0
  4780.1      .1       0  4994.3     .05       0  5036.3      .1       0
  5297.9     .07       0  5401.5      .1       0  5499.2     .07       0
  5689.4     .07       0  5825.1     .05       0  5971.7     .07       0
  6148.3     .07       0  6741.7     .07       0
Bank Sta=4994.3,5036.3
XS Rating Curve= 0 ,0
Exp/Cntr=0.3,0.1

Type RM Length L Ch R = 1 ,120049  ,1380,1380,1380
BEGIN DESCRIPTION:
ELM CREEK 56.0
END DESCRIPTION:
XS GIS Cut Line= 3
      2372349.32     13624273.06      2373542.88     13621929.34
      2372002.09     13620084.73
#Sta/Elev= 30
  2714.6  306.69  2847.3  305.67  3417.4   297.4  4125.5  290.21  4376.6  288.23
  4429.4  288.72  4451.6  285.41  4479.4  287.91  4726.7  289.18  4934.4  291.98
  4956.8  285.45  4958.3  278.21  4959.3  277.71  5000.3  278.21  5001.7  291.21
  5007.6  291.84  5595.1  291.37  5743.4  291.12  5812.3  291.32  5979.6  291.47
  6103.4  291.97  6176.9  292.65  6219.8  288.69  6227.7  292.43  6286.4  291.31
  6731.3  291.51  6979.1  298.66    7015  296.69    7490   310.3  7748.2  313.97
#Mann= 15 ,-1 , 0
  2714.6     .07       0  2847.3     .05       0  3417.4     .07       0
  4125.5     .12       0  4376.6     .07       0  4726.7      .1       0
  4958.3     .05       0  5000.3      .1       0  5595.1     .07       0
  5743.4     .12       0  5812.3     .07       0  5979.6     .12       0
  6103.4     .07       0  6227.7     .12       0  6286.4     .07       0
Bank Sta=4958.3,5000.3
XS Rating Curve= 0 ,0
Exp/Cntr=0.3,0.1

Type RM Length L Ch R = 1 ,118669  ,1124,1124,1124
BEGIN DESCRIPTION:
ELM CREEK 55.0
END DESCRIPTION:
XS GIS Cut Line= 4
      2374085.42     13625054.35      2374345.83     13622276.56
      2375213.89     13620497.05      2376060.15      13619325.3
#Sta/Elev= 30
  2610.2   309.3  2947.3  304.93  4529.9   289.3  4693.7  288.61  4959.8  289.98
  4968.5  278.26  4969.5  277.76  5011.3  278.26  5015.7  290.27  5088.5  288.72
  5411.6  288.74  5650.3  288.57  5923.4   289.3  6139.6  290.66  6247.7   289.2
  6253.3  281.66  6258.9  285.46  6275.9  280.35    6292  282.48  6298.4  290.39
    6534  288.64  6900.9  288.12  7220.4  288.02    7327  288.31  7442.3  288.47
  7511.5  288.44  7918.4  292.46  8036.7  298.19  8212.8  309.71  8825.5  325.17
#Mann= 20 ,-1 , 0
  2610.2     .05       0  2947.3     .07       0  4529.9     .12       0
  4693.7      .1       0  4968.5     .05       0  5011.3      .1       0
  5088.5    .035       0  5411.6    .035       0  5650.3    .035       0
  5923.4    .035       0  6139.6      .1       0  6247.7    .035       0
    6534     .07       0  6900.9     .07       0  7220.4     .12       0
    7327     .12       0  7442.3     .07       0  7511.5     .12       0
  7918.4    .035       0  8036.7     .07       0
Bank Sta=4968.5,5011.3
XS Rating Curve= 0 ,0
Exp/Cntr=0.3,0.1

Type RM Length L Ch R = 1 ,117545  ,1283,1283,1283
BEGIN DESCRIPTION:
ELM CREEK 54.0
END DESCRIPTION:
XS GIS Cut Line= 3
      2374215.63     13625097.73      2375148.79     13622992.71
      2377036.45     13620779.59
#Sta/Elev= 30
  3005.7  307.98  3440.9  305.73    3451  305.63  3978.8  301.72  4735.5  289.97
  4940.2  288.25  4942.1   276.3  4943.1   275.8  4984.9   276.3  4986.8  284.03
  4992.3  287.62  5010.1  289.06  5425.1  288.55  5552.6  287.05  5671.4  285.81
  5765.3  283.17    5891  286.73  6126.8  289.13  6133.4  281.65  6147.7  278.88
  6161.9  288.96  6555.8  286.82    6670  283.69    6849  285.01    6856  285.01
    6960  286.81  7232.7  294.27  7559.7  309.71  7822.1  317.35  8217.1  338.78
#Mann= 17 ,-1 , 0
  3005.7     .05       0  3440.9     .07       0    3451     .05       0
  3978.8     .07       0  4735.5      .1       0  4942.1     .05       0
  4984.9      .1       0  5425.1     .12       0  5552.6     .07       0
  5671.4     .12       0    5891      .1       0  6555.8     .12       0
    6670     .07       0    6849     .12       0    6856     .07       0
    6960     .12       0  7232.7     .07       0
Bank Sta=4942.1,4984.9
XS Rating Curve= 0 ,0
Exp/Cntr=0.3,0.1

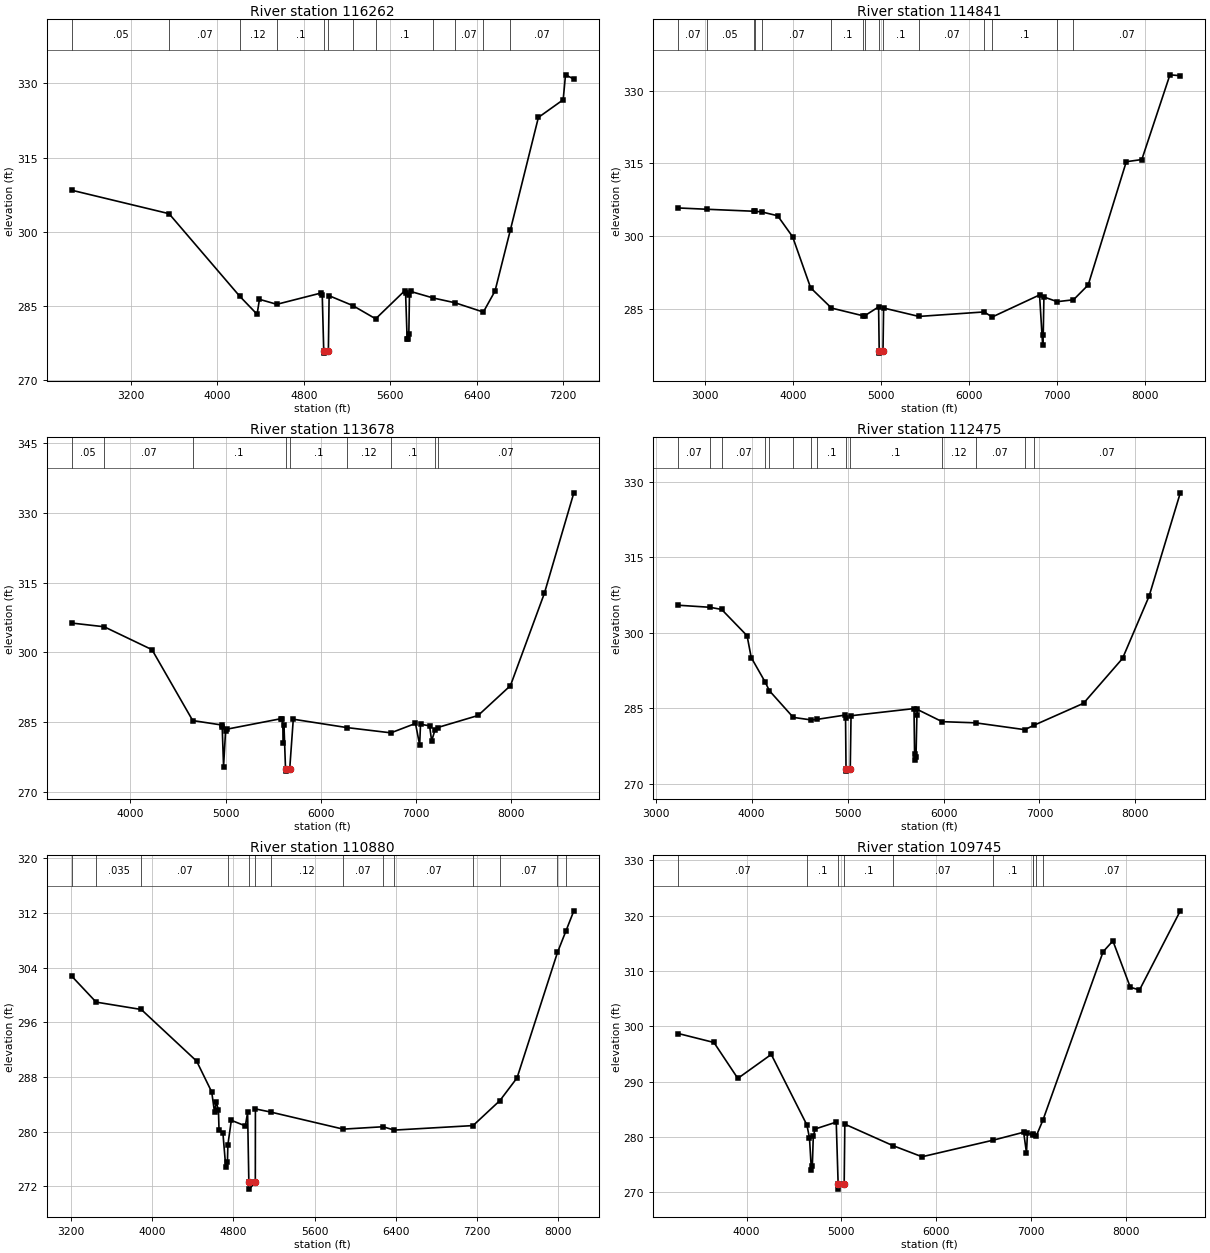
Type RM Length L Ch R = 1 ,116262  ,1421,1421,1421
BEGIN DESCRIPTION:
ELM CREEK 53.0
END DESCRIPTION:
XS GIS Cut Line= 3
      2374324.12     13625184.56      2376298.96     13623405.03
      2377297.22     13621690.62
#Sta/Elev= 30
  2655.4  308.37  3554.6  303.62  4207.2  286.92    4369  283.24  4390.7  286.27
  4551.1  285.26  4957.2  287.53  4971.4  287.07    4985  275.87    4986  275.37
    5028  275.87  5034.9     287    5254     285  5465.3  282.32  5734.6  288.02
  5741.9  287.56  5756.1  278.33  5765.1  278.33  5771.9  279.31  5777.7  287.13
  5787.6  287.87    5999  286.53  6199.4  285.57  6460.8  283.69  6568.6  287.94
  6711.4  300.38  6969.8  323.12    7199   326.7  7220.5  331.75  7297.6  330.89
#Mann= 12 ,-1 , 0
  2655.4     .05       0  3554.6     .07       0  4207.2     .12       0
  4551.1      .1       0    4985     .05       0    5028      .1       0
    5254     .07       0  5465.3      .1       0    5999     .12       0
  6199.4     .07       0  6460.8     .12       0  6711.4     .07       0
Bank Sta=4985,5028
XS Rating Curve= 0 ,0
Exp/Cntr=0.3,0.1

Type RM Length L Ch R = 1 ,114841  ,1163,1163,1163
BEGIN DESCRIPTION:
ELM CREEK 52.0
END DESCRIPTION:
XS GIS Cut Line= 3
      2374801.54     13626356.44      2376819.79      13624490.1
      2378772.89      13622276.6
#Sta/Elev= 30
    2697  305.81  3021.2  305.54  3554.8  305.13  3568.1  305.12  3642.5     305
  3825.6   304.2  3995.6  299.86  4200.4  289.31    4437  285.13  4798.7  283.52
  4816.8  283.57  4972.1  285.37  4978.9  276.32  4979.9  275.82    5022  276.32
  5028.8  285.14  5429.5   283.4  6170.4  284.33  6261.5  283.28  6799.7  287.84
  6834.9   277.4  6841.6  279.65  6849.1  287.42    7000  286.45    7185  286.84
  7351.9   289.9  7784.4  315.36  7960.9  315.81    8280  333.31  8397.9  333.13
#Mann= 15 ,-1 , 0
    2697     .07       0  3021.2     .05       0  3554.8     .07       0
  3568.1    .035       0  3642.5     .07       0    4437      .1       0
  4798.7     .07       0  4816.8      .1       0  4978.9     .05       0
    5022      .1       0  5429.5     .07       0  6170.4     .12       0
  6261.5      .1       0    7000     .12       0    7185     .07       0
Bank Sta=4978.9,5022
XS Rating Curve= 0 ,0
Exp/Cntr=0.3,0.1

Type RM Length L Ch R = 1 ,113678  ,1203,1203,1203
BEGIN DESCRIPTION:
ELM CREEK 51.0
END DESCRIPTION:
XS GIS Cut Line= 3
       2375669.6     13626747.06      2377167.01     13625488.37
      2380096.72     13623925.86
#Sta/Elev= 30
  3382.9  306.31  3722.6  305.52    4226  300.59    4654  285.35  4957.3   284.4
  4963.8  283.98  4978.1  275.47    4999  283.06  5013.3   283.5  5585.5  285.77
  5597.4   285.6  5607.5  280.52  5613.1  284.32  5629.3  274.98  5630.3  274.48
  5673.4  274.98  5710.8  285.64  6274.9  283.84  6736.8  282.71  6995.1  284.73
    7039  280.11  7048.1  284.56  7143.1  284.22  7165.1  280.98  7199.5  283.28
  7227.6  283.85  7653.1  286.44  7993.1  292.86  8349.4  312.69  8659.4  334.31
#Mann= 9 ,-1 , 0
  3382.9     .05       0  3722.6     .07       0    4654      .1       0
  5629.3     .05       0  5673.4      .1       0  6274.9     .12       0
  6736.8      .1       0  7199.5     .12       0  7227.6     .07       0
Bank Sta=5629.3,5673.4
XS Rating Curve= 0 ,0
Exp/Cntr=0.3,0.1

Type RM Length L Ch R = 1 ,112475  ,1595,1595,1595
BEGIN DESCRIPTION:
ELM CREEK 50.0
END DESCRIPTION:
XS GIS Cut Line= 3
      2376190.44      13627484.9      2378816.32     13625748.78
      2380443.95     13624446.68
#Sta/Elev= 30
  3235.6  305.49  3567.9  305.08  3688.1  304.65    3953  299.43  3996.3  295.09
  4140.8  290.25  4185.5   288.5  4434.2   283.2  4623.6  282.69  4684.3  282.81
  4970.2  283.65  4979.2  283.05  4984.2  273.02  4985.2  272.52  5028.3  273.02
  5036.4  283.53  5692.5  284.95  5698.6  275.99  5707.5  274.65  5713.5  275.34
  5722.6  283.64  5728.6  284.77  5985.3  282.35  6333.8  282.12  6846.9  280.76
  6942.3  281.63    7459     286  7865.6  294.91  8142.6  307.29  8467.9  327.83
#Mann= 14 ,-1 , 0
  3235.6     .07       0  3567.9    .035       0  3688.1     .07       0
  4140.8    .035       0  4185.5     .07       0  4434.2      .1       0
  4623.6     .12       0  4684.3      .1       0  4984.2     .05       0
  5028.3      .1       0  5985.3     .12       0  6333.8     .07       0
  6846.9     .12       0  6942.3     .07       0
Bank Sta=4984.2,5028.3
XS Rating Curve= 0 ,0
Exp/Cntr=0.3,0.1

Type RM Length L Ch R = 1 ,110880  ,1135,1135,1135
BEGIN DESCRIPTION:
ELM CREEK 49.0
END DESCRIPTION:
XS GIS Cut Line= 3
      2376667.87     13628287.85      2378881.42     13627137.67
      2380877.96     13625705.38
#Sta/Elev= 30
  3205.3  302.77  3445.5  298.98  3890.8   297.9  4436.5  290.35  4585.6  285.83
  4613.4  282.85  4629.9  284.39    4652  283.14  4657.6   280.2  4696.2  279.78
  4723.9  274.84  4740.4  275.53    4745  278.11    4779  281.68  4917.3  280.86
  4939.4  282.84  4951.8  272.61  4953.3  271.61  5015.5  272.61  5016.4  283.35
  5167.2  282.89  5882.3  280.39  6274.9  280.74  6386.1  280.25  7162.9  280.91
  7427.8  284.57  7596.7  287.89  7995.6  306.25  8077.7  309.34    8157  312.34
#Mann= 14 ,-1 , 0
  3205.3     .07       0  3445.5    .035       0  3890.8     .07       0
    4745      .1       0  4951.8     .05       0  5015.5      .1       0
  5167.2     .12       0  5882.3     .07       0  6274.9     .12       0
  6386.1     .07       0  7162.9     .05       0  7427.8     .07       0
  7995.6    .035       0  8077.7     .07       0
Bank Sta=4951.8,5015.5
XS Rating Curve= 0 ,0
Exp/Cntr=0.3,0.1

Type RM Length L Ch R = 1 ,109745  ,1064,1064,1064
BEGIN DESCRIPTION:
ELM CREEK 48.0
END DESCRIPTION:
XS GIS Cut Line= 3
      2376841.51     13628700.17      2379055.04     13628439.76
      2382114.92     13628331.25
#Sta/Elev= 30
  3280.6   298.7  3656.7  297.08  3908.4  290.59  4260.8  294.92  4635.7   282.2
  4663.6  279.86  4683.7     274  4693.8  274.83  4703.8  280.17    4724  281.45
  4945.5  282.69  4965.5  271.58    4967  270.58  5029.2  271.58  5036.1  282.32
  5541.3  278.45  5849.6  276.43  6601.9  279.44  6920.2  280.86  6950.3  277.14
  6960.3  280.68  7017.9  280.44  7023.8  280.59  7053.8  280.21  7122.4     283
  7757.8  313.48  7860.8  315.44    8044  307.07    8141  306.56  8571.2  320.87
#Mann= 10 ,-1 , 0
  3280.6     .07       0  4635.7      .1       0  4965.5     .05       0
  5029.2      .1       0  5541.3     .07       0  6601.9      .1       0
  7017.9     .12       0  7023.8     .07       0  7053.8     .12       0
  7122.4     .07       0
Bank Sta=4965.5,5029.2
XS Rating Curve= 0 ,0
Exp/Cntr=0.3,0.1