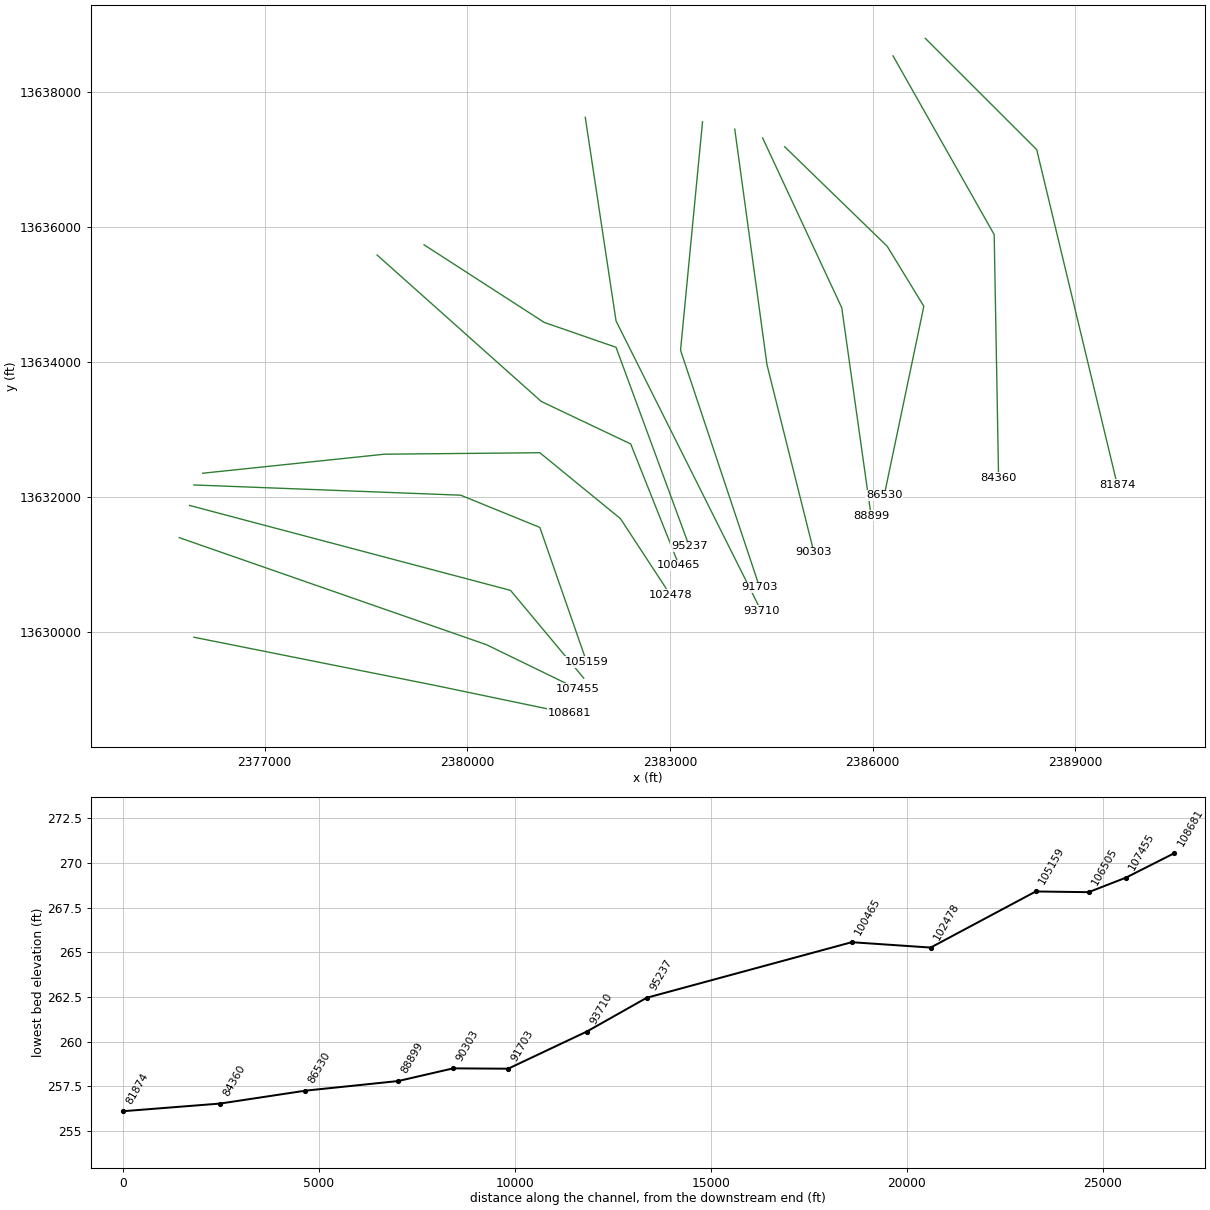
HEC-RAS study ELM CREEK.prj: ELM CREEK Base Level Engineering

--- ELM CREEK.g01 (geometry) --- (continued)

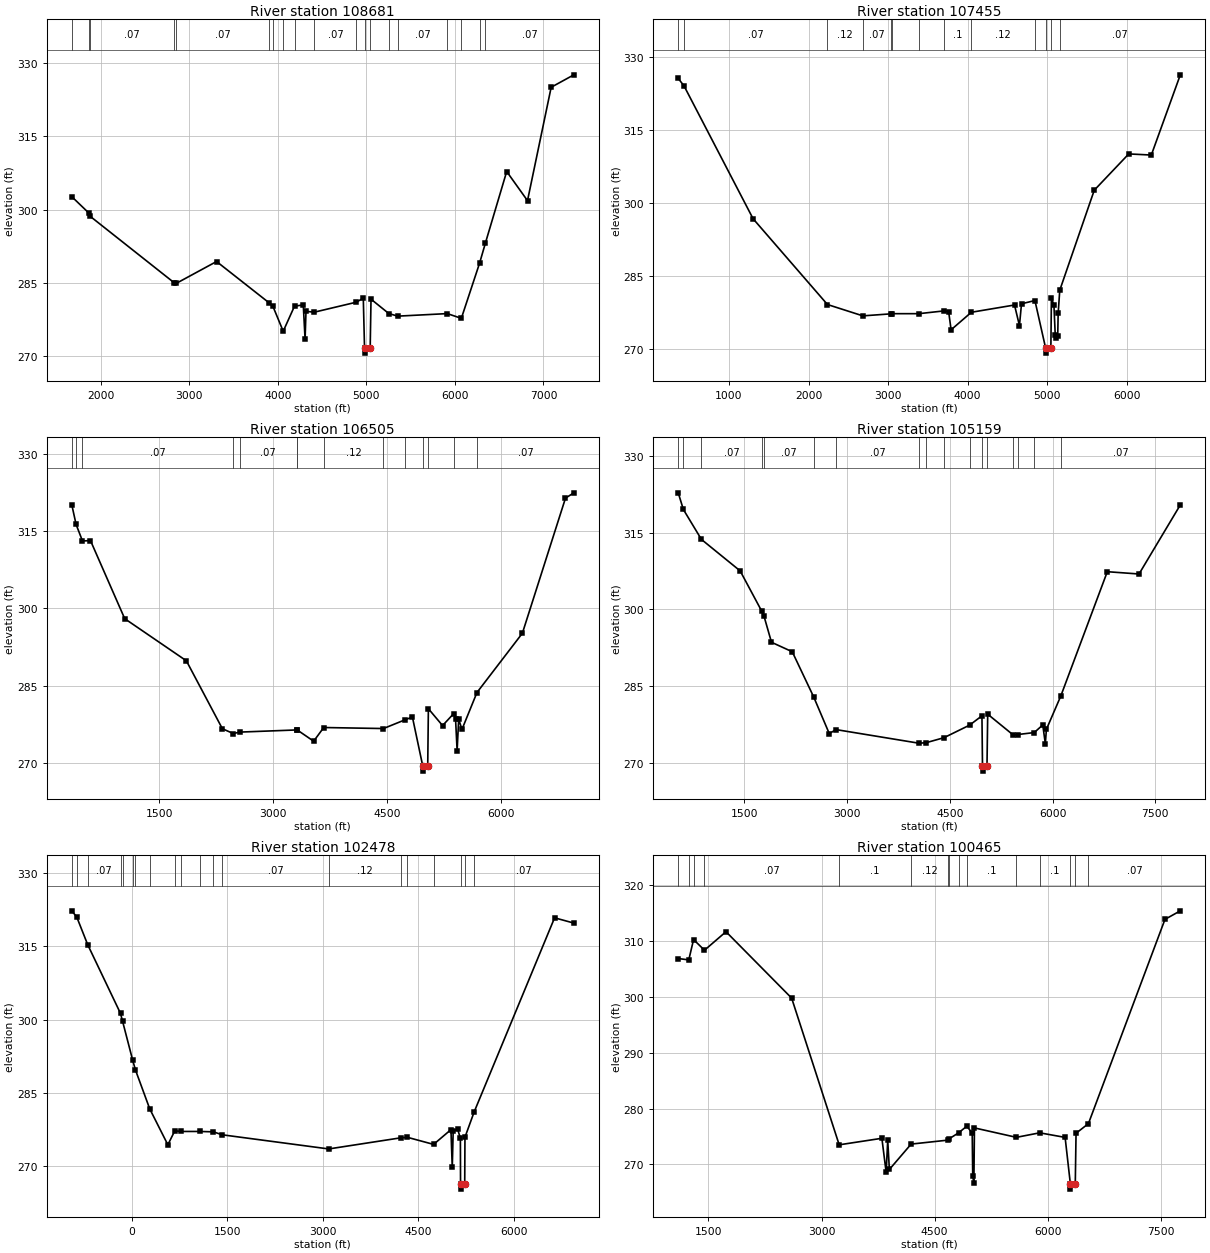
Type RM Length L Ch R = 1 ,108681  ,1226,1226,1226
BEGIN DESCRIPTION:
ELM CREEK 47.0
END DESCRIPTION:
XS GIS Cut Line= 3
      2375951.77     13629915.44      2379532.47      13629199.3
      2381507.27     13628786.98
#Sta/Elev= 30
    1674  302.65  1866.2   299.3  1879.5  298.65  2829.8  284.99  2854.4  284.86
    3309  289.34  3898.8  280.91  3941.9  280.29  4061.4  275.03  4188.9  280.18
    4288  280.43  4308.4  273.38  4318.6  279.11    4414  278.95  4886.4  280.99
  4965.6  281.82  4979.7  271.54  4981.2  270.54  5043.4  271.54  5052.8  281.61
    5254  278.66    5355  278.13    5914  278.65  6072.8  277.68  6279.8  289.07
  6344.6  293.14  6584.7  307.81  6819.7  301.83    7087   325.1    7343  327.65
#Mann= 19 ,-1 , 0
    1674     .07       0  1866.2    .035       0  1879.5     .07       0
  2829.8     .12       0  2854.4     .07       0  3898.8     .12       0
  3941.9     .07       0  4061.4     .12       0  4188.9      .1       0
    4414     .07       0  4886.4      .1       0  4979.7     .05       0
  5043.4      .1       0    5254     .12       0    5355     .07       0
    5914      .1       0  6072.8     .07       0  6279.8     .12       0
  6344.6     .07       0
Bank Sta=4979.7,5043.4
XS Rating Curve= 0 ,0
Exp/Cntr=0.3,0.1

Type RM Length L Ch R = 1 ,107455  ,950,950,950
BEGIN DESCRIPTION:
X19123
END DESCRIPTION:
XS GIS Cut Line= 3
      2375734.76     13631391.13      2380281.99     13629805.29
      2381627.85     13629150.55
#Sta/Elev= 30
     362  325.58     435  324.04  1303.2  296.77  2237.9  279.16  2683.4  276.83
  3031.3  277.24  3050.7  277.28  3386.8  277.28    3698  277.84  3761.6  277.72
  3792.7  273.97  4047.5  277.57  4589.9  279.06    4652  274.83  4677.8  279.31
  4846.5  279.98  4981.5  270.18    4983  269.18    5047  270.18  5053.9  280.59
  5085.7  278.96  5102.2  272.81  5117.5  272.35  5133.3  272.72  5138.7  277.32
  5158.7  282.08  5592.6  302.63  6026.3  310.08    6310  309.85  6674.5  326.32
#Mann= 13 ,-1 , 0
     362     .05       0     435     .07       0  2237.9     .12       0
  2683.4     .07       0  3031.3     .12       0  3050.7     .07       0
  3386.8     .12       0    3698      .1       0  4047.5     .12       0
  4846.5      .1       0  4981.5     .05       0    5047      .1       0
  5158.7     .07       0
Bank Sta=4981.5,5047
XS Rating Curve= 0 ,0
Exp/Cntr=0.3,0.1

Type RM Length L Ch R = 1 ,106505  ,1346,1346,1346
BEGIN DESCRIPTION:
X19122
END DESCRIPTION:
XS GIS Cut Line= 3
      2375886.67     13631868.56      2380639.24     13630609.89
      2381723.38     13629308.92
#Sta/Elev= 30
   350.4  320.12   407.5  316.27   491.5  313.07   596.9  313.14  1047.4  297.98
    1859   289.8  2333.3   276.6  2476.9  275.67  2561.5  275.95  3314.2  276.37
  3317.2  276.38  3534.9  274.18  3667.5  276.84  4453.8  276.64  4733.4  278.31
  4834.9  278.88    4971  269.37  4972.5  268.37  5036.6  269.37  5045.2  280.49
    5232  277.22  5379.2  279.55  5402.7  278.59  5423.5  272.37  5444.4  278.45
  5487.3  276.47  5684.9  283.64  6282.7  295.15  6850.2  321.39  6960.3  322.42
#Mann= 14 ,-1 , 0
   350.4     .07       0   407.5     .05       0   491.5     .07       0
  2476.9     .12       0  2561.5     .07       0  3314.2     .12       0
  3317.2     .07       0  3667.5     .12       0  4453.8     .07       0
  4733.4      .1       0    4971     .05       0  5036.6      .1       0
  5379.2     .12       0  5684.9     .07       0
Bank Sta=4971,5036.6
XS Rating Curve= 0 ,0
Exp/Cntr=0.3,0.1

Type RM Length L Ch R = 1 ,105159  ,2681,2681,2681
BEGIN DESCRIPTION:
X19121
END DESCRIPTION:
XS GIS Cut Line= 4
      2375951.73     13632172.39      2379901.39     13632020.48
      2381073.26     13631543.05      2381767.11     13629548.26
#Sta/Elev= 30
   535.7  322.75   610.4   319.5   874.5  313.65  1439.6  307.51  1752.8  299.69
  1786.3  298.74    1897  293.57  2200.2  291.72  2514.4  282.86  2740.6  275.74
  2839.7  276.52  4050.2  273.86  4154.5  273.96  4415.7  274.94  4789.4  277.39
  4969.7  279.21  4977.7  269.41  4979.2  268.41  5043.3  269.41  5053.7  279.53
  5429.9  275.43  5489.6  275.55  5733.3  275.94  5857.5  277.43  5895.2  273.77
  5910.4  276.56    6121  283.08  6799.8  307.35    7263   306.9  7865.7  320.39
#Mann= 17 ,-1 , 0
   535.7    .035       0   610.4     .05       0   874.5     .07       0
  1752.8     .12       0  1786.3     .07       0  2514.4     .12       0
  2839.7     .07       0  4050.2     .12       0  4154.5     .07       0
  4415.7     .12       0  4789.4      .1       0  4977.7     .05       0
  5043.3      .1       0  5429.9     .12       0  5489.6      .1       0
  5733.3     .12       0    6121     .07       0
Bank Sta=4977.7,5043.3
XS Rating Curve= 0 ,0
Exp/Cntr=0.3,0.1

Type RM Length L Ch R = 1 ,102478  ,2013,2013,2013
BEGIN DESCRIPTION:
X19120
END DESCRIPTION:
XS GIS Cut Line= 5
      2376081.99     13632346.01      2378772.92     13632628.12
      2381073.26     13632649.82      2382266.84     13631673.26
       2383004.7     13630544.77
#Sta/Elev= 30
  -948.4  322.26  -869.9  320.99  -697.6  315.32  -181.8  301.25  -149.6  299.66
     9.8  291.65    53.7  289.66   277.7  281.71   562.8  274.35   672.2  277.22
   770.8  277.08  1066.7  277.08  1280.5     277  1415.4   276.4  3093.2   273.5
  4222.7  275.77  4330.5  275.88  4742.1  274.43  5015.2  277.45    5036   269.7
  5050.4  277.17  5120.7  277.53  5163.8   275.7  5166.1  266.27  5167.6  265.27
  5231.8  266.27  5235.6  275.89  5379.1  281.04  6645.2  320.83  6948.2  319.75
#Mann= 20 ,-1 , 0
  -948.4     .07       0  -869.9     .05       0  -697.6     .07       0
  -181.8     .12       0  -149.6     .07       0     9.8     .12       0
    53.7     .07       0   277.7     .12       0   672.2     .07       0
   770.8     .12       0  1066.7     .07       0  1280.5     .12       0
  1415.4     .07       0  3093.2     .12       0  4222.7     .07       0
  4330.5     .12       0  4742.1      .1       0  5166.1     .05       0
  5231.8      .1       0  5379.1     .07       0
Bank Sta=5166.1,5231.8
XS Rating Curve= 0 ,0
Exp/Cntr=0.3,0.1

Type RM Length L Ch R = 1 ,100465  ,5228,5228,5228
BEGIN DESCRIPTION:
ELM CREEK 46.0
END DESCRIPTION:
XS GIS Cut Line= 4
      2378664.44     13635579.48      2381094.97     13633409.37
      2382418.75     13632780.03      2383134.65     13630979.44
#Sta/Elev= 30
    1099  306.89  1238.9  306.65  1302.5  310.29  1447.3  308.38  1732.7   311.7
  2603.8   299.8  3234.5  273.51    3801  274.68  3857.8  268.58  3878.7  274.31
  3900.4  269.09  4189.1  273.64  4683.6  274.36  4685.9  274.52  4817.9  275.65
  4928.3  276.85  4999.6   275.6  5006.6  267.91  5021.7  266.66  5029.3  276.54
  5585.8  274.85  5895.2  275.66  6232.3  274.84  6301.5  266.57    6303  265.57
  6367.2  266.57  6377.4  275.58  6541.6  277.31  7557.2  313.91  7760.8  315.44
#Mann= 15 ,-1 , 0
    1099    .033       0  1238.9     .07       0  1302.5     .05       0
  1447.3     .07       0  3234.5      .1       0  4189.1     .12       0
  4683.6     .07       0  4685.9     .12       0  4817.9     .07       0
  4928.3      .1       0  5585.8     .12       0  5895.2      .1       0
  6301.5     .05       0  6367.2      .1       0  6541.6     .07       0
Bank Sta=6301.5,6367.2
XS Rating Curve= 0 ,0
Exp/Cntr=0.3,0.1

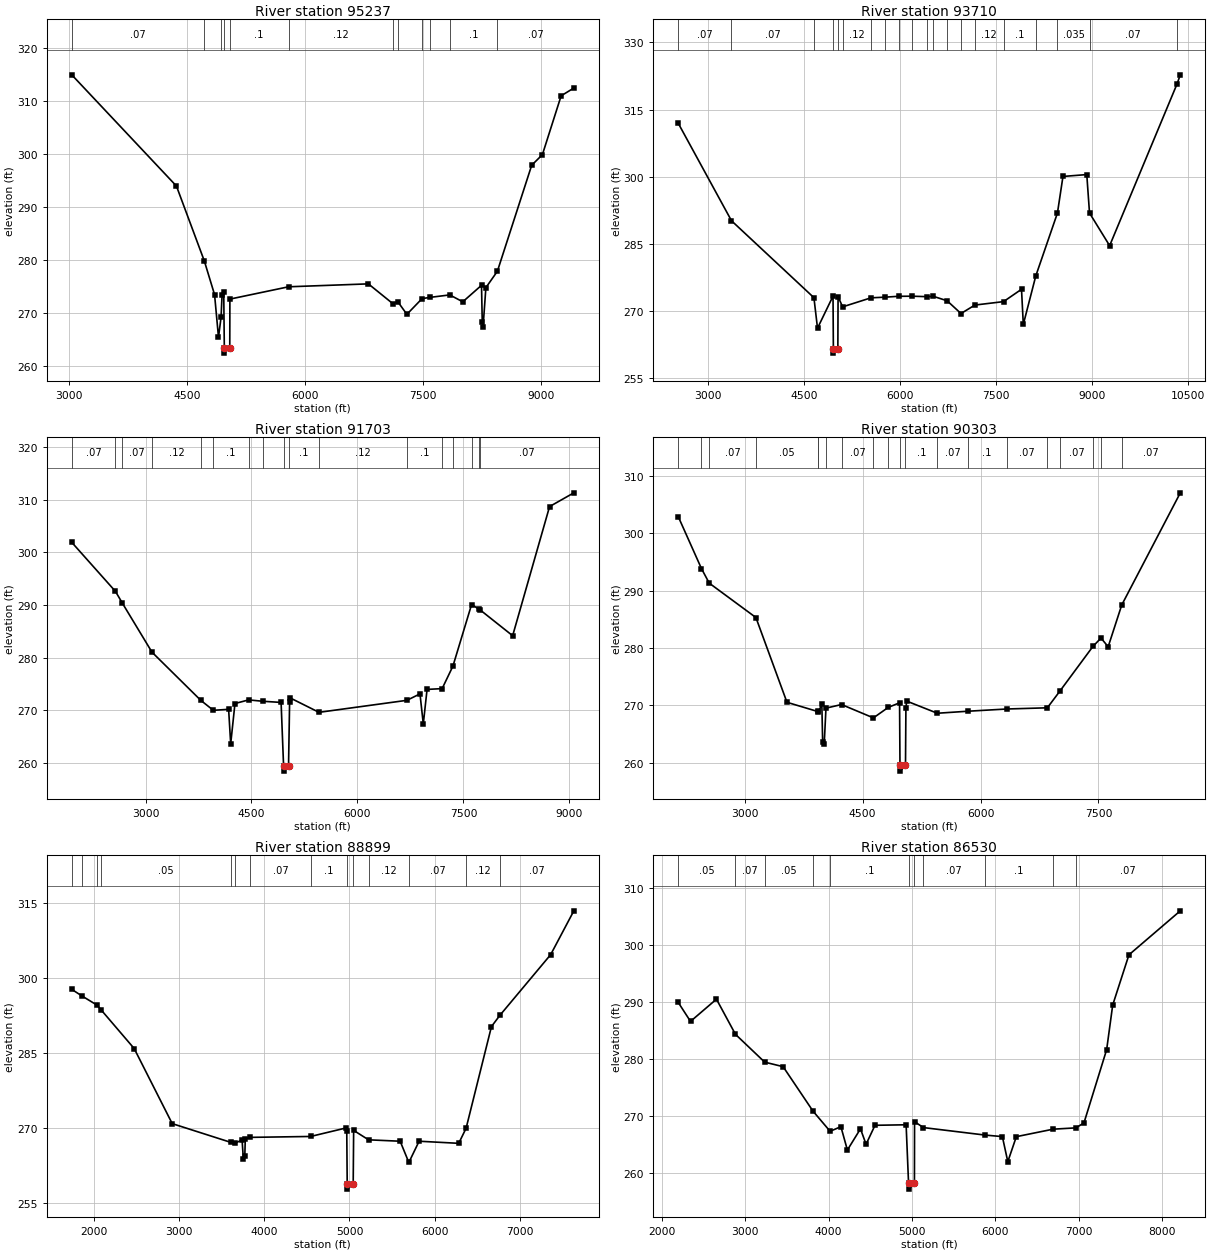
Type RM Length L Ch R = 1 ,95237   ,1527,1527,1527
BEGIN DESCRIPTION:
X19119
END DESCRIPTION:
XS GIS Cut Line= 4
      2379358.88     13635731.41      2381138.37     13634581.25
      2382201.74     13634212.32       2383286.8     13631260.95
#Sta/Elev= 30
  3031.5   314.9  4363.5  293.94  4718.4  279.82  4848.6  273.48  4898.5  265.46
  4931.1  269.18  4943.9  273.36  4965.1  274.07  4972.7  263.46  4974.2  262.46
    5042  263.46  5043.6  272.64  5789.9  274.96  6805.8  275.51  7114.8  271.81
  7180.1  272.15  7295.9  269.77  7488.8  272.73  7592.6  272.97  7841.6  273.43
    8007  272.13  8245.5  275.24  8254.8   268.4  8265.3  267.42  8301.1   274.8
  8447.5  277.89  8883.9  297.86  9020.2  299.86  9258.7  310.95  9420.4  312.41
#Mann= 12 ,-1 , 0
  3031.5     .07       0  4718.4     .12       0  4931.1      .1       0
  4972.7     .05       0    5042      .1       0  5789.9     .12       0
  7114.8     .07       0  7180.1     .12       0  7488.8     .07       0
  7592.6     .12       0  7841.6      .1       0  8447.5     .07       0
Bank Sta=4972.7,5042
XS Rating Curve= 0 ,0
Exp/Cntr=0.3,0.1

Type RM Length L Ch R = 1 ,93710   ,2007,2007,2007
BEGIN DESCRIPTION:
X19118
END DESCRIPTION:
XS GIS Cut Line= 3
      2381746.01     13637619.42      2382201.74     13634602.95
      2384350.11     13630306.21
#Sta/Elev= 30
  2528.2  311.94  3361.4  290.15  4650.9  272.96  4707.1  266.14  4949.8  273.32
  4955.1  261.57  4956.6  260.57  5025.3  261.57  5028.7  273.19  5099.9  270.91
  5543.6  272.93  5757.4  273.07  5974.6  273.27  6191.7  273.29  6412.4  273.19
  6517.4  273.27  6734.5  272.27  6951.6  269.42  7168.8  271.31  7617.2  272.08
  7898.5  274.84  7926.5  266.98  8121.8  277.82  8460.5  291.87    8547  300.05
  8919.5  300.47  8962.3  291.88  9277.3  284.58 10330.1  320.67 10382.8  322.76
#Mann= 20 ,-1 , 0
  2528.2     .07       0  3361.4     .07       0  4650.9      .1       0
  4955.1     .05       0  5025.3      .1       0  5099.9     .12       0
  5543.6    .035       0  5757.4    .035       0  5974.6    .035       0
  6191.7    .035       0  6412.4     .12       0  6517.4    .035       0
  6734.5    .035       0  6951.6    .063       0  7168.8     .12       0
  7617.2      .1       0  8121.8     .07       0  8460.5    .035       0
  8962.3     .07       0 10330.1     .07       0
Bank Sta=4955.1,5025.3
XS Rating Curve= 0 ,0
Exp/Cntr=0.3,0.1

Type RM Length L Ch R = 1 ,91703   ,1400,1400,1400
BEGIN DESCRIPTION:
X19117
END DESCRIPTION:
XS GIS Cut Line= 3
      2383482.11      13637554.3       2383156.6     13634168.92
      2384328.48     13630653.28
#Sta/Elev= 30
  1956.1  301.91  2574.1  292.61  2673.3  290.35  3091.4  281.07  3783.6  271.91
  3960.4  270.03  4176.4  270.22  4205.7  263.67    4266  271.32  4459.7  272.01
  4658.2  271.75    4919  271.53  4954.2  259.49  4955.7  258.49  5024.4  259.49
  5039.6  271.63  5049.6  272.37  5455.6  269.65  6700.1  271.93  6885.1  273.15
  6931.8  267.44  6985.2     274  7198.6  274.15  7351.6  278.43  7615.3  290.11
  7718.2  289.24  7739.9  289.05  8196.7  284.19  8719.2   308.7  9062.9  311.31
#Mann= 17 ,-1 , 0
  1956.1     .07       0  2574.1    .035       0  2673.3     .07       0
  3091.4     .12       0  3783.6     .07       0  3960.4      .1       0
  4459.7     .12       0  4658.2      .1       0  4954.2     .05       0
  5024.4      .1       0  5455.6     .12       0  6700.1      .1       0
  7198.6     .07       0  7351.6    .035       0  7615.3     .07       0
  7718.2    .035       0  7739.9     .07       0
Bank Sta=4954.2,5024.4
XS Rating Curve= 0 ,0
Exp/Cntr=0.3,0.1

Type RM Length L Ch R = 1 ,90303   ,1404,1404,1404
BEGIN DESCRIPTION:
X19116
END DESCRIPTION:
XS GIS Cut Line= 3
      2383959.55     13637445.82      2384436.98     13633951.91
      2385131.41     13631174.18
#Sta/Elev= 30
  2152.7  302.92  2448.3  293.85  2547.3  291.31  3141.3  285.31  3536.3  270.52
  3925.8  268.92  3933.8  268.79  3980.3  270.14  3990.4  263.67  4010.6  263.29
  4032.8   269.5  4230.9  270.13  4636.6   267.8  4825.1  269.63  4969.5  270.43
  4974.7  259.51  4976.2  258.51  5044.9  259.51  5050.2  269.58  5060.3  270.73
  5449.9  268.61  5836.6  268.96  6332.8  269.35  6850.1  269.56  7009.7  272.47
  7430.9  280.28    7533  281.73  7624.1  280.21  7796.9   287.5  8542.3  307.07
#Mann= 20 ,-1 , 0
  2152.7     .07       0  2448.3    .035       0  2547.3     .07       0
  3141.3     .05       0  3925.8     .07       0  3933.8     .12       0
  4032.8      .1       0  4230.9     .07       0  4636.6     .12       0
  4825.1      .1       0  4974.7     .05       0  5044.9      .1       0
  5449.9     .07       0  5836.6      .1       0  6332.8     .07       0
  6850.1     .12       0  7009.7     .07       0  7430.9     .12       0
    7533     .12       0  7796.9     .07       0
Bank Sta=4974.7,5044.9
XS Rating Curve= 0 ,0
Exp/Cntr=0.3,0.1

Type RM Length L Ch R = 1 ,88899   ,2369,2369,2369
BEGIN DESCRIPTION:
X19115
END DESCRIPTION:
XS GIS Cut Line= 3
       2384371.9     13637315.58      2385543.75     13634798.26
      2385977.54     13631718.37
#Sta/Elev= 30
  1744.2  297.66  1867.5  296.31  2040.5  294.52  2089.9  293.54  2476.3  285.85
    2922  270.87  3611.2  267.12  3656.4  266.96  3741.3  267.61  3755.8  263.89
  3773.2  264.48  3778.7  267.85  3839.3  268.13  4544.8  268.31  4958.4     270
  4968.5  269.49  4973.8   258.8  4975.3   257.8    5044   258.8  5049.3  269.52
  5224.2  267.64  5594.7  267.36  5696.5  263.12  5816.8  267.36  6281.4  266.94
    6368  269.96  6665.1  290.24  6764.3  292.49  7359.5   304.6  7631.2  313.34
#Mann= 14 ,-1 , 0
  1744.2     .07       0  1867.5     .05       0  2040.5    .035       0
  2089.9     .05       0  3611.2     .07       0  3656.4     .05       0
  3839.3     .07       0  4544.8      .1       0  4973.8     .05       0
    5044      .1       0  5224.2     .12       0  5696.5     .07       0
    6368     .12       0  6764.3     .07       0
Bank Sta=4973.8,5044
XS Rating Curve= 0 ,0
Exp/Cntr=0.3,0.1

Type RM Length L Ch R = 1 ,86530   ,2170,2170,2170
BEGIN DESCRIPTION:
X19114
END DESCRIPTION:
XS GIS Cut Line= 4
       2384697.4     13637185.41      2386216.49     13635709.72
      2386759.03     13634819.96      2386173.09      13632020.5
#Sta/Elev= 30
  2197.1  289.93  2344.3  286.61  2655.3   290.5  2883.1  284.35  3233.9  279.48
  3454.5  278.69  3812.5  270.92  4018.1  267.38  4147.4  268.19  4225.3   264.1
  4382.1  267.81  4449.3  265.11  4556.4  268.43  4929.5  268.52  4958.9  258.26
  4960.4  257.26  5029.1  258.26  5030.7  269.06  5137.2  268.03  5875.5  266.72
  6083.5  266.45  6148.8  262.06    6251  266.44    6692  267.75  6965.3  267.98
    7062  268.85    7334  281.67  7406.5  289.47  7601.2  298.26  8217.2  305.96
#Mann= 11 ,-1 , 0
  2197.1     .05       0  2883.1     .07       0  3233.9     .05       0
  3812.5     .07       0  4018.1      .1       0  4958.9     .05       0
  5029.1      .1       0  5137.2     .07       0  5875.5      .1       0
    6692     .12       0  6965.3     .07       0
Bank Sta=4958.9,5029.1
XS Rating Curve= 0 ,0
Exp/Cntr=0.3,0.1

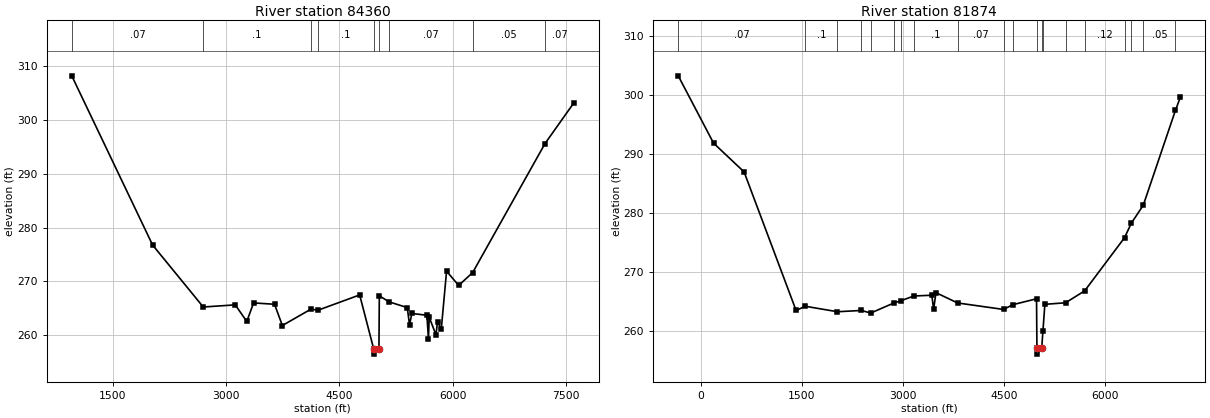
Type RM Length L Ch R = 1 ,84360   ,2486,2486,2486
BEGIN DESCRIPTION:
ELM CREEK 45.0
END DESCRIPTION:
XS GIS Cut Line= 3
       2386303.3     13638530.91      2387800.69     13635883.33
       2387865.8     13632280.91
#Sta/Elev= 30
   957.8  308.11  2027.5  276.76  2698.2  265.27  3121.7  265.67  3273.8  262.59
  3364.2  266.03  3641.4  265.78  3744.8  261.84  4123.3  264.88  4217.5  264.68
  4767.9  267.51  4952.8  257.54  4954.3  256.54  5023.1  257.54    5028  267.35
  5156.4  266.23    5398  265.16  5428.1  261.94  5458.1  264.08  5658.1  263.74
  5678.1  259.31  5688.1  263.38  5778.1  260.11  5798.1  262.52  5848.1  261.19
  5918.1  271.91  6078.2  269.27  6263.7  271.66    7221  295.56  7602.5   303.1
#Mann= 9 ,-1 , 0
   957.8     .07       0  2698.2      .1       0  4123.3     .07       0
  4217.5      .1       0  4952.8     .05       0  5023.1      .1       0
  5156.4     .07       0  6263.7     .05       0    7221     .07       0
Bank Sta=4952.8,5023.1
XS Rating Curve= 0 ,0
Exp/Cntr=0.3,0.1

Type RM Length L Ch R = 1 ,81874   ,1245,1245,1245
BEGIN DESCRIPTION:
ELM CREEK 44.0
END DESCRIPTION:
XS GIS Cut Line= 3
       2386780.7     13638791.34      2388430.04     13637142.01
       2389623.6     13632172.44
#Sta/Elev= 30
  -332.5  303.32   191.2   291.9   643.8  287.02  1414.5  263.52  1551.2  264.23
  2028.6   263.3  2382.1  263.52  2521.2  263.08  2863.7  264.78  2964.3  265.15
  3160.1  265.97  3426.5   266.1    3454  263.73  3488.2  266.54  3808.8  264.79
  4490.3  263.69  4626.1  264.49  4979.4   265.5  4985.1  257.11  4986.6  256.11
    5056  257.11  5073.9  259.96  5102.8  264.56  5409.4  264.82  5692.9  266.84
  6284.5  275.87  6385.1  278.33  6561.9  281.37  7038.9  297.47  7110.9  299.66
#Mann= 20 ,-1 , 0
  -332.5     .07       0  1551.2      .1       0  2028.6     .07       0
  2382.1      .1       0  2521.2     .07       0  2863.7     .12       0
  2964.3     .07       0  3160.1      .1       0  3808.8     .07       0
  4490.3     .12       0  4626.1      .1       0  4985.1     .05       0
    5056      .1       0  5073.9     .12       0  5409.4      .1       0
  5692.9     .12       0  6284.5     .05       0  6385.1     .07       0
  6561.9     .05       0  7038.9     .07       0
Bank Sta=4985.1,5056
XS Rating Curve= 0 ,0
Exp/Cntr=0.3,0.1