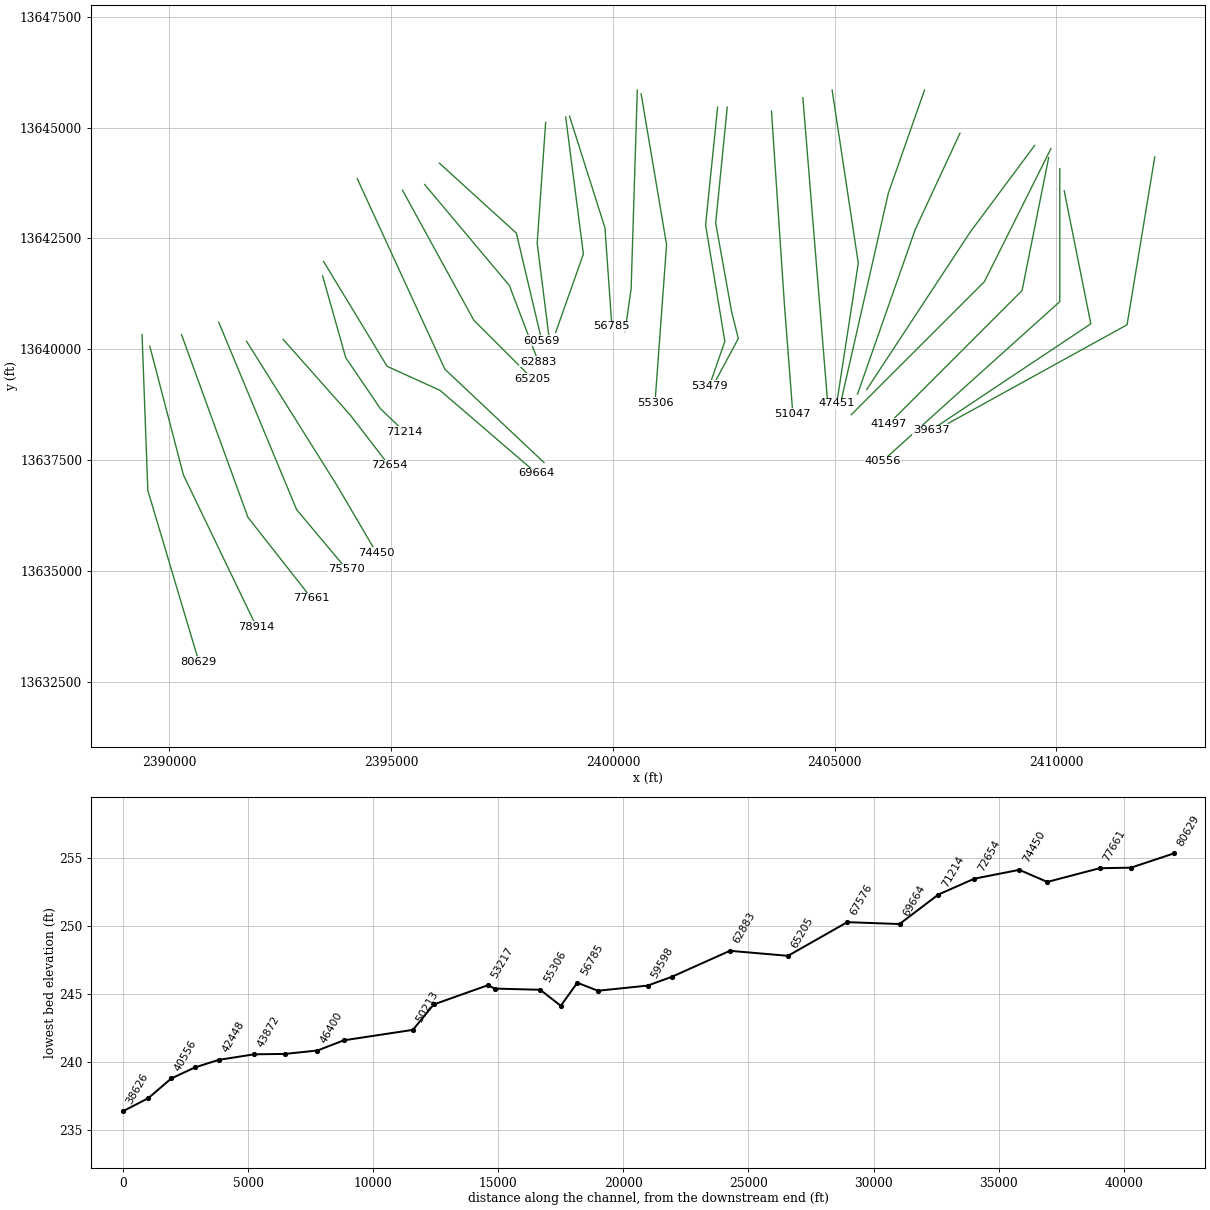
HEC-RAS study ELM CREEK.prj: ELM CREEK Base Level Engineering

--- ELM CREEK.g01 (geometry) --- (continued)

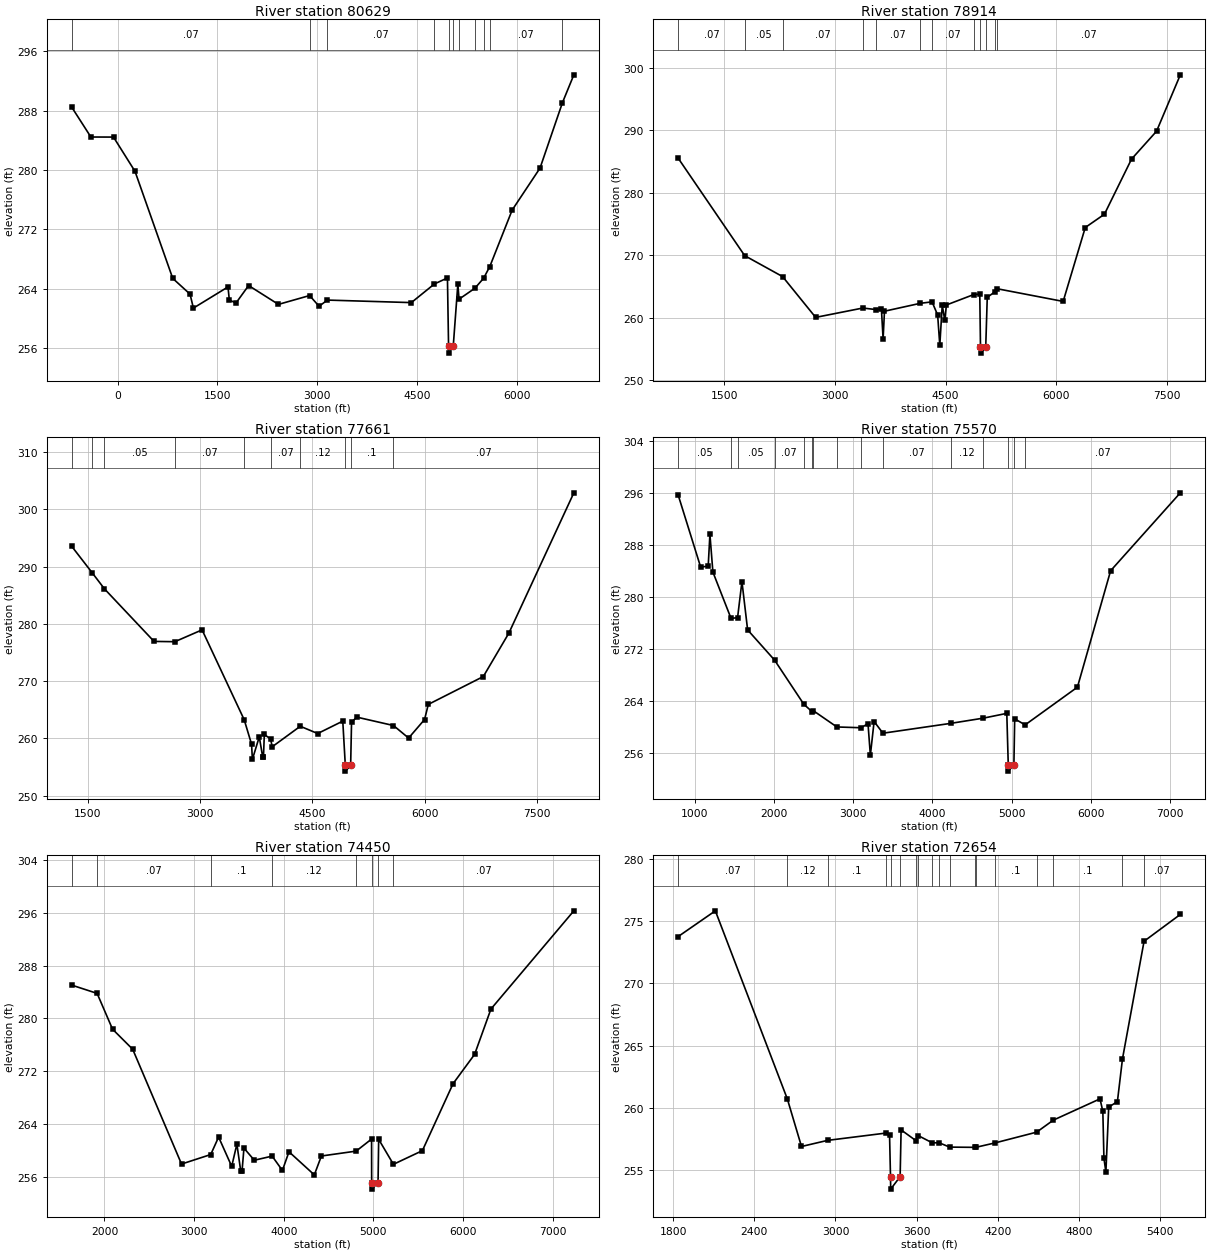
Type RM Length L Ch R = 1 ,80629   ,1715,1715,1715
BEGIN DESCRIPTION:
ELM CREEK 43.0
END DESCRIPTION:
XS GIS Cut Line= 3
       2389384.9     13640332.11       2389515.1     13636816.49
      2390665.29     13632953.62
#Sta/Elev= 30
  -689.4  288.45  -402.1  284.44   -61.9  284.43   261.2  279.82   828.7  265.41
  1088.9  263.29    1139  261.41  1659.3  264.26  1679.3   262.5  1779.4  262.09
  1969.5  264.45  2417.7  261.91  2886.1   263.1  3028.4  261.66  3154.3  262.49
  4416.1  262.15  4762.5  264.66  4958.7  265.47  4975.4  256.35  4976.9  255.35
  5046.4  256.35  5115.2  264.64    5133  262.61  5372.2  264.09  5503.2  265.44
  5595.8  267.01  5931.9  274.61  6350.8  280.26  6687.5  289.06  6859.1  292.81
#Mann= 11 ,-1 , 0
  -689.4     .07       0  2886.1      .1       0  3154.3     .07       0
  4762.5      .1       0  4975.4     .05       0  5046.4      .1       0
    5133     .12       0  5372.2     .07       0  5503.2     .12       0
  5595.8     .07       0  6687.5     .05       0
Bank Sta=4975.4,5046.4
XS Rating Curve= 0 ,0
Exp/Cntr=0.3,0.1

Type RM Length L Ch R = 1 ,78914   ,1253,1253,1253
BEGIN DESCRIPTION:
ELM CREEK 42.0
END DESCRIPTION:
XS GIS Cut Line= 3
       2389558.5     13640071.71      2390318.06     13637163.71
      2391967.35     13633734.91
#Sta/Elev= 30
   873.8  285.54  1775.2  269.93  2289.5  266.57  2737.7  260.03  3377.8  261.53
  3551.5  261.29    3630  261.32  3652.7  256.57  3671.3  261.02  4158.5  262.29
  4316.8  262.52  4392.6  260.41  4421.7  255.55    4455  262.02  4488.7  259.56
  4511.4  262.02  4881.6  263.69    4964  263.75  4973.7   255.3  4975.2   254.3
  5044.8   255.3  5065.6  263.25  5166.1   264.1  5197.1  264.63  6095.1  262.59
  6394.9  274.44  6654.9  276.57  7022.6  285.41    7362  289.88  7684.2  298.92
#Mann= 12 ,-1 , 0
   873.8     .07       0  1775.2     .05       0  2289.5     .07       0
  3377.8     .12       0  3551.5     .07       0  4158.5     .12       0
  4316.8     .07       0  4881.6      .1       0  4973.7     .05       0
  5044.8      .1       0  5166.1     .12       0  5197.1     .07       0
Bank Sta=4973.7,5044.8
XS Rating Curve= 0 ,0
Exp/Cntr=0.3,0.1

Type RM Length L Ch R = 1 ,77661   ,2091,2091,2091
BEGIN DESCRIPTION:
ELM CREEK 41.0
END DESCRIPTION:
XS GIS Cut Line= 3
      2390274.67     13640332.08      2391772.05     13636208.85
      2393204.35     13634385.93
#Sta/Elev= 30
    1287  293.54  1561.7  288.89  1723.8  286.11  2385.8  276.93  2663.7  276.88
  3027.2  278.95    3590  263.23  3688.3  258.95  3698.9   256.3  3791.1  260.26
  3837.2  256.69    3847  256.76  3858.5  260.67    3942  259.87  3964.1  258.52
  4338.7   262.1  4571.3  260.83  4906.2     263  4940.1  255.26  4941.6  254.26
  5011.2  255.26  5023.3  262.81  5092.7   263.7  5583.3  262.23  5785.2  260.04
  5998.5  263.28  6048.2  265.92  6782.9  270.79  7124.6  278.39    7992   302.9
#Mann= 10 ,-1 , 0
    1287     .05       0  1561.7    .035       0  1723.8     .05       0
  2663.7     .07       0    3590      .1       0    3942     .07       0
  4338.7     .12       0  4940.1     .05       0  5011.2      .1       0
  5583.3     .07       0
Bank Sta=4940.1,5011.2
XS Rating Curve= 0 ,0
Exp/Cntr=0.3,0.1

Type RM Length L Ch R = 1 ,75570   ,1120,1120,1120
BEGIN DESCRIPTION:
ELM CREEK 40.0
END DESCRIPTION:
XS GIS Cut Line= 3
      2391112.33     13640614.24      2392870.14     13636382.46
      2393997.32     13635038.52
#Sta/Elev= 30
   793.4  295.67  1076.8   284.6  1171.6  284.79  1193.2  289.67  1230.8  283.86
  1459.2  276.75  1542.1  276.83  1597.4   282.4    1669  274.97  2009.2  270.32
  2378.9  263.52  2486.1  262.36  2497.2  262.55  2795.5  260.04  3103.2  259.92
  3188.3  260.56  3218.1   255.7  3265.3  260.88  3377.1  259.08  4230.3  260.59
  4645.7   261.4  4939.9  262.13  4958.4  254.25  4959.9  253.25  5029.6  254.25
  5039.6  261.29  5171.3  260.36  5831.3  266.16  6250.2  284.06  7129.8  296.04
#Mann= 15 ,-1 , 0
   793.4     .05       0  1459.2     .07       0  1542.1     .05       0
  2009.2     .07       0  2378.9     .12       0  2486.1     .07       0
  2497.2     .12       0  2795.5     .07       0  3103.2      .1       0
  3377.1     .07       0  4230.3     .12       0  4645.7      .1       0
  4958.4     .05       0  5029.6      .1       0  5171.3     .07       0
Bank Sta=4958.4,5029.6
XS Rating Curve= 0 ,0
Exp/Cntr=0.3,0.1

Type RM Length L Ch R = 1 ,74450   ,1796,1796,1796
BEGIN DESCRIPTION:
ELM CREEK 39.0
END DESCRIPTION:
XS GIS Cut Line= 3
      2391741.64     13640180.25       2393781.6       13636925.
      2394670.69     13635407.03
#Sta/Elev= 30
    1635  285.05  1917.7   283.8  2089.7  278.38  2314.8  275.33  2859.3  257.94
  3185.2  259.38    3273  262.03  3419.1  257.59  3476.9  260.96  3519.3  256.93
  3534.6   256.9  3555.8  260.35  3671.3  258.52  3870.2  259.14  3984.8  256.97
  4057.9   259.8  4340.7   256.3  4419.7  259.16  4807.4   259.9  4979.5  261.73
  4980.4  255.14  4981.9  254.14  5051.7  255.14  5058.5  261.69  5223.1   257.9
  5546.2  259.97  5888.5  270.12  6128.9  274.56    6311  281.43  7235.8  296.31
#Mann= 8 ,-1 , 0
    1635     .05       0  1917.7     .07       0  3185.2      .1       0
  3870.2     .12       0  4807.4      .1       0  4980.4     .05       0
  5051.7      .1       0  5223.1     .07       0
Bank Sta=4980.4,5051.7
XS Rating Curve= 0 ,0
Exp/Cntr=0.3,0.1

Type RM Length L Ch R = 1 ,72654   ,1440,1440,1440
BEGIN DESCRIPTION:
ELM CREEK 38.0
END DESCRIPTION:
XS GIS Cut Line= 3
      2392566.33      13640223.6      2394085.42      13638509.2
      2394953.47     13637380.73
#Sta/Elev= 30
  1836.9  273.75  2111.4  275.81  2644.4  260.71  2748.7  256.91  2941.9   257.4
  3376.9  257.99  3400.2  257.85  3407.2  254.49  3408.7  253.49  3478.5  254.49
  3485.6  258.24  3595.2  257.38  3612.8  257.78  3716.7   257.2  3766.2  257.21
  3845.1  256.86  4035.7  256.84  4041.3  256.85  4181.6   257.2  4488.5  258.06
  4611.2  259.02  4957.1  260.73  4978.1  259.72  4986.1  255.97  5000.6  254.86
  5021.5  260.07  5085.8  260.51  5123.5  263.95    5283  273.37  5551.2  275.52
#Mann= 18 ,-1 , 0
  1836.9     .07       0  2644.4     .12       0  2941.9      .1       0
  3376.9     .12       0  3407.2     .05       0  3478.5     .12       0
  3595.2      .1       0  3612.8     .12       0  3716.7     .07       0
  3766.2     .12       0  3845.1     .07       0  4035.7      .1       0
  4041.3     .07       0  4181.6      .1       0  4488.5     .07       0
  4611.2      .1       0  5123.5     .12       0    5283     .07       0
Bank Sta=3407.2,3478.5
XS Rating Curve= 0 ,0
Exp/Cntr=0.3,0.1

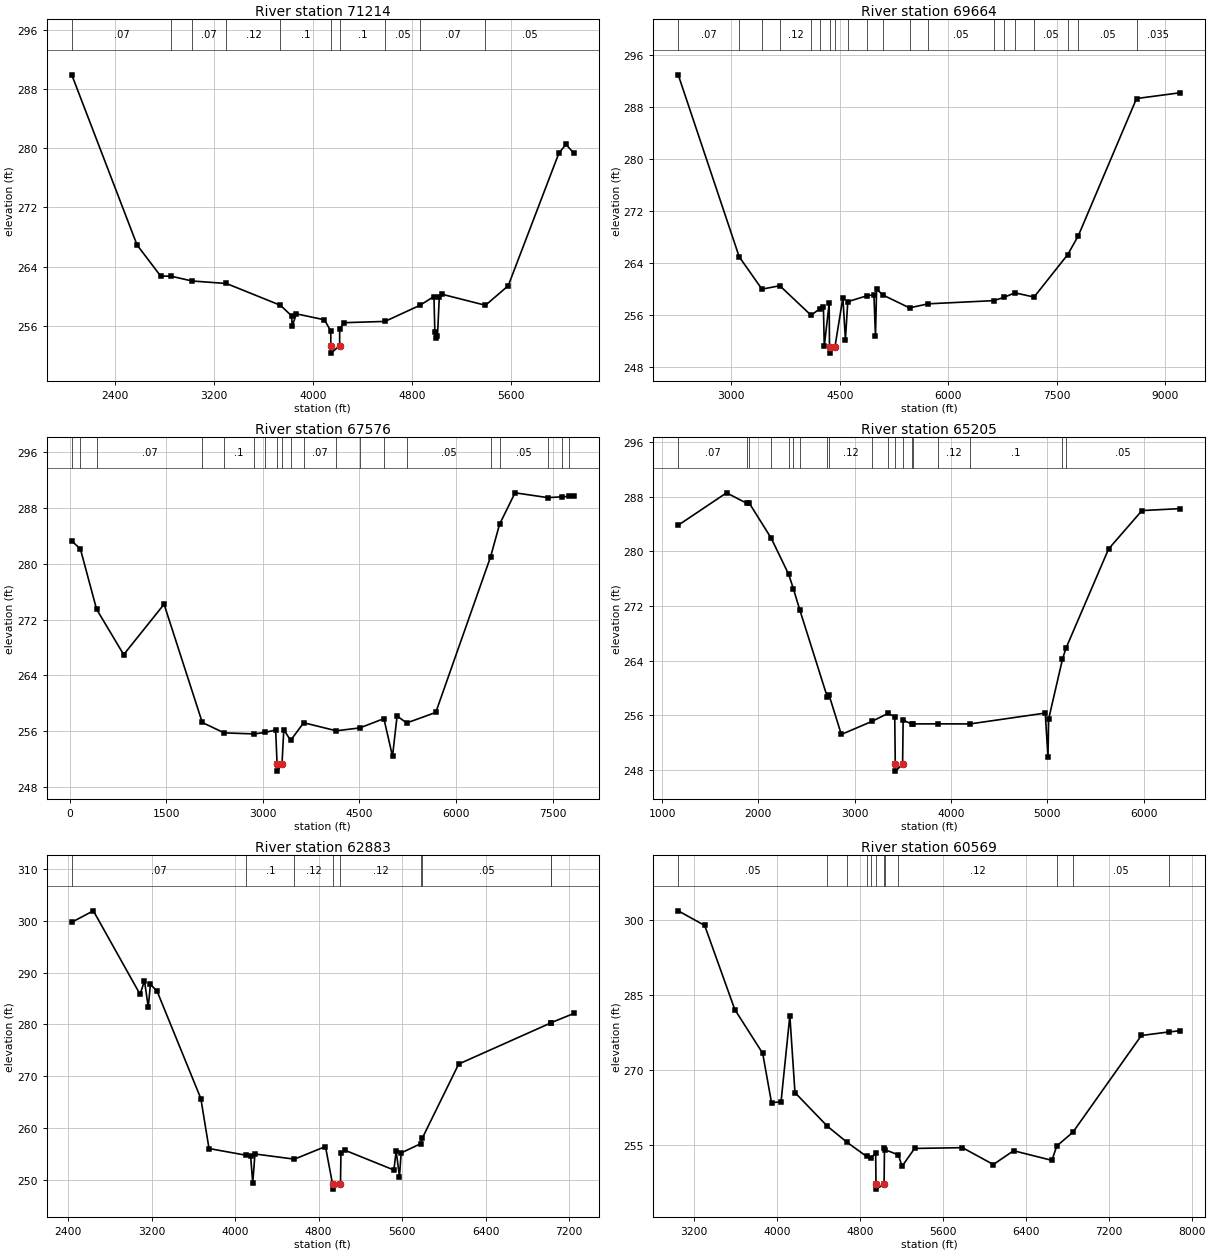
Type RM Length L Ch R = 1 ,71214   ,1550,1550,1550
BEGIN DESCRIPTION:
ELM CREEK 37.0
END DESCRIPTION:
XS GIS Cut Line= 4
      2393456.08     13641655.89      2393976.91     13639811.28
      2394758.16     13638661.11      2395300.33     13638140.63
#Sta/Elev= 30
  2051.1  289.89  2578.8  266.92  2769.5  262.73    2856   262.7  3022.4  262.06
  3301.1  261.72  3737.6  258.78  3827.8  257.36    3833  255.99    3867  257.62
  4094.1  256.82  4144.7   255.3  4145.2  253.32  4146.7  252.32  4216.5  253.32
  4216.8  255.58  4252.7  256.43  4583.2   256.6    4866  258.78  4978.8  259.96
  4986.3  255.17  4992.3  254.35  5007.3  254.58  5022.2  259.89  5043.2  260.27
  5395.6  258.78  5579.5  261.42  5989.9  279.36  6046.5  280.49  6109.8  279.31
#Mann= 10 ,-1 , 0
  2051.1     .07       0    2856      .1       0  3022.4     .07       0
  3301.1     .12       0  3737.6      .1       0  4145.2     .05       0
  4216.5      .1       0  4583.2     .05       0    4866     .07       0
  5395.6     .05       0
Bank Sta=4145.2,4216.5
XS Rating Curve= 0 ,0
Exp/Cntr=0.3,0.1

Type RM Length L Ch R = 1 ,69664   ,2088,2088,2088
BEGIN DESCRIPTION:
ELM CREEK 36.0
END DESCRIPTION:
XS GIS Cut Line= 4
       2393477.8     13641981.39      2394910.07     13639615.97
      2396103.65     13639073.44      2398273.77     13637207.13
#Sta/Elev= 30
  2266.4  292.88  3108.6  264.95  3423.3  259.97  3669.9   260.5  4102.7  255.96
  4221.3  256.95  4272.8   257.3  4284.6  251.21  4352.3  257.79    4357  251.15
  4358.5  250.15    4433  251.15  4541.8  258.66  4576.9  252.22  4609.6  258.05
  4881.3  258.98    4971  259.08  4992.4  252.73  5007.9  259.97  5098.6  259.05
    5463   257.1  5721.4  257.72  6625.4  258.21  6771.5  258.72  6917.7  259.41
  7183.9  258.76  7648.5  265.27  7794.6  268.15  8600.2  289.24    9205  290.13
#Mann= 20 ,-1 , 0
  2266.4     .07       0  3108.6     .12       0  3423.3     .07       0
  3669.9     .12       0  4102.7      .1       0  4221.3     .12       0
    4357     .05       0    4433     .12       0  4609.6     .07       0
  4881.3      .1       0  5098.6     .05       0    5463     .07       0
  5721.4     .05       0  6625.4     .05       0  6771.5     .12       0
  6917.7     .05       0  7183.9     .05       0  7648.5    .035       0
  7794.6     .05       0  8600.2    .035       0
Bank Sta=4357,4433
XS Rating Curve= 0 ,0
Exp/Cntr=0.3,0.1

Type RM Length L Ch R = 1 ,67576   ,2371,2371,2371
BEGIN DESCRIPTION:
ELM CREEK 35.0
END DESCRIPTION:
XS GIS Cut Line= 3
      2394237.31     13643847.78      2396212.15     13639550.87
      2398447.38     13637445.85
#Sta/Elev= 30
    31.1  283.25   164.7  282.13   416.2  273.49   837.6  266.98  1464.9   274.2
  2058.4  257.26  2397.4  255.77  2863.4  255.62  3028.3  255.83  3198.4  256.18
  3220.7  251.29  3222.2  250.29  3296.8  251.29  3324.8  256.23  3430.7  254.69
  3633.8  257.22  4140.2  256.07  4505.3  256.48  4879.6  257.81  5013.7  252.42
  5084.5  258.18  5234.5  257.19  5685.8   258.7  6537.2     281  6676.6  285.65
  6916.9  290.16  7428.9  289.47  7646.7  289.59  7759.2  289.65  7830.5  289.69
#Mann= 20 ,-1 , 0
    31.1     .05       0   164.7    .035       0   416.2     .07       0
  2058.4     .12       0  2397.4      .1       0  2863.4      .1       0
  3028.3     .12       0  3220.7     .05       0  3296.8     .12       0
  3430.7     .07       0  3633.8     .07       0  4140.2      .1       0
  4505.3      .1       0  4879.6      .1       0  5234.5     .05       0
  6537.2    .035       0  6676.6     .05       0  7428.9    .035       0
  7646.7     .05       0  7759.2    .035       0
Bank Sta=3220.7,3296.8
XS Rating Curve= 0 ,0
Exp/Cntr=0.3,0.1

Type RM Length L Ch R = 1 ,65205   ,2322,2322,2322
BEGIN DESCRIPTION:
ELM CREEK 34.0
END DESCRIPTION:
XS GIS Cut Line= 3
      2395257.27     13643587.36      2396863.19     13640657.64
      2398186.97     13639333.86
#Sta/Elev= 30
  1167.8  283.81  1669.7  288.55  1878.9  287.02  1905.6  287.04  2132.7  281.92
  2315.3   276.6  2362.6  274.54  2431.8  271.33    2717   258.6    2733  258.98
  2861.3  253.18  3178.9  255.09    3344  256.25  3415.8   255.8  3421.4  248.81
  3422.9  247.81  3497.5  248.81  3503.1  255.26  3597.4  254.68  3600.5  254.72
  3864.8  254.73  4197.4  254.72  4978.6  256.31  5006.9  249.86    5014  255.44
  5157.6   264.2  5194.1  265.81  5636.2  280.33  5982.7  285.95  6380.9  286.24
#Mann= 19 ,-1 , 0
  1167.8     .07       0  1878.9    .035       0  1905.6     .07       0
  2132.7    .035       0  2315.3     .07       0  2362.6    .035       0
  2431.8     .07       0    2717    .035       0    2733     .12       0
  3178.9      .1       0    3344     .12       0  3421.4     .05       0
  3497.5     .12       0  3597.4     .12       0  3600.5      .1       0
  3864.8     .12       0  4197.4      .1       0  5157.6     .07       0
  5194.1     .05       0
Bank Sta=3421.4,3497.5
XS Rating Curve= 0 ,0
Exp/Cntr=0.3,0.1

Type RM Length L Ch R = 1 ,62883   ,2314,2314,2314
BEGIN DESCRIPTION:
ELM CREEK 33.0
END DESCRIPTION:
XS GIS Cut Line= 3
      2395756.44     13643717.51      2397666.15     13641438.89
      2398317.18      13639724.5
#Sta/Elev= 30
  2436.6  299.73  2643.3  301.93  3090.9  285.79  3132.5  288.42  3168.9  283.34
  3189.8  287.75  3253.5   286.4  3672.4  265.67  3750.5  256.02  4106.6  254.72
  4148.6  254.64  4169.4  249.32  4190.3  254.97  4568.5  253.97  4865.5  256.41
    4933  249.18  4934.5  248.18  5009.2  249.18  5013.8  255.16  5056.8  255.65
  5520.8  251.87  5542.2  255.53  5574.3  250.59  5589.9  255.16  5776.1  256.95
  5791.9  257.99  6141.2  272.34  7024.2  280.29  7025.9  280.32  7243.5  282.11
#Mann= 9 ,-1 , 0
  2436.6     .07       0  4106.6      .1       0  4568.5     .12       0
    4933     .05       0  5009.2     .12       0  5776.1     .07       0
  5791.9     .05       0  7024.2    .035       0  7025.9     .05       0
Bank Sta=4933,5009.2
XS Rating Curve= 0 ,0
Exp/Cntr=0.3,0.1

Type RM Length L Ch R = 1 ,60569   ,971,971,971
BEGIN DESCRIPTION:
X19113
END DESCRIPTION:
XS GIS Cut Line= 3
      2396088.43     13644199.33      2397824.57     13642619.44
      2398397.36     13640189.42
#Sta/Elev= 30
  3046.7  301.92    3302  298.99  3592.5  282.18  3861.5  273.43  3946.6  263.57
  4038.5  263.71  4123.6  280.95    4173  265.57  4485.6  258.85  4675.5  255.63
  4864.7   252.8  4907.1  252.53  4951.4  253.45  4954.9  247.27  4956.4  246.27
  5032.9  247.27  5036.5  254.47  5043.8  254.13  5170.7  253.12  5206.1  250.83
  5327.1  254.41  5789.1  254.56    6087  251.19  6282.2  253.95  6652.1  252.02
  6698.6  254.89  6854.7  257.65  7515.1  276.99  7779.6   277.7  7890.7  277.94
#Mann= 12 ,-1 , 0
  3046.7     .05       0  4485.6     .12       0  4675.5     .07       0
  4864.7     .12       0  4907.1      .1       0  4954.9     .05       0
  5032.9      .1       0  5043.8      .1       0  5170.7     .12       0
  6698.6     .07       0  6854.7     .05       0  7779.6    .035       0
Bank Sta=4954.9,5032.9
XS Rating Curve= 0 ,0
Exp/Cntr=0.3,0.1

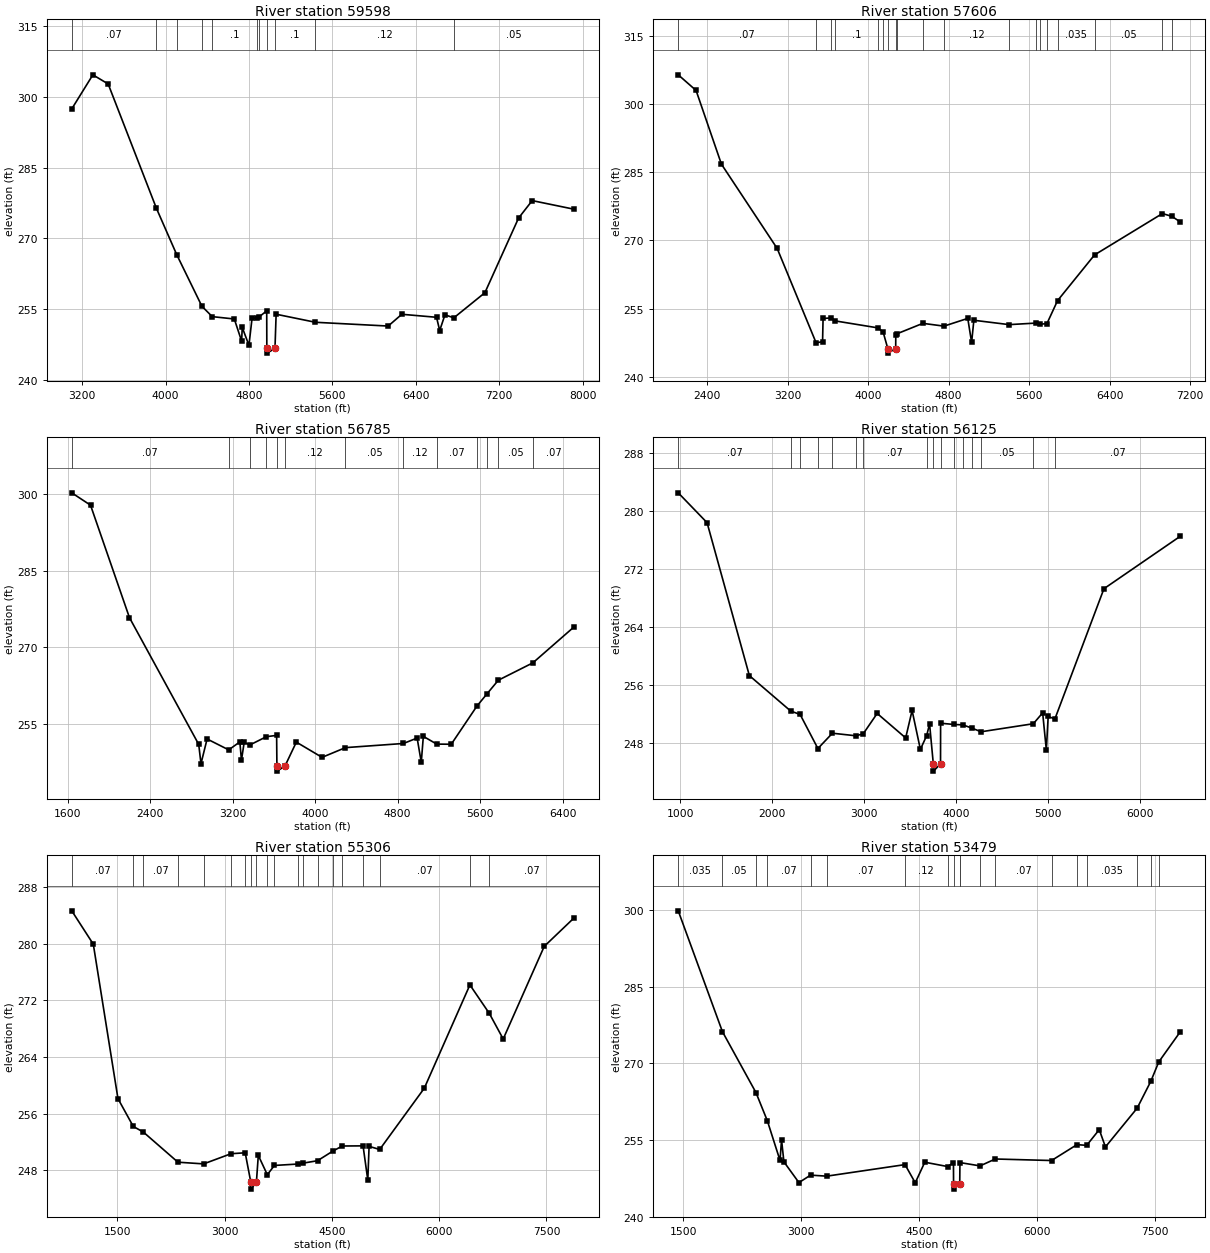
Type RM Length L Ch R = 1 ,59598   ,1992,1992,1992
BEGIN DESCRIPTION:
X19112
END DESCRIPTION:
XS GIS Cut Line= 3
      2398484.29     13645119.47      2398293.32     13642393.75
      2398553.59     13640328.89
#Sta/Elev= 30
  3101.1  297.49  3303.3  304.72    3450  302.78  3913.1  276.35    4107  266.55
  4348.9  255.57  4447.9  253.37  4659.4  252.87  4729.6  248.16  4735.4  251.08
  4799.7  247.28  4829.8  253.08  4878.7  253.05  4891.5  253.21  4970.1   254.6
  4971.2  246.62  4972.7  245.62  5049.3  246.62  5060.4  253.88  5437.3  252.17
  6134.6  251.37  6265.6  253.87  6598.3  253.23  6628.5  250.42  6678.9  253.75
  6764.4  253.12  7061.9  258.45  7384.4  274.29  7515.5  278.01  7914.7  276.19
#Mann= 11 ,-1 , 0
  3101.1     .07       0  3913.1     .12       0    4107     .07       0
  4348.9     .12       0  4447.9      .1       0  4878.7     .12       0
  4891.5      .1       0  4971.2     .05       0  5049.3      .1       0
  5437.3     .12       0  6764.4     .05       0
Bank Sta=4971.2,5049.3
XS Rating Curve= 0 ,0
Exp/Cntr=0.3,0.1

Type RM Length L Ch R = 1 ,57606   ,821,821,821
BEGIN DESCRIPTION:
X19111
END DESCRIPTION:
XS GIS Cut Line= 3
      2398935.68     13645240.95      2399334.98     13642150.69
      2398710.03     13640379.99
#Sta/Elev= 30
  2110.4  306.37  2287.8  302.94  2539.9  286.75  3094.5  268.23  3481.8   247.5
  3545.9  247.76    3551  252.86  3632.4  252.97    3671  252.32  4098.2  250.78
  4148.2  249.88  4194.7  246.24  4196.2  245.24  4273.1  246.24  4274.2  249.31
  4284.1  249.47  4543.4  251.78  4753.6  251.17  4990.1  252.87  5028.4  247.58
  5050.6  252.46  5401.4   251.5  5667.9  251.84  5711.7  251.59  5777.6  251.73
  5883.1  256.77  6250.9  266.81  6926.1   275.9  7020.7  275.28  7104.1  274.05
#Mann= 19 ,-1 , 0
  2110.4     .07       0  3481.8     .12       0  3632.4     .07       0
    3671      .1       0  4098.2     .07       0  4148.2     .12       0
  4194.7     .05       0  4273.1     .12       0  4284.1     .12       0
  4543.4     .07       0  4753.6     .12       0  5401.4     .07       0
  5667.9     .12       0  5711.7     .05       0  5777.6     .07       0
  5883.1    .035       0  6250.9     .05       0  6926.1    .035       0
  7020.7     .05       0
Bank Sta=4194.7,4273.1
XS Rating Curve= 0 ,0
Exp/Cntr=0.3,0.1

Type RM Length L Ch R = 1 ,56785   ,660,660,660
BEGIN DESCRIPTION:
X19110
END DESCRIPTION:
XS GIS Cut Line= 3
      2399022.49     13645258.31      2399821.09     13642740.97
       2399977.3     13640519.33
#Sta/Elev= 30
  1640.5  300.19  1822.3  297.78    2200   275.8  2871.4  251.05  2893.3  247.28
  2952.6  252.11  3162.4  249.98  3270.1  251.54  3285.8  247.97  3312.1  251.44
  3367.3  250.94  3527.9  252.56  3626.8  252.81  3629.5  246.83    3631  245.83
    3708  246.83  3817.9   251.5  4067.4  248.52  4293.9  250.42  4856.1  251.23
  4989.2  252.29  5029.3  247.56  5049.3  252.62  5178.9  251.11    5320  251.08
  5569.8  258.56  5668.3  260.97  5776.5  263.59  6111.3  266.98  6508.6  273.97
#Mann= 13 ,-1 , 0
  1640.5     .07       0  3162.4     .12       0  3367.3     .07       0
  3527.9     .12       0  3629.5     .05       0    3708     .12       0
  4293.9     .05       0  4856.1     .12       0  5178.9     .07       0
  5569.8     .05       0  5668.3    .035       0  5776.5     .05       0
  6111.3     .07       0
Bank Sta=3629.5,3708
XS Rating Curve= 0 ,0
Exp/Cntr=0.3,0.1

Type RM Length L Ch R = 1 ,56125   ,819,819,819
BEGIN DESCRIPTION:
X19109
END DESCRIPTION:
XS GIS Cut Line= 3
      2400550.26     13645848.61      2400411.37     13641369.44
      2400272.49     13640397.23
#Sta/Elev= 30
   978.7  282.53  1292.5  278.41  1752.7  257.31  2202.5  252.42  2304.9  251.95
  2498.4  247.25  2656.5  249.36  2910.3  249.01  2991.1  249.27  3143.4  252.09
  3453.5  248.71  3523.5   252.5  3613.6  247.13  3682.1  249.03  3713.6  250.65
  3754.4  245.13  3755.9  244.13  3832.9  245.13  3833.7  250.74    3978  250.57
  4076.7  250.51  4175.3  250.06  4273.9  249.56  4842.6  250.67  4944.2  252.17
  4984.2  247.05  5004.2  251.67  5077.3  251.33  5611.1   269.3  6442.1  276.54
#Mann= 16 ,-1 , 0
   978.7     .07       0  2202.5     .12       0  2304.9     .07       0
  2498.4     .12       0  2656.5     .07       0  2910.3     .12       0
  2991.1     .07       0  3682.1     .12       0  3754.4     .05       0
  3832.9     .12       0    3978     .05       0  4076.7     .12       0
  4175.3     .07       0  4273.9     .05       0  4842.6     .12       0
  5077.3     .07       0
Bank Sta=3754.4,3832.9
XS Rating Curve= 0 ,0
Exp/Cntr=0.3,0.1

Type RM Length L Ch R = 1 ,55306   ,1827,1827,1827
BEGIN DESCRIPTION:
X19108
END DESCRIPTION:
XS GIS Cut Line= 3
      2400637.06     13645761.81      2401209.98     13642359.03
      2400949.57     13638800.02
#Sta/Elev= 30
   863.3  284.68  1164.3  279.96  1509.1  258.11  1723.1  254.18  1865.3  253.37
  2347.6  249.12  2706.9  248.88    3090  250.32  3287.9  250.45  3366.1  246.31
  3367.6  245.31  3444.6  246.31  3471.1  250.08    3597  247.35  3696.4  248.66
    4026  248.86    4094  248.98  4299.2  249.33  4518.1  250.72  4645.6  251.41
  4935.6  251.43  5001.9  246.59  5019.9  251.36  5168.3  250.92  5791.9  259.59
  6429.3   274.2  6700.7  270.17  6894.9  266.55  7468.5  279.65  7882.5  283.65
#Mann= 20 ,-1 , 0
   863.3     .07       0  1723.1     .12       0  1865.3     .07       0
  2347.6      .1       0  2706.9     .12       0    3090     .07       0
  3287.9     .12       0  3366.1     .05       0  3444.6     .12       0
    3597     .12       0  3696.4     .12       0    4026     .07       0
    4094     .12       0  4299.2     .05       0  4518.1     .12       0
  4645.6     .05       0  4935.6     .12       0  5168.3     .07       0
  6429.3    .035       0  6700.7     .07       0
Bank Sta=3366.1,3444.6
XS Rating Curve= 0 ,0
Exp/Cntr=0.3,0.1

Type RM Length L Ch R = 1 ,53479   ,262,262,262
BEGIN DESCRIPTION:
F21660a
END DESCRIPTION:
XS GIS Cut Line= 4
      2402361.09     13645463.25      2402089.82     13642804.79
      2402523.84     13640178.92      2402176.62     13639180.65
#Sta/Elev= 30
  1435.2  299.89  1997.5  276.24  2424.6   264.3  2569.9  258.76  2730.8  251.01
  2750.2  255.04  2780.4  250.74  2971.4  246.68  3119.7  248.14  3325.4  247.94
  4321.7   250.2  4451.9  246.64  4573.5  250.67  4864.3  249.82  4938.4  250.59
  4939.7   246.4  4941.2   245.4  5018.2   246.4  5020.8   250.6  5276.8  249.95
  5470.7   251.3  6187.1     251  6510.3  254.11  6634.1  253.97  6794.3  257.05
  6872.8  253.66  7276.4  261.25  7450.7  266.52  7551.3   270.3  7825.9  276.22
#Mann= 19 ,-1 , 0
  1435.2    .035       0  1997.5     .05       0  2424.6    .035       0
  2569.9     .07       0  3119.7    .035       0  3325.4     .07       0
  4321.7     .12       0  4864.3    .035       0  4939.7    .035       0
  5018.2    .035       0  5020.8     .07       0  5276.8    .035       0
  5470.7     .07       0  6187.1    .035       0  6510.3     .07       0
  6634.1    .035       0  7276.4     .07       0  7450.7    .035       0
  7551.3     .07       0
Bank Sta=4939.7,5018.2
XS Rating Curve= 0 ,0
Exp/Cntr=0.3,0.1

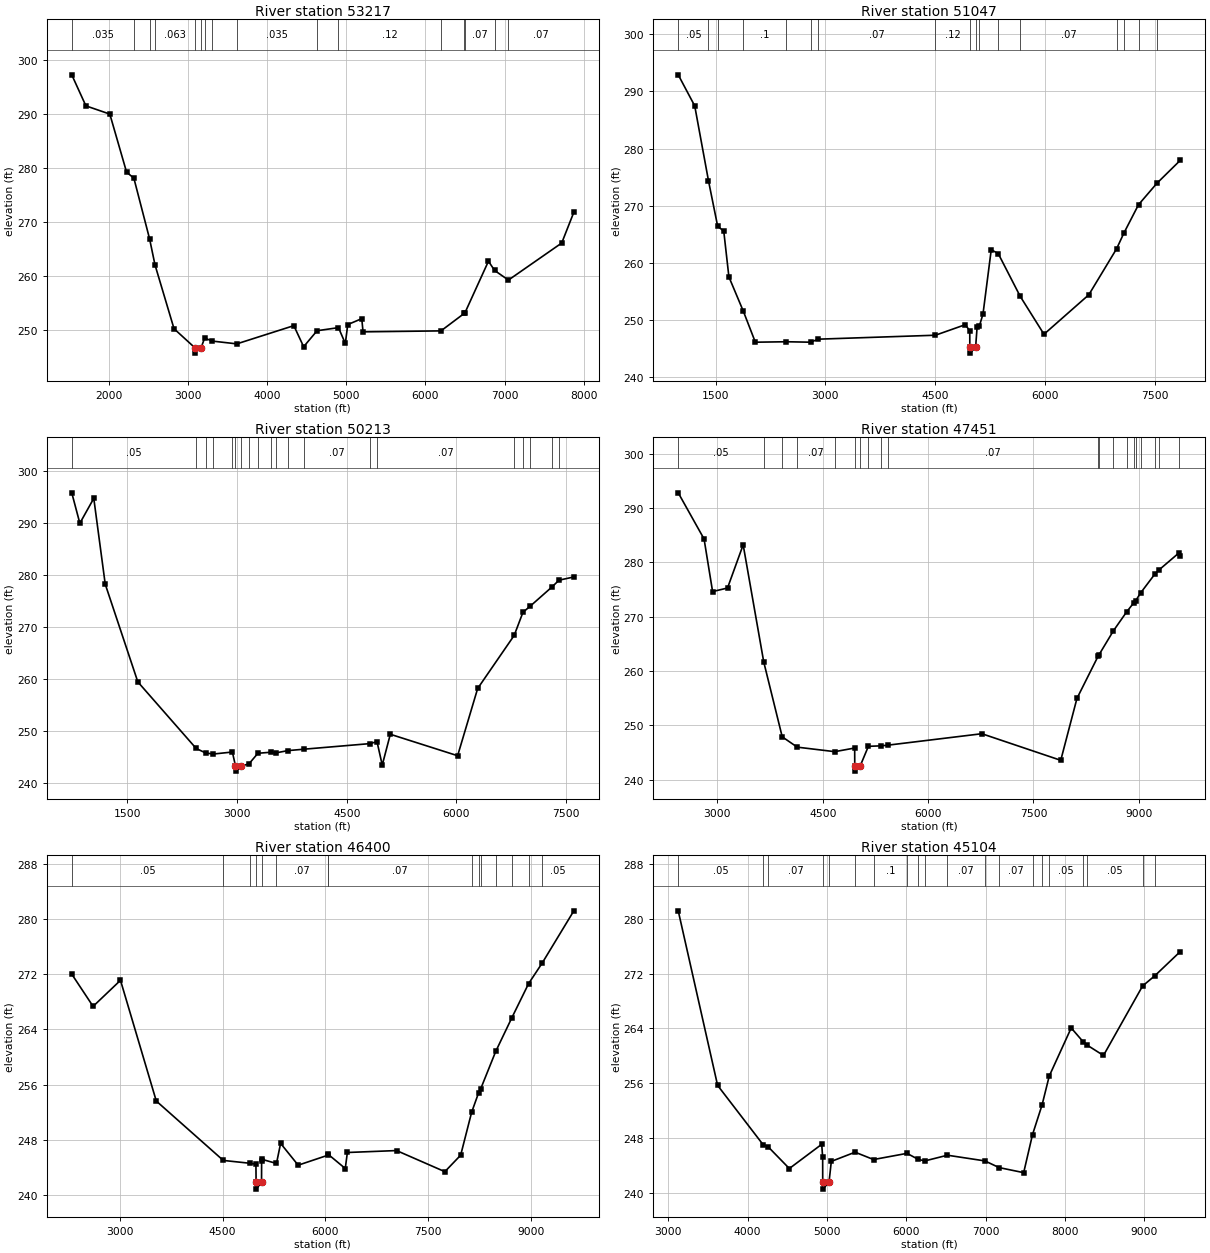
Type RM Length L Ch R = 1 ,53217   ,2170,2170,2170
BEGIN DESCRIPTION:
F21659a
END DESCRIPTION:
XS GIS Cut Line= 5
       2402578.1     13645463.23      2402317.68     13642848.19
      2402675.75     13640851.66      2402827.66     13640244.02
      2402329.27     13639312.24
#Sta/Elev= 30
  1535.8  297.31  1714.2  291.55  2016.3  290.02  2227.7  279.25    2320  278.12
  2518.5  266.85  2586.5  262.04  2826.9  250.18  3089.8  246.65  3091.3  245.65
  3168.3  246.65  3213.5  248.44  3312.7  247.88  3619.8  247.37  4339.7  250.75
  4463.4  246.84  4633.3  249.81  4903.3  250.38  4989.9  247.44  5020.4  250.95
  5197.4  252.05  5213.5   249.6  6197.7  249.78  6491.9  253.03  6500.1  253.13
  6796.9  262.71  6875.3  260.99    7049  259.21  7722.1  266.09  7875.2  271.81
#Mann= 16 ,-1 , 0
  1535.8    .035       0    2320    .063       0  2518.5     .12       0
  2586.5    .063       0  3089.8     .05       0  3168.3    .063       0
  3213.5      .1       0  3312.7     .07       0  3619.8    .035       0
  4633.3     .07       0  4903.3     .12       0  6197.7     .07       0
  6491.9     .12       0  6500.1     .07       0  6875.3    .063       0
    7049     .07       0
Bank Sta=3089.8,3168.3
XS Rating Curve= 0 ,0
Exp/Cntr=0.3,0.1

Type RM Length L Ch R = 1 ,51047   ,834,834,834
BEGIN DESCRIPTION:
ELM CREEK 28.0
END DESCRIPTION:
XS GIS Cut Line= 3
        2403575.     13645374.95      2403866.23     13641022.22
      2404057.19     13638539.82
#Sta/Elev= 30
   991.4  292.89  1216.4  287.46  1404.2  274.37  1529.2  266.43  1612.7  265.55
  1682.9  257.56  1881.3  251.51  2043.7  246.14  2468.3  246.22  2798.5  246.14
  2902.4  246.67  4501.1  247.36  4910.1  249.21  4970.2  248.11  4970.8  245.23
  4972.3  244.23  5049.8  245.23  5070.5  248.82  5101.3  248.98  5150.6  251.06
  5263.2  262.31  5358.8  261.63  5658.4  254.16  5982.9  247.53  6594.7  254.43
  6974.2  262.48  7072.8   265.2    7273  270.18  7524.4  273.93  7843.6  277.95
#Mann= 17 ,-1 , 0
   991.4     .05       0  1404.2     .07       0  1529.2     .05       0
  1881.3      .1       0  2468.3     .07       0  2798.5     .12       0
  2902.4     .07       0  4501.1     .12       0  4970.8     .05       0
  5049.8     .12       0  5101.3     .07       0  5358.8    .035       0
  5658.4     .07       0  6974.2    .035       0  7072.8     .05       0
    7273     .07       0  7524.4     .05       0
Bank Sta=4970.8,5049.8
XS Rating Curve= 0 ,0
Exp/Cntr=0.3,0.1

Type RM Length L Ch R = 1 ,50213   ,2762,2762,2762
BEGIN DESCRIPTION:
X19107
END DESCRIPTION:
XS GIS Cut Line= 2
       2404282.9     13645674.95      2404838.46     13638834.67
#Sta/Elev= 30
   741.6  295.82   851.9  289.97  1042.5  294.76  1198.9  278.28  1644.5   259.5
  2442.2  246.71  2570.4  245.86  2674.9  245.64  2936.7  246.03  2979.5  243.36
    2981  242.36  3058.5  243.36    3162  243.73  3286.1  245.79  3464.4  245.99
    3530  245.86  3695.2   246.3  3914.1  246.57  4821.8  247.65  4913.8  248.03
  4985.5  243.52  5095.8  249.44  6015.7  245.32  6289.8  258.24  6788.9  268.43
  6908.8  272.87  7007.4  274.04  7303.2  277.71  7401.8  279.04  7604.4  279.66
#Mann= 20 ,-1 , 0
   741.6     .05       0  2442.2      .1       0  2570.4     .07       0
  2674.9     .12       0  2936.7      .1       0  2979.5     .05       0
  3058.5      .1       0    3162     .07       0  3286.1     .12       0
  3464.4     .07       0    3530     .12       0  3695.2     .07       0
  3914.1     .07       0  4821.8     .12       0  4913.8     .07       0
  6788.9     .05       0  6908.8     .07       0  7007.4     .05       0
  7303.2    .035       0  7401.8     .05       0
Bank Sta=2979.5,3058.5
XS Rating Curve= 0 ,0
Exp/Cntr=0.3,0.1

Type RM Length L Ch R = 1 ,47451   ,1051,1051,1051
BEGIN DESCRIPTION:
X19106
END DESCRIPTION:
XS GIS Cut Line= 3
      2404942.62     13645848.63       2405532.9     13641942.36
      2405046.79     13638782.65
#Sta/Elev= 30
  2443.3  292.78  2811.1  284.29  2932.4  274.62  3144.8  275.27  3367.6  283.22
  3660.6  261.67  3923.6   247.9  4137.5     246  4671.6  245.17  4955.1  245.84
  4956.1  242.59  4957.6  241.59  5035.1  242.59  5150.1  246.15  5325.8  246.24
  5430.7  246.37  6765.6  248.47  7888.7  243.58  8119.6  254.97  8425.1  262.85
  8432.8  262.98  8638.3   267.4  8825.5  270.86  8925.6  272.51  8956.6  272.96
  9025.8  274.37  9229.4  277.85  9290.5  278.63  9566.9  281.68  9590.8  281.12
#Mann= 20 ,-1 , 0
  2443.3     .05       0  3660.6    .045       0  3923.6     .05       0
  4137.5     .07       0  4671.6      .1       0  4956.1     .05       0
  5035.1      .1       0  5150.1     .07       0  5325.8      .1       0
  5430.7     .07       0  8425.1     .05       0  8432.8     .07       0
  8638.3     .05       0  8825.5     .07       0  8925.6     .05       0
  8956.6     .07       0  9025.8     .05       0  9229.4    .035       0
  9290.5     .05       0  9566.9    .035       0
Bank Sta=4956.1,5035.1
XS Rating Curve= 0 ,0
Exp/Cntr=0.3,0.1

Type RM Length L Ch R = 1 ,46400   ,1296,1296,1296
BEGIN DESCRIPTION:
ELM CREEK 27.0
END DESCRIPTION:
XS GIS Cut Line= 3
      2407025.97     13645848.66      2406209.98     13643522.22
      2405133.59      13638782.6
#Sta/Elev= 30
  2298.9     272  2610.1  267.33  3009.7  271.11  3532.1  253.61  4509.7     245
  4897.3  244.59  4985.9  244.46  4988.4  241.84  4989.9  240.84  5067.7  241.84
  5069.1  244.94  5077.2  245.15  5285.8  244.56    5346  247.47  5602.3  244.31
  6034.4  245.75  6038.3   245.9  6289.4  243.83  6320.1  246.15    7038  246.43
  7742.4  243.37  7973.2  245.76  8132.9  251.97  8234.6  254.79  8266.4   255.4
  8484.7   260.8    8716   265.6    8965  270.64  9161.5  273.59  9624.6  281.18
#Mann= 15 ,-1 , 0
  2298.9     .05       0  4509.7     .07       0  4897.3      .1       0
  4988.4     .05       0  5067.7      .1       0  5285.8     .07       0
  6034.4     .12       0  6038.3     .07       0  8132.9     .05       0
  8234.6     .07       0  8266.4     .05       0  8484.7     .07       0
    8716     .05       0    8965     .07       0  9161.5     .05       0
Bank Sta=4988.4,5067.7
XS Rating Curve= 0 ,0
Exp/Cntr=0.3,0.1

Type RM Length L Ch R = 1 ,45104   ,1232,1232,1232
BEGIN DESCRIPTION:
ELM CREEK 26.0
END DESCRIPTION:
XS GIS Cut Line= 3
        2407825.     13644875.01      2406817.62     13642706.25
      2405515.55     13638991.01
#Sta/Elev= 30
  3126.1  281.13  3622.3   255.7  4194.2  247.09  4257.1  246.78  4526.4  243.59
  4934.4  247.12  4946.5   245.2  4947.1  241.59  4948.6  240.59  5026.4  241.59
  5055.5  244.63  5355.1  245.97  5587.7   244.9  6009.5   245.8  6151.9  244.92
  6234.6   244.7    6519  245.53  6991.7   244.7  7169.5  243.73  7479.9  242.99
  7591.3  248.53  7711.9  252.86  7802.2  257.06    8079  264.07  8229.4  262.06
  8279.5  261.57  8485.7  260.06  8979.2  270.19    9133  271.67  9454.2   275.2
#Mann= 20 ,-1 , 0
  3126.1     .05       0  4194.2     .05       0  4257.1     .07       0
  4947.1     .05       0  5026.4      .1       0  5355.1     .07       0
  5587.7      .1       0  6009.5     .12       0  6151.9     .07       0
  6234.6     .12       0    6519     .07       0  6991.7     .12       0
  7169.5     .07       0  7591.3     .12       0  7711.9     .12       0
  7802.2     .05       0  8229.4     .07       0  8279.5     .05       0
  8979.2     .07       0    9133     .05       0
Bank Sta=4947.1,5026.4
XS Rating Curve= 0 ,0
Exp/Cntr=0.3,0.1

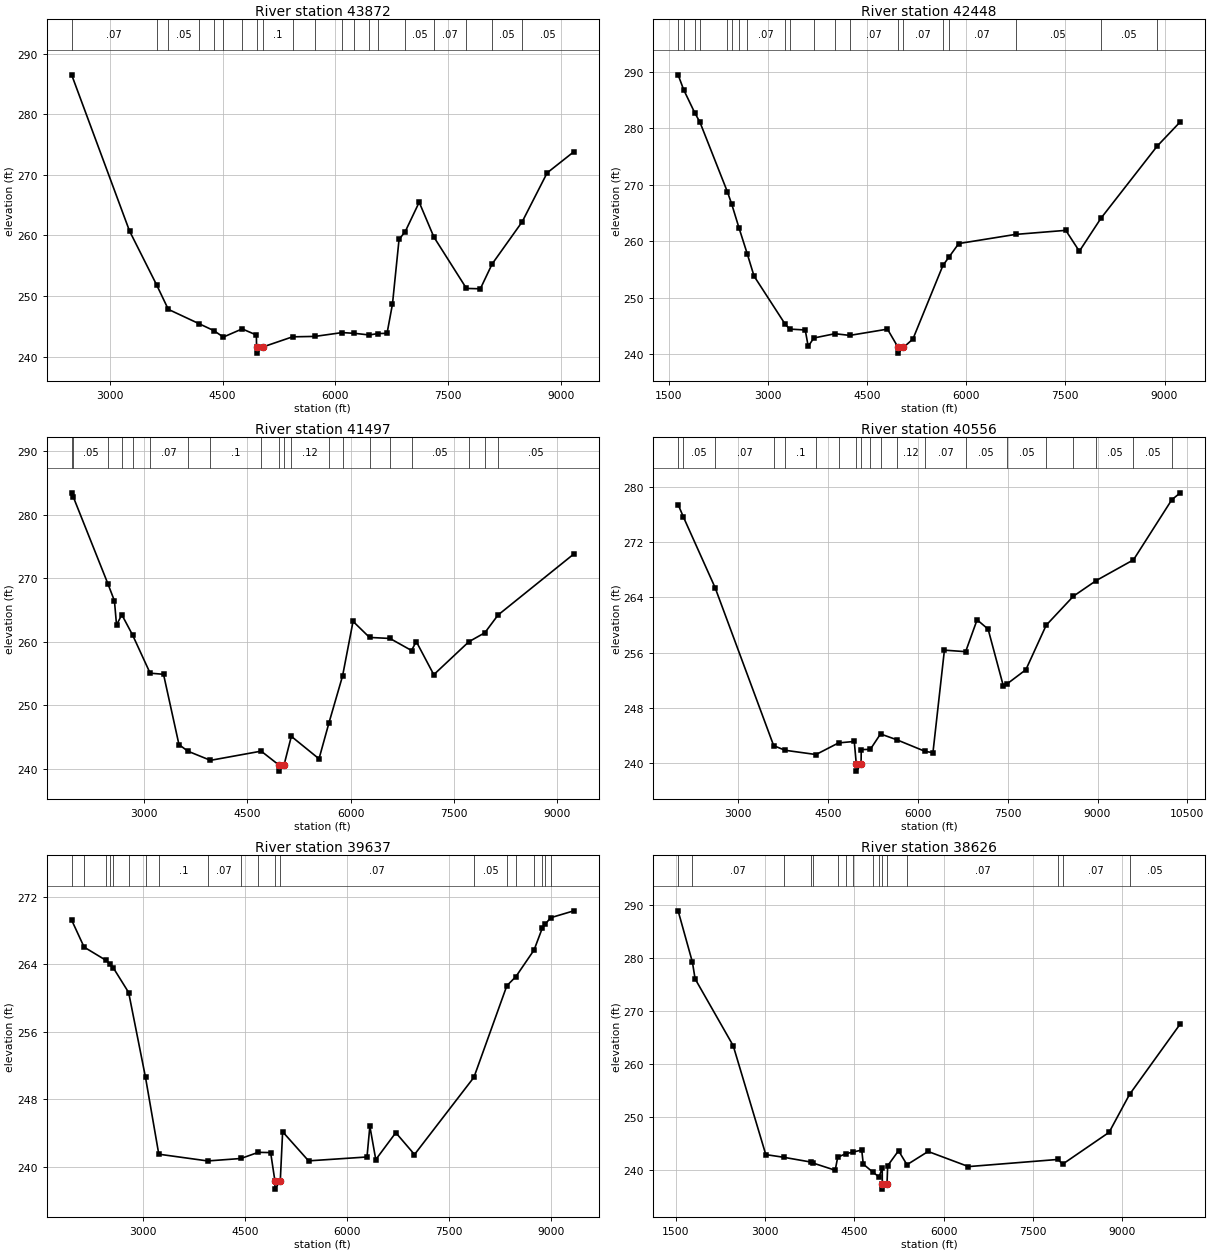
Type RM Length L Ch R = 1 ,43872   ,1424,1424,1424
BEGIN DESCRIPTION:
ELM CREEK 25.0
END DESCRIPTION:
XS GIS Cut Line= 3
      2409508.61     13644598.63      2408050.26      13642636.8
      2405723.87     13639095.13
#Sta/Elev= 30
  2492.8   286.5  3262.6  260.73    3624  251.81  3778.5  247.79  4182.4  245.45
  4385.5  244.27  4510.9  243.21  4761.8  244.56  4950.7  243.55  4953.2  241.56
  4954.7  240.56  5032.6  241.56  5431.7  243.25  5730.3  243.32  6090.7  243.95
  6255.6  243.83  6451.1  243.56  6571.2  243.79  6689.3  243.83  6761.6  248.67
    6849  259.33  6931.6  260.63    7117  265.47  7312.3  259.73  7745.8  251.24
  7930.7  251.18  8087.2  255.27  8487.3  262.24  8819.7  270.32  9174.7   273.8
#Mann= 20 ,-1 , 0
  2492.8     .07       0    3624     .07       0  3778.5     .05       0
  4182.4     .07       0  4385.5      .1       0  4510.9     .07       0
  4761.8     .07       0  4953.2     .05       0  5032.6      .1       0
  5431.7     .12       0  5730.3      .1       0  6090.7     .07       0
  6255.6     .07       0  6451.1     .12       0  6571.2     .12       0
  6931.6     .05       0  7312.3     .07       0  7745.8     .05       0
  8087.2     .05       0  8487.3     .05       0
Bank Sta=4953.2,5032.6
XS Rating Curve= 0 ,0
Exp/Cntr=0.3,0.1

Type RM Length L Ch R = 1 ,42448   ,951,951,951
BEGIN DESCRIPTION:
ELM CREEK 24.0
END DESCRIPTION:
XS GIS Cut Line= 3
        2409875.     13644525.01        2408375.       13641525.
      2405374.96     13638524.96
#Sta/Elev= 30
  1641.5  289.45  1724.6  286.83  1891.2  282.77  1971.8  281.05  2387.8   268.7
  2449.9  266.64  2561.6  262.37  2687.1  257.75  2790.3  253.79  3259.7   245.3
  3328.9  244.41  3564.5  244.25  3609.2  241.35  3694.8  242.83  4014.3  243.59
  4237.8  243.29  4808.3   244.4    4970  241.15  4971.5  240.15  5049.6  241.15
  5193.6  242.65  5647.3  255.68  5734.7   257.1  5886.6  259.56  6745.9  261.18
  7505.8   261.9  7710.9   258.2  8038.3  264.05  8887.7  276.81  9238.3  281.13
#Mann= 20 ,-1 , 0
  1641.5     .05       0  1724.6     .07       0  1891.2     .05       0
  1971.8     .07       0  2387.8     .07       0  2449.9     .05       0
  2561.6     .07       0  2687.1     .07       0  3259.7     .05       0
  3328.9     .07       0  3694.8     .07       0  4014.3     .12       0
  4237.8     .07       0    4970     .05       0  5049.6     .07       0
  5647.3     .05       0  5734.7     .07       0  6745.9     .05       0
  8038.3     .05       0  8887.7     .05       0
Bank Sta=4970,5049.6
XS Rating Curve= 0 ,0
Exp/Cntr=0.3,0.1

Type RM Length L Ch R = 1 ,41497   ,941,941,941
BEGIN DESCRIPTION:
ELM CREEK 23.0
END DESCRIPTION:
XS GIS Cut Line= 3
        2409825.     13644325.02        2409225.       13641325.
      2406224.98     13638324.98
#Sta/Elev= 30
  1944.8  283.45  1966.9  282.85  2472.1  269.11  2566.9  266.43  2597.5  262.62
  2674.2  264.24    2831  261.04  3085.8  255.03  3280.8  254.85  3505.1  243.78
  3633.2  242.74  3963.5  241.29  4700.5  242.74  4954.2  240.59  4955.7  239.59
  5033.8  240.59    5139  245.07  5541.6  241.53  5686.5  247.21  5884.1  254.59
  6036.6  263.19  6276.2  260.66  6573.5   260.5  6886.7   258.6  6955.8  260.01
  7210.4  254.79  7720.1  259.98  7953.1   261.4  8144.5  264.19  9246.9  273.81
#Mann= 20 ,-1 , 0
  1944.8     .07       0  1966.9     .05       0  2472.1     .07       0
  2674.2     .05       0    2831     .07       0  3085.8     .07       0
  3633.2     .12       0  3963.5      .1       0  4700.5     .07       0
  4954.2     .05       0  5033.8     .12       0    5139     .12       0
  5686.5    .035       0  5884.1     .05       0  6276.2     .07       0
  6573.5    .035       0  6886.7     .05       0  7720.1     .05       0
  7953.1     .05       0  8144.5     .05       0
Bank Sta=4954.2,5033.8
XS Rating Curve= 0 ,0
Exp/Cntr=0.3,0.1

Type RM Length L Ch R = 1 ,40556   ,919,919,919
BEGIN DESCRIPTION:
ELM CREEK 22.0
END DESCRIPTION:
XS GIS Cut Line= 3
        2410075.     13644075.01        2410075.       13641075.
      2406074.97     13637474.97
#Sta/Elev= 30
    2000   277.5  2085.6  275.74  2616.8  265.44  3594.8  242.48  3784.7  241.81
  4301.5  241.19  4678.3  242.88    4940  243.09    4974  239.78  4975.5  238.78
  5053.6  239.78  5056.4  241.91  5207.7  241.94    5378  244.18  5651.4  243.33
  6124.8  241.64  6253.1  241.47  6444.4  256.35  6798.6  256.13    6990  260.76
  7173.9   259.4  7428.8  251.12  7482.5   251.4    7804  253.51  8143.1  259.97
  8596.3  264.18  8978.7  266.46  9600.1  269.47 10239.8   278.2 10381.5   279.2
#Mann= 20 ,-1 , 0
    2000     .07       0  2085.6     .05       0  2616.8     .07       0
  3594.8     .07       0  3784.7      .1       0  4301.5     .07       0
  4678.3      .1       0    4974     .05       0  5053.6      .1       0
  5207.7     .12       0    5378     .07       0  5651.4     .12       0
  6124.8     .07       0  6798.6     .05       0  7482.5     .05       0
  8143.1    .035       0  8596.3     .05       0  8978.7     .05       0
  9600.1     .05       0 10239.8     .05       0
Bank Sta=4974,5053.6
XS Rating Curve= 0 ,0
Exp/Cntr=0.3,0.1

Type RM Length L Ch R = 1 ,39637   ,1011,1011,1011
BEGIN DESCRIPTION:
ELM CREEK 21.0
END DESCRIPTION:
XS GIS Cut Line= 3
        2410175.       13643575.        2410775.       13640575.
      2407174.98     13638174.99
#Sta/Elev= 30
  1945.4  269.21  2128.7  266.01  2451.3  264.44  2502.5  264.02  2555.1  263.59
  2783.8  260.63  3031.9  250.56    3227  241.47  3946.6  240.67    4434  240.96
  4690.8  241.69  4872.2  241.66  4934.4  238.33  4935.9  237.33    5014  238.33
  5048.4  244.13    5430  240.68  6289.3  241.14  6331.4  244.78  6418.5  240.83
  6712.9  244.02  6987.9  241.43  7862.5  250.59  8346.5  261.44  8477.9   262.5
  8746.6  265.67  8867.9  268.27  8907.6   268.7  8989.7  269.49  9331.5  270.31
#Mann= 20 ,-1 , 0
  1945.4     .07       0  2128.7     .05       0  2451.3     .07       0
  2502.5     .05       0  2555.1     .07       0  2783.8     .05       0
  3031.9     .07       0    3227      .1       0  3946.6     .07       0
    4434     .12       0  4690.8     .07       0  4934.4     .05       0
    5014     .07       0  7862.5     .05       0  8346.5    .035       0
  8477.9     .05       0  8746.6    .035       0  8867.9     .05       0
  8907.6    .035       0  8989.7     .05       0
Bank Sta=4934.4,5014
XS Rating Curve= 0 ,0
Exp/Cntr=0.3,0.1

Type RM Length L Ch R = 1 ,38626   ,916,916,916
BEGIN DESCRIPTION:
X19105
END DESCRIPTION:
XS GIS Cut Line= 3
      2412216.93      13644338.2      2411591.93     13640553.47
      2407564.17     13638331.26
#Sta/Elev= 30
    1541  288.85  1781.3  279.16    1826  276.03  2466.6  263.41  3013.9  242.88
  3311.8  242.38  3769.1  241.48  3812.6  241.27  4179.5  239.93    4222  242.39
    4356  243.04    4480  243.36  4625.4  243.74  4651.5  241.09  4816.6  239.53
  4916.9  238.67    4970  240.38  4970.8  237.37  4972.3  236.37  5050.4  237.37
  5061.2  240.78  5243.7  243.61  5385.6  240.97  5740.4  243.47  6418.9  240.62
    7925  241.97  7998.3  241.06  8780.9  247.08    9124  254.22  9977.1  267.53
#Mann= 16 ,-1 , 0
    1541     .05       0  1781.3     .07       0  3311.8    .035       0
  3769.1     .07       0  3812.6      .1       0    4222     .07       0
    4356     .05       0    4480     .07       0  4816.6      .1       0
  4916.9     .07       0  4970.8     .05       0  5050.4     .07       0
  5385.6     .07       0    7925     .12       0  7998.3     .07       0
    9124     .05       0
Bank Sta=4970.8,5050.4
XS Rating Curve= 0 ,0
Exp/Cntr=0.3,0.1