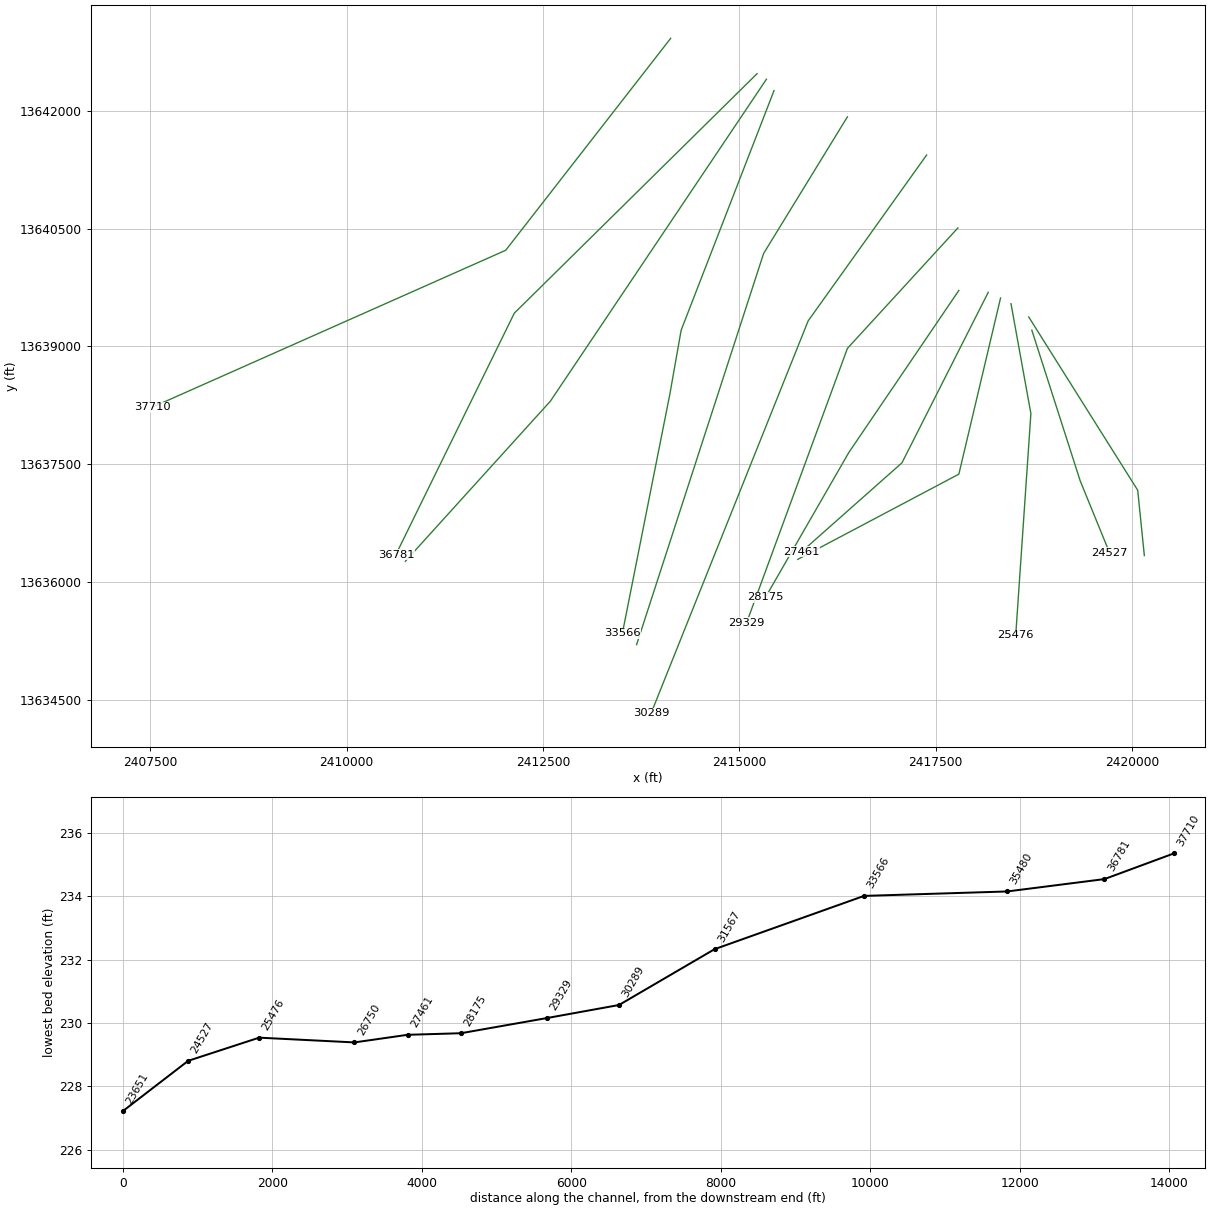
HEC-RAS study ELM CREEK.prj: ELM CREEK Base Level Engineering

--- ELM CREEK.g01 (geometry) --- (continued)

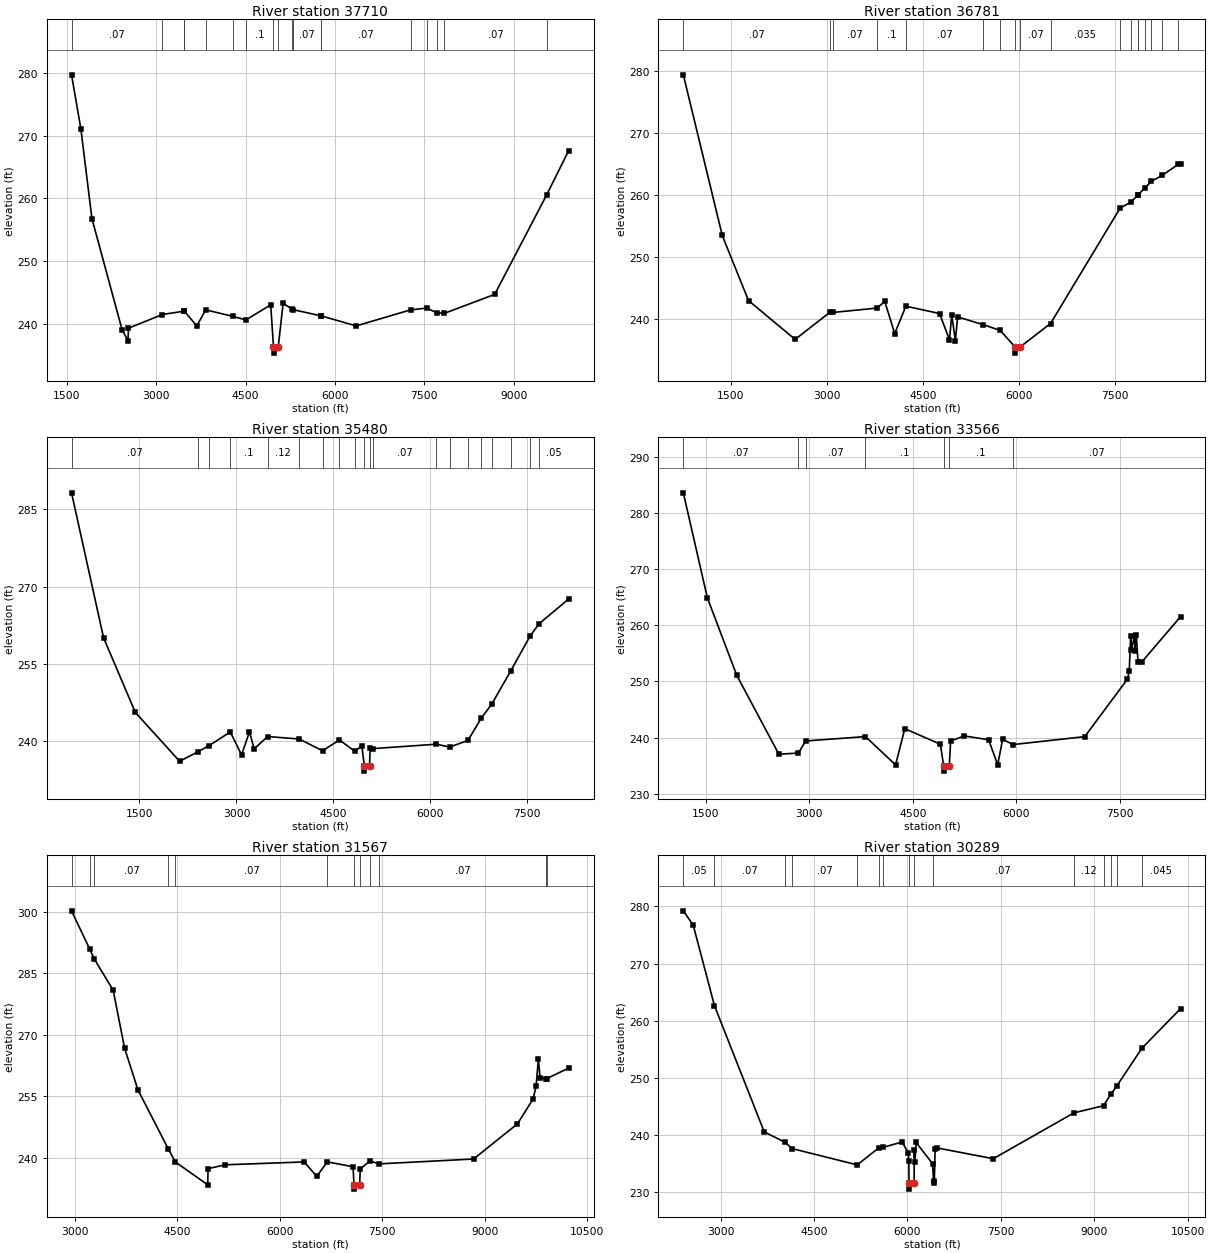
Type RM Length L Ch R = 1 ,37710   ,929,929,929
BEGIN DESCRIPTION:
ELM CREEK 20.0
END DESCRIPTION:
XS GIS Cut Line= 3
      2414124.99     13642924.99        2412025.       13640225.
      2407525.04     13638225.02
#Sta/Elev= 30
  1580.1   279.7  1736.6  271.12  1922.1   256.8  2428.9  239.07  2528.4  237.33
  2534.8  239.32  3102.4   241.5  3462.6  242.03    3475  242.02  3683.1  239.68
  3831.1  242.25  4286.1  241.21  4507.4  240.64  4922.8  243.05  4969.6  236.35
  4971.1  235.35  5049.4  236.35  5131.2  243.27  5275.5  242.42  5297.1  242.28
  5763.7   241.3    5765   241.3  6357.6  239.69  7269.1  242.24  7543.2  242.53
  7705.6  241.79    7837  241.69  8682.3  244.71  9553.1  260.55    9925  267.64
#Mann= 18 ,-1 , 0
  1580.1     .07       0  3102.4     .05       0  3462.6    .063       0
    3475     .07       0  3831.1     .05       0  4286.1     .07       0
  4507.4      .1       0  4969.6     .05       0  5049.4      .1       0
  5275.5     .05       0  5297.1     .07       0  5763.7     .05       0
    5765     .07       0  7269.1     .05       0  7543.2     .07       0
  7705.6     .12       0    7837     .07       0  9553.1     .05       0
Bank Sta=4969.6,5049.4
XS Rating Curve= 0 ,0
Exp/Cntr=0.3,0.1

Type RM Length L Ch R = 1 ,36781   ,1301,1301,1301
BEGIN DESCRIPTION:
ELM CREEK 19.0
END DESCRIPTION:
XS GIS Cut Line= 3
        2415225.       13642475.      2412134.67     13639423.87
      2410627.16     13636348.55
#Sta/Elev= 30
   757.1  279.44  1365.2  253.52  1775.4  243.02  2503.7  236.75  3047.2  241.14
  3090.9   241.1    3785  241.81  3903.8  242.88  4059.4  237.69  4233.6  242.11
  4759.4  240.93    4915   236.7  4950.3  240.66  5006.9  236.56  5042.3  240.38
  5439.8  239.14  5706.3  238.21    5939  235.54  5940.5  234.54  6018.8  235.54
  6493.6  239.32  7582.8  257.97    7747  258.88  7856.9  260.03  7858.3  260.04
  7969.6  261.21    8068  262.25  8236.6  263.21  8490.3  265.01  8524.8  265.04
#Mann= 18 ,-1 , 0
   757.1     .07       0  3047.2    .035       0  3090.9     .07       0
    3785      .1       0  4233.6     .07       0  5439.8     .05       0
  5706.3     .07       0    5939     .05       0  6018.8     .07       0
  6493.6    .035       0  7582.8     .07       0    7747    .035       0
  7856.9     .07       0  7858.3     .05       0  7969.6    .035       0
    8068     .05       0  8236.6    .035       0  8490.3     .05       0
Bank Sta=5939,6018.8
XS Rating Curve= 0 ,0
Exp/Cntr=0.3,0.1

Type RM Length L Ch R = 1 ,35480   ,1914,1914,1914
BEGIN DESCRIPTION:
X19104
END DESCRIPTION:
XS GIS Cut Line= 3
      2415344.26     13642404.22      2412593.18     13638301.73
      2410747.08     13636262.57
#Sta/Elev= 30
   449.7  288.21   945.3  260.05  1436.1  245.56  2121.7  236.06  2406.1  237.92
  2575.5   239.1  2905.7  241.75  3079.2  237.32  3202.2  241.77  3274.2  238.48
  3482.7  240.87  3969.6  240.39  4332.4  238.11  4592.5   240.2    4831  238.01
  4939.8  239.06  4977.8  235.15  4979.3  234.15  5058.2  235.15    5069  238.72
  5119.2  238.53  6093.8  239.38    6297  238.82  6581.2  240.11  6789.4   244.5
  6946.9  247.12  7243.1  253.63  7539.8  260.34    7680  262.77  8139.9   267.6
#Mann= 20 ,-1 , 0
   449.7     .07       0  2406.1    .035       0  2575.5     .07       0
  2905.7      .1       0  3482.7     .12       0  3969.6      .1       0
  4332.4     .12       0  4592.5     .07       0    4831      .1       0
  4977.8     .05       0  5058.2      .1       0  5119.2     .07       0
  6093.8     .07       0    6297     .07       0  6581.2    .035       0
  6789.4     .05       0  6946.9     .07       0  7243.1     .07       0
  7539.8     .07       0    7680     .05       0
Bank Sta=4977.8,5058.2
XS Rating Curve= 0 ,0
Exp/Cntr=0.3,0.1

Type RM Length L Ch R = 1 ,33566   ,1999,1999,1999
BEGIN DESCRIPTION:
X19103
END DESCRIPTION:
XS GIS Cut Line= 4
      2415440.76     13642259.36       2414258.3     13639206.68
      2414113.51     13638386.19       2413510.2     13635345.52
#Sta/Elev= 30
  1172.9  283.65  1520.7  264.94  1947.3   251.1  2557.4  237.03  2839.9  237.23
  2946.8  239.39    3812  240.17    4249  235.13  4382.6  241.58  4898.7  238.81
  4945.1  235.01  4946.6  234.01  5027.9  235.01  5047.4  239.39  5243.9  240.29
    5597  239.61  5729.5  235.16  5800.9  239.67  5953.9  238.75    6991  240.16
  7610.2  250.42    7636  251.85  7656.3  258.06  7666.6   255.6  7712.6  258.18
  7717.7  255.51    7738  258.31  7763.8  253.41  7814.4  253.43  8379.7  261.56
#Mann= 7 ,-1 , 0
  1172.9     .07       0  2839.9    .035       0  2946.8     .07       0
    3812      .1       0  4945.1     .05       0  5027.9      .1       0
  5953.9     .07       0
Bank Sta=4945.1,5027.9
XS Rating Curve= 0 ,0
Exp/Cntr=0.3,0.1

Type RM Length L Ch R = 1 ,31567   ,1278,1278,1278
BEGIN DESCRIPTION:
ELM CREEK 18.0
END DESCRIPTION:
XS GIS Cut Line= 3
      2416374.98     13641924.97      2415308.05     13640184.04
      2413691.19     13635200.74
#Sta/Elev= 30
  2949.1  300.19  3215.6  290.85  3284.4  288.39    3559  280.83  3726.6  266.66
  3922.5  256.49  4367.1   242.1  4470.6  238.94  4942.9  233.39  4948.9  237.33
  5200.2  238.26  6356.7  238.96  6540.3  235.44  6693.9  238.98  7071.6  237.78
  7084.8  233.33  7086.3  232.33  7167.8  233.33  7176.7   237.2  7317.2   239.2
  7455.6  238.49  8836.5  239.67  9479.1  248.25  9710.3  254.39  9752.8  257.59
  9784.7  263.95  9811.4  259.39  9890.6   259.3  9907.2  259.28   10230  261.85
#Mann= 12 ,-1 , 0
  2949.1     .07       0  3215.6     .05       0  3284.4     .07       0
  4367.1    .035       0  4470.6     .07       0  6693.9      .1       0
  7084.8     .05       0  7167.8      .1       0  7317.2     .12       0
  7455.6     .07       0  9890.6    .033       0  9907.2     .07       0
Bank Sta=7084.8,7167.8
XS Rating Curve= 0 ,0
Exp/Cntr=0.3,0.1

Type RM Length L Ch R = 1 ,30289   ,960,960,960
BEGIN DESCRIPTION:
ELM CREEK 17.0
END DESCRIPTION:
XS GIS Cut Line= 3
      2417383.42     13641438.92        2415875.       13639325.
      2413874.99     13634324.98
#Sta/Elev= 30
  2402.7  279.24  2562.3  276.71  2902.2  262.66  3701.7  240.58  4031.6  238.78
  4148.9  237.66  5194.9  234.81  5537.9  237.77  5610.2  237.88  5915.1  238.81
  6013.4  236.95  6022.8  235.41  6025.7  231.57  6027.2  230.57  6108.7  231.57
    6109  237.45  6121.1  235.38  6139.9  238.73  6404.2  235.01  6421.3  231.72
  6432.1  231.97  6444.2  237.51  6468.4  237.79  7378.5  235.89  8674.2  243.91
  9148.6  245.16  9266.4  247.19  9361.9  248.62  9765.4  255.22 10384.8  262.13
#Mann= 15 ,-1 , 0
  2402.7     .05       0  2902.2     .07       0  4031.6    .035       0
  4148.9     .07       0  5194.9    .035       0  5537.9     .07       0
  5610.2     .12       0  6025.7     .05       0  6108.7     .12       0
  6404.2     .07       0  8674.2     .12       0  9148.6     .07       0
  9266.4     .12       0  9361.9     .07       0  9765.4    .045       0
Bank Sta=6025.7,6108.7
XS Rating Curve= 0 ,0
Exp/Cntr=0.3,0.1

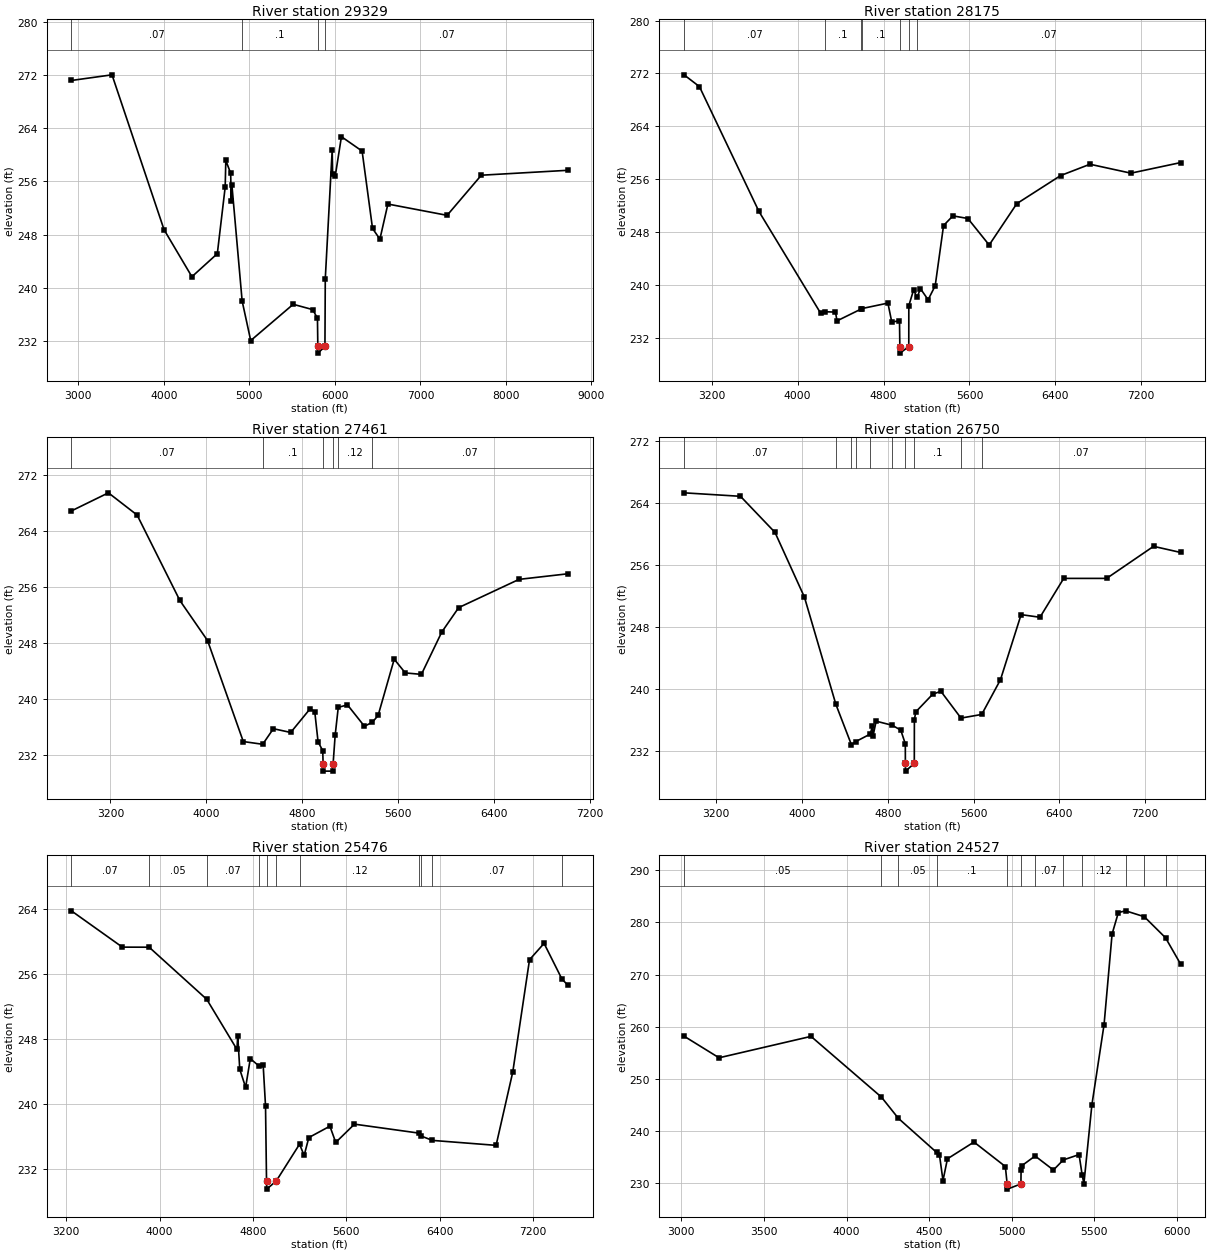
Type RM Length L Ch R = 1 ,29329   ,1154,1154,1154
BEGIN DESCRIPTION:
ELM CREEK 16.0
END DESCRIPTION:
XS GIS Cut Line= 3
      2417781.57     13640509.79        2416375.       13638975.
      2415091.17     13635479.12
#Sta/Elev= 30
  2918.3   271.2  3393.5  272.05  4002.1  248.74  4327.7  241.66  4624.9  245.13
  4716.8  255.14  4724.2  259.16  4780.9  257.24  4787.7   253.1  4795.1   255.5
  4915.1  238.01  5015.4  232.05  5512.3  237.51  5740.2  236.71  5795.8  235.41
  5800.2  231.16  5801.7  230.16  5883.3  231.16  5887.3  241.35  5968.1  260.75
  5973.4  257.09  6003.9  256.82  6076.1  262.74  6317.9  260.57  6439.8  248.93
    6526  247.31  6619.4   252.6  7311.8   250.9  7711.9  256.94  8724.3  257.68
#Mann= 4 ,-1 , 0
  2918.3     .07       0  4915.1      .1       0  5800.2     .05       0
  5883.3     .07       0
Bank Sta=5800.2,5883.3
XS Rating Curve= 0 ,0
Exp/Cntr=0.3,0.1

Type RM Length L Ch R = 1 ,28175   ,714,714,714
BEGIN DESCRIPTION:
X19102
END DESCRIPTION:
XS GIS Cut Line= 3
      2417793.65     13639713.44      2416393.99     13637650.16
      2415332.18     13635804.06
#Sta/Elev= 30
  2942.5  271.79  3085.5  270.01  3639.6  251.12  4214.6  235.71  4255.8  235.94
  4352.3  235.89  4366.5  234.56  4590.9  236.35  4594.8  236.41  4840.5  237.25
  4876.4  234.38  4948.3  234.58  4951.6  230.68  4953.1  229.68  5034.8  230.68
  5035.1  236.86  5079.4  239.23  5112.5   238.1    5143  239.44  5214.8  237.76
  5280.7  239.87  5358.6  248.99  5445.6  250.45    5585  250.05  5783.3  246.04
  6040.6   252.3  6448.8  256.55  6721.9  258.26  7102.8  256.91  7565.4  258.51
#Mann= 7 ,-1 , 0
  2942.5     .07       0  4255.8      .1       0  4590.9     .07       0
  4594.8      .1       0  4951.6     .05       0  5034.8      .1       0
  5112.5     .07       0
Bank Sta=4951.6,5034.8
XS Rating Curve= 0 ,0
Exp/Cntr=0.3,0.1

Type RM Length L Ch R = 1 ,27461   ,711,711,711
BEGIN DESCRIPTION:
X19101
END DESCRIPTION:
XS GIS Cut Line= 3
      2418167.72     13639689.36      2417069.69     13637517.43
      2415790.67      13636383.2
#Sta/Elev= 30
  2873.6  266.85  3182.7  269.44  3422.3  266.26  3778.9  254.04  4010.2   248.3
  4308.2  233.86  4469.9  233.47  4559.3   235.7  4703.8  235.16  4865.4  238.54
  4904.4  238.15  4932.2  233.81  4971.2  232.56  4974.2  230.63  4975.7  229.63
  5055.9  229.63  5057.4  230.63  5074.7  234.76  5100.6  238.75  5177.4  239.11
  5319.4  236.04  5386.1  236.64  5433.1  237.59  5567.5  245.64  5659.8  243.68
  5794.4  243.47  5964.2  249.52  6105.5  253.02    6609  257.06  7016.8  257.86
#Mann= 6 ,-1 , 0
  2873.6     .07       0  4469.9      .1       0  4974.2     .05       0
  5057.4      .1       0  5100.6     .12       0  5386.1     .07       0
Bank Sta=4974.2,5057.4
XS Rating Curve= 0 ,0
Exp/Cntr=0.3,0.1

Type RM Length L Ch R = 1 ,26750   ,1274,1274,1274
BEGIN DESCRIPTION:
X19100
END DESCRIPTION:
XS GIS Cut Line= 3
      2418324.56      13639616.9      2417793.66     13637372.64
      2415742.39     13636286.67
#Sta/Elev= 30
  2901.7  265.33  3427.7  264.88  3749.1  260.22  4023.7  251.85  4316.6  238.01
  4461.4   232.8  4502.4  233.21  4637.4  234.18  4657.4  235.26  4662.5  233.91
  4691.7  235.84  4842.4  235.31  4921.3  234.68  4963.6  232.92  4964.2  230.39
  4965.7  229.39  5047.4  230.39  5048.1  236.05  5061.6  237.05  5218.5  239.32
  5295.1   239.7  5482.4  236.24  5675.6  236.71  5850.2  241.19  6042.6   249.6
  6218.6  249.26  6439.7  254.28  6839.6  254.28    7277  258.42  7528.9  257.63
#Mann= 10 ,-1 , 0
  2901.7     .07       0  4316.6      .1       0  4461.4     .12       0
  4502.4      .1       0  4637.4     .12       0  4842.4      .1       0
  4964.2     .05       0  5047.4      .1       0  5482.4    .035       0
  5675.6     .07       0
Bank Sta=4964.2,5047.4
XS Rating Curve= 0 ,0
Exp/Cntr=0.3,0.1

Type RM Length L Ch R = 1 ,25476   ,949,949,949
BEGIN DESCRIPTION:
ELM CREEK 15.0
END DESCRIPTION:
XS GIS Cut Line= 3
      2418457.29     13639544.53      2418710.68     13638144.87
      2418517.62     13635321.37
#Sta/Elev= 30
  3244.6  263.81  3681.1  259.34  3910.8  259.33  4404.2  252.91  4662.5  246.75
  4669.5   248.4  4686.9  244.29    4737  242.07  4777.1  245.61    4853  244.68
  4887.4  244.78  4907.4  239.79    4916  230.54  4917.5  229.54  4999.2  230.54
  5198.8  235.07  5238.2  233.69  5278.3  235.89  5458.7  237.29  5508.8  235.29
  5669.2  237.54  6225.3  236.43    6238  236.09    6337  235.54    6882  234.93
  7024.9  243.96  7168.4  257.79    7293   259.8  7445.3  255.43  7497.1  254.64
#Mann= 11 ,-1 , 0
  3244.6     .07       0  3910.8     .05       0  4404.2     .07       0
    4853     .12       0    4916     .05       0  4999.2     .12       0
  5198.8     .12       0  6225.3     .07       0    6238     .12       0
    6337     .07       0  7445.3     .05       0
Bank Sta=4916,4999.2
XS Rating Curve= 0 ,0
Exp/Cntr=0.3,0.1

Type RM Length L Ch R = 1 ,24527   ,876,876,876
BEGIN DESCRIPTION:
ELM CREEK 14.0
END DESCRIPTION:
XS GIS Cut Line= 3
      2418722.74     13639206.71      2419338.12     13637288.18
      2419712.17     13636371.14
#Sta/Elev= 30
  3016.5  258.17  3228.3  254.02  3784.9  258.13  4211.2  246.47  4313.7   242.4
    4545  235.86  4562.1  235.42  4583.7  230.46  4610.6  234.63  4771.2  237.85
  4961.1  233.15    4972  229.81  4973.5  228.81  5055.3  229.81  5056.3  232.51
  5062.3  233.34  5141.2  235.17  5252.1  232.48  5311.6  234.41  5407.2  235.44
  5426.3  231.47  5436.6  229.87  5484.7  244.95  5558.5  260.38  5607.1  277.78
  5645.1   281.9  5689.4  282.23    5802   281.1  5930.5  277.06  6021.7  272.01
#Mann= 12 ,-1 , 0
  3016.5     .05       0  4211.2    .035       0  4313.7     .05       0
    4545      .1       0    4972     .05       0  5055.3      .1       0
  5141.2     .07       0  5311.6      .1       0  5426.3     .12       0
  5689.4     .07       0    5802     .05       0  5930.5     .07       0
Bank Sta=4972,5055.3
XS Rating Curve= 0 ,0
Exp/Cntr=0.3,0.1

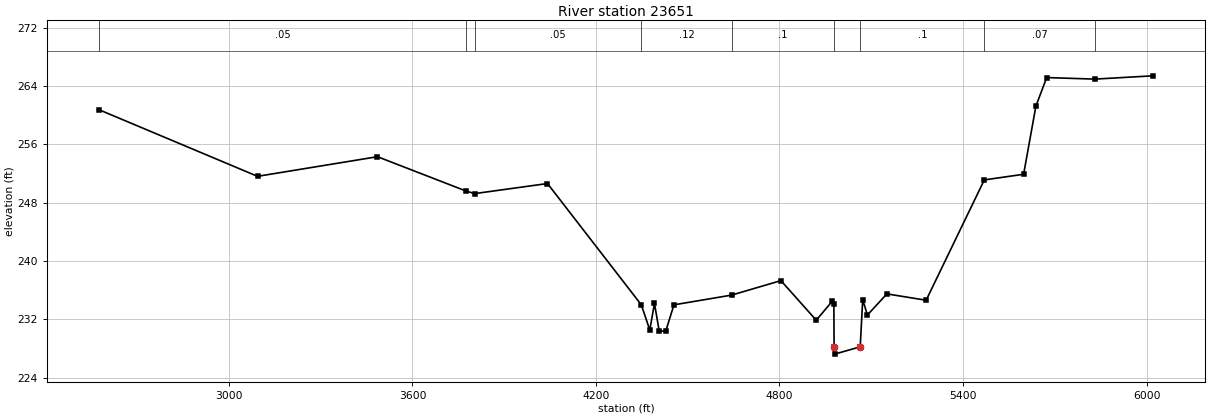
Type RM Length L Ch R = 1 ,23651   ,598,598,598
BEGIN DESCRIPTION:
X19099
END DESCRIPTION:
XS GIS Cut Line= 3
      2418682.95     13639375.57      2420070.53     13637167.52
      2420154.99     13636334.93
#Sta/Elev= 30
  2575.7  260.72  3093.3   251.6  3485.5  254.29  3774.7  249.59  3803.1  249.23
  4041.4  250.61  4348.2  233.98  4375.9  230.53  4391.2  234.17  4406.5  230.43
  4427.8  230.33  4454.9  233.98  4643.1  235.31  4804.7   237.3  4920.1  231.87
  4971.9  234.44  4977.8  234.03  4978.5  228.22    4980  227.22  5063.9  228.22
  5072.1  234.69  5087.4  232.58  5151.1  235.48  5279.5  234.61  5469.7  251.11
  5598.2  251.88  5638.4  261.23  5673.6  265.14  5831.2  264.93  6020.4  265.38
#Mann= 9 ,-1 , 0
  2575.7     .05       0  3774.7    .035       0  3803.1     .05       0
  4348.2     .12       0  4643.1      .1       0  4978.5     .05       0
  5063.9      .1       0  5469.7     .07       0  5831.2     .05       0
Bank Sta=4978.5,5063.9
XS Rating Curve= 0 ,0
Exp/Cntr=0.3,0.1