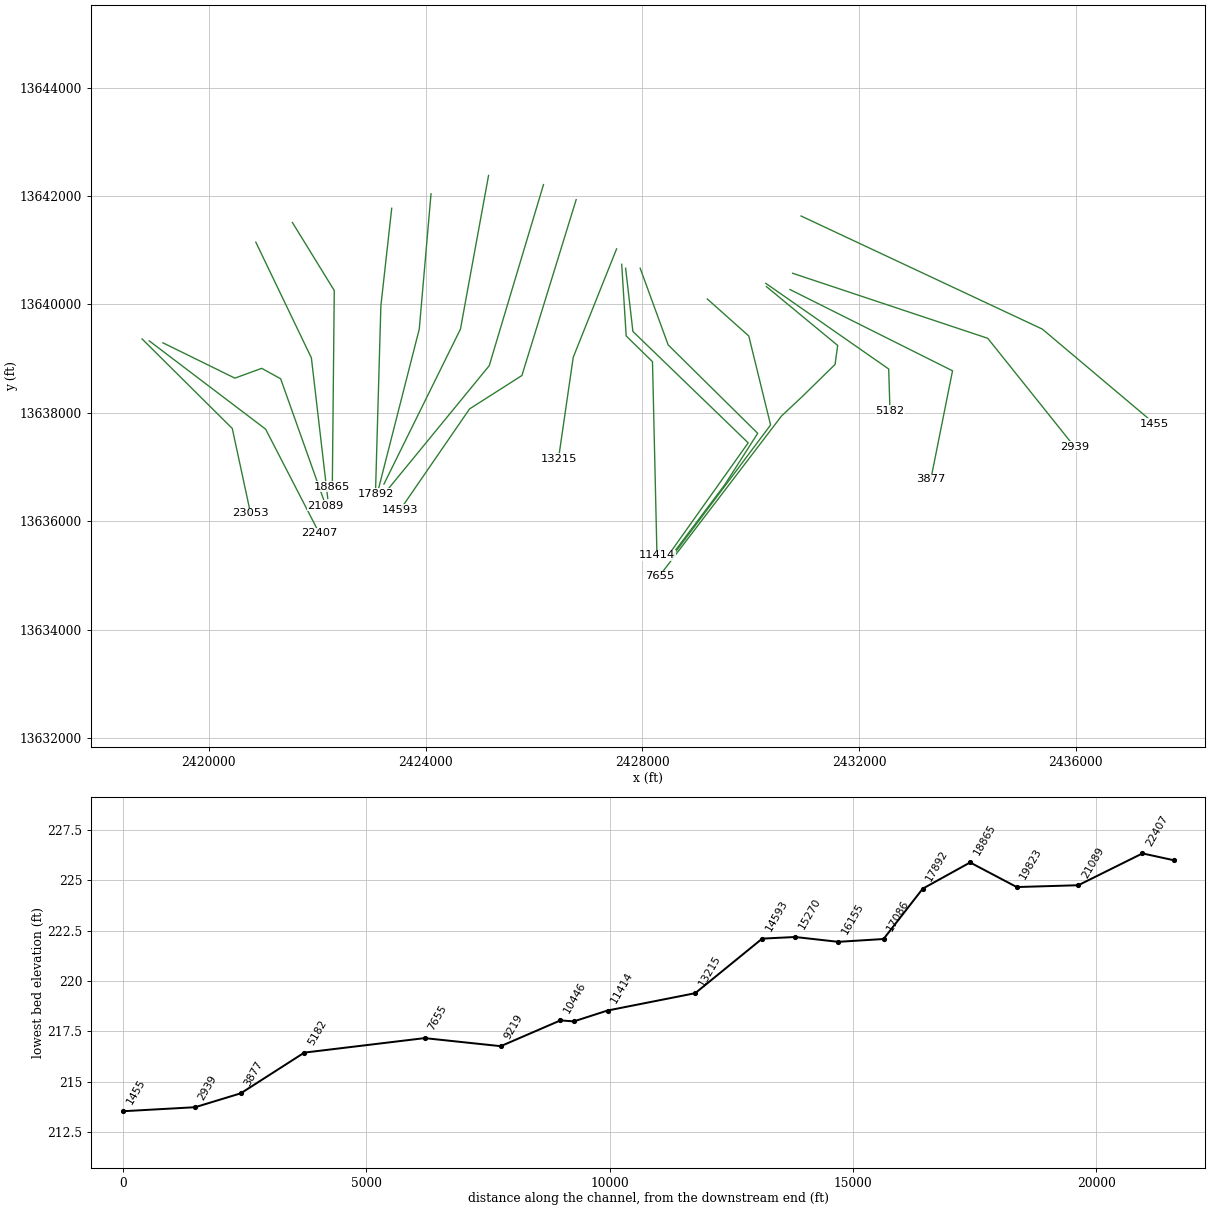
HEC-RAS study ELM CREEK.prj: ELM CREEK Base Level Engineering

--- ELM CREEK.g01 (geometry) --- (continued)

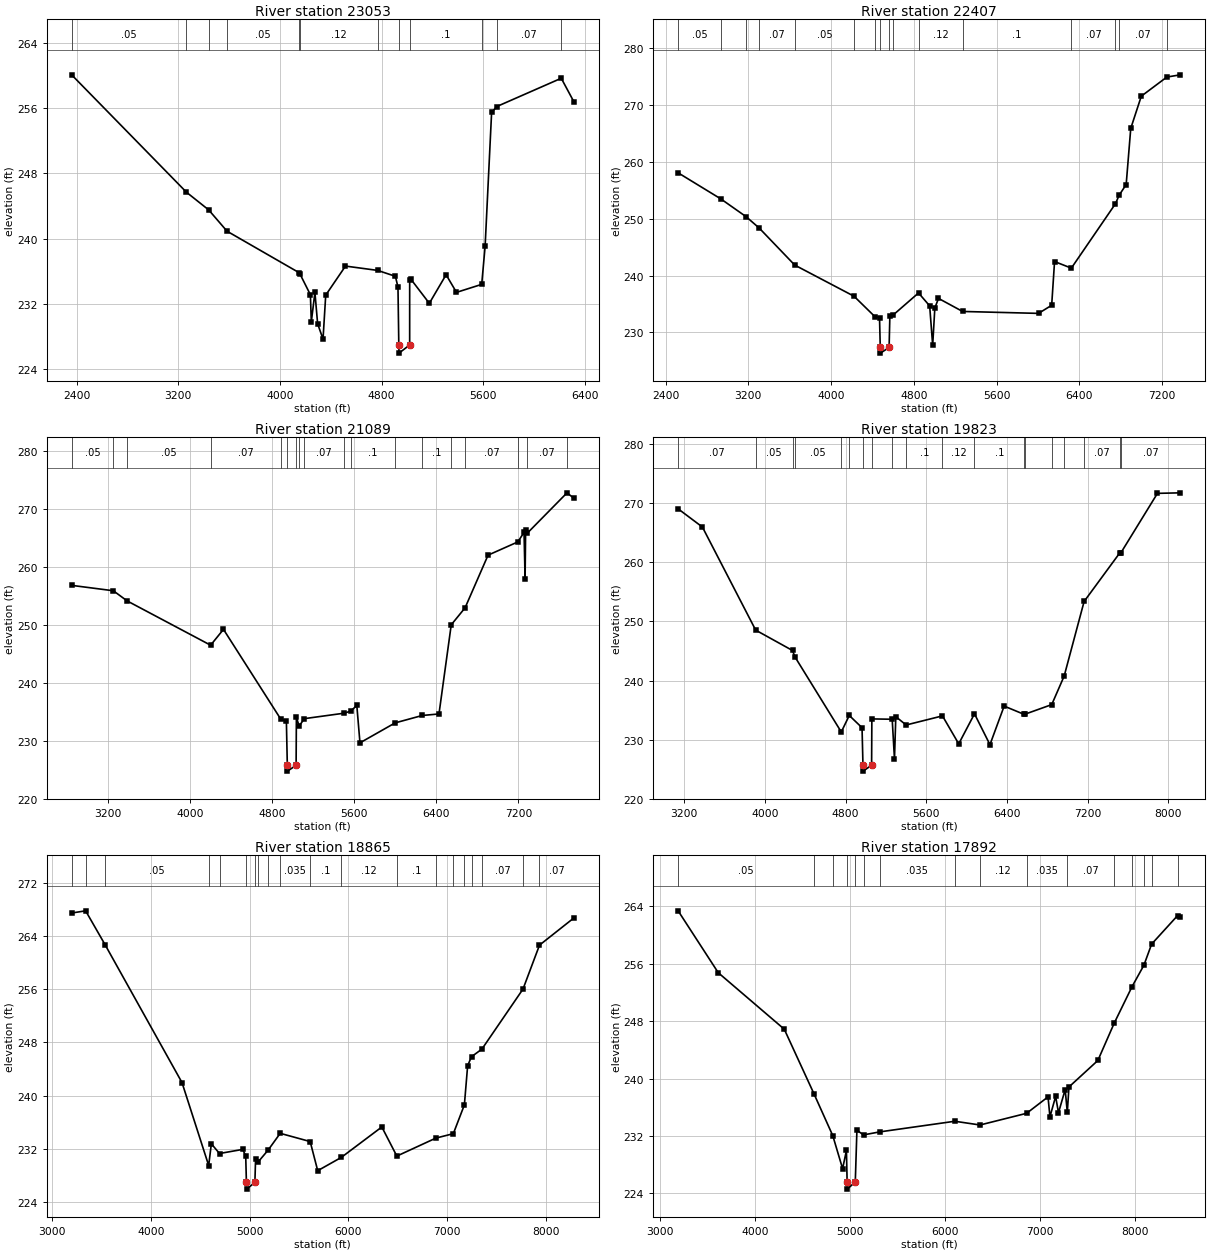
Type RM Length L Ch R = 1 ,23053   ,646,646,646
BEGIN DESCRIPTION:
ELM CREEK 13.0
END DESCRIPTION:
XS GIS Cut Line= 3
      2418767.41     13639363.52      2420432.51     13637710.49
      2420770.18     13636142.73
#Sta/Elev= 30
  2361.4  260.08  3264.7   245.7  3439.2  243.54  3583.7  240.93  4152.8  235.83
  4157.4  235.69  4239.2  233.15  4246.6  229.85  4274.9  233.43  4296.1   229.6
  4338.6  227.71  4359.8   233.1  4515.3  236.66  4768.2  236.13  4907.7  235.41
  4928.1  234.09  4934.7     227  4936.2     226  5020.1     227  5020.2  234.91
  5026.8  235.11  5174.7   232.1  5306.6   235.6  5388.4  233.44  5586.7  234.42
  5613.5  239.07  5664.6  255.47  5705.8   256.2  6212.4  259.66  6311.4  256.79
#Mann= 12 ,-1 , 0
  2361.4     .05       0  3264.7    .035       0  3439.2     .07       0
  3583.7     .05       0  4152.8     .07       0  4157.4     .12       0
  4768.2      .1       0  4934.7     .05       0  5020.1      .1       0
  5586.7     .12       0  5705.8     .07       0  6212.4     .05       0
Bank Sta=4934.7,5020.1
XS Rating Curve= 0 ,0
Exp/Cntr=0.3,0.1

Type RM Length L Ch R = 1 ,22407   ,1318,1318,1318
BEGIN DESCRIPTION:
X19098
END DESCRIPTION:
XS GIS Cut Line= 3
       2418900.1     13639327.36      2421047.88     13637698.42
      2422037.28     13635779.95
#Sta/Elev= 30
  2521.4   258.1  2934.7   253.5  3179.6  250.36  3305.8  248.36  3648.5  241.85
  4221.9  236.36  4423.8  232.76  4468.2  232.56  4475.4  227.34  4476.9  226.34
  4560.8  227.34    4568   232.8  4599.7  233.05  4845.3  236.94  4952.9  234.66
    4982  227.71  5002.8  234.28  5038.2  235.98  5271.2  233.68    6005  233.34
  6132.2  234.77  6160.1  242.47  6322.3  241.31  6748.9  252.66  6784.5  254.16
  6852.3  256.03  6896.6  265.92  6998.6   271.6  7245.7  274.97  7375.6  275.36
#Mann= 16 ,-1 , 0
  2521.4     .05       0  2934.7     .07       0  3179.6    .035       0
  3305.8     .07       0  3648.5     .05       0  4221.9     .07       0
  4423.8     .12       0  4475.4     .05       0  4560.8     .12       0
  4599.7      .1       0  4845.3     .12       0  5271.2      .1       0
  6322.3     .07       0  6748.9    .035       0  6784.5     .07       0
  7245.7    .035       0
Bank Sta=4475.4,4560.8
XS Rating Curve= 0 ,0
Exp/Cntr=0.3,0.1

Type RM Length L Ch R = 1 ,21089   ,1266,1266,1266
BEGIN DESCRIPTION:
X19097
END DESCRIPTION:
XS GIS Cut Line= 5
      2419153.47     13639291.17      2420480.77     13638639.58
      2420975.48     13638820.57       2421325.4     13638627.51
      2422157.39      13636288.3
#Sta/Elev= 30
    2851   256.8  3256.7  255.87  3390.9  254.12  4203.5  246.48  4328.7  249.21
  4887.2   233.7  4940.9  233.43  4950.1  225.76  4951.6  224.76  5035.6  225.76
  5038.4  234.05    5065  232.52  5115.5  233.81  5501.9  234.75    5568  235.11
  5626.4   236.1  5657.2  229.64  5999.4  233.08  6263.9  234.36  6426.2  234.62
  6545.5     250  6680.3  252.93  6903.8  262.01  7193.3  264.29  7254.1  265.94
  7264.3  257.98  7269.6  266.37  7285.8   265.8  7672.4  272.76  7738.8  271.83
#Mann= 18 ,-1 , 0
    2851     .05       0  3256.7    .035       0  3390.9     .05       0
  4203.5     .07       0  4887.2      .1       0  4950.1     .05       0
  5035.6      .1       0    5065    .035       0  5115.5     .07       0
  5501.9     .12       0    5568      .1       0  5999.4     .12       0
  6263.9      .1       0  6545.5     .12       0  6680.3     .07       0
  7193.3    .035       0  7285.8     .07       0  7672.4    .035       0
Bank Sta=4950.1,5035.6
XS Rating Curve= 0 ,0
Exp/Cntr=0.3,0.1

Type RM Length L Ch R = 1 ,19823   ,958,958,958
BEGIN DESCRIPTION:
X19096
END DESCRIPTION:
XS GIS Cut Line= 3
      2420866.88     13641149.33      2421892.51     13639013.63
      2422194.12     13636419.71
#Sta/Elev= 30
  3139.6  269.07  3380.4  265.99  3908.8  248.54  4274.1  245.09  4298.2  244.01
  4757.7   231.3  4837.1  234.09  4963.7  232.02  4972.9  225.67  4974.4  224.67
  5058.6  225.67  5061.1  233.51  5262.8  233.45  5285.4  226.72  5298.6  233.89
  5401.1  232.48  5761.3  234.02  5922.6  229.29  6078.9  234.37  6232.3  229.15
  6373.2  235.68  6570.9  234.28  6581.6  234.32    6845  235.93  6968.5  240.77
  7166.2  253.39  7519.9  261.61  7531.2  261.63  7893.4  271.69  8120.2  271.78
#Mann= 19 ,-1 , 0
  3139.6     .07       0  3908.8     .05       0  4274.1    .035       0
  4298.2     .05       0  4757.7     .07       0  4837.1      .1       0
  4972.9     .05       0  5058.6      .1       0  5262.8     .12       0
  5401.1      .1       0  5761.3     .12       0  6078.9      .1       0
  6570.9     .07       0  6581.6     .12       0    6845      .1       0
  6968.5     .12       0  7166.2     .07       0  7519.9    .035       0
  7531.2     .07       0
Bank Sta=4972.9,5058.6
XS Rating Curve= 0 ,0
Exp/Cntr=0.3,0.1

Type RM Length L Ch R = 1 ,18865   ,973,973,973
BEGIN DESCRIPTION:
X19095
END DESCRIPTION:
XS GIS Cut Line= 3
      2421542.61     13641511.28      2422314.82     13640256.43
      2422278.64     13636638.32
#Sta/Elev= 30
  3195.2  267.51  3336.9  267.84  3533.8  262.74  4314.1  241.95  4584.6  229.45
  4611.6  232.72  4694.3  231.26  4930.1  231.88  4960.1  230.86  4967.1  226.89
  4968.6  225.89    5053  226.89  5060.1  230.45  5088.5  230.03    5187  231.77
  5309.8   234.3  5613.6  233.06  5690.1  228.67  5929.2  230.67  6340.1  235.26
  6492.3  230.87  6887.7  233.58  7065.1  234.25  7177.1  238.59  7210.2   244.5
  7249.4  245.85    7355     247  7771.6  256.05  7938.7  262.67  8286.9  266.76
#Mann= 20 ,-1 , 0
  3195.2     .05       0  3336.9    .035       0  3533.8     .05       0
  4584.6     .12       0  4694.3      .1       0  4967.1     .05       0
    5053      .1       0  5088.5    .035       0    5187     .12       0
  5309.8    .035       0  5613.6      .1       0  5929.2     .12       0
  6492.3      .1       0  6887.7     .07       0  7065.1     .12       0
  7177.1     .07       0  7249.4     .12       0    7355     .07       0
  7771.6    .035       0  7938.7     .07       0
Bank Sta=4967.1,5053
XS Rating Curve= 0 ,0
Exp/Cntr=0.3,0.1

Type RM Length L Ch R = 1 ,17892   ,806,806,806
BEGIN DESCRIPTION:
ELM CREEK 12.0
END DESCRIPTION:
XS GIS Cut Line= 3
        2423375.     13641775.02        2423175.       13639975.
      2423074.98     13636503.84
#Sta/Elev= 30
  3188.5  263.38  3611.1  254.75  4305.4  246.88  4617.1   237.9  4815.9  232.04
  4919.1  227.44  4959.4  229.98  4966.7  225.59  4968.2  224.59  5052.6  225.59
  5069.6  232.79  5139.5  232.15  5310.6  232.57  6099.6  234.05    6365  233.53
  6855.6  235.16  7080.5  237.45  7100.5  234.67  7160.5  237.51  7190.5  235.24
  7260.9  238.47  7283.2  235.28  7300.6  238.83  7604.6  242.52    7777  247.73
  7965.1  252.83  8089.3   255.8  8170.3  258.74  8443.9  262.72  8472.2  262.58
#Mann= 16 ,-1 , 0
  3188.5     .05       0  4617.1    .035       0  4815.9      .1       0
  4966.7     .05       0  5052.6      .1       0  5139.5     .05       0
  5310.6    .035       0  6099.6     .05       0    6365     .12       0
  6855.6    .035       0  7283.2     .07       0    7777    .035       0
  7965.1     .07       0  8089.3    .035       0  8170.3     .07       0
  8443.9    .035       0
Bank Sta=4966.7,5052.6
XS Rating Curve= 0 ,0
Exp/Cntr=0.3,0.1

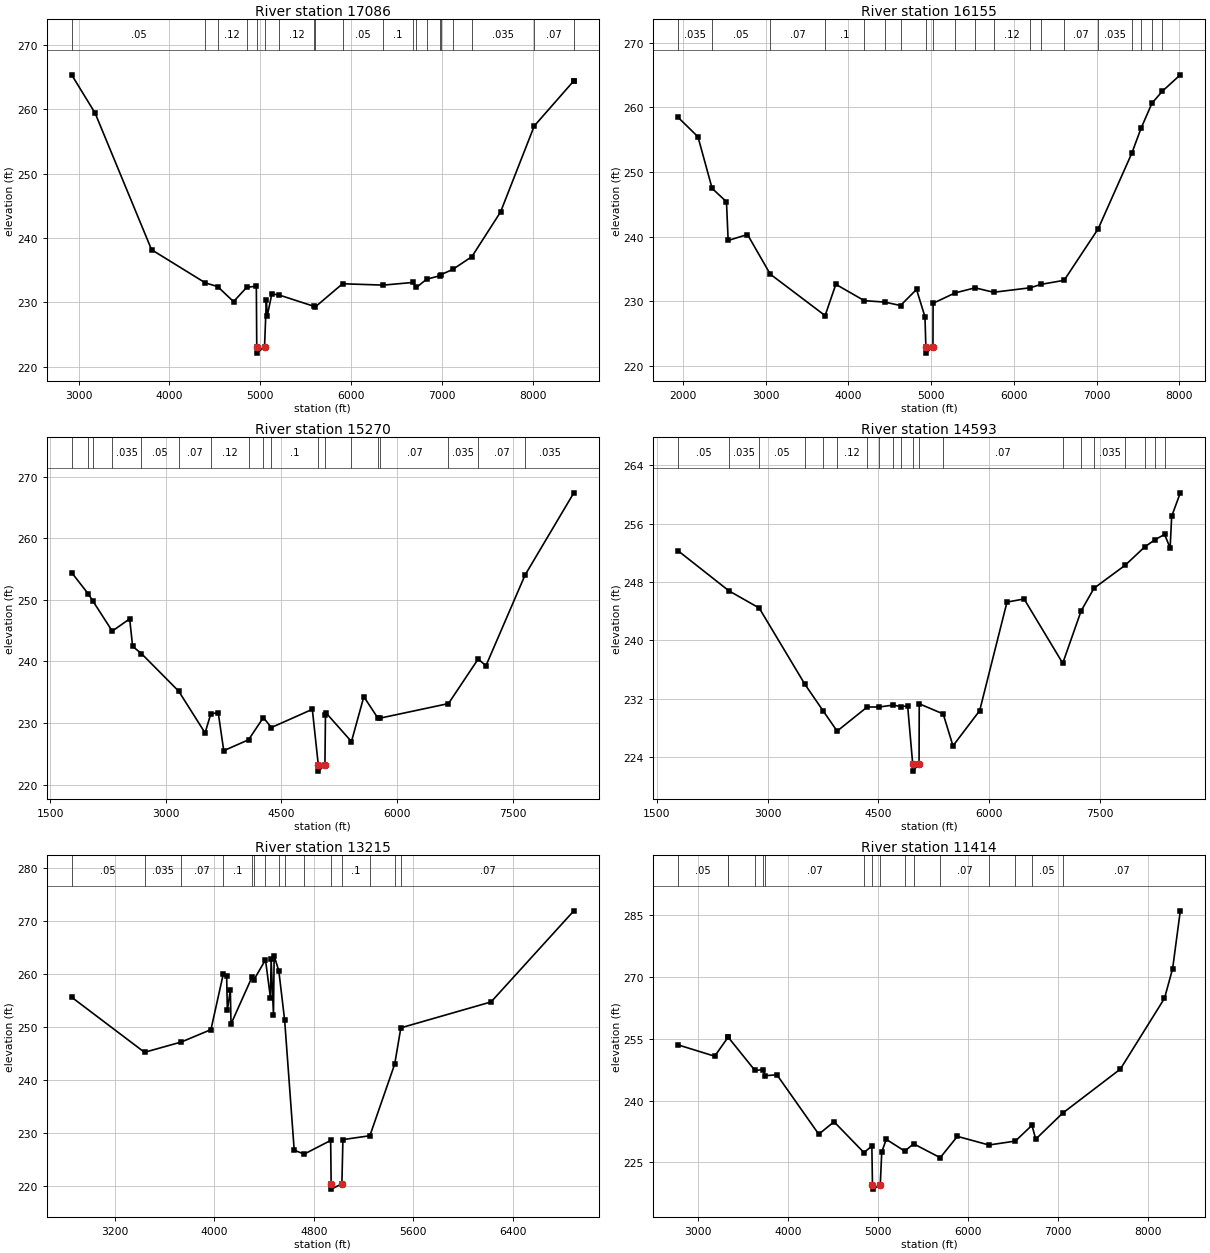
Type RM Length L Ch R = 1 ,17086   ,931,931,931
BEGIN DESCRIPTION:
ELM CREEK 11.0
END DESCRIPTION:
XS GIS Cut Line= 3
       2424100.6     13642042.21      2423883.41     13639544.53
      2423135.31     13636612.47
#Sta/Elev= 30
  2922.3  265.34  3180.5   259.4  3802.8  238.16  4396.1     233  4530.3  232.44
  4706.2  230.09  4849.3  232.29  4957.2  232.52  4961.7  223.09  4963.2  222.09
  5047.6  223.09  5067.6  230.39  5077.6  227.86  5127.8   231.3  5210.9  231.11
  5590.8  229.37  5606.6  229.27  5907.1  232.87  6356.6  232.66  6679.7  233.07
  6720.7   232.3  6833.3  233.57  6982.8  234.13  6992.3  234.29  7121.4   235.1
  7331.9  237.08  7647.8  244.02  8019.7   257.4  8452.8  264.37  8455.4  264.36
#Mann= 20 ,-1 , 0
  2922.3     .05       0  4396.1      .1       0  4530.3     .12       0
  4849.3      .1       0  4961.7     .05       0  5047.6      .1       0
  5210.9     .12       0  5590.8     .07       0  5606.6    .035       0
  5907.1     .05       0  6356.6      .1       0  6679.7     .12       0
  6720.7      .1       0  6833.3     .12       0  6982.8     .07       0
  6992.3     .12       0  7121.4     .07       0  7331.9    .035       0
  8019.7     .07       0  8452.8    .035       0
Bank Sta=4961.7,5047.6
XS Rating Curve= 0 ,0
Exp/Cntr=0.3,0.1

Type RM Length L Ch R = 1 ,16155   ,885,885,885
BEGIN DESCRIPTION:
ELM CREEK 10.0
END DESCRIPTION:
XS GIS Cut Line= 3
      2425162.42     13642380.09      2424643.57     13639544.53
      2423231.83     13636684.85
#Sta/Elev= 30
  1940.4  258.44  2180.3  255.44  2351.5  247.45    2525  245.38  2545.4  239.39
  2779.2  240.31  3054.1  234.18  3717.6  227.76  3847.3   232.6  4191.5  230.07
  4438.8  229.85  4629.2  229.32    4823  231.81    4925  227.57  4935.7  222.95
  4937.2  221.95  5021.6  222.95  5023.3  229.67  5289.5  231.27  5531.1  232.06
    5754  231.37  6199.8  232.07  6329.9   232.6  6607.6  233.22  7019.6   241.2
  7425.6  252.89  7537.1  256.74  7669.7  260.64  7795.5   262.5  8012.2  265.03
#Mann= 20 ,-1 , 0
  1940.4    .035       0  2351.5     .05       0  3054.1     .07       0
  3717.6      .1       0  4191.5     .07       0  4438.8     .12       0
  4629.2      .1       0  4935.7     .05       0  5021.6      .1       0
  5289.5     .12       0  5531.1     .05       0    5754     .12       0
  6199.8      .1       0  6329.9     .07       0  6607.6     .07       0
  7019.6    .035       0  7425.6     .07       0  7537.1    .035       0
  7669.7     .07       0  7795.5    .035       0
Bank Sta=4935.7,5021.6
XS Rating Curve= 0 ,0
Exp/Cntr=0.3,0.1

Type RM Length L Ch R = 1 ,15270   ,677,677,677
BEGIN DESCRIPTION:
X19094
END DESCRIPTION:
XS GIS Cut Line= 3
      2426175.95     13642211.11      2425174.48     13638868.83
      2423256.77     13636528.98
#Sta/Elev= 30
  1778.6  254.44  1996.8  250.93    2058  249.74  2305.1  244.93  2531.2  246.92
  2569.5  242.46  2683.8  241.28  3167.1  235.18  3509.6  228.39  3583.9  231.51
  3680.2  231.67  3751.6  225.51  4073.2  227.28  4265.6  230.89  4369.3  229.27
  4900.6  232.23  4978.1  223.19  4979.6  222.19  5064.1  223.19  5071.2  231.32
  5083.8  231.57  5408.2  226.99    5569  234.28  5753.8  230.75  5781.2   230.8
  6666.4  233.16  7051.7  240.39    7153  239.31    7660  254.03    8293  267.39
#Mann= 18 ,-1 , 0
  1778.6     .05       0  1996.8     .07       0    2058     .05       0
  2305.1    .035       0  2683.8     .05       0  3167.1     .07       0
  3583.9     .12       0  4073.2     .12       0  4265.6    .035       0
  4369.3      .1       0  4978.1     .05       0  5064.1      .1       0
  5408.2     .07       0  5753.8      .1       0  5781.2     .07       0
  6666.4    .035       0  7051.7     .07       0    7660    .035       0
Bank Sta=4978.1,5064.1
XS Rating Curve= 0 ,0
Exp/Cntr=0.3,0.1

Type RM Length L Ch R = 1 ,14593   ,1378,1378,1378
BEGIN DESCRIPTION:
X19093
END DESCRIPTION:
XS GIS Cut Line= 4
      2426779.27     13641933.63      2425777.78     13638687.84
       2424812.5     13638072.47      2423533.51     13636214.33
#Sta/Elev= 30
    1789  252.27  2477.1  246.79  2886.3  244.44  3504.3  234.01    3754  230.33
  3941.3  227.59  4348.3  230.89  4509.9  230.89  4699.6  231.15  4803.6  230.95
  4895.7  231.03  4964.1  223.11  4965.6  222.11  5050.2  223.11  5052.7  231.33
  5376.7  229.94  5509.3  225.57  5870.5  230.39  6240.4  245.25  6471.6  245.68
  6995.1  236.88    7244  244.05  7418.4  247.15  7840.6   250.3  8103.9   252.8
  8247.6  253.82  8374.2  254.51  8448.6  252.66  8469.6     257  8586.3  260.21
#Mann= 20 ,-1 , 0
    1789     .05       0  2477.1    .035       0  2886.3     .05       0
  3504.3     .07       0    3754     .12       0  3941.3     .12       0
  4348.3      .1       0  4509.9     .12       0  4699.6     .07       0
  4803.6     .12       0  4964.1     .05       0  5050.2      .1       0
  5376.7     .07       0  6995.1    .035       0    7244     .07       0
  7418.4    .035       0  7840.6     .07       0  8103.9    .035       0
  8247.6     .07       0  8374.2     .07       0
Bank Sta=4964.1,5050.2
XS Rating Curve= 0 ,0
Exp/Cntr=0.3,0.1

Type RM Length L Ch R = 1 ,13215   ,1801,1801,1801
BEGIN DESCRIPTION:
ELM CREEK 9.0
END DESCRIPTION:
XS GIS Cut Line= 3
      2427524.98     13641024.96        2426725.       13639025.
      2426453.48     13637155.43
#Sta/Elev= 30
  2850.6  255.63  3437.3  245.23    3734  247.18    3972  249.51  4070.9  259.96
  4098.6  259.65  4103.9  253.13  4128.2  257.01  4133.6  250.57    4304   259.5
  4318.1  258.93  4411.3  262.69  4451.3  255.49  4456.7  262.77  4475.5  252.28
  4480.9  263.44  4518.6   260.6  4565.3  251.33  4642.5  226.74  4723.3  226.02
    4936  228.59  4939.8   220.4  4941.3   219.4  5026.3   220.4  5034.6  228.75
  5251.7  229.48  5451.6  243.01    5501  249.85  6227.3  254.74  6893.8  271.94
#Mann= 15 ,-1 , 0
  2850.6     .05       0  3437.3    .035       0    3734     .07       0
  4070.9      .1       0    4304    .035       0  4318.1      .1       0
  4411.3    .035       0  4518.6     .07       0  4565.3     .12       0
  4723.3      .1       0  4939.8     .05       0  5026.3      .1       0
  5251.7     .07       0  5451.6     .12       0    5501     .07       0
Bank Sta=4939.8,5026.3
XS Rating Curve= 0 ,0
Exp/Cntr=0.3,0.1

Type RM Length L Ch R = 1 ,11414   ,693,693,693
BEGIN DESCRIPTION:
F21658a
END DESCRIPTION:
XS GIS Cut Line= 4
      2427619.66      13640740.4      2427702.29     13639418.23
      2428187.78     13638943.08      2428270.41     13635369.49
#Sta/Elev= 30
  2778.1  253.48  3184.3  250.74  3331.6   255.3  3333.4  255.37    3632  247.28
    3721  247.48  3745.1  246.01  3875.6  246.24  4340.4  231.84  4510.2  234.86
    4842   227.4  4930.3  228.96    4937  219.54  4938.5  218.54  5023.5  219.54
  5040.3  227.54  5090.3   230.6  5295.5  227.75    5394  229.52  5689.7  226.16
  5880.5  231.32  6230.7  229.23  6524.1  230.18  6708.6     234  6750.8  230.65
  7049.4  236.94    7691  247.62  8181.1  264.77  8271.2  271.94  8356.7  285.96
#Mann= 16 ,-1 , 0
  2778.1     .05       0  3331.6     .07       0  3333.4    .035       0
    3632    .063       0    3721    .035       0  3745.1     .07       0
    4842      .1       0    4937     .05       0  5023.5      .1       0
  5295.5     .07       0    5394     .12       0  5689.7     .07       0
  6230.7     .05       0  6524.1    .035       0  6708.6     .05       0
  7049.4     .07       0
Bank Sta=4937,5023.5
XS Rating Curve= 0 ,0
Exp/Cntr=0.3,0.1

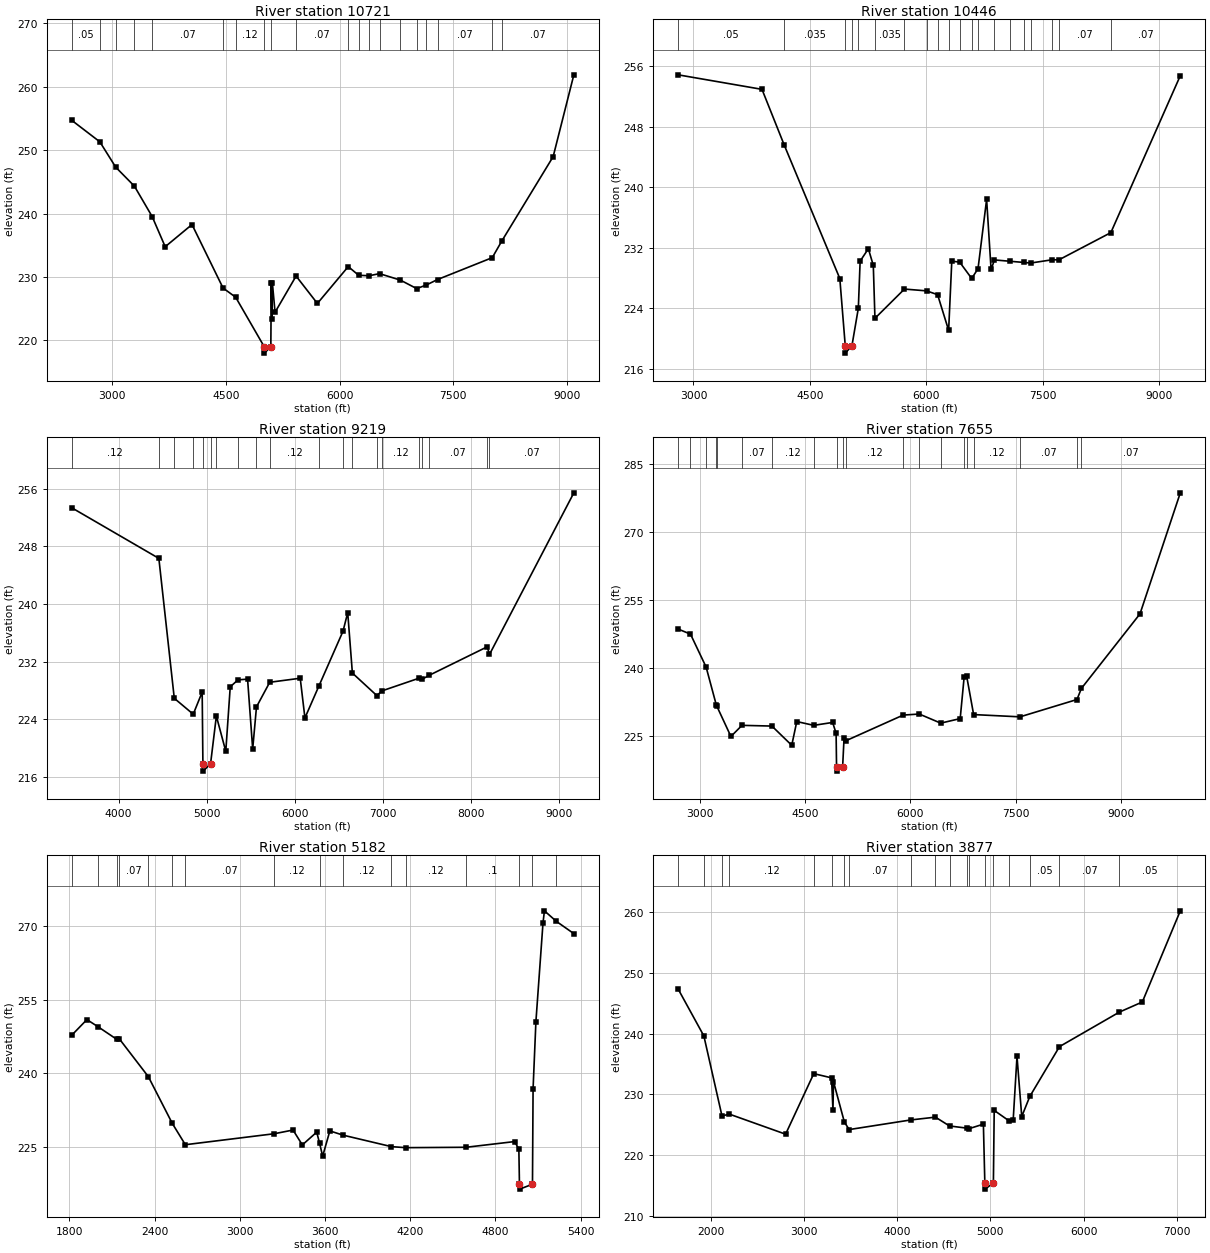
Type RM Length L Ch R = 1 ,10721   ,275,275,275
BEGIN DESCRIPTION:
F21656
END DESCRIPTION:
XS GIS Cut Line= 4
      2427691.97     13640668.08      2427826.25     13639500.87
      2429954.13      13637445.3        2428509.     13635411.79
#Sta/Elev= 30
  2463.5  254.71  2835.4  251.31  3045.4  247.31  3291.8  244.32  3526.5  239.52
  3698.2  234.77  4051.9  238.27  4461.9  228.26  4628.3  226.81  5005.7     219
  5007.2     218  5092.4     219  5098.4  229.08  5105.6  223.42  5112.6  229.09
  5148.1  224.44  5425.8  230.15  5706.8  225.83  6114.2  231.64  6251.9  230.27
  6389.6   230.2  6527.3  230.53  6802.2  229.51  7018.1  228.17  7146.5  228.75
  7292.4   229.6    8015  233.05  8138.3  235.62  8818.9  248.98  9091.7  261.87
#Mann= 20 ,-1 , 0
  2463.5     .05       0  2835.4     .07       0  3045.4    .035       0
  3291.8    .035       0  3526.5     .07       0  4461.9      .1       0
  4628.3     .12       0  5005.7     .05       0  5092.4     .12       0
  5425.8     .07       0  6114.2     .12       0  6251.9     .12       0
  6389.6     .12       0  6527.3     .12       0  6802.2     .12       0
  7018.1     .07       0  7146.5     .12       0  7292.4     .07       0
    8015    .035       0  8138.3     .07       0
Bank Sta=5005.7,5092.4
XS Rating Curve= 0 ,0
Exp/Cntr=0.3,0.1

Type RM Length L Ch R = 1 ,10446   ,1227,1227,1227
BEGIN DESCRIPTION:
F21655
END DESCRIPTION:
XS GIS Cut Line= 5
      2427960.54     13640668.08      2428477.01     13639252.96
      2430129.73      13637620.9      2429520.29     13636670.58
      2428611.32     13635462.07
#Sta/Elev= 30
  2802.5  254.84  3883.2  252.92  4168.7  245.58  4885.9  227.91  4955.7  219.05
  4957.2  218.05  5042.4  219.05  5124.4  223.98  5147.6  230.21  5253.6  231.85
  5317.3  229.65  5338.5  222.65  5718.6  226.52  6003.3  226.28  6145.6  225.78
  6287.9  221.06  6328.5  230.21  6430.2  230.08    6585  227.92  6666.5  229.21
  6777.3  238.37  6834.8  229.11  6878.6  230.37  7082.9  230.19  7254.6  230.04
  7344.9  229.96  7620.8  230.39  7708.3  230.38  8377.9  233.98  9272.8  254.73
#Mann= 20 ,-1 , 0
  2802.5     .05       0  4168.7    .035       0  4955.7    .035       0
  5042.4    .035       0  5124.4    .063       0  5338.5    .035       0
  5718.6    .035       0  6003.3    .035       0  6145.6    .035       0
  6287.9    .035       0  6430.2    .035       0    6585    .035       0
  6666.5    .063       0  6878.6     .12       0  7082.9     .07       0
  7254.6     .07       0  7344.9     .12       0  7620.8     .12       0
  7708.3     .07       0  8377.9     .07       0
Bank Sta=4955.7,5042.4
XS Rating Curve= 0 ,0
Exp/Cntr=0.3,0.1

Type RM Length L Ch R = 1 ,9219    ,1564,1564,1564
BEGIN DESCRIPTION:
F21657
END DESCRIPTION:
XS GIS Cut Line= 4
      2429200.06       13640100.      2429964.46     13639418.23
      2430367.31     13637775.84      2428580.39     13635389.83
#Sta/Elev= 30
  3468.2  253.38  4457.3  246.34  4632.4  226.89  4847.3  224.68  4948.8  227.76
    4957  217.77  4958.5  216.77  5043.7  217.77  5109.6  224.42  5216.5  219.52
  5267.1  228.49  5354.6  229.45  5463.7  229.56  5521.7  219.84  5564.8   225.7
    5715  229.12  6060.9  229.68  6114.2  224.16  6275.2  228.67  6546.3  236.22
  6599.6   238.8  6652.5   230.4  6930.7  227.26  6987.2  227.92  7407.2  229.68
  7440.1  229.52    7526   230.1  8182.1  234.05  8207.4  232.98  9164.5  255.45
#Mann= 20 ,-1 , 0
  3468.2     .12       0  4457.3    .035       0  4632.4     .12       0
  4847.3     .12       0    4957     .05       0  5043.7     .12       0
  5109.6      .1       0  5354.6     .12       0  5564.8      .1       0
    5715     .12       0  6275.2    .035       0  6546.3    .063       0
  6652.5     .12       0  6930.7     .07       0  6987.2     .12       0
  7407.2     .07       0  7440.1     .12       0    7526     .07       0
  8182.1    .035       0  8207.4     .07       0
Bank Sta=4957,5043.7
XS Rating Curve= 0 ,0
Exp/Cntr=0.3,0.1

Type RM Length L Ch R = 1 ,7655    ,2473,2473,2473
BEGIN DESCRIPTION:
X19092
END DESCRIPTION:
XS GIS Cut Line= 6
      2430290.48     13640328.85       2431605.7     13639242.88
      2431557.43     13638892.97      2430954.13     13638301.73
      2430568.01     13637939.75      2428311.67     13634983.57
#Sta/Elev= 30
  2693.9  248.58  2870.2  247.45  3092.7  240.17  3237.7  231.79  3242.2  231.63
  3445.7  224.83  3603.7  227.29  4029.8  227.13  4312.1  222.88  4383.7  228.13
  4625.1  227.29  4894.5  227.93  4943.9  225.52  4950.1  218.17  4951.6  217.17
  5036.9  218.17  5057.1   224.5  5089.8  223.93    5899  229.56  6128.6  229.79
  6433.5  227.78  6710.9  228.78  6767.5  238.01  6802.5  238.22  6902.4  229.67
  7562.7  229.17  8374.1     233  8436.9  235.45  9271.4  251.93  9845.6  278.69
#Mann= 20 ,-1 , 0
  2693.9     .12       0  2870.2     .07       0  3092.7     .12       0
  3237.7     .05       0  3242.2     .12       0  3603.7     .07       0
  4029.8     .12       0  4625.1      .1       0  4950.1     .05       0
  5036.9      .1       0  5089.8     .12       0    5899      .1       0
  6128.6     .12       0  6433.5    .035       0  6767.5    .063       0
  6802.5    .035       0  6902.4     .12       0  7562.7     .07       0
  8374.1    .035       0  8436.9     .07       0
Bank Sta=4950.1,5036.9
XS Rating Curve= 0 ,0
Exp/Cntr=0.3,0.1

Type RM Length L Ch R = 1 ,5182    ,1305,1305,1305
BEGIN DESCRIPTION:
X19091
END DESCRIPTION:
XS GIS Cut Line= 3
      2430278.43     13640389.16      2432546.85      13638808.5
      2432570.93     13638038.09
#Sta/Elev= 30
  1816.3  247.76  1923.8  250.96  2004.3  249.46  2132.4  246.97    2153     247
  2356.1  239.35  2525.1  229.81  2616.8  225.49  3243.8  227.73  3374.9  228.48
  3440.4  225.45  3541.6  228.05  3562.1  225.76  3583.5  223.15  3634.1   228.3
  3728.2  227.43  4067.6   225.1  4167.4  224.89  4593.3  224.97  4934.8  226.13
  4964.8   224.6    4969  217.45  4970.5  216.45  5060.7  217.45  5064.9  236.85
  5084.9  250.57  5134.9  270.68  5144.9   273.1  5228.6  270.96  5351.9  268.46
#Mann= 16 ,-1 , 0
  1816.3     .12       0  2004.3     .07       0  2132.4     .12       0
    2153     .07       0  2356.1     .05       0  2525.1     .12       0
  2616.8     .07       0  3243.8     .12       0  3562.1    .035       0
  3728.2     .12       0  4067.6      .1       0  4167.4     .12       0
  4593.3      .1       0    4969     .05       0  5060.7      .1       0
  5228.6     .07       0
Bank Sta=4969,5060.7
XS Rating Curve= 0 ,0
Exp/Cntr=0.3,0.1

Type RM Length L Ch R = 1 ,3877    ,938,938,938
BEGIN DESCRIPTION:
ELM CREEK 3.0
END DESCRIPTION:
XS GIS Cut Line= 3
      2430724.98     13640275.01        2433725.       13638775.
      2433325.01     13636775.04
#Sta/Elev= 30
  1645.8  247.32  1922.3  239.61    2117  226.45  2195.7  226.76  2800.2  223.46
  3102.7  233.41  3293.3  232.72  3308.9  227.41  3314.5   232.1  3431.7  225.44
  3483.3  224.22  4144.2   225.8  4409.4  226.26  4560.8  224.81  4744.2  224.46
  4769.1  224.36  4924.5  225.11  4940.1  215.43  4941.6  214.43  5031.9  215.43
  5040.7  227.37  5197.6  225.68  5244.7  225.83  5285.5  236.24  5336.5  226.36
    5423  229.66  5741.6  237.85  6384.5  243.52  6631.6  245.19  7039.5  260.17
#Mann= 19 ,-1 , 0
  1645.8     .07       0  1922.3     .05       0    2117     .07       0
  2195.7     .12       0  3102.7    .035       0  3293.3      .1       0
  3431.7     .12       0  3483.3     .07       0  4144.2     .12       0
  4409.4     .07       0  4560.8     .12       0  4744.2     .07       0
  4769.1      .1       0  4940.1     .05       0  5031.9      .1       0
  5197.6     .07       0    5423     .05       0  5741.6     .07       0
  6384.5     .05       0
Bank Sta=4940.1,5031.9
XS Rating Curve= 0 ,0
Exp/Cntr=0.3,0.1

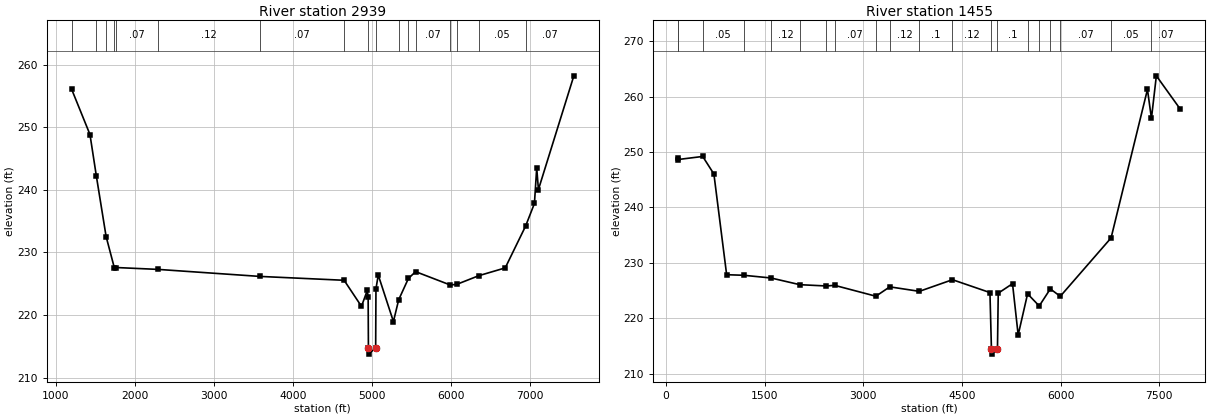
Type RM Length L Ch R = 1 ,2939    ,1484,1484,1484
BEGIN DESCRIPTION:
ELM CREEK 2.0
END DESCRIPTION:
XS GIS Cut Line= 3
      2430775.01       13640575.        2434375.       13639375.
      2435975.02     13637374.98
#Sta/Elev= 30
  1200.5   256.1  1432.4  248.86    1514  242.16  1636.6  232.55  1741.4  227.52
  1764.8  227.59    2296  227.29  3580.4  226.17  4649.1  225.55  4868.7  221.38
  4942.5  223.94  4953.1  222.81  4956.5  214.74    4958  213.74  5048.3  214.74
    5052  224.18  5080.9  226.39    5273  218.95  5339.7  222.44    5463  225.85
  5553.9  226.93  5992.1   224.8  6075.1   224.9  6354.7  226.29    6688  227.53
  6945.3   234.2  7057.8  237.84  7086.6  243.53  7108.2  240.06  7556.5  258.25
#Mann= 17 ,-1 , 0
  1200.5     .07       0    1514     .05       0  1636.6     .07       0
  1741.4     .12       0  1764.8     .07       0    2296     .12       0
  3580.4     .07       0  4649.1      .1       0  4956.5     .05       0
  5048.3      .1       0  5339.7     .07       0    5463     .12       0
  5553.9     .07       0  5992.1     .12       0  6075.1     .07       0
  6354.7     .05       0  6945.3     .07       0
Bank Sta=4956.5,5048.3
XS Rating Curve= 0 ,0
Exp/Cntr=0.3,0.1

Type RM Length L Ch R = 1 ,1455    ,0,0,0
BEGIN DESCRIPTION:
ELM CREEK 1.0
END DESCRIPTION:
XS GIS Cut Line= 3
      2430929.97     13641631.98      2435382.38     13639544.53
      2437457.75     13637794.95
#Sta/Elev= 30
   186.3  248.93     187  248.66   560.1  249.21   730.1  246.04   923.8  227.87
  1182.5  227.77    1598  227.28  2036.3  226.07  2436.3  225.84  2565.2  225.95
  3191.6  223.99  3402.7  225.68  3852.5  224.87  4355.7  226.97  4925.2  224.65
  4947.7  214.54  4949.2  213.54  5039.7  214.54  5051.4  224.54  5268.3  226.25
  5354.1     217  5497.3  224.42    5674  222.23  5842.8  225.31  5993.8  223.97
  6766.1  234.51    7319   261.3  7379.5  256.08  7454.2  263.76  7818.2  257.74
#Mann= 20 ,-1 , 0
   186.3     .07       0     187    .035       0   560.1     .05       0
  1182.5     .07       0    1598     .12       0  2036.3     .07       0
  2436.3     .12       0  2565.2     .07       0  3191.6      .1       0
  3402.7     .12       0  3852.5      .1       0  4355.7     .12       0
  4947.7     .05       0  5039.7      .1       0  5497.3     .12       0
    5674      .1       0  5842.8     .12       0  5993.8     .07       0
  6766.1     .05       0  7379.5     .07       0
Bank Sta=4947.7,5039.7
XS Rating Curve= 0 ,0
Exp/Cntr=0.3,0.1

Chan Stop Cuts=-1
Use User Specified Reach Order=0
Composite Channel Slope=5