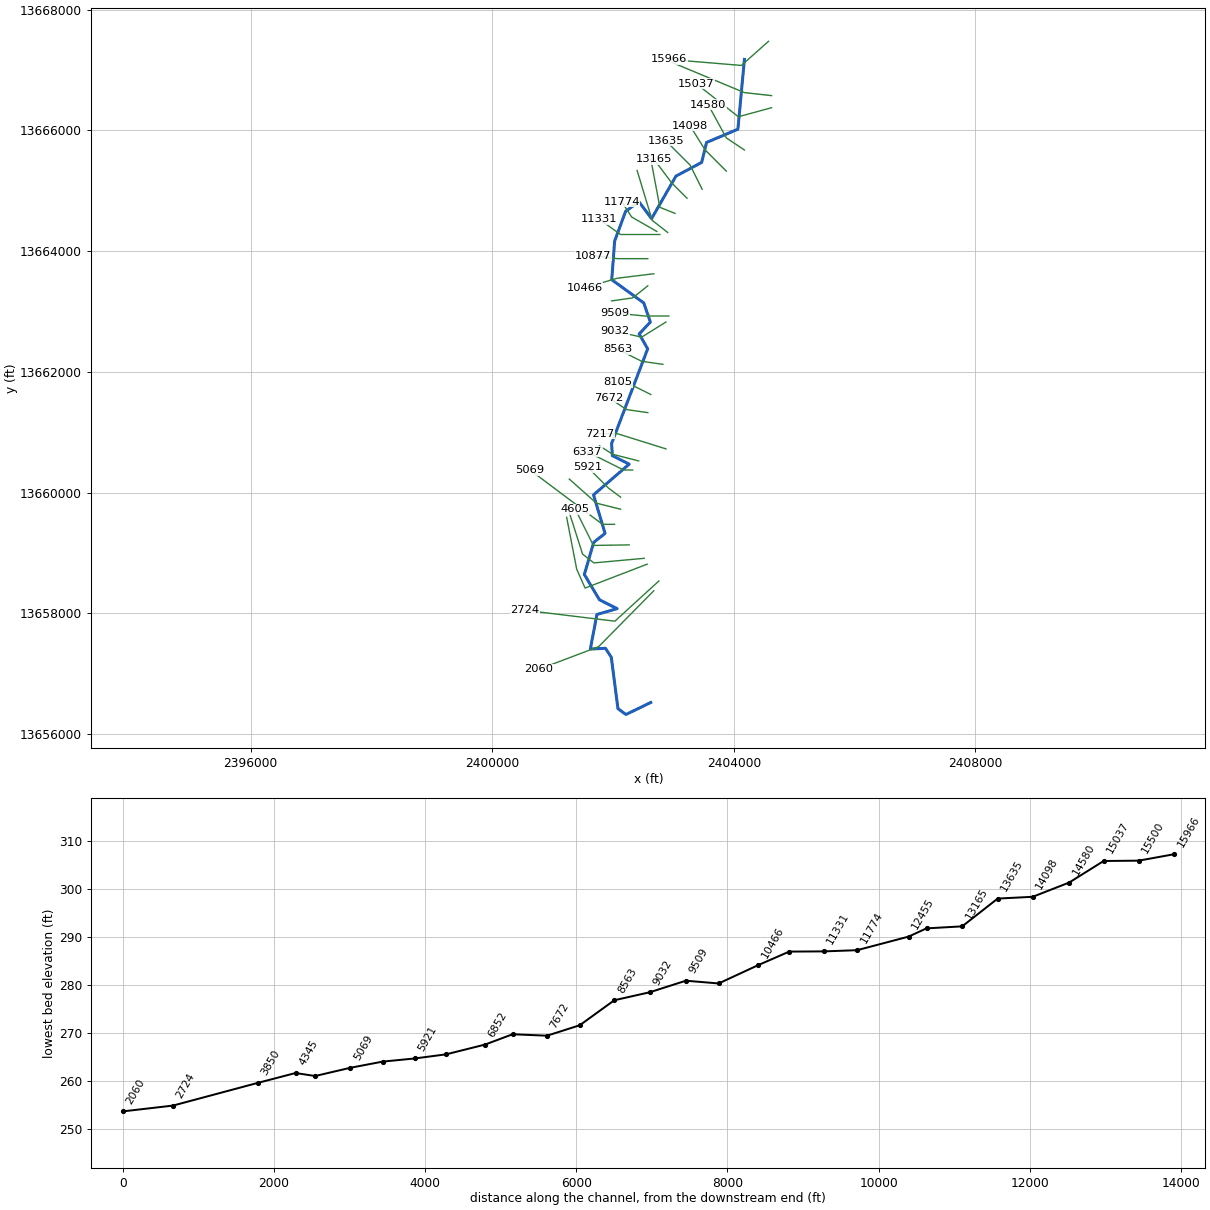
--- EVANS HOLLOW.prj (project) ---

Proj Title=EVANS HOLLOW Base Level Engineering
Current Plan=p01
Default Exp/Contr=0.3,0.1
English Units
Geom File=g01
Flow File=f01
Plan File=p01
Y Axis Title=Elevation
X Axis Title(PF)=Main Channel Distance
X Axis Title(XS)=Station
BEGIN DESCRIPTION:
EVANS HOLLOW
END DESCRIPTION:
DSS Export Rating Curves= 0
DSS Export Rating Curve Sorted= 0
DSS Export Volume Flow Curves= 0
DXF OffsetX= 0
DXF OffsetY= 0
DXF ScaleX= 1
DXF ScaleY= 10

--- EVANS HOLLOW.p01 (plan) ---

Plan Title=Multiple Run
Short Identifier=Multiple
Geom File=g01
Flow File=f01
Subcritical Flow
K Sum by GR= 0
Std Step Tol= 0.01
Critical Tol= 0.01
Num of Std Step Trials= 20
Max Error Tol= 0.3
Flow Tol Ratio= 0.001
Split Flow NTrial= 30
Split Flow Tol= 0.02
Split Flow Ratio= 0.02
Log Output Level= 0
Friction Slope Method= 1
Unsteady Friction Slope Method= 2
Unsteady Bridges Friction Slope Method= 1
Parabolic Critical Depth
Global Vel Dist=  1 , 1 , 1
Global Log Level= 0
CheckData=True
Encroach Param= -1, 0, 0, 0
BEGIN DESCRIPTION:
Multiple Run
END DESCRIPTION:

--- EVANS HOLLOW.f01 (steady flow) ---

Flow Title=Multiple
Number of Profiles=7
Profile Names=10-year,25-year,50-year,1pct_min,100-year,1pct_plu,500-year
River Rch & RM= EVANS HOLLOW,Reach-1,15966
     636    1025    1374     892    1779    3550    2958
River Rch & RM= EVANS HOLLOW,Reach-1,14098
     908    1487    2017    1321    2636    5260    4468
River Rch & RM= EVANS HOLLOW,Reach-1,6337
     934    1529    2073    1358    2710    5407    4590
River Rch & RM= EVANS HOLLOW,Reach-1,2724
    2189    3726    5184    3476    6935   13838   12316
Boundary for River Rch & Prof#=EVANS HOLLOW,Reach-1,1
Up Type=0
Dn Type=3
Dn Slope=0.005
Boundary for River Rch & Prof#=EVANS HOLLOW,Reach-1,2
Up Type=0
Dn Type=3
Dn Slope=0.005
Boundary for River Rch & Prof#=EVANS HOLLOW,Reach-1,3
Up Type=0
Dn Type=3
Dn Slope=0.005
Boundary for River Rch & Prof#=EVANS HOLLOW,Reach-1,4
Up Type=0
Dn Type=3
Dn Slope=0.005
Boundary for River Rch & Prof#=EVANS HOLLOW,Reach-1,5
Up Type=0
Dn Type=3
Dn Slope=0.005
Boundary for River Rch & Prof#=EVANS HOLLOW,Reach-1,6
Up Type=0
Dn Type=3
Dn Slope=0.005
Boundary for River Rch & Prof#=EVANS HOLLOW,Reach-1,7
Up Type=0
Dn Type=3
Dn Slope=0.005

--- EVANS HOLLOW.g01 (geometry) ---

Geom Title=Existing Conditions
Program Version=4.10

River Reach=EVANS HOLLOW    ,Reach-1
Reach XY= 30
        2404175.       13667175.       2404067.2     13666018.79
      2403547.65     13665799.03      2403467.15     13665468.81
      2403041.46     13665242.13      2402638.38     13664538.51
      2402428.44     13664817.61      2402207.78     13664658.73
      2402026.06     13664164.56      2401978.43     13663526.22
      2402508.59      13663141.8      2402617.92     13662824.99
       2402432.6     13662628.34      2402573.18     13662381.12
      2401976.05     13660814.56      2401988.36     13660611.65
      2402267.51     13660471.86       2401676.5     13659963.15
      2401867.77     13659324.68      2401680.45     13659177.47
      2401524.89     13658645.09        2401775.       13658225.
      2402067.42     13658078.32      2401732.64     13657981.55
      2401624.04     13657409.43      2401873.58     13657421.96
      2401971.25     13657273.45      2402080.82     13656422.69
      2402214.29     13656325.72        2402625.       13656525.

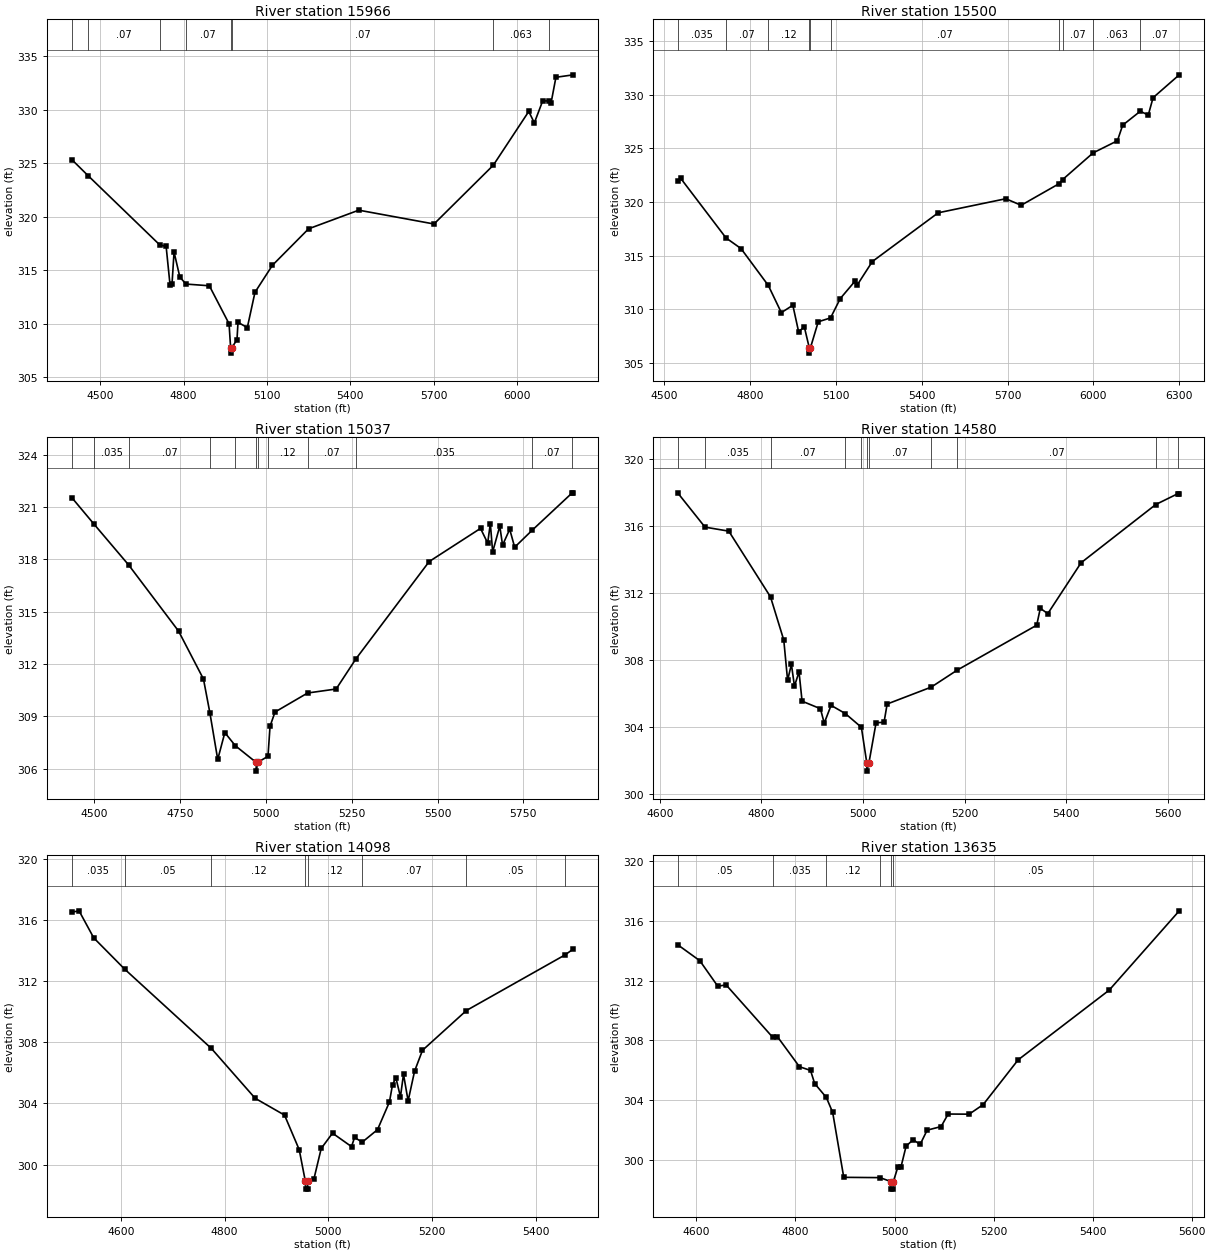
Type RM Length L Ch R = 1 ,15966   ,466,466,466
BEGIN DESCRIPTION:
EVANS HOLLOW 30.0
END DESCRIPTION:
XS GIS Cut Line= 3
        2404575.       13667475.        2404125.       13667075.
      2402925.04       13667175.
#Sta/Elev= 30
  4397.1  325.33  4455.7  323.83  4713.5  317.37    4737  317.21  4751.2  313.58
  4758.3  313.75  4765.5  316.69  4786.4  314.35  4808.5   313.7  4892.6  313.54
  4963.6  309.99  4969.2  307.75  4969.4  307.25  4973.2  307.75  4992.1   308.5
  4995.8  310.13  5029.3  309.63  5056.9  312.93  5119.6  315.45    5250  318.86
  5430.7   320.6  5701.6  319.31  5915.2   324.8  6042.8  329.82  6062.9  328.75
    6093  330.81  6116.4   330.8  6123.1  330.61  6140.6  333.01  6203.3  333.24
#Mann= 8 ,-1 , 0
  4397.1    .035       0  4455.7     .07       0  4713.5    .033       0
  4808.5     .07       0  4969.2     .05       0  4973.2     .07       0
  5915.2    .063       0  6116.4     .07       0
Bank Sta=4969.2,4973.2
XS Rating Curve= 0 ,0
Exp/Cntr=0.3,0.1

Type RM Length L Ch R = 1 ,15500   ,463,463,463
BEGIN DESCRIPTION:
EVANS HOLLOW 29.0
END DESCRIPTION:
XS GIS Cut Line= 3
      2404624.96       13666575.        2404175.       13666625.
      2402975.02     13667124.99
#Sta/Elev= 30
  4547.3  321.95  4557.3  322.22  4716.2  316.65  4768.6  315.66  4864.1  312.22
  4909.5  309.69  4949.7  310.38  4969.8  307.93    4990  308.35  5007.1  306.42
  5007.4  305.92  5011.3  306.42  5038.5  308.84  5081.5   309.2  5115.4     311
  5168.5  312.67  5173.9  312.23  5227.5  314.45  5457.7  318.99  5693.9   320.3
  5747.5  319.69  5878.7  321.68  5892.3  322.08    5999  324.57  6083.9   325.7
  6102.3  327.15  6163.9  328.45  6191.7  328.09  6208.5  329.71    6300  331.84
#Mann= 10 ,-1 , 0
  4547.3    .035       0  4716.2     .07       0  4864.1     .12       0
  5007.1     .05       0  5011.3     .12       0  5081.5     .07       0
  5878.7    .063       0  5892.3     .07       0    5999    .063       0
  6163.9     .07       0
Bank Sta=5007.1,5011.3
XS Rating Curve= 0 ,0
Exp/Cntr=0.3,0.1

Type RM Length L Ch R = 1 ,15037   ,457,457,457
BEGIN DESCRIPTION:
EVANS HOLLOW 28.0
END DESCRIPTION:
XS GIS Cut Line= 3
      2404625.03     13666375.01        2404075.       13666225.
      2403375.03     13666774.98
#Sta/Elev= 30
    4435  321.54    4500  320.01  4601.2  317.66    4746  313.88  4818.5  311.13
  4837.2  309.19    4860  306.52  4880.7  308.06  4911.1  307.31  4971.9  306.35
  4972.2  305.85  4976.1  306.35  5006.3   306.7  5012.3  308.42  5026.8  309.24
  5121.7  310.33  5204.8  310.56  5262.4  312.29  5475.7  317.87  5625.1  319.77
  5645.9  318.93  5653.7  320.05  5660.4  318.42  5681.2   319.9  5689.3  318.81
  5710.1  319.72  5724.5  318.69  5774.7  319.65  5890.5  321.78  5895.3  321.81
#Mann= 12 ,-1 , 0
    4435     .05       0    4500    .035       0  4601.2     .07       0
  4837.2     .12       0  4911.1     .07       0  4971.9     .05       0
  4976.1     .07       0  5006.3     .12       0  5121.7     .07       0
  5262.4    .035       0  5774.7     .07       0  5890.5    .063       0
Bank Sta=4971.9,4976.1
XS Rating Curve= 0 ,0
Exp/Cntr=0.3,0.1

Type RM Length L Ch R = 1 ,14580   ,482,482,482
BEGIN DESCRIPTION:
EVANS HOLLOW 27.0
END DESCRIPTION:
XS GIS Cut Line= 3
      2404174.96     13665675.03        2403875.       13665875.
        2403575.     13666424.99
#Sta/Elev= 30
  4635.3  317.99  4689.1  315.94  4735.9   315.7    4818  311.77  4844.1  309.19
  4851.6  306.79  4859.1  307.74  4865.1  306.44  4874.1  307.29  4880.1  305.54
  4916.2  305.09  4923.7  304.23  4937.2  305.29  4965.2   304.8  4996.8  303.98
  5007.4  301.86  5007.7  301.36  5011.7  301.86  5025.7  304.25  5041.4  304.28
  5047.5  305.37  5134.2  306.38  5185.6   307.4  5341.8  310.08  5348.9  311.09
  5363.6  310.77  5429.1  313.81    5576  317.29  5619.6  317.94  5622.3  317.94
#Mann= 11 ,-1 , 0
  4635.3     .05       0  4689.1    .035       0    4818     .07       0
  4965.2     .12       0  4996.8     .07       0  5007.4     .05       0
  5011.7     .07       0  5134.2     .12       0  5185.6     .07       0
    5576    .035       0  5619.6     .07       0
Bank Sta=5007.4,5011.7
XS Rating Curve= 0 ,0
Exp/Cntr=0.3,0.1

Type RM Length L Ch R = 1 ,14098   ,463,463,463
BEGIN DESCRIPTION:
EVANS HOLLOW 26.0
END DESCRIPTION:
XS GIS Cut Line= 3
      2403874.99     13665325.01        2403525.       13665675.
      2403274.98     13666075.03
#Sta/Elev= 30
  4505.5  316.51  4519.6   316.6  4547.9  314.83  4607.7  312.78  4774.6   307.6
    4859  304.34  4915.6  303.24  4943.9  300.98  4955.8   298.9  4956.1   298.4
  4959.9   298.4  4960.2   298.9  4972.2  299.06  4986.3  301.06  5008.1  302.06
  5044.7  301.18  5050.6  301.78  5065.3  301.47  5094.8  302.29  5117.8   304.1
  5123.7  305.23  5130.2  305.68    5139  304.44  5144.9  305.91  5153.8  304.17
  5166.2  306.11  5181.5  307.48  5266.1  310.08  5455.3   313.7  5472.2   314.1
#Mann= 8 ,-1 , 0
  4505.5    .035       0  4607.7     .05       0  4774.6     .12       0
  4955.8     .05       0  4960.2     .12       0  5065.3     .07       0
  5266.1     .05       0  5455.3     .07       0
Bank Sta=4955.8,4960.2
XS Rating Curve= 0 ,0
Exp/Cntr=0.3,0.1

Type RM Length L Ch R = 1 ,13635   ,470,470,470
BEGIN DESCRIPTION:
EVANS HOLLOW 25.0
END DESCRIPTION:
XS GIS Cut Line= 3
      2403474.99     13665025.02        2403275.       13665425.
      2402874.98     13665825.02
#Sta/Elev= 30
  4562.1   314.4  4606.8  313.33  4643.1  311.62  4659.9  311.71  4753.7  308.21
  4763.3  308.25    4808  306.23  4830.4  305.98  4838.8   305.1  4862.3  304.17
  4875.1  303.17  4897.5  298.82  4970.8   298.8  4993.1  298.53  4993.4  298.03
  4997.3  298.03  4997.6  298.53  5006.5  299.48  5012.8  299.48  5023.4  300.91
  5037.6  301.34  5051.7  301.02  5065.9  301.98  5094.1  302.22  5108.3  303.06
  5150.7  303.05    5179  303.69  5249.7  306.69  5433.6  311.36    5575  316.67
#Mann= 6 ,-1 , 0
  4562.1     .05       0  4753.7    .035       0  4862.3     .12       0
  4970.8     .05       0  4993.1     .05       0  4997.6     .05       0
Bank Sta=4993.1,4997.6
XS Rating Curve= 0 ,0
Exp/Cntr=0.3,0.1

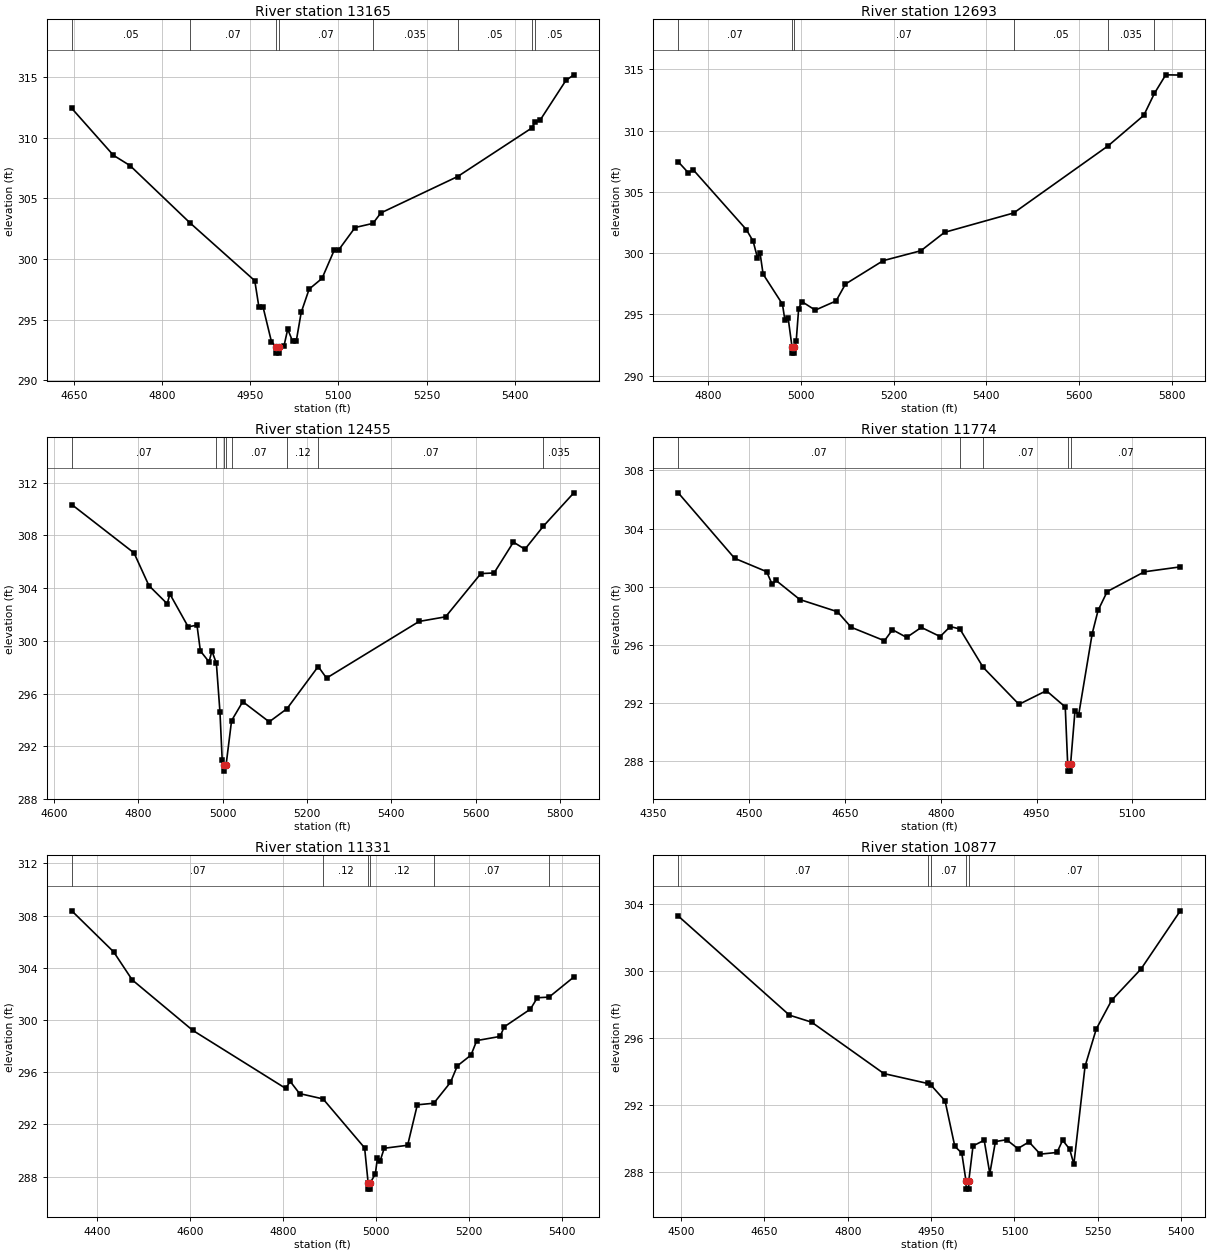
Type RM Length L Ch R = 1 ,13165   ,472,472,472
BEGIN DESCRIPTION:
EVANS HOLLOW 24.0
END DESCRIPTION:
XS GIS Cut Line= 3
      2403224.97     13664875.03        2402975.       13665125.
      2402675.01     13665524.99
#Sta/Elev= 30
  4646.7   312.4  4717.4  308.54  4745.7  307.69  4847.5  302.98  4957.8  298.21
  4964.9  296.02  4971.9  296.04  4986.1   293.2  4994.4  292.75  4994.7  292.25
  4998.6  292.25  4998.9  292.75  5007.5  292.85  5013.8  294.22  5022.1  293.23
  5028.3  293.24  5036.7   295.6  5050.2  297.52  5072.1   298.4  5092.9  300.73
  5100.2  300.73  5128.3  302.59  5158.7  302.93  5172.1  303.79  5302.8  306.79
  5428.3  310.77  5434.5  311.27  5442.9  311.43  5486.7   314.7  5500.2  315.16
#Mann= 8 ,-1 , 0
  4646.7     .05       0  4847.5     .07       0  4994.4     .05       0
  4998.9     .07       0  5158.7    .035       0  5302.8     .05       0
  5428.3    .035       0  5434.5     .05       0
Bank Sta=4994.4,4998.9
XS Rating Curve= 0 ,0
Exp/Cntr=0.3,0.1

Type RM Length L Ch R = 1 ,12693   ,238,238,238
BEGIN DESCRIPTION:
EVANS HOLLOW 23.0
END DESCRIPTION:
XS GIS Cut Line= 3
      2403025.01     13664624.99        2402775.       13664725.
        2402625.     13665524.99
#Sta/Elev= 30
  4735.3  307.45  4756.9  306.56  4767.6   306.8  4882.1  301.92  4896.9  300.97
  4906.3   299.6  4911.7  300.03  4918.4  298.28  4960.1  295.83  4965.5  294.51
  4972.3  294.73  4980.8  292.33  4981.1  291.83    4985  291.83  4985.3  292.33
  4989.8   292.8  4995.1  295.46  5001.9  296.04  5030.9  295.34  5075.8  296.09
  5096.1  297.47  5177.5  299.38  5258.9  300.19  5309.8  301.69  5458.9  303.27
    5663  308.76  5739.7  311.24  5762.7  313.04  5787.1  314.55  5818.5  314.53
#Mann= 6 ,-1 , 0
  4735.3     .07       0  4980.8     .05       0  4985.3     .07       0
  5458.9     .05       0    5663    .035       0  5762.7     .05       0
Bank Sta=4980.8,4985.3
XS Rating Curve= 0 ,0
Exp/Cntr=0.3,0.1

Type RM Length L Ch R = 1 ,12455   ,681,681,681
BEGIN DESCRIPTION:
X19157
END DESCRIPTION:
XS GIS Cut Line= 3
      2402905.09     13664308.19      2402648.18     13664509.55
      2402398.18     13665335.95
#Sta/Elev= 30
  4642.6  310.34  4790.1  306.67  4825.4  304.19  4868.8  302.81  4875.1  303.55
  4918.5  301.06  4939.3  301.19  4947.4  299.23  4967.9   298.4  4974.7  299.23
  4985.3  298.29  4993.8  294.58  4999.1  290.94  5003.8  290.61  5004.1  290.11
  5008.4  290.61  5021.3  293.94  5047.8  295.38  5110.5  293.85  5152.7  294.85
  5226.6  298.05  5246.3  297.17  5465.7  301.47  5528.4  301.82    5612   305.1
  5643.4  305.15  5689.2  307.49  5716.5  306.95  5760.2   308.7  5832.4  311.23
#Mann= 8 ,-1 , 0
  4642.6     .07       0  4985.3     .12       0  5003.8     .05       0
  5008.4     .12       0  5021.3     .07       0  5152.7     .12       0
  5226.6     .07       0  5760.2    .035       0
Bank Sta=5003.8,5008.4
XS Rating Curve= 0 ,0
Exp/Cntr=0.3,0.1

Type RM Length L Ch R = 1 ,11774   ,443,443,443
BEGIN DESCRIPTION:
EVANS HOLLOW 22.0
END DESCRIPTION:
XS GIS Cut Line= 3
      2402724.96     13664325.02       2402307.9     13664565.11
      2402141.89     13664821.05
#Sta/Elev= 30
  4388.8  306.46  4477.1  301.95  4527.2  301.03    4536  300.15  4541.8  300.43
  4579.2  299.11  4638.1  298.27  4659.6   297.2  4711.8  296.27  4724.3  297.03
  4746.5   296.5  4769.5  297.19    4799  296.56  4814.8  297.25  4829.9  297.08
  4866.3  294.44  4922.4  291.89  4965.3  292.83  4994.9  291.71  4998.7  287.79
  4999.1  287.29    5003  287.29  5003.3  287.79  5010.1  291.42    5016  291.19
  5037.1  296.76  5046.3  298.36  5060.6  299.66  5118.8  301.02  5175.1  301.36
#Mann= 5 ,-1 , 0
  4388.8     .07       0  4829.9     .12       0  4866.3     .07       0
  4998.7     .05       0  5003.3     .07       0
Bank Sta=4998.7,5003.3
XS Rating Curve= 0 ,0
Exp/Cntr=0.3,0.1

Type RM Length L Ch R = 1 ,11331   ,454,454,454
BEGIN DESCRIPTION:
EVANS HOLLOW 21.0
END DESCRIPTION:
XS GIS Cut Line= 3
      2402774.99       13664275.        2402125.       13664275.
        2401775.       13664525.
#Sta/Elev= 30
    4346  308.36    4436  305.22    4476  303.07    4606  299.21    4806  294.76
    4816  295.29    4836  294.36  4886.6  293.95    4976   290.2  4983.5  287.54
  4983.8  287.04  4988.1  287.04  4988.5  287.54  4999.1  288.21  5003.4  289.39
  5009.5  289.21  5018.1  290.17  5068.5   290.4  5089.4   293.5  5124.8  293.62
  5160.7  295.22  5175.4  296.48  5204.9  297.31  5217.2  298.42  5267.6  298.74
  5276.2  299.47  5332.7  300.83  5347.5   301.7  5372.8  301.75  5426.1  303.29
#Mann= 6 ,-1 , 0
    4346     .07       0  4886.6     .12       0  4983.5     .05       0
  4988.5     .12       0  5124.8     .07       0  5372.8    .035       0
Bank Sta=4983.5,4988.5
XS Rating Curve= 0 ,0
Exp/Cntr=0.3,0.1

Type RM Length L Ch R = 1 ,10877   ,411,411,411
BEGIN DESCRIPTION:
EVANS HOLLOW 20.0
END DESCRIPTION:
XS GIS Cut Line= 3
      2402575.04       13663875.        2402075.       13663875.
      2401674.95     13663925.01
#Sta/Elev= 30
  4495.1  303.31  4695.1  297.39  4735.1  296.97  4865.1   293.9  4943.8  293.31
  4950.1   293.2  4975.1  292.27  4992.6  289.56  5005.2  289.15  5012.7   287.5
  5013.1     287  5017.4     287  5017.8   287.5  5025.4  289.58  5045.5  289.92
  5055.6  287.93  5065.7  289.84  5085.8  289.95    5106  289.42  5126.1  289.82
  5146.3  289.09  5176.5  289.19  5186.6  289.92  5199.2  289.39  5206.8  288.49
  5226.9  294.33  5247.1  296.56  5274.8  298.28  5327.7  300.15  5398.3  303.62
#Mann= 5 ,-1 , 0
  4495.1     .07       0  4943.8     .12       0  4950.1     .07       0
  5012.7     .05       0  5017.8     .07       0
Bank Sta=5012.7,5017.8
XS Rating Curve= 0 ,0
Exp/Cntr=0.3,0.1

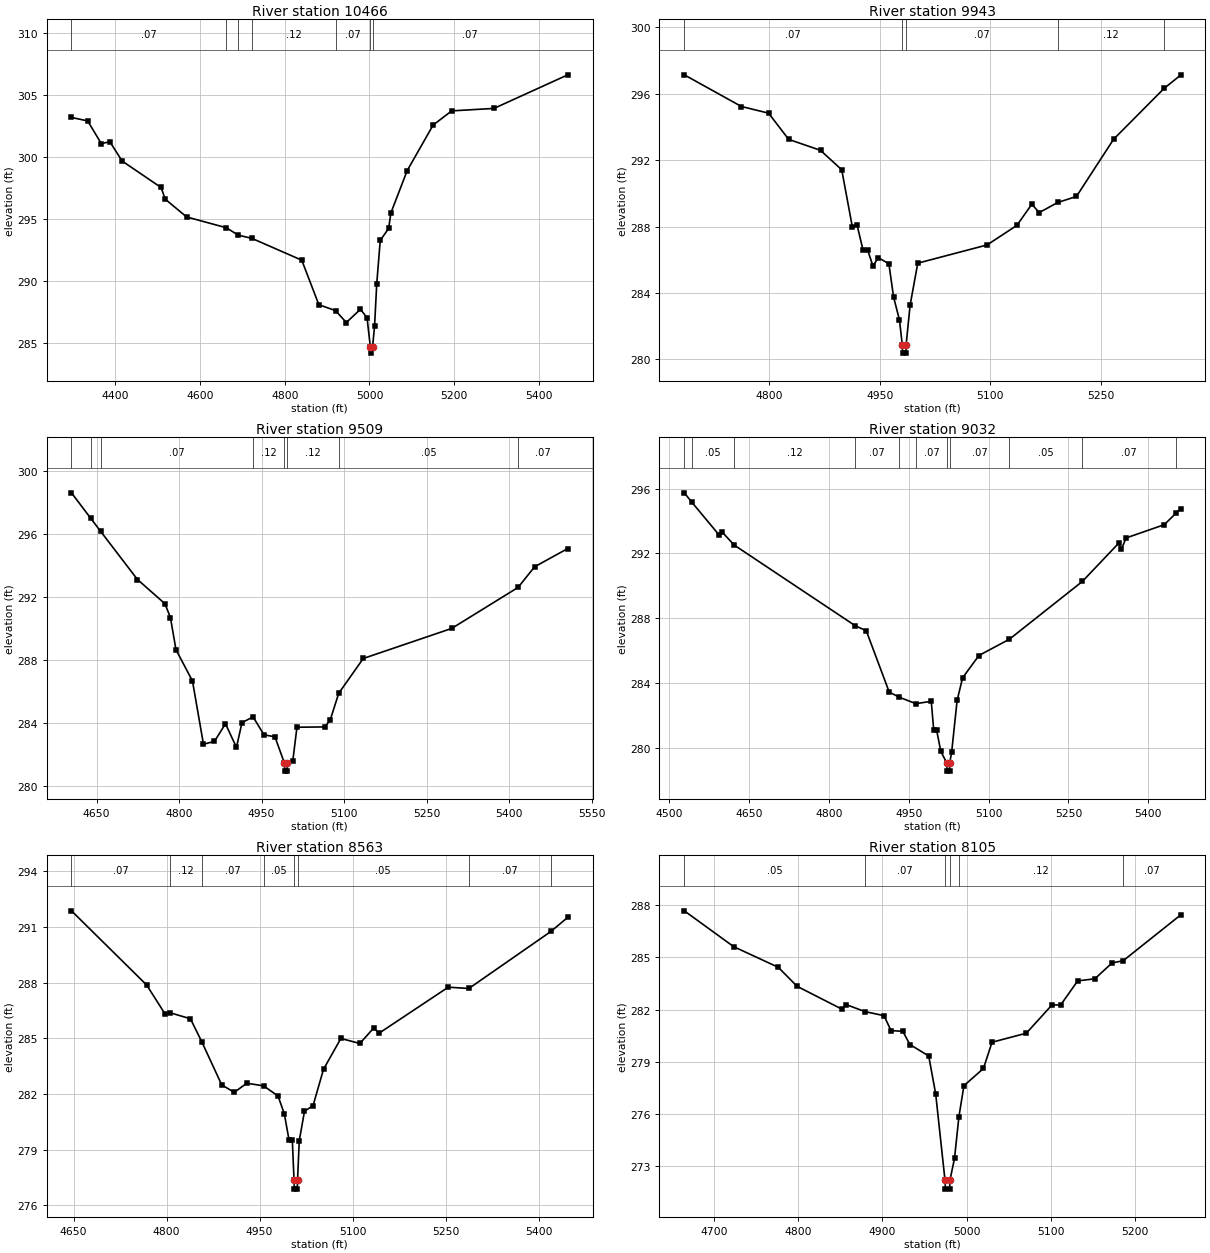
Type RM Length L Ch R = 1 ,10466   ,523,523,523
BEGIN DESCRIPTION:
EVANS HOLLOW 19.0
END DESCRIPTION:
XS GIS Cut Line= 3
      2402674.98       13663625.      2402071.79     13663551.22
      2401530.13      13663391.5
#Sta/Elev= 30
  4296.1   303.2  4334.3  302.92  4366.6  301.09  4386.7  301.24  4415.8  299.68
  4507.6  297.55  4517.7   296.6  4568.1  295.17  4661.8   294.3  4690.1   293.7
  4722.4  293.44  4840.1  291.68  4880.4  288.09  4919.9  287.61  4945.4  286.65
  4978.7  287.72  4994.3  287.04  5002.1  284.68  5002.5  284.18  5007.3  284.68
    5012  286.33  5017.2  289.78  5025.5  293.28  5045.3  294.24  5050.6  295.49
  5089.1  298.91  5150.5  302.59  5194.3  303.73  5294.2  303.93  5468.5  306.64
#Mann= 7 ,-1 , 0
  4296.1     .07       0  4661.8     .12       0  4690.1     .07       0
  4722.4     .12       0  4919.9     .07       0  5002.1     .05       0
  5007.3     .07       0
Bank Sta=5002.1,5007.3
XS Rating Curve= 0 ,0
Exp/Cntr=0.3,0.1

Type RM Length L Ch R = 1 ,9943    ,434,434,434
BEGIN DESCRIPTION:
EVANS HOLLOW 18.0
END DESCRIPTION:
XS GIS Cut Line= 3
      2402574.99     13663424.99        2402325.       13663225.
      2401974.99       13663175.
#Sta/Elev= 30
  4684.5  297.14  4762.1  295.23  4798.9  294.83  4826.2  293.25  4869.4  292.59
  4898.2  291.42  4912.6  287.98    4919  288.09    4927   286.6  4933.4  286.58
  4940.6  285.62  4947.8  286.12  4962.2  285.76  4968.6  283.75  4976.6  282.36
  4980.4  280.87  4980.8  280.37  4985.2  280.37  4985.6  280.87    4991  283.25
  5001.4  285.79  5095.6  286.89    5136  288.07  5156.2  289.34  5166.3  288.84
  5191.6  289.45  5216.8  289.81  5267.3  293.26    5336  296.33  5358.2  297.12
#Mann= 5 ,-1 , 0
  4684.5     .07       0  4980.4     .05       0  4985.6     .07       0
  5191.6     .12       0    5336     .07       0
Bank Sta=4980.4,4985.6
XS Rating Curve= 0 ,0
Exp/Cntr=0.3,0.1

Type RM Length L Ch R = 1 ,9509    ,477,477,477
BEGIN DESCRIPTION:
EVANS HOLLOW 17.0
END DESCRIPTION:
XS GIS Cut Line= 3
      2402924.98       13662925.        2402525.       13662925.
      2402024.98       13662975.
#Sta/Elev= 30
  4604.3  298.63  4639.3  297.01  4657.1  296.19  4724.3  293.12  4774.3  291.58
  4784.3  290.69  4794.3  288.66  4824.3  286.67  4844.3  282.65  4864.3  282.83
  4884.3  283.95  4904.3  282.45  4914.3  284.02  4934.5  284.39  4954.3  283.25
  4974.3  283.12  4991.6  281.44  4992.1  280.94  4996.5  280.94  4996.9  281.44
  5006.8  281.61  5014.3  283.73  5064.6  283.75  5074.6  284.17  5090.3  285.89
  5134.9   288.1  5295.7  290.01  5416.5  292.62  5446.5  293.93  5506.8  295.09
#Mann= 8 ,-1 , 0
  4604.3     .07       0  4639.3     .12       0  4657.1     .07       0
  4934.5     .12       0  4991.6     .05       0  4996.9     .12       0
  5090.3     .05       0  5416.5     .07       0
Bank Sta=4991.6,4996.9
XS Rating Curve= 0 ,0
Exp/Cntr=0.3,0.1

Type RM Length L Ch R = 1 ,9032    ,469,469,469
BEGIN DESCRIPTION:
EVANS HOLLOW 16.0
END DESCRIPTION:
XS GIS Cut Line= 3
      2402875.04     13662825.02        2402475.       13662575.
      2402025.02       13662675.
#Sta/Elev= 30
    4528  295.75  4542.4  295.16  4593.5  293.14  4599.4  293.32  4621.3  292.53
  4849.3  287.53    4870  287.22  4913.1  283.43  4932.1  283.11  4963.3  282.71
  4992.1  282.86  4996.8  281.06  5002.3  281.06    5010  279.77  5021.3  279.04
  5021.8  278.54  5026.4  278.54  5026.8  279.04  5030.5  279.73  5040.7  282.91
    5051  284.31  5081.7  285.69  5139.1   286.7  5276.1  290.27  5344.2  292.63
  5349.3  292.25  5358.3  292.96    5430  293.78  5451.7  294.48  5460.7  294.76
#Mann= 11 ,-1 , 0
    4528     .07       0  4542.4     .05       0  4621.3     .12       0
  4849.3     .07       0  4932.1     .12       0  4963.3     .07       0
  5021.3     .05       0  5026.8     .07       0  5139.1     .05       0
  5276.1     .07       0  5451.7     .05       0
Bank Sta=5021.3,5026.8
XS Rating Curve= 0 ,0
Exp/Cntr=0.3,0.1

Type RM Length L Ch R = 1 ,8563    ,458,458,458
BEGIN DESCRIPTION:
EVANS HOLLOW 15.0
END DESCRIPTION:
XS GIS Cut Line= 3
      2402824.96     13662125.01        2402475.       13662175.
      2402075.02     13662374.99
#Sta/Elev= 30
  4646.5  291.86  4767.7  287.87    4798  286.28  4805.9  286.37  4838.4  286.05
  4856.6  284.82  4888.9  282.49  4909.1  282.09  4929.3  282.58  4956.4  282.44
  4979.8  281.89  4989.9  280.93  4997.5  279.52  5002.8  279.52  5005.5  277.38
    5006  276.88  5010.8  276.88  5011.2  277.38    5014  279.49  5022.4  281.07
  5036.3  281.38  5053.1  283.33  5081.1  284.99  5111.8  284.72  5134.2  285.56
  5142.6  285.27  5254.4  287.75  5287.6  287.68    5420  290.75  5447.2  291.51
#Mann= 8 ,-1 , 0
  4646.5     .07       0  4805.9     .12       0  4856.6     .07       0
  4956.4     .05       0  5005.5     .05       0  5011.2     .05       0
  5287.6     .07       0    5420     .05       0
Bank Sta=5005.5,5011.2
XS Rating Curve= 0 ,0
Exp/Cntr=0.3,0.1

Type RM Length L Ch R = 1 ,8105    ,433,433,433
BEGIN DESCRIPTION:
EVANS HOLLOW 14.0
END DESCRIPTION:
XS GIS Cut Line= 3
      2402624.97     13661625.02        2402325.       13661775.
      2402075.02       13661825.
#Sta/Elev= 30
  4664.3  287.68    4723  285.62  4776.1  284.43  4798.4  283.34  4851.5  282.03
  4857.1  282.28  4879.4  281.88  4901.8  281.65  4910.2  280.79  4924.2  280.75
  4932.6  279.99    4955  279.33  4963.3  277.15  4974.4  272.17  4974.9  271.67
  4979.8  271.67  4980.2  272.17  4985.7  273.44  4990.9  275.83  4996.9  277.62
  5020.1  278.61  5030.3  280.12  5071.1  280.64  5101.7  282.27  5111.9  282.26
  5132.2  283.65  5152.6  283.77    5173  284.68  5186.3  284.81  5254.6  287.44
#Mann= 6 ,-1 , 0
  4664.3     .05       0  4879.4     .07       0  4974.4     .05       0
  4980.2     .07       0  4990.9     .12       0  5186.3     .07       0
Bank Sta=4974.4,4980.2
XS Rating Curve= 0 ,0
Exp/Cntr=0.3,0.1

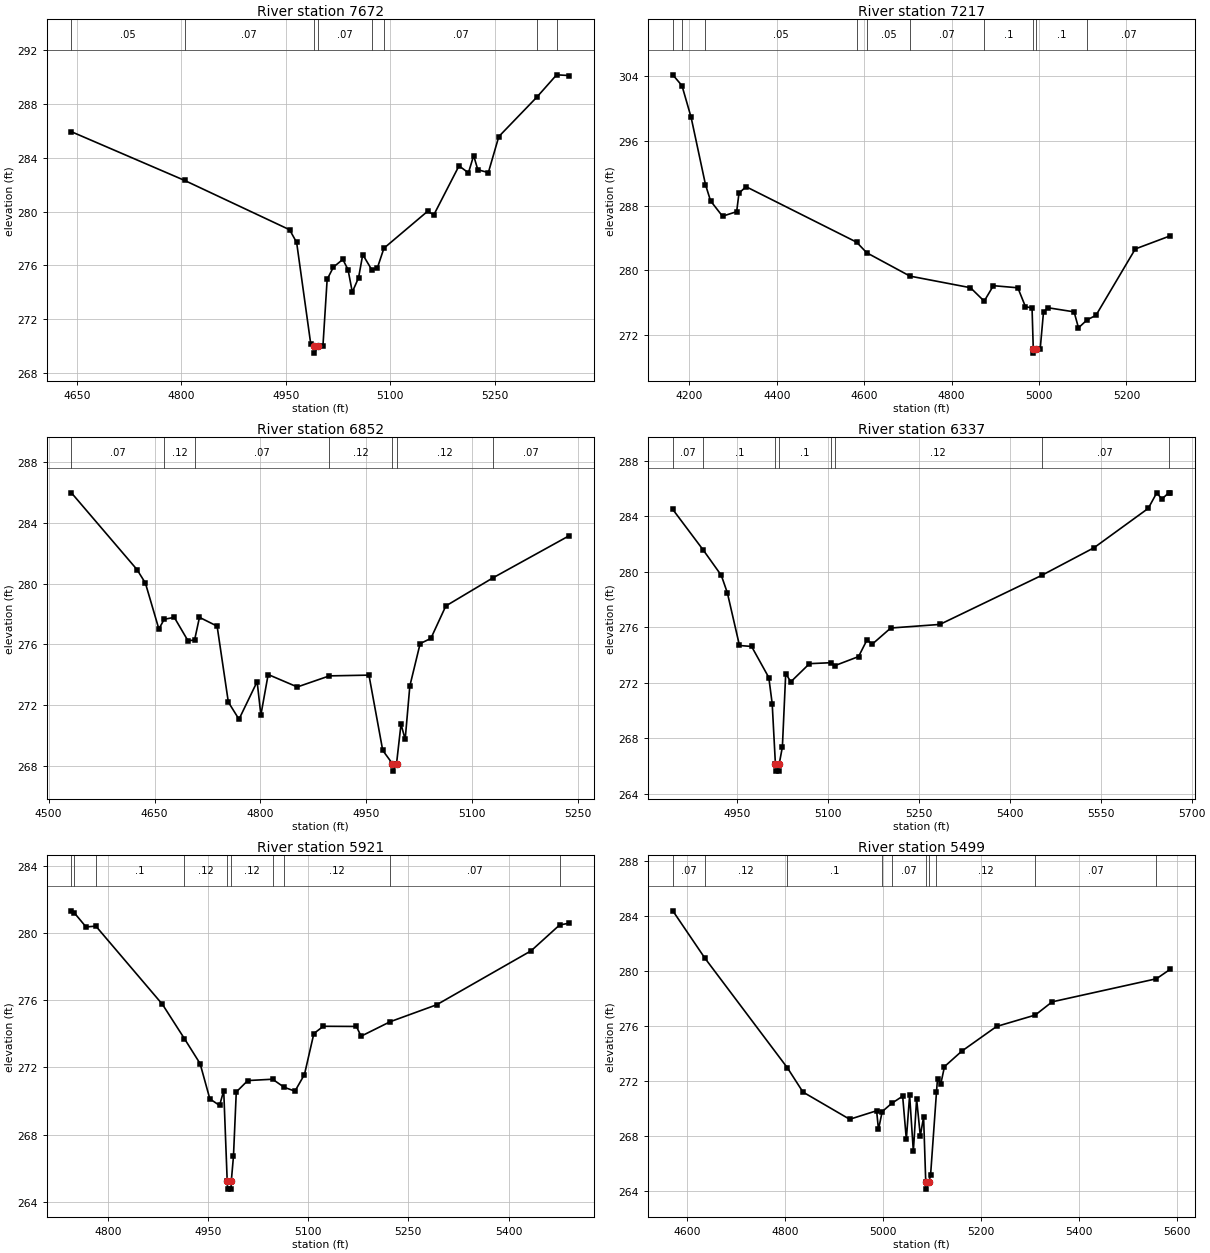
Type RM Length L Ch R = 1 ,7672    ,455,455,455
BEGIN DESCRIPTION:
EVANS HOLLOW 13.0
END DESCRIPTION:
XS GIS Cut Line= 3
      2402575.02       13661325.        2402225.       13661375.
      2401925.02     13661574.98
#Sta/Elev= 30
  4642.2  285.92  4804.6  282.31  4955.4  278.65  4965.5  277.71  4985.7   270.2
  4990.3     270  4990.8   269.5  4996.2     270  5003.3  270.06  5009.3  274.97
  5018.3  275.88  5031.8  276.45  5039.3  275.69  5045.4  274.03  5054.4  275.09
  5060.4  276.81  5073.5  275.67  5081.4  275.82  5090.8  277.28  5153.5  280.02
  5162.5  279.76  5198.6  283.39  5212.1  282.87  5219.6  284.15  5225.6   283.1
  5240.7  282.89  5255.7  285.56  5310.4  288.49  5338.7  290.14  5356.3  290.09
#Mann= 8 ,-1 , 0
  4642.2     .05       0  4804.6     .07       0  4990.3     .05       0
  4996.2     .07       0  5073.5     .12       0  5090.8     .07       0
  5310.4     .12       0  5338.7     .07       0
Bank Sta=4990.3,4996.2
XS Rating Curve= 0 ,0
Exp/Cntr=0.3,0.1

Type RM Length L Ch R = 1 ,7217    ,365,365,365
BEGIN DESCRIPTION:
EVANS HOLLOW 12.0
END DESCRIPTION:
XS GIS Cut Line= 3
        2402875.       13660725.        2402075.       13660975.
      2401775.05       13660975.
#Sta/Elev= 30
  4162.3  304.13  4183.3  302.79  4204.2  298.88    4237   290.6  4248.7  288.58
    4276  286.69  4308.4  287.25  4313.7  289.54  4329.9  290.33  4582.7  283.49
    4606  282.18  4704.9   279.3  4843.3  277.87  4874.7  276.21  4895.7  278.12
  4951.7  277.86    4969  275.54  4984.2  275.36    4987   270.3  4987.5   269.8
  4992.9   270.3  5002.9  270.35  5010.4  274.88  5020.4   275.4  5080.4  274.89
  5090.4  272.92  5110.3  273.91  5130.4  274.46  5220.4  282.65  5300.4  284.27
#Mann= 10 ,-1 , 0
  4162.3     .05       0  4183.3     .07       0    4237     .05       0
  4582.7     .07       0    4606     .05       0  4704.9     .07       0
  4874.7      .1       0    4987     .05       0  4992.9      .1       0
  5110.3     .07       0
Bank Sta=4987,4992.9
XS Rating Curve= 0 ,0
Exp/Cntr=0.3,0.1

Type RM Length L Ch R = 1 ,6852    ,515,515,515
BEGIN DESCRIPTION:
EVANS HOLLOW 11.0
END DESCRIPTION:
XS GIS Cut Line= 3
      2402425.04     13660524.99       2401995.4     13660634.55
      2401775.03     13660774.98
#Sta/Elev= 30
  4532.2     286  4625.1  280.94    4637  280.05  4656.1  277.02  4663.6  277.66
  4677.9  277.79  4697.4  276.24  4706.7   276.3  4713.6  277.79  4738.6  277.21
  4754.5   272.2  4769.6  271.07  4795.3  273.55  4800.6  271.35  4810.9  274.02
  4852.2   273.2  4897.6  273.93  4953.7  273.98  4973.2  269.02  4986.8  268.15
  4987.3  267.65  4992.8  268.15  4999.1  270.75    5005  269.74  5011.6  273.26
  5026.2  276.06  5041.4   276.4  5062.6  278.54  5129.2  280.39  5236.9  283.16
#Mann= 7 ,-1 , 0
  4532.2     .07       0  4663.6     .12       0  4706.7     .07       0
  4897.6     .12       0  4986.8     .05       0  4992.8     .12       0
  5129.2     .07       0
Bank Sta=4986.8,4992.8
XS Rating Curve= 0 ,0
Exp/Cntr=0.3,0.1

Type RM Length L Ch R = 1 ,6337    ,416,416,416
BEGIN DESCRIPTION:
EVANS HOLLOW 10.0
END DESCRIPTION:
XS GIS Cut Line= 3
      2402325.01       13660375.        2402175.       13660375.
      2401575.02     13660674.99
#Sta/Elev= 30
  4843.9  284.49  4894.2  281.56  4923.9  279.74  4933.9  278.48  4953.9  274.68
  4973.9  274.61  5002.3  272.37  5007.9  270.48  5013.2  266.12  5013.7  265.62
  5018.9  265.62  5019.4  266.12  5024.7  267.36  5030.2  272.66  5038.6  272.06
  5069.4  273.37  5105.4  273.44  5111.4  273.23  5150.4  273.88  5164.4  275.09
  5172.8  274.77  5203.5  275.94  5284.6   276.2  5452.7  279.74  5538.9  281.73
  5628.4  284.57  5642.4  285.69  5650.8  285.24  5662.2  285.69  5664.7  285.69
#Mann= 8 ,-1 , 0
  4843.9     .07       0  4894.2      .1       0  5013.2     .05       0
  5019.4      .1       0  5105.4     .07       0  5111.4     .12       0
  5452.7     .07       0  5662.2     .12       0
Bank Sta=5013.2,5019.4
XS Rating Curve= 0 ,0
Exp/Cntr=0.3,0.1

Type RM Length L Ch R = 1 ,5921    ,422,422,422
BEGIN DESCRIPTION:
EVANS HOLLOW 9.0
END DESCRIPTION:
XS GIS Cut Line= 3
      2402124.99     13659925.01        2401925.       13660075.
      2401574.97     13660425.03
#Sta/Elev= 30
  4745.4  281.32  4749.7   281.2  4767.3  280.36    4782  280.41  4881.8  275.75
  4914.7  273.71  4938.1  272.23  4952.7  270.13  4967.3  269.74  4973.5  270.62
  4978.7  265.26  4979.2  264.76  4984.4  264.76  4984.9  265.26  4988.1  266.72
  4992.3  270.54  5009.5  271.22  5046.7   271.3    5064  270.82  5080.2  270.59
  5094.4  271.58  5108.5  274.02  5122.7  274.45  5172.2  274.44  5179.2  273.86
  5222.7  274.72  5292.4  275.73  5433.8  278.94  5476.6  280.48  5490.4  280.58
#Mann= 10 ,-1 , 0
  4745.4     .12       0  4749.7     .07       0    4782      .1       0
  4914.7     .12       0  4978.7     .05       0  4984.9     .12       0
  5046.7      .1       0    5064     .12       0  5222.7     .07       0
  5476.6     .12       0
Bank Sta=4978.7,4984.9
XS Rating Curve= 0 ,0
Exp/Cntr=0.3,0.1

Type RM Length L Ch R = 1 ,5499    ,430,430,430
BEGIN DESCRIPTION:
EVANS HOLLOW 8.0
END DESCRIPTION:
XS GIS Cut Line= 3
      2402124.96     13659725.01        2401725.       13659825.
      2401274.97     13660225.03
#Sta/Elev= 30
  4571.3  284.35  4636.7  280.91    4805  272.93  4836.7  271.17    4932  269.19
  4986.9  269.81  4990.7  268.45  4998.3  269.75  5017.7  270.35    5040  270.87
  5047.5  267.73  5054.2  270.93  5061.8  266.86  5068.5  270.66    5076  267.98
  5082.7  269.36  5087.1  264.61  5087.6  264.11  5093.3  264.61  5096.9  265.11
    5109  271.17  5111.1  272.15  5117.8  271.77  5125.3  273.02  5160.4  274.14
  5231.5  275.94  5310.4  276.77  5344.8  277.73  5557.5  279.41  5585.7   280.1
#Mann= 10 ,-1 , 0
  4571.3     .07       0  4636.7     .12       0    4805      .1       0
  4998.3     .12       0  5017.7     .07       0  5087.1     .05       0
  5093.3     .07       0    5109     .12       0  5310.4     .07       0
  5557.5     .12       0
Bank Sta=5087.1,5093.3
XS Rating Curve= 0 ,0
Exp/Cntr=0.3,0.1

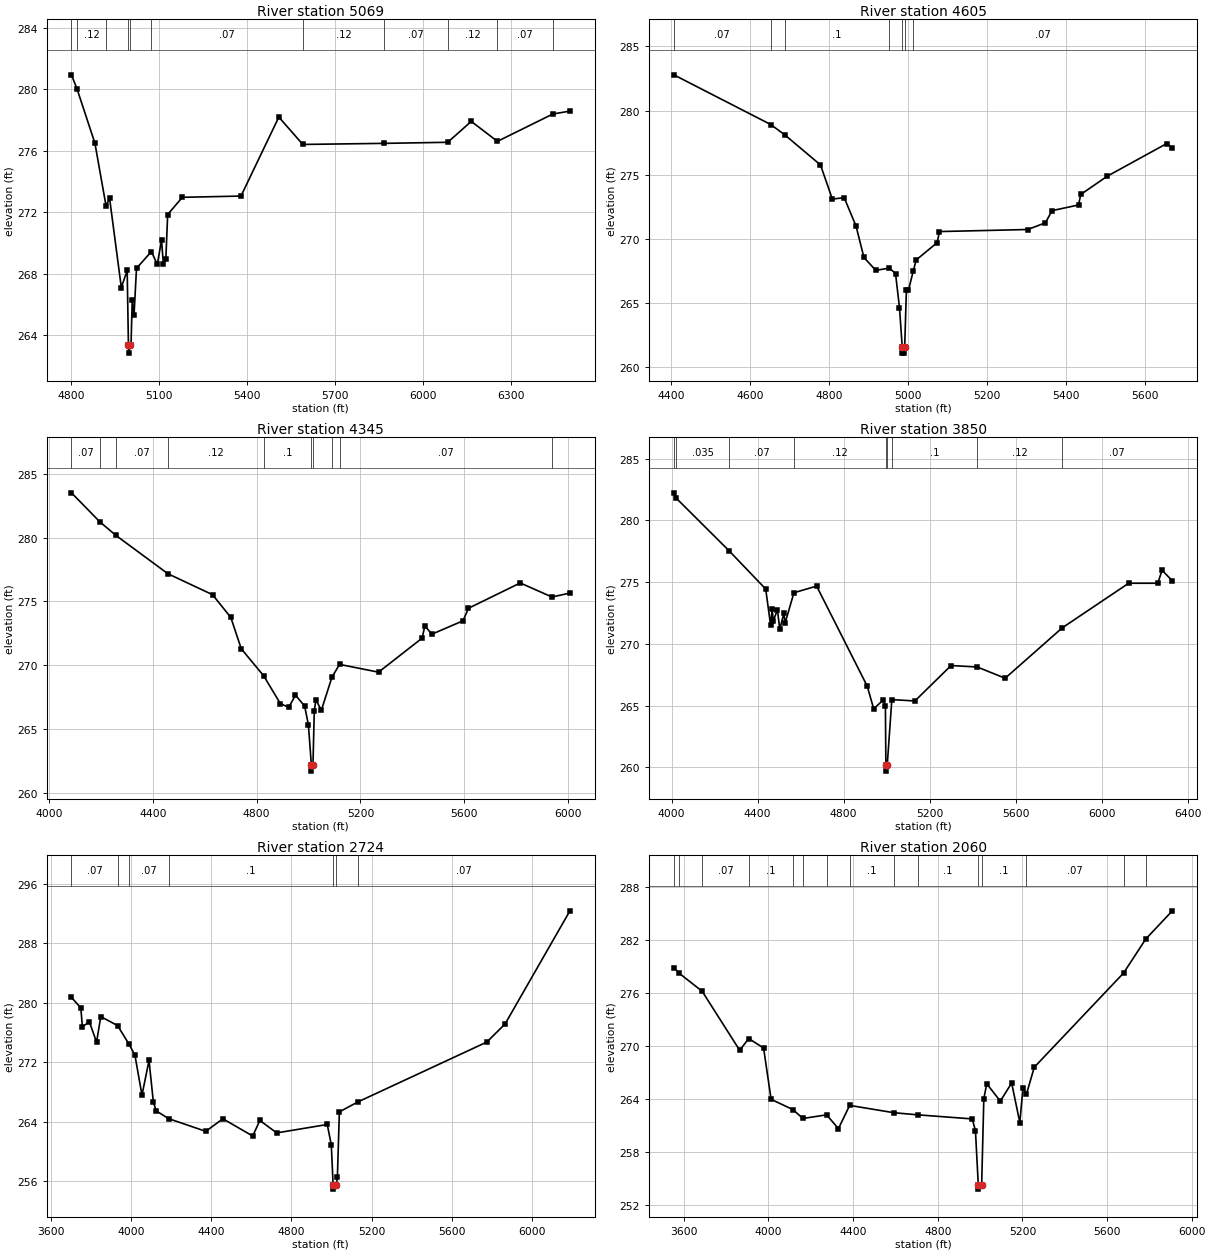
Type RM Length L Ch R = 1 ,5069    ,464,464,464
BEGIN DESCRIPTION:
EVANS HOLLOW 7.0
END DESCRIPTION:
XS GIS Cut Line= 3
      2402024.95       13659475.        2401825.       13659475.
      2400624.96     13660375.03
#Sta/Elev= 30
  4800.4  280.93  4819.8  279.99  4880.4  276.48  4918.3   272.4  4930.4   272.9
  4970.4  267.09  4990.4   268.2  4994.7  263.32  4995.2  262.82    5001  263.32
  5003.5  263.32  5007.6  266.29  5013.9  265.33  5022.2  268.34  5073.1  269.43
  5093.1  268.59  5107.6  270.17  5113.9  268.61  5122.2  268.92  5128.5  271.84
  5178.5  272.96  5378.5  273.04  5507.6  278.18  5589.4   276.4  5866.9  276.47
  6083.6  276.54  6163.9   277.9  6253.1   276.6  6442.1  278.38  6500.4  278.57
#Mann= 11 ,-1 , 0
  4800.4     .07       0  4819.8     .12       0  4918.3      .1       0
  4994.7     .05       0    5001      .1       0  5073.1     .07       0
  5589.4     .12       0  5866.9     .07       0  6083.6     .12       0
  6253.1     .07       0  6442.1      .1       0
Bank Sta=4994.7,5001
XS Rating Curve= 0 ,0
Exp/Cntr=0.3,0.1

Type RM Length L Ch R = 1 ,4605    ,260,260,260
BEGIN DESCRIPTION:
EVANS HOLLOW 6.0
END DESCRIPTION:
XS GIS Cut Line= 3
      2402266.25     13659134.55        2401675.       13659125.
      2401375.02     13659724.96
#Sta/Elev= 30
  4407.7  282.79  4652.9  278.92  4688.3  278.12    4779  275.77    4809  273.11
    4839  273.22    4869  271.01    4889  268.56    4919  267.56  4953.6  267.73
    4969  267.31    4979  264.65  4985.9  261.61  4986.4  261.11  4991.7  261.11
  4992.2  261.61  4996.5  266.02  5001.8  266.02  5014.1  267.53  5021.4  268.37
  5074.5  269.72  5080.1  270.58  5303.7  270.74  5348.4  271.26  5365.2  272.21
  5432.3  272.65  5437.9  273.47  5504.9  274.89  5655.9  277.44  5669.8  277.08
#Mann= 7 ,-1 , 0
  4407.7     .07       0  4652.9     .12       0  4688.3      .1       0
  4953.6     .12       0  4985.9     .05       0  4992.2     .12       0
  5014.1     .07       0
Bank Sta=4985.9,4992.2
XS Rating Curve= 0 ,0
Exp/Cntr=0.3,0.1

Type RM Length L Ch R = 1 ,4345    ,495,495,495
BEGIN DESCRIPTION:
X19156
END DESCRIPTION:
XS GIS Cut Line= 4
      2402516.24     13658912.33       2401682.9     13658835.94
       2401495.4     13658981.77      2401238.46     13659787.33
#Sta/Elev= 30
  4086.9   283.5  4197.3  281.21  4258.1  280.17  4458.4  277.17  4630.4  275.53
  4700.7  273.75  4740.9   271.3  4827.4  269.18  4891.5  267.01  4923.7  266.72
  4949.7  267.67    4985  266.82  4999.5  265.35  5010.8  262.23  5011.3  261.73
  5017.1  262.23  5022.1  266.44  5028.4  267.32  5049.2  266.48  5090.2  269.08
  5119.4  270.08  5269.6  269.47  5437.3  272.13  5448.1  273.09  5474.8  272.44
    5595  273.49    5616  274.47  5815.4  276.45  5937.6  275.35  6006.8  275.66
#Mann= 10 ,-1 , 0
  4086.9     .07       0  4197.3    .035       0  4258.1     .07       0
  4458.4     .12       0  4827.4      .1       0  5010.8     .05       0
  5017.1      .1       0  5090.2     .12       0  5119.4     .07       0
  5937.6     .12       0
Bank Sta=5010.8,5017.1
XS Rating Curve= 0 ,0
Exp/Cntr=0.3,0.1

Type RM Length L Ch R = 1 ,3850    ,1126,1126,1126
BEGIN DESCRIPTION:
X19155
END DESCRIPTION:
XS GIS Cut Line= 4
      2402564.82     13658815.09      2401537.07     13658419.27
      2401398.18     13658731.77       2401231.8     13659591.41
#Sta/Elev= 30
  4010.1  282.23  4022.1  281.78  4268.6  277.51  4437.4  274.44    4460  271.55
  4467.4  272.79  4472.8  271.87    4492  272.76  4502.8  271.18    4522  272.48
  4527.4  271.67  4568.7  274.14  4674.3  274.68  4909.7  266.58  4939.7  264.75
  4985.1  265.47  4994.3  264.95  4996.4   260.2  4996.9   259.7  5002.8   260.2
  5024.2  265.49  5131.5  265.38  5299.7  268.25  5421.6  268.13  5551.3  267.22
  5816.9   271.3  6125.9  274.91  6261.4  274.91  6281.2  275.96    6329  275.11
#Mann= 9 ,-1 , 0
  4010.1     .07       0  4022.1    .035       0  4268.6     .07       0
  4568.7     .12       0  4996.4     .05       0  5002.8     .12       0
  5024.2      .1       0  5421.6     .12       0  5816.9     .07       0
Bank Sta=4996.4,5002.8
XS Rating Curve= 0 ,0
Exp/Cntr=0.3,0.1

Type RM Length L Ch R = 1 ,2724    ,664,664,664
BEGIN DESCRIPTION:
EVANS HOLLOW 5.0
END DESCRIPTION:
XS GIS Cut Line= 3
      2402759.27     13658537.31      2402030.13     13657870.66
      2400544.02     13658051.22
#Sta/Elev= 30
    3704  280.74  3750.8  279.32  3758.3  276.79  3793.4  277.45  3829.2  274.72
  3850.1  278.16  3933.9  276.95  3991.6  274.42  4020.4  272.97  4055.5   267.6
  4090.6  272.26  4112.2  266.69  4126.4  265.48    4189  264.43  4373.7  262.73
  4458.8  264.42  4607.4   262.1  4643.2  264.19  4727.3  262.52  4979.2  263.65
  4999.3  260.92  5008.5  255.46    5009  254.96  5024.1  255.46  5029.6  256.53
  5039.6  265.35  5133.1   266.7    5775  274.74  5865.7  277.17    6189  292.38
#Mann= 7 ,-1 , 0
    3704     .07       0  3933.9     .12       0  3991.6     .07       0
    4189      .1       0  5008.5     .05       0  5024.1      .1       0
  5133.1     .07       0
Bank Sta=5008.5,5024.1
XS Rating Curve= 0 ,0
Exp/Cntr=0.3,0.1

Type RM Length L Ch R = 1 ,2060    ,614,614,614
BEGIN DESCRIPTION:
EVANS HOLLOW 4.0
END DESCRIPTION:
XS GIS Cut Line= 3
        2402675.       13658375.      2401760.89     13657448.76
      2400775.01       13657075.
#Sta/Elev= 30
  3552.9  278.84  3575.6  278.24  3686.8  276.15    3864  269.47  3906.9   270.8
  3977.1  269.72  4012.5  263.92    4116  262.75  4162.7  261.75  4274.8  262.16
  4330.7   260.6  4383.8  263.23  4593.2   262.4  4706.3  262.16  4962.9   261.7
  4978.2  260.37  4991.6  254.25  4992.1  253.75  5007.6  254.25  5017.8  263.99
  5031.7  265.68  5095.8  263.71  5149.3  265.77    5188  261.28  5202.8  265.24
  5219.2   264.5  5256.2  267.55  5678.7  278.23  5782.8  282.06  5908.6  285.26
#Mann= 15 ,-1 , 0
  3552.9     .07       0  3575.6     .12       0  3686.8     .07       0
  3906.9      .1       0    4116     .05       0  4162.7      .1       0
  4274.8     .05       0  4383.8      .1       0  4593.2     .07       0
  4706.3      .1       0  4991.6     .05       0  5007.6      .1       0
  5219.2     .07       0  5678.7    .035       0  5782.8     .07       0
Bank Sta=4991.6,5007.6
XS Rating Curve= 0 ,0
Exp/Cntr=0.3,0.1