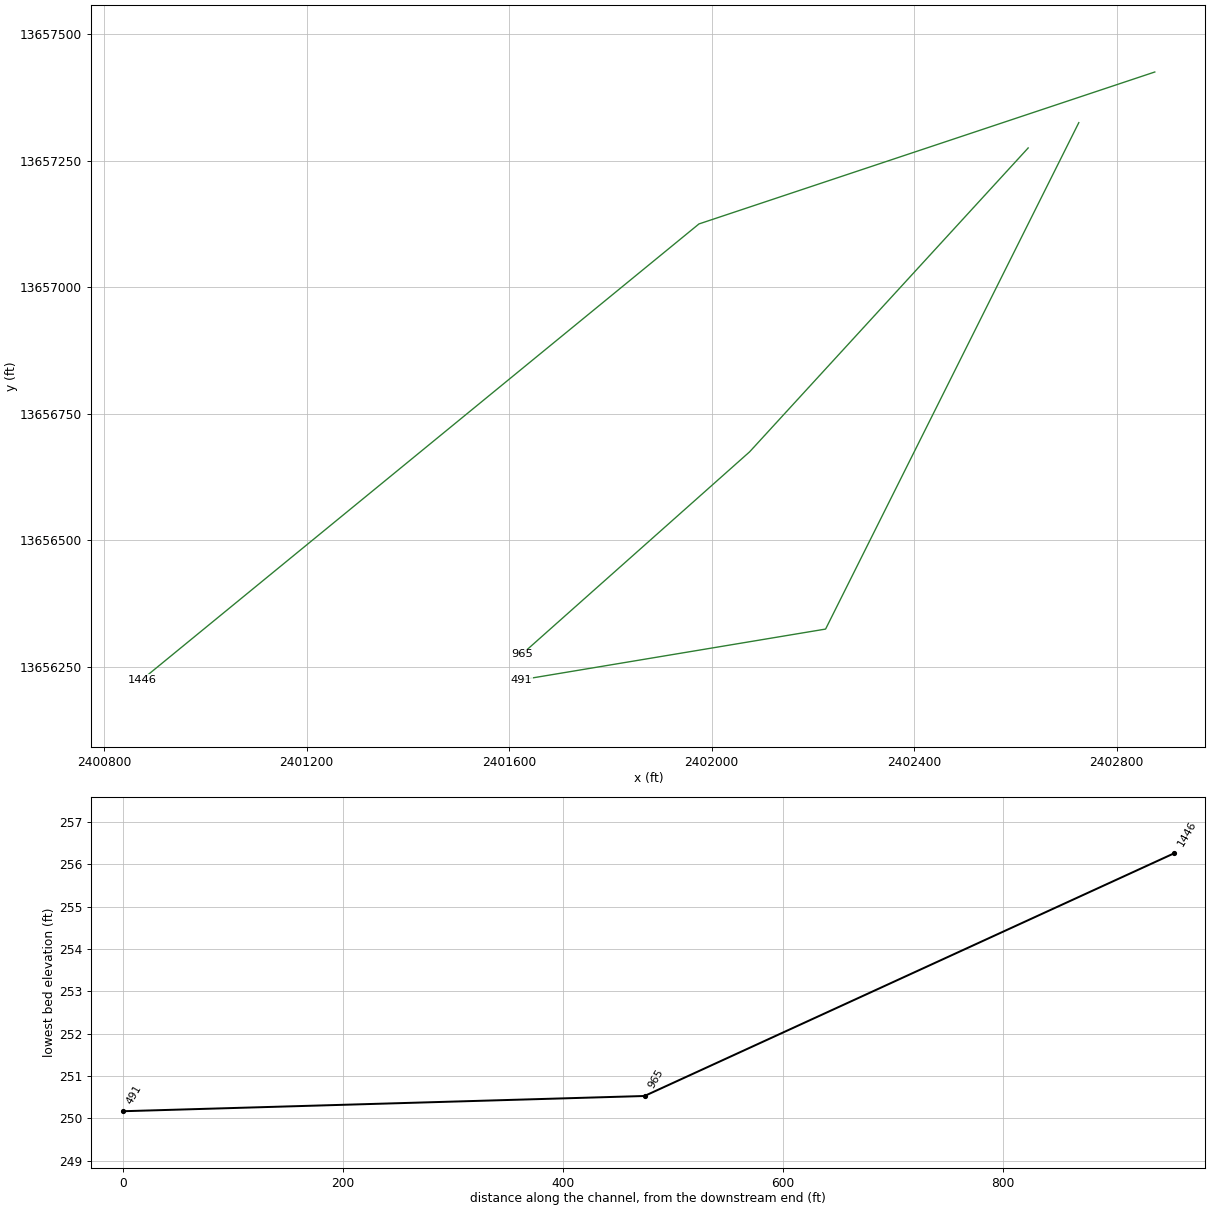
HEC-RAS study EVANS HOLLOW.prj: EVANS HOLLOW Base Level Engineering

--- EVANS HOLLOW.g01 (geometry) --- (continued)

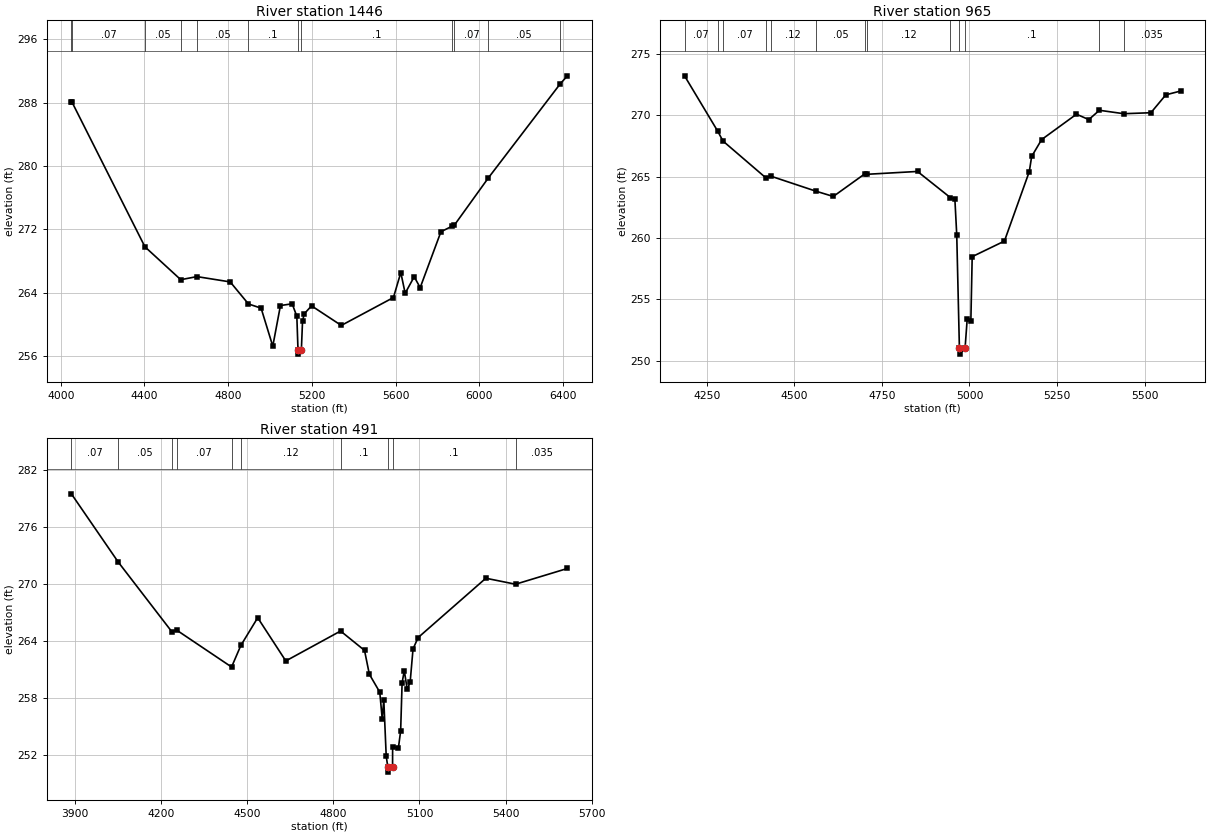
Type RM Length L Ch R = 1 ,1446    ,481,481,481
BEGIN DESCRIPTION:
EVANS HOLLOW 3.0
END DESCRIPTION:
XS GIS Cut Line= 3
        2402875.       13657425.        2401975.       13657125.
      2400875.04     13656225.03
#Sta/Elev= 30
  4050.8   288.1    4053   288.1  4402.3   269.8  4573.5  265.65  4650.8  266.04
  4809.7  265.37  4896.8  262.59  4957.3  262.06  5013.1  257.26  5049.7  262.39
  5105.7  262.61    5128  261.03  5133.6  256.76  5134.1  256.26  5149.6  256.76
  5155.2  260.38  5163.1  261.34  5198.3  262.35  5340.4  259.88  5589.5   263.4
  5624.7  266.55  5645.5  263.94  5688.6  266.02  5717.3  264.65  5816.4   271.7
    5869  272.39  5881.1  272.55  6042.3  278.47  6386.9  290.38  6420.7  291.37
#Mann= 12 ,-1 , 0
  4050.8     .05       0    4053     .07       0  4402.3     .05       0
  4573.5     .07       0  4650.8     .05       0  4896.8      .1       0
  5133.6     .05       0  5149.6      .1       0    5869    .035       0
  5881.1     .07       0  6042.3     .05       0  6386.9    .035       0
Bank Sta=5133.6,5149.6
XS Rating Curve= 0 ,0
Exp/Cntr=0.3,0.1

Type RM Length L Ch R = 1 ,965     ,474,474,474
BEGIN DESCRIPTION:
EVANS HOLLOW 2.0
END DESCRIPTION:
XS GIS Cut Line= 3
      2402625.01     13657275.01        2402075.       13656675.
      2401625.03     13656275.03
#Sta/Elev= 30
  4186.6  273.23  4280.8  268.74  4296.4  267.91  4419.5  264.89  4433.6  265.04
  4560.7  263.83  4611.2  263.39  4701.9  265.25  4708.2   265.2  4851.6  265.43
  4945.7  263.29  4958.3  263.16  4963.6  260.26  4971.2  251.03  4971.7  250.53
  4987.4  251.03  4993.5  253.41  5003.9  253.25  5007.7  258.48  5099.7  259.75
  5170.7  265.42  5177.4  266.65  5205.9  268.03  5305.4   270.1  5340.5  269.66
  5370.8  270.42  5440.3  270.14  5517.8  270.22  5560.4  271.68  5602.6  271.99
#Mann= 13 ,-1 , 0
  4186.6     .07       0  4280.8     .05       0  4296.4     .07       0
  4419.5     .05       0  4433.6     .12       0  4560.7     .05       0
  4701.9     .07       0  4708.2     .12       0  4945.7      .1       0
  4971.2     .05       0  4987.4      .1       0  5370.8     .12       0
  5440.3    .035       0
Bank Sta=4971.2,4987.4
XS Rating Curve= 0 ,0
Exp/Cntr=0.3,0.1

Type RM Length L Ch R = 1 ,491     ,0,0,0
BEGIN DESCRIPTION:
EVANS HOLLOW 1.0
END DESCRIPTION:
XS GIS Cut Line= 3
        2402725.       13657325.        2402225.       13656325.
      2401625.01       13656225.
#Sta/Elev= 30
  3888.5  279.48  4051.5   272.3  4238.1  264.96  4254.8  265.13  4446.1  261.24
  4478.3  263.51    4537  266.43  4634.8  261.88  4825.4  265.03  4908.7  262.99
  4925.5  260.48  4961.8  258.59  4970.2   255.8  4975.8  257.78  4984.2  251.84
    4990  250.67  4990.5  250.17  5006.3  250.67  5006.5   252.8  5026.8  252.76
  5034.4   254.5  5039.5  259.58  5047.1  260.86  5057.2  258.89  5067.4  259.62
  5077.5  263.14  5095.2  264.34  5330.9  270.59  5434.1  269.96  5614.8  271.62
#Mann= 10 ,-1 , 0
  3888.5     .07       0  4051.5     .05       0  4238.1     .12       0
  4254.8     .07       0  4446.1     .05       0  4478.3     .12       0
  4825.4      .1       0    4990     .05       0  5006.3      .1       0
  5434.1    .035       0
Bank Sta=4990,5006.3
XS Rating Curve= 0 ,0
Exp/Cntr=0.3,0.1

Chan Stop Cuts=-1
Use User Specified Reach Order=0
Composite Channel Slope=5