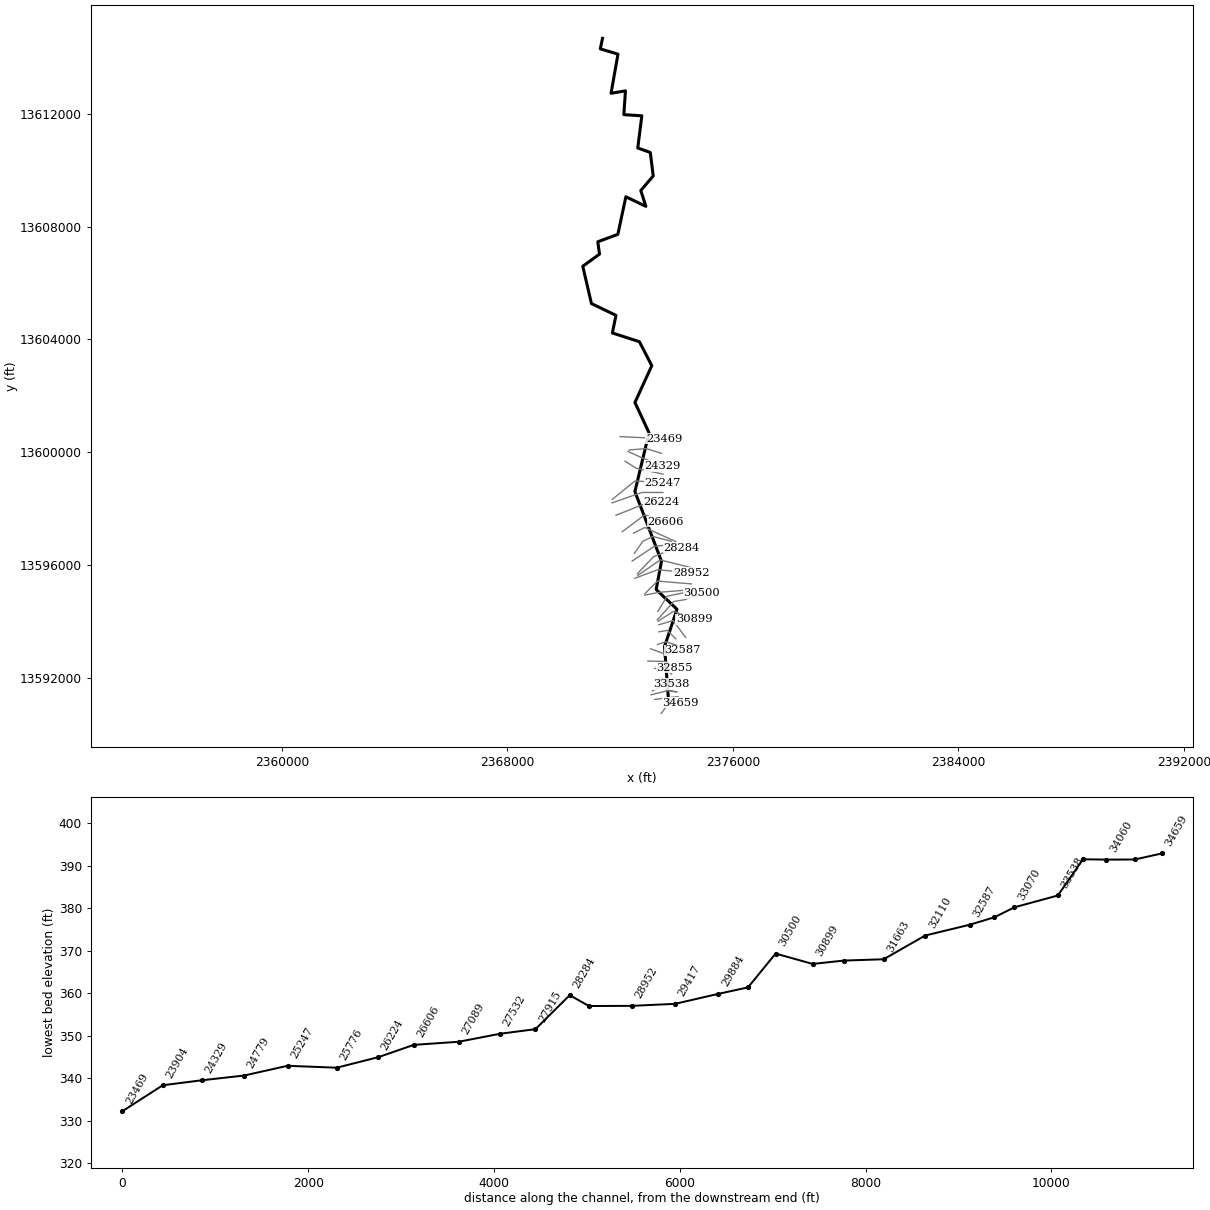
--- JACK PUMP CREEK.prj (project) ---

Proj Title=JACK PUMP CREEK Base Level Engineering
Current Plan=p01
Default Exp/Contr=0.3,0.1
English Units
Geom File=g01
Flow File=f01
Plan File=p01
Y Axis Title=Elevation
X Axis Title(PF)=Main Channel Distance
X Axis Title(XS)=Station
BEGIN DESCRIPTION:
JACK PUMP CREEK
END DESCRIPTION:
DSS Export Rating Curves= 0
DSS Export Rating Curve Sorted= 0
DSS Export Volume Flow Curves= 0
DXF OffsetX= 0
DXF OffsetY= 0
DXF ScaleX= 1
DXF ScaleY= 10

--- JACK PUMP CREEK.p01 (plan) ---

Plan Title=Multiple Run
Program Version=4.10
Short Identifier=Multiple
Geom File=g01
Flow File=f01
Subcritical Flow
K Sum by GR= 0
Std Step Tol= 0.01
Critical Tol= 0.01
Num of Std Step Trials= 20
Max Error Tol= 0.3
Flow Tol Ratio= 0.001
Split Flow NTrial= 30
Split Flow Tol= 0.02
Split Flow Ratio= 0.02
Log Output Level= 0
Friction Slope Method= 1
Unsteady Friction Slope Method= 2
Unsteady Bridges Friction Slope Method= 1
Parabolic Critical Depth
Global Vel Dist= 1 , 1 , 1
Global Log Level= 0
CheckData=True
Encroach Param=-1 ,0,0, 0
BEGIN DESCRIPTION:
Multiple Run
END DESCRIPTION:
Computation Interval=1HOUR
Output Interval=1HOUR
Run HTab= 0
Run UNet= 0
Run PostProcess= 0
Run WQNet= 0
UNET Theta= 1
UNET Theta Warmup= 1
UNET ZTol= 0.02
UNET ZSATol= 0.05
UNET MxIter= 20
UNET MaxInSteps= 0
UNET DtIC= 0
UNET DtMin= 0
UNET MaxCRTS= 20
UNET WFStab= 2
UNET SFStab= 1
UNET WFX= 1
UNET SFX= 1
UNET DSS MLevel= 4
UNET DZMax Abort= 100
UNET Convert EG Bridges= 0
UNET Use Existing IB Tables=-1
UNET Froude Reduction=False
UNET Froude Limit= 1
UNET Froude Power= 10
UNET Time Slicing=0,0, 5
UNET Junction Losses=0
Instantaneous Interval=1HOUR
Write IC File= 0
Write IC File at Sim End=0
Echo Input=False
Echo Parameters=False
Echo Output=False
Write Detailed= 0
WQ AD Non Conservative
WQ ULTIMATE=-1
WQ Max Comp Step=1HOUR
WQ Output Interval=15MIN
WQ Output Selected Increments= 0
WQ Output face flow=0
WQ Output face velocity=0
WQ Output face area=0
WQ Output face dispersion=0
WQ Output cell volume=0
WQ Output cell surface area=0
WQ Output cell continuity=0
WQ Output cumulative cell continuity=0
WQ Output face conc=0
WQ Output face dconc_dx=0
WQ Output face courant=0
WQ Output face peclet=0
WQ Output face adv mass=0
WQ Output face disp mass=0
WQ Output cell mass=0
WQ Output cell source sink temp=0
WQ Output cell source sink nsm=0
WQ Output MaxMinRange=-1
WQ Daily Max Min Mean=-1
WQ Daily Range=0
WQ Daily Time=0
WQ Create Restart=0
WQ Fixed Restart=0
WQ System Summary=0
WQ Use Fixed Temperature=0
Sorting and Armoring Iterations= 10
XS Update Threshold= 0.02
Hydraulics Update Threshold= 0.02
Energy Slope Method= 1
Volume Change Method= 0
XS Weighting Method= 0
Number of US Weighted Cross Sections= 1
Number of DS Weighted Cross Sections= 1
Upstream XS Weight=0.25
Main XS Weight=0.5
Downstream XS Weight=0.25
Number of DS XS's Weighted with US Boundary= 1
Upstream Boundary Weight= 1
Weight of XSs Associated with US Boundary= 0
Number of US XS's Weighted with DS Boundary= 1
Downstream Boundary Weight= 0.5
Weight of XSs Associated with DS Boundary= 0.5
Sediment Output Level= 4
Mass or Volume Output= 0
Output Increment Type= 1
Profile and TS Output Increment= 10
XS Output Flag= 0
XS Output Increment= 10
Disregard all LS=0
Disregard all Conn=0
Disregard all Breaches=0
Disregard all Pumps=0

--- JACK PUMP CREEK.f01 (steady flow) ---

Flow Title=Multiple
Number of Profiles=7
Profile Names=10-year,25-year,50-year,1pct_min,100-year,1pct_plu,500-year
River Rch & RM= JACK PUMP CREEK,Reach-1,34659
     405     643     855     552    1101    2196    1806
River Rch & RM= JACK PUMP CREEK,Reach-1,30500
     805    1333    1821    1203    2401    4791    4143
River Rch & RM= JACK PUMP CREEK,Reach-1,29417
    1026    1710    2345    1554    3101    6186    5381
River Rch & RM= JACK PUMP CREEK,Reach-1,21022
    1468    2477    3427    2288    4565    9108    8039
River Rch & RM= JACK PUMP CREEK,Reach-1,17540
    2168    3696    5147    3453    6890   13748   12256
River Rch & RM= JACK PUMP CREEK,Reach-1,7078
    2407    4113    5734    3850    7683   15329   13689
River Rch & RM= JACK PUMP CREEK,Reach-1,2351
    3087    5311    7440    5016   10009   19970   17977
Boundary for River Rch & Prof#=JACK PUMP CREEK,Reach-1,1
Up Type=0
Dn Type=3
Dn Slope=0.005
Boundary for River Rch & Prof#=JACK PUMP CREEK,Reach-1,2
Up Type=0
Dn Type=3
Dn Slope=0.005
Boundary for River Rch & Prof#=JACK PUMP CREEK,Reach-1,3
Up Type=0
Dn Type=3
Dn Slope=0.005
Boundary for River Rch & Prof#=JACK PUMP CREEK,Reach-1,4
Up Type=0
Dn Type=3
Dn Slope=0.005
Boundary for River Rch & Prof#=JACK PUMP CREEK,Reach-1,5
Up Type=0
Dn Type=3
Dn Slope=0.005
Boundary for River Rch & Prof#=JACK PUMP CREEK,Reach-1,6
Up Type=0
Dn Type=3
Dn Slope=0.005
Boundary for River Rch & Prof#=JACK PUMP CREEK,Reach-1,7
Up Type=0
Dn Type=3
Dn Slope=0.005

--- JACK PUMP CREEK.g01 (geometry) ---

Geom Title=Existing Conditions
Program Version=4.10

River Reach=JACK PUMP CREEK ,Reach-1
Reach XY= 30
        2373725.       13591075.      2373575.07     13593104.97
       2374017.7     13594424.92      2373278.45     13595126.48
       2373467.4     13596128.33       2372524.5     13598599.96
       2373025.5     13600685.21      2372525.51     13601759.79
      2373123.96     13603064.57      2372684.68     13603914.83
        2371725.       13604225.      2371852.31     13604849.15
      2370983.03     13605268.66      2370675.36     13606590.16
      2371269.54     13607022.55      2371207.76     13607458.76
       2371919.6     13607722.54      2372204.35      13609055.6
      2372914.39     13608714.94      2372733.05      13609278.3
      2373175.04     13609794.98      2373069.92     13610627.31
      2372625.86     13610785.31       2372769.6     13611927.71
      2372132.68     13611968.47      2372188.88     13612811.62
      2371678.39     13612726.41      2371924.25     13614114.32
       2371297.5     13614301.03        2371375.       13614675.

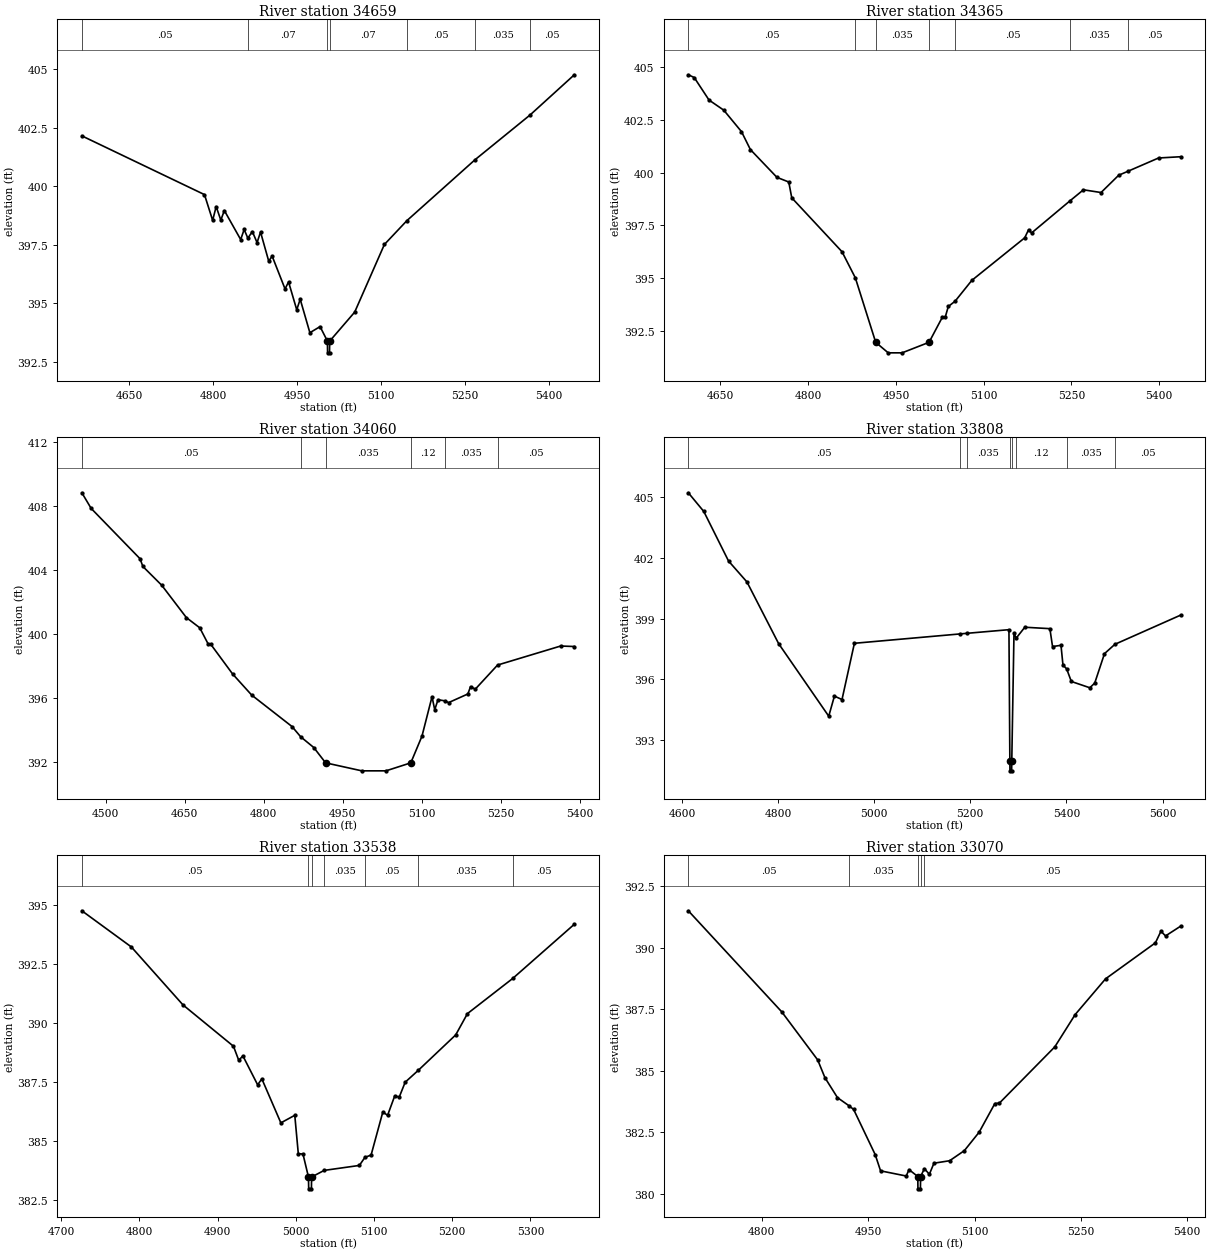
Type RM Length L Ch R = 1 ,34659   ,294,294,294
BEGIN DESCRIPTION:
A19493
END DESCRIPTION:
XS GIS Cut Line= 4
      2373460.34     13590732.71      2373703.16      13591060.3
      2373728.36     13591099.24      2374154.41      13591108.4
#Sta/Elev= 30
  4565.6  402.15  4784.8  399.64  4799.4  398.54  4805.7  399.13    4814  398.55
  4820.3  398.96  4849.5  397.72  4855.7  398.15  4862.3  397.78  4870.4  398.06
  4878.8  397.59    4885  398.04  4899.6   396.8  4905.8  397.01  4928.8  395.61
  4935.1  395.91  4949.7  394.72  4955.9  395.17  4973.2  393.74  4991.4     394
  5004.6  393.38  5004.8  392.88  5008.3  392.88  5008.6  393.38  5053.3  394.62
  5106.4  397.51  5146.7  398.53  5268.4  401.13  5366.7  403.04  5445.9  404.76
#Mann= 7 ,-1 , 0
  4565.6     .05       0  4862.3     .07       0  5004.6     .05       0
  5008.6     .07       0  5146.7     .05       0  5268.4    .035       0
  5366.7     .05       0
Bank Sta=5004.6,5008.6
XS Rating Curve= 0 ,0
Exp/Cntr=0.3,0.1

Type RM Length L Ch R = 1 ,34365   ,305,305,305
BEGIN DESCRIPTION:
JACK PUMP CREEK 48.0
END DESCRIPTION:
XS GIS Cut Line= 3
      2373224.98       13591225.      2373659.64     13591287.07
      2374060.76     13591323.14
#Sta/Elev= 30
  4595.2  404.65  4605.3  404.52  4630.6  403.45  4655.8  402.97  4686.1  401.95
  4701.3   401.1  4746.7  399.78  4766.9  399.56    4772  398.81  4857.9  396.25
  4880.7  395.01  4915.5  391.95  4936.9  391.45  4960.6  391.45  5006.7  391.95
  5029.4  393.14  5034.3  393.14  5039.6  393.65  5051.2   393.9  5079.8  394.89
  5170.2  396.91  5176.9   397.3  5181.9  397.14  5248.2  398.68  5270.6  399.19
  5300.7  399.06  5330.8  399.88  5346.7  400.07    5399   400.7    5437  400.76
#Mann= 7 ,-1 , 0
  4595.2     .05       0  4880.7     .12       0  4915.5    .035       0
  5006.7     .12       0  5051.2     .05       0  5248.2    .035       0
  5346.7     .05       0
Bank Sta=4915.5,5006.7
XS Rating Curve= 0 ,0
Exp/Cntr=0.3,0.1

Type RM Length L Ch R = 1 ,34060   ,252,252,252
BEGIN DESCRIPTION:
JACK PUMP CREEK 47.0
END DESCRIPTION:
XS GIS Cut Line= 3
      2373097.79     13591392.04      2373689.17      13591539.1
      2374010.73     13591489.15
#Sta/Elev= 30
    4455  408.82  4472.7  407.84  4565.5  404.69  4570.8  404.21  4606.7  403.03
  4653.4  401.01  4678.8  400.37  4694.7  399.36  4699.9  399.33  4741.2  397.48
  4777.4  396.16    4854  394.19  4870.4  393.55  4895.2  392.88  4917.7  391.92
  4986.4  391.42  5032.3  391.42  5079.4  391.92  5100.6  393.59  5119.7  396.06
  5124.8  395.24    5131  395.87  5144.1   395.8  5151.2  395.69  5187.7  396.23
  5192.8  396.69  5201.8  396.53  5244.1  398.04  5363.8  399.23  5389.8   399.2
#Mann= 6 ,-1 , 0
    4455     .05       0  4870.4     .12       0  4917.7    .035       0
  5079.4     .12       0  5144.1    .035       0  5244.1     .05       0
Bank Sta=4917.7,5079.4
XS Rating Curve= 0 ,0
Exp/Cntr=0.3,0.1

Type RM Length L Ch R = 1 ,33808   ,270,270,270
BEGIN DESCRIPTION:
A19492
END DESCRIPTION:
XS GIS Cut Line= 6
      2373146.53     13591530.47      2373478.78     13591719.06
      2373593.91     13591746.53      2373658.88     13591723.66
      2373760.17     13591542.52      2374001.35     13591499.39
#Sta/Elev= 30
  4613.2  405.19  4645.4  404.27  4696.9  401.83  4735.2   400.8  4801.2  397.76
  4905.4  394.19  4917.2  395.18    4933  395.01  4958.8  397.78  5178.3  398.24
  5192.5  398.27  5280.4  398.45  5282.3     392  5282.5   391.5    5286   391.5
  5286.3     392  5290.9  398.28  5295.4  398.03  5313.4  398.57  5365.6   398.5
  5371.1  397.62  5388.7  397.68  5392.8  396.71  5400.5  396.52  5410.2   395.9
  5448.7  395.59  5458.9  395.82  5479.2  397.27  5500.9  397.73    5638  399.17
#Mann= 8 ,-1 , 0
  4613.2     .05       0  5178.3     .12       0  5192.5    .035       0
  5282.3     .05       0  5286.3    .035       0  5295.4     .12       0
  5400.5    .035       0  5500.9     .05       0
Bank Sta=5282.3,5286.3
XS Rating Curve= 0 ,0
Exp/Cntr=0.3,0.1

Type RM Length L Ch R = 1 ,33538   ,468,468,468
BEGIN DESCRIPTION:
JACK PUMP CREEK 46.0
END DESCRIPTION:
XS GIS Cut Line= 3
      2373274.99       13591875.        2373525.       13591975.
      2373824.98     13591775.01
#Sta/Elev= 30
  4726.4  394.75  4789.7  393.22  4855.7  390.77  4920.3  389.02    4927  388.43
  4932.4  388.61  4951.2  387.39  4956.6  387.64  4980.9  385.78  4998.7   386.1
  5003.2  384.48  5009.2  384.46  5016.2  383.49  5016.5  382.99    5020  382.99
  5020.2  383.49  5036.3  383.77  5081.3  383.98  5088.4  384.32  5096.3  384.42
  5111.3  386.24  5117.4   386.1  5126.4  386.91  5132.4  386.88  5139.9   387.5
  5156.9  388.01  5204.5   389.5  5219.5   390.4  5277.5  391.89  5356.2  394.18
#Mann= 7 ,-1 , 0
  4726.4     .05       0  5016.2     .05       0  5020.2     .05       0
  5036.3    .035       0  5088.4     .05       0  5156.9    .035       0
  5277.5     .05       0
Bank Sta=5016.2,5020.2
XS Rating Curve= 0 ,0
Exp/Cntr=0.3,0.1

Type RM Length L Ch R = 1 ,33070   ,215,215,215
BEGIN DESCRIPTION:
JACK PUMP CREEK 45.0
END DESCRIPTION:
XS GIS Cut Line= 3
      2373224.95     13592324.99        2373525.       13592375.
        2373825.       13592125.
#Sta/Elev= 30
  4696.3  391.49  4828.1  387.39  4878.8  385.44    4889  384.72  4906.7  383.91
    4923  383.58  4929.5  383.43  4959.9   381.6  4967.5  380.94  5003.7  380.73
  5007.6  380.99    5020  380.71  5020.2  380.21  5023.7  380.21    5024  380.71
  5029.3  381.03  5036.3   380.8  5042.8  381.25  5064.9  381.35  5085.7  381.76
  5106.6  382.51  5128.7  383.67  5135.2  383.69  5213.3  385.97    5242  387.28
  5284.9  388.73  5355.2  390.19    5363  390.66  5369.5  390.47    5391  390.87
#Mann= 5 ,-1 , 0
  4696.3     .05       0    4923    .035       0    5020    .035       0
    5024    .035       0  5029.3     .05       0
Bank Sta=5020,5024
XS Rating Curve= 0 ,0
Exp/Cntr=0.3,0.1

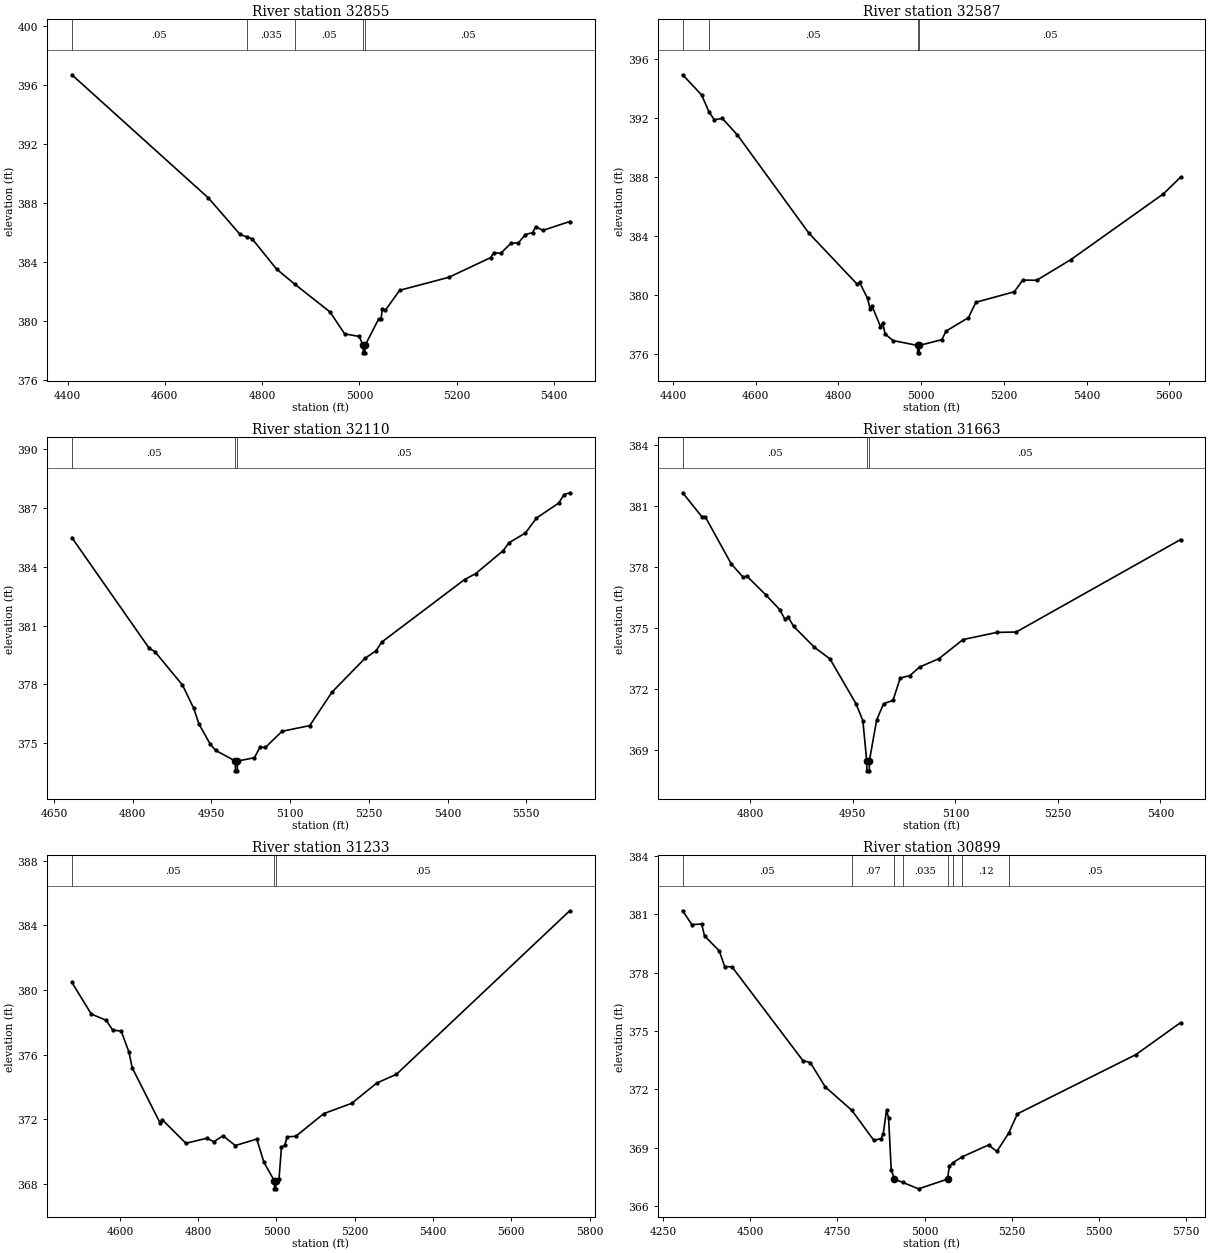
Type RM Length L Ch R = 1 ,32855   ,268,268,268
BEGIN DESCRIPTION:
A19491
END DESCRIPTION:
XS GIS Cut Line= 3
      2372984.47      13592588.5      2373619.86     13592572.88
      2373936.84     13592349.43
#Sta/Elev= 30
  4408.9  396.72  4689.5  388.37  4754.6   385.9  4768.4  385.73  4779.5   385.6
  4829.6  383.55  4866.9  382.53  4939.6  380.64  4969.6  379.16  4999.6  378.98
  5007.6  378.37  5007.9  377.87  5011.4  377.87  5011.6  378.37  5039.6  380.17
  5044.5  380.17  5047.1  380.86  5053.2  380.75  5082.8  382.11  5183.8  382.99
    5270  384.33  5276.1  384.66  5290.9  384.62  5311.8  385.31  5326.6  385.32
  5341.4  385.89  5356.2  386.02  5362.3  386.43  5377.1  386.17  5432.3  386.77
#Mann= 5 ,-1 , 0
  4408.9     .05       0  4768.4    .035       0  4866.9     .05       0
  5007.6     .05       0  5011.6     .05       0
Bank Sta=5007.6,5011.6
XS Rating Curve= 0 ,0
Exp/Cntr=0.3,0.1

Type RM Length L Ch R = 1 ,32587   ,477,477,477
BEGIN DESCRIPTION:
JACK PUMP CREEK 44.0
END DESCRIPTION:
XS GIS Cut Line= 3
        2373075.       13593025.        2373625.       13592825.
        2374225.       13592975.
#Sta/Elev= 30
  4423.3  394.91  4469.2  393.54    4487  392.39  4499.8  391.87  4519.1  391.96
  4555.6  390.84  4728.6  384.19  4845.6  380.73  4850.9  380.87  4870.2  379.79
  4876.2  379.09  4881.5  379.24  4901.5  377.88  4906.8  378.11  4912.8  377.37
  4932.1  376.93  4991.2   376.6  4991.5   376.1    4995   376.1  4995.2   376.6
  5049.8  376.99  5060.1  377.57  5114.2  378.48  5132.2  379.52    5225  380.23
  5245.6  381.02  5279.1  381.01  5361.6   382.4  5585.8  386.86    5627  387.98
#Mann= 4 ,-1 , 0
  4423.3    .035       0    4487     .05       0  4991.2     .05       0
  4995.2     .05       0
Bank Sta=4991.2,4995.2
XS Rating Curve= 0 ,0
Exp/Cntr=0.3,0.1

Type RM Length L Ch R = 1 ,32110   ,447,447,447
BEGIN DESCRIPTION:
JACK PUMP CREEK 43.0
END DESCRIPTION:
XS GIS Cut Line= 3
        2373325.       13593175.        2373625.       13593275.
      2374225.02     13593074.99
#Sta/Elev= 30
  4684.1  385.49  4831.7  379.83  4842.2  379.67  4894.9  377.96    4916  376.79
  4926.5  375.96  4947.6  374.95  4958.2  374.62  4995.7  374.08  4995.9  373.58
  4999.4  373.58  4999.7  374.08  5031.9  374.25  5042.5  374.78    5053  374.78
  5084.7   375.6  5137.4  375.89  5179.5  377.59  5242.8  379.33  5263.8  379.71
  5274.4  380.15  5432.5  383.35  5453.6  383.65  5506.3  384.83  5516.8  385.22
  5548.5  385.73  5569.5  386.49  5611.7  387.25  5622.2  387.69  5632.8  387.78
#Mann= 3 ,-1 , 0
  4684.1     .05       0  4995.7     .05       0  4999.7     .05       0
Bank Sta=4995.7,4999.7
XS Rating Curve= 0 ,0
Exp/Cntr=0.3,0.1

Type RM Length L Ch R = 1 ,31663   ,430,430,430
BEGIN DESCRIPTION:
JACK PUMP CREEK 42.0
END DESCRIPTION:
XS GIS Cut Line= 3
      2373374.96     13593624.99        2373675.       13593675.
      2373974.97     13593375.03
#Sta/Elev= 30
    4701  381.66  4728.9  380.49    4734  380.48    4772  378.17  4789.8   377.5
  4794.8  377.57  4822.7  376.64    4843  375.92  4850.6  375.44  4855.6  375.54
  4863.3   375.1  4893.7  374.07  4916.5   373.5  4954.5   371.3  4964.6  370.47
  4970.2   368.5  4970.5     368    4974     368  4974.2   368.5  4984.9  370.51
    4995   371.3  5008.7  371.46  5019.3  372.56  5033.5  372.68  5047.6   373.1
  5075.9  373.51  5111.2  374.45  5160.7   374.8    5189  374.82  5429.4  379.36
#Mann= 3 ,-1 , 0
    4701     .05       0  4970.2     .05       0  4974.2     .05       0
Bank Sta=4970.2,4974.2
XS Rating Curve= 0 ,0
Exp/Cntr=0.3,0.1

Type RM Length L Ch R = 1 ,31233   ,334,334,334
BEGIN DESCRIPTION:
JACK PUMP CREEK 41.0
END DESCRIPTION:
XS GIS Cut Line= 3
      2373375.02     13593875.01        2373875.       13594025.
      2374325.01     13593424.99
#Sta/Elev= 30
  4477.3  380.47  4526.9  378.51  4565.1  378.12  4581.7  377.51  4603.4  377.46
  4623.4  376.13  4631.3  375.19  4702.6  371.77  4707.8  371.98  4768.7  370.51
  4821.8  370.82  4840.1  370.61  4863.6  370.97  4894.9  370.37  4949.7  370.77
    4968  369.33  4994.7  368.19  4994.9  367.69  4998.4  367.69  4998.7  368.19
  5006.6  368.32  5012.8  370.26  5021.2  370.39  5027.4  370.91  5049.3  370.94
  5121.2  372.35    5192  372.98  5256.6  374.24  5306.6  374.78  5749.3   384.9
#Mann= 3 ,-1 , 0
  4477.3     .05       0  4994.7     .05       0  4998.7     .05       0
Bank Sta=4994.7,4998.7
XS Rating Curve= 0 ,0
Exp/Cntr=0.3,0.1

Type RM Length L Ch R = 1 ,30899   ,399,399,399
BEGIN DESCRIPTION:
JACK PUMP CREEK 40.0
END DESCRIPTION:
XS GIS Cut Line= 3
      2373349.05     13594005.18      2373901.11     13594354.13
      2374619.89     13594062.45
#Sta/Elev= 30
  4305.9  381.17  4332.2  380.46  4360.3  380.49  4368.6  379.88    4411  379.11
  4426.3  378.31  4447.5  378.29    4651  373.48  4672.1  373.38  4715.2  372.13
  4791.3  370.93  4854.5  369.39  4875.6  369.48  4881.6  369.74  4890.9  370.95
  4896.8  370.53  4904.4  367.89  4913.4   367.4  4937.5  367.23    4983   366.9
  5066.1   367.4    5071  368.05  5081.9  368.25  5108.8  368.55  5183.6  369.15
  5207.7  368.82  5241.8  369.77  5266.6  370.75  5606.8  373.79  5734.7  375.43
#Mann= 8 ,-1 , 0
  4305.9     .05       0  4791.3     .07       0  4913.4     .05       0
  4937.5    .035       0  5066.1     .12       0  5081.9     .05       0
  5108.8     .12       0  5241.8     .05       0
Bank Sta=4913.4,5066.1
XS Rating Curve= 0 ,0
Exp/Cntr=0.3,0.1

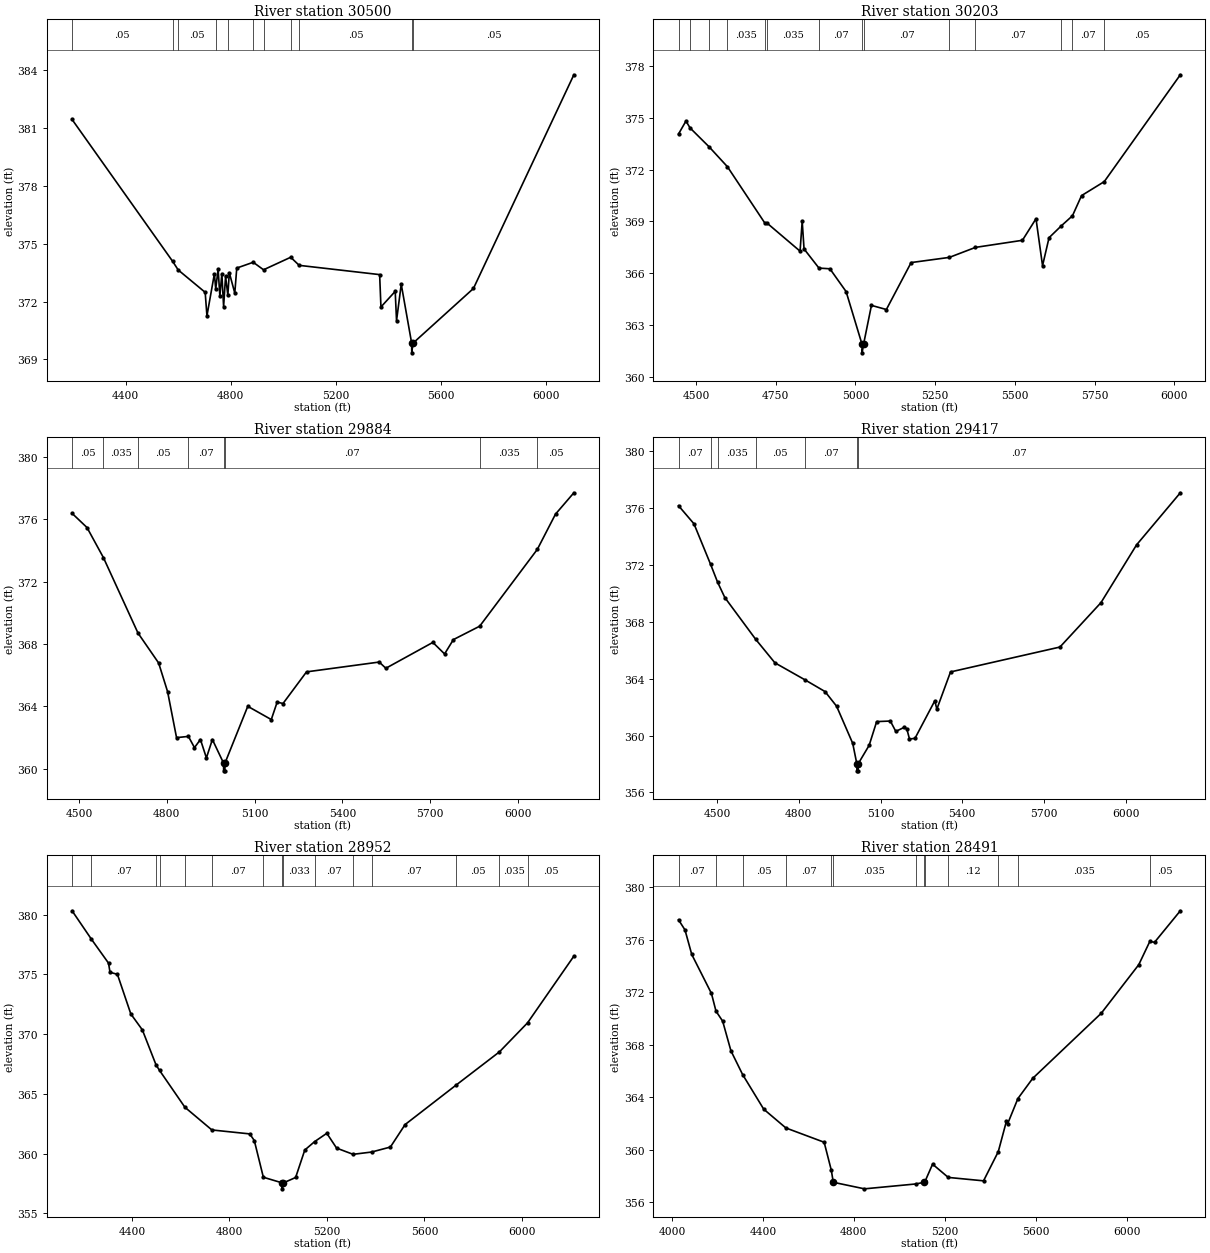
Type RM Length L Ch R = 1 ,30500   ,297,297,297
BEGIN DESCRIPTION:
A19490
END DESCRIPTION:
XS GIS Cut Line= 4
      2373317.76     13594046.81      2373901.11     13594697.88
      2374286.53     13594765.58      2374890.36     13594994.62
#Sta/Elev= 30
  4195.9  381.45  4578.9  374.09  4600.2  373.64  4702.9  372.48  4709.6  371.26
    4738  373.44  4743.1  372.66  4752.2  373.69  4758.9  372.28  4766.4  373.45
  4773.1  371.74  4780.6  373.31  4789.3  372.33  4794.8   373.5  4815.7  372.44
  4823.2  373.74  4885.9  374.04  4925.2  373.65  5028.7   374.3    5061  373.88
  5367.4   373.4  5372.4  371.72  5426.7  372.53  5431.8  371.01  5449.7   372.9
  5489.4  369.84  5489.7  369.34  5494.3  369.84  5724.7  372.68  6107.2  383.77
#Mann= 11 ,-1 , 0
  4195.9     .05       0  4578.9     .07       0  4600.2     .05       0
  4743.1    .033       0  4789.3     .05       0  4885.9    .033       0
  4925.2     .05       0  5028.7    .033       0    5061     .05       0
  5489.4     .05       0  5494.3     .05       0
Bank Sta=5489.4,5494.3
XS Rating Curve= 0 ,0
Exp/Cntr=0.3,0.1

Type RM Length L Ch R = 1 ,30203   ,319,319,319
BEGIN DESCRIPTION:
JACK PUMP CREEK 39.0
END DESCRIPTION:
XS GIS Cut Line= 3
      2373338.62     13594348.93      2373666.74     13594890.58
      2374588.58     13595078.08
#Sta/Elev= 30
  4445.1  374.07  4468.4  374.82  4481.3  374.42  4541.3  373.32  4598.6  372.17
  4715.8  368.91  4722.5  368.91  4826.3  367.28    4833  369.01  4838.8  367.41
  4885.6   366.3  4919.9  366.26  4970.7  364.94  5020.6  361.89  5020.9  361.39
  5025.5  361.89  5050.2  364.14    5097   363.9  5174.7  366.62  5294.6  366.92
  5376.6   367.5  5523.8  367.91  5566.4  369.16  5586.9  366.44  5607.3  368.06
  5645.9  368.75  5680.7  369.33  5709.3   370.5  5780.5  371.31  6019.1   377.5
#Mann= 14 ,-1 , 0
  4445.1     .05       0  4481.3    .035       0  4541.3     .05       0
  4598.6    .035       0  4715.8     .05       0  4722.5    .035       0
  4885.6     .07       0  5020.6     .05       0  5025.5     .07       0
  5294.6    .035       0  5376.6     .07       0  5645.9    .035       0
  5680.7     .07       0  5780.5     .05       0
Bank Sta=5020.6,5025.5
XS Rating Curve= 0 ,0
Exp/Cntr=0.3,0.1

Type RM Length L Ch R = 1 ,29884   ,467,467,467
BEGIN DESCRIPTION:
JACK PUMP CREEK 38.0
END DESCRIPTION:
XS GIS Cut Line= 3
      2372874.99       13594925.        2373375.       13595025.
      2374575.03       13595125.
#Sta/Elev= 30
  4476.5  376.39  4527.5  375.48  4583.6  373.55  4701.7  368.71  4772.2  366.79
  4802.8  364.95  4833.4     362  4873.9  362.08  4894.6  361.36    4915  361.88
  4935.4   360.7  4955.8  361.88  4993.9  360.37  4994.3  359.87  4998.5  359.87
  4998.9  360.37  5076.7  364.01    5157  363.16  5177.1  364.28  5197.1  364.19
  5277.4  366.22  5525.8  366.85  5548.3  366.45  5708.9  368.11    5749  367.37
  5779.1  368.29  5868.9  369.15  6065.8  374.08  6127.9  376.34  6190.6  377.71
#Mann= 8 ,-1 , 0
  4476.5     .05       0  4583.6    .035       0  4701.7     .05       0
  4873.9     .07       0  4993.9     .05       0  4998.9     .07       0
  5868.9    .035       0  6065.8     .05       0
Bank Sta=4993.9,4998.9
XS Rating Curve= 0 ,0
Exp/Cntr=0.3,0.1

Type RM Length L Ch R = 1 ,29417   ,465,465,465
BEGIN DESCRIPTION:
JACK PUMP CREEK 37.0
END DESCRIPTION:
XS GIS Cut Line= 3
        2372875.       13594975.        2373325.       13595425.
      2374524.95       13595325.
#Sta/Elev= 30
  4359.2  376.15  4415.8  374.88  4476.6  372.04  4502.4  370.78  4528.9   369.7
  4642.3  366.76  4712.7  365.11  4822.5  363.92  4896.6  363.09    4939  362.06
  4998.1  359.45  5013.1  358.02  5013.5  357.52  5017.9  357.52  5018.3  358.02
  5058.3  359.31  5085.9  360.98  5136.1  361.02  5156.1  360.29  5186.2  360.57
  5196.3  360.48  5206.3  359.76  5226.4   359.8  5299.1  362.44  5306.7  361.86
  5356.8  364.47  5758.2  366.22  5908.7  369.34  6039.2   373.4  6199.7  377.06
#Mann= 7 ,-1 , 0
  4359.2     .07       0  4476.6     .05       0  4502.4    .035       0
  4642.3     .05       0  4822.5     .07       0  5013.1     .05       0
  5018.3     .07       0
Bank Sta=5013.1,5018.3
XS Rating Curve= 0 ,0
Exp/Cntr=0.3,0.1

Type RM Length L Ch R = 1 ,28952   ,461,461,461
BEGIN DESCRIPTION:
JACK PUMP CREEK 36.0
END DESCRIPTION:
XS GIS Cut Line= 3
      2372525.04     13595525.02        2373325.       13595825.
      2374524.99       13595725.
#Sta/Elev= 30
  4154.3  380.33    4234  377.94  4303.8  375.95    4310  375.18  4340.3  375.01
  4395.4  371.69  4442.6  370.36  4498.9  367.42  4513.3  366.96  4617.2  363.88
  4727.8  361.98  4883.2  361.65  4901.9  361.09    4939  358.02    5016  357.55
  5016.4  357.05  5021.4  357.55  5071.4     358    5109   360.3  5149.1     361
  5199.3   361.7  5239.5  360.46    5307  359.94  5382.7  360.13  5460.2  360.55
  5520.4  362.43    5728  365.71  5907.6  368.52  6022.9  370.95  6212.8  376.53
#Mann= 15 ,-1 , 0
  4154.3     .05       0    4234     .07       0  4498.9    .035       0
  4513.3     .07       0  4617.2     .05       0  4727.8     .07       0
    4939    .033       0    5016    .033       0  5021.4    .033       0
  5149.1     .07       0    5307    .033       0  5382.7     .07       0
    5728     .05       0  5907.6    .035       0  6022.9     .05       0
Bank Sta=5016,5021.4
XS Rating Curve= 0 ,0
Exp/Cntr=0.3,0.1

Type RM Length L Ch R = 1 ,28491   ,207,207,207
BEGIN DESCRIPTION:
JACK PUMP CREEK 35.0
END DESCRIPTION:
XS GIS Cut Line= 3
      2372625.03     13595625.02        2373425.       13596175.
      2374624.98     13595875.01
#Sta/Elev= 30
    4029  377.51  4057.4  376.74  4087.2  374.87  4173.8   371.9  4193.8  370.55
  4223.1  369.79  4259.5  367.53  4310.9  365.72  4403.8  363.08  4501.3  361.65
  4669.7  360.56  4701.1  358.43  4709.8  357.51  4847.1  357.01  5071.8  357.38
  5110.9  357.51  5113.6  357.58  5146.7  358.89  5215.7  357.88  5370.9  357.62
  5435.7  359.84  5471.4  362.15  5476.5  361.95  5522.1  363.89  5587.3  365.43
  5888.8  370.39  6053.8  374.09  6102.4  375.86  6123.3   375.8  6236.7   378.2
#Mann= 13 ,-1 , 0
    4029     .07       0  4193.8    .035       0  4310.9     .05       0
  4501.3     .07       0  4701.1    .033       0  4709.8    .035       0
  5071.8     .12       0  5110.9    .033       0  5113.6    .033       0
  5215.7     .12       0  5435.7     .07       0  5522.1    .035       0
  6102.4     .05       0
Bank Sta=4709.8,5110.9
XS Rating Curve= 0 ,0
Exp/Cntr=0.3,0.1

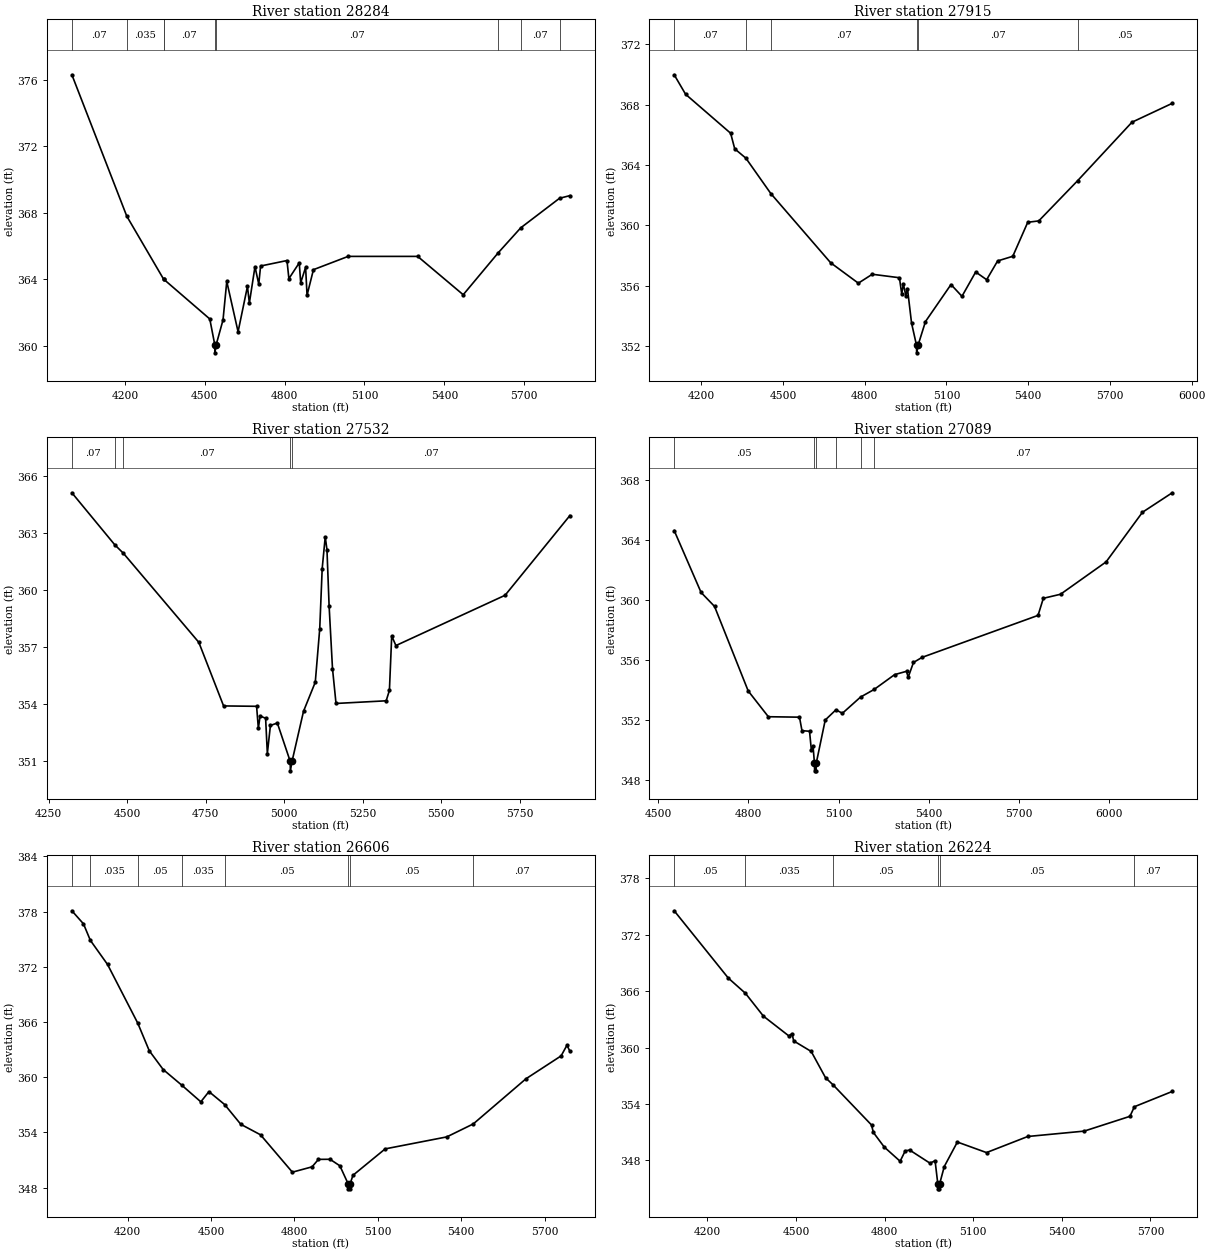
Type RM Length L Ch R = 1 ,28284   ,369,369,369
BEGIN DESCRIPTION:
A19489
END DESCRIPTION:
XS GIS Cut Line= 4
      2372614.68      13595692.7      2373182.36     13596286.42
      2373599.03     13596458.29      2374177.12     13596614.53
#Sta/Elev= 30
  4000.7  376.31    4207  367.79  4345.2     364  4345.3     364  4518.8   361.6
  4537.4  360.06  4537.8  359.56    4543  360.06  4568.5  361.54  4582.6  363.86
  4625.1  360.83  4660.3  363.56  4667.5  362.56  4688.6  364.75  4702.8   363.7
  4709.7  364.79  4808.8  365.12    4816  364.03  4854.9  364.98  4860.3  363.78
  4878.8  364.71  4884.2  363.03  4908.2  364.57  5038.6  365.37  5299.8  365.37
  5470.9  363.06  5602.6  365.59    5687  367.09  5832.7  368.87  5871.7  369.03
#Mann= 9 ,-1 , 0
  4000.7     .07       0    4207    .035       0  4345.2     .05       0
  4345.3     .07       0  4537.4     .05       0    4543     .07       0
  5602.6    .035       0    5687     .07       0  5832.7     .05       0
Bank Sta=4537.4,4543
XS Rating Curve= 0 ,0
Exp/Cntr=0.3,0.1

Type RM Length L Ch R = 1 ,27915   ,383,383,383
BEGIN DESCRIPTION:
JACK PUMP CREEK 34.0
END DESCRIPTION:
XS GIS Cut Line= 3
      2372427.17     13596135.39       2373208.4     13596656.21
      2374091.88     13596754.95
#Sta/Elev= 30
  4100.7  369.97  4142.6  368.68  4307.9   366.1  4322.9  365.07  4363.9  364.45
  4455.4  362.11    4675  357.53  4776.6  356.18  4827.7  356.77  4927.4  356.54
  4935.8  355.47  4941.8  356.12  4950.9  355.36  4956.9  355.82  4971.9  353.54
  4990.1  352.07  4990.6  351.57  4995.7  352.07    5023  353.64  5116.7  356.09
  5156.9  355.31  5207.3  356.92  5247.5  356.41  5287.8  357.65  5343.5  357.96
  5398.4  360.21  5438.8   360.3  5581.4  362.96  5780.8  366.83  5928.6  368.08
#Mann= 6 ,-1 , 0
  4100.7     .07       0  4363.9    .035       0  4455.4     .07       0
  4990.1     .05       0  4995.7     .07       0  5581.4     .05       0
Bank Sta=4990.1,4995.7
XS Rating Curve= 0 ,0
Exp/Cntr=0.3,0.1

Type RM Length L Ch R = 1 ,27532   ,443,443,443
BEGIN DESCRIPTION:
A19488
END DESCRIPTION:
XS GIS Cut Line= 4
      2372505.27      13596411.4      2372812.57     13596843.71
      2373166.74     13597005.17      2373811.29     13596838.83
#Sta/Elev= 30
  4324.2  365.13  4460.7  362.39  4488.3  361.94  4728.3  357.25  4807.1   353.9
  4912.2  353.88  4917.8  352.72  4923.3  353.37  4940.9  353.25  4946.4  351.39
  4956.2  352.87  4978.2     353  5019.2  350.98  5019.7  350.48    5025  350.98
  5061.6  353.62    5099  355.15  5113.2  357.97    5121  361.14  5130.7  362.81
  5136.2  362.13    5143  359.18  5153.8  355.87    5165  354.03  5324.7  354.17
    5335  354.72  5342.3  357.59  5355.6  357.08  5703.2  359.73  5909.5  363.93
#Mann= 5 ,-1 , 0
  4324.2     .07       0  4460.7    .035       0  4488.3     .07       0
  5019.2     .05       0    5025     .07       0
Bank Sta=5019.2,5025
XS Rating Curve= 0 ,0
Exp/Cntr=0.3,0.1

Type RM Length L Ch R = 1 ,27089   ,483,483,483
BEGIN DESCRIPTION:
JACK PUMP CREEK 33.0
END DESCRIPTION:
XS GIS Cut Line= 3
      2372475.01     13597125.01        2372875.       13597325.
        2373975.       13596825.
#Sta/Elev= 30
  4553.3  364.64  4642.7  360.51  4687.4  359.58  4799.3  353.94  4866.3  352.22
  4969.8  352.19  4978.1  351.29  5003.2  351.25  5009.3  349.99  5014.8  350.27
  5019.6  349.11    5020  348.61  5024.9  348.61  5025.4  349.11  5055.4     352
  5090.9  352.68  5112.5  352.45  5172.7  353.53    5218  354.04  5286.1  355.03
  5325.6  355.25  5331.1  354.85  5348.7  355.84  5377.3  356.18  5762.8  358.98
  5780.4  360.12  5837.5  360.39  5989.1  362.55  6109.9  365.86  6208.8  367.16
#Mann= 6 ,-1 , 0
  4553.3     .05       0  5019.6     .05       0  5025.4     .05       0
  5090.9     .07       0  5172.7     .05       0    5218     .07       0
Bank Sta=5019.6,5025.4
XS Rating Curve= 0 ,0
Exp/Cntr=0.3,0.1

Type RM Length L Ch R = 1 ,26606   ,382,382,382
BEGIN DESCRIPTION:
JACK PUMP CREEK 32.0
END DESCRIPTION:
XS GIS Cut Line= 3
      2372074.96     13597174.97        2372875.       13597775.
      2373624.98     13597525.01
#Sta/Elev= 30
  3999.9  378.08  4041.6  376.66  4066.3  374.87  4128.1  372.25  4236.7  365.88
  4278.1  362.88  4328.1  360.84  4396.1  359.11  4463.5  357.33  4492.7  358.44
    4549  357.04  4607.2  354.89  4678.1  353.75  4792.7  349.69  4863.5  350.27
  4886.4  351.08  4928.1  351.09  4963.5  350.38  4993.9  348.38  4994.4  347.88
  4999.3  347.88  4999.8  348.38  5010.5  349.35  5126.4  352.22  5347.8  353.52
  5443.1  354.93  5632.4  359.83  5758.9  362.32    5780  363.48  5790.5  362.82
#Mann= 8 ,-1 , 0
  3999.9     .05       0  4066.3    .035       0  4236.7     .05       0
  4396.1    .035       0    4549     .05       0  4993.9     .05       0
  4999.8     .05       0  5443.1     .07       0
Bank Sta=4993.9,4999.8
XS Rating Curve= 0 ,0
Exp/Cntr=0.3,0.1

Type RM Length L Ch R = 1 ,26224   ,448,448,448
BEGIN DESCRIPTION:
A19487
END DESCRIPTION:
XS GIS Cut Line= 3
      2371854.27     13597760.39      2372849.03     13598156.21
      2373461.85     13598213.34
#Sta/Elev= 30
  4087.6  374.52  4270.9  367.37  4328.7  365.76  4389.7  363.33  4475.8  361.23
  4486.6  361.47  4492.1   360.7  4551.5  359.58    4600  356.79  4625.3  356.04
  4755.7  351.77  4761.9  350.98  4798.7  349.43  4852.5  347.92  4869.8  349.02
  4884.8  349.11  4953.4  347.72  4970.9  347.97  4980.2  345.49  4980.7  344.99
  4985.6  344.99  4986.1  345.49    5002  347.36  5046.3  349.96    5145  348.84
  5284.7  350.55  5475.6  351.12  5630.6  352.69  5645.7  353.71  5773.7  355.33
#Mann= 6 ,-1 , 0
  4087.6     .05       0  4328.7    .035       0  4625.3     .05       0
  4980.2     .05       0  4986.1     .05       0  5645.7     .07       0
Bank Sta=4980.2,4986.1
XS Rating Curve= 0 ,0
Exp/Cntr=0.3,0.1

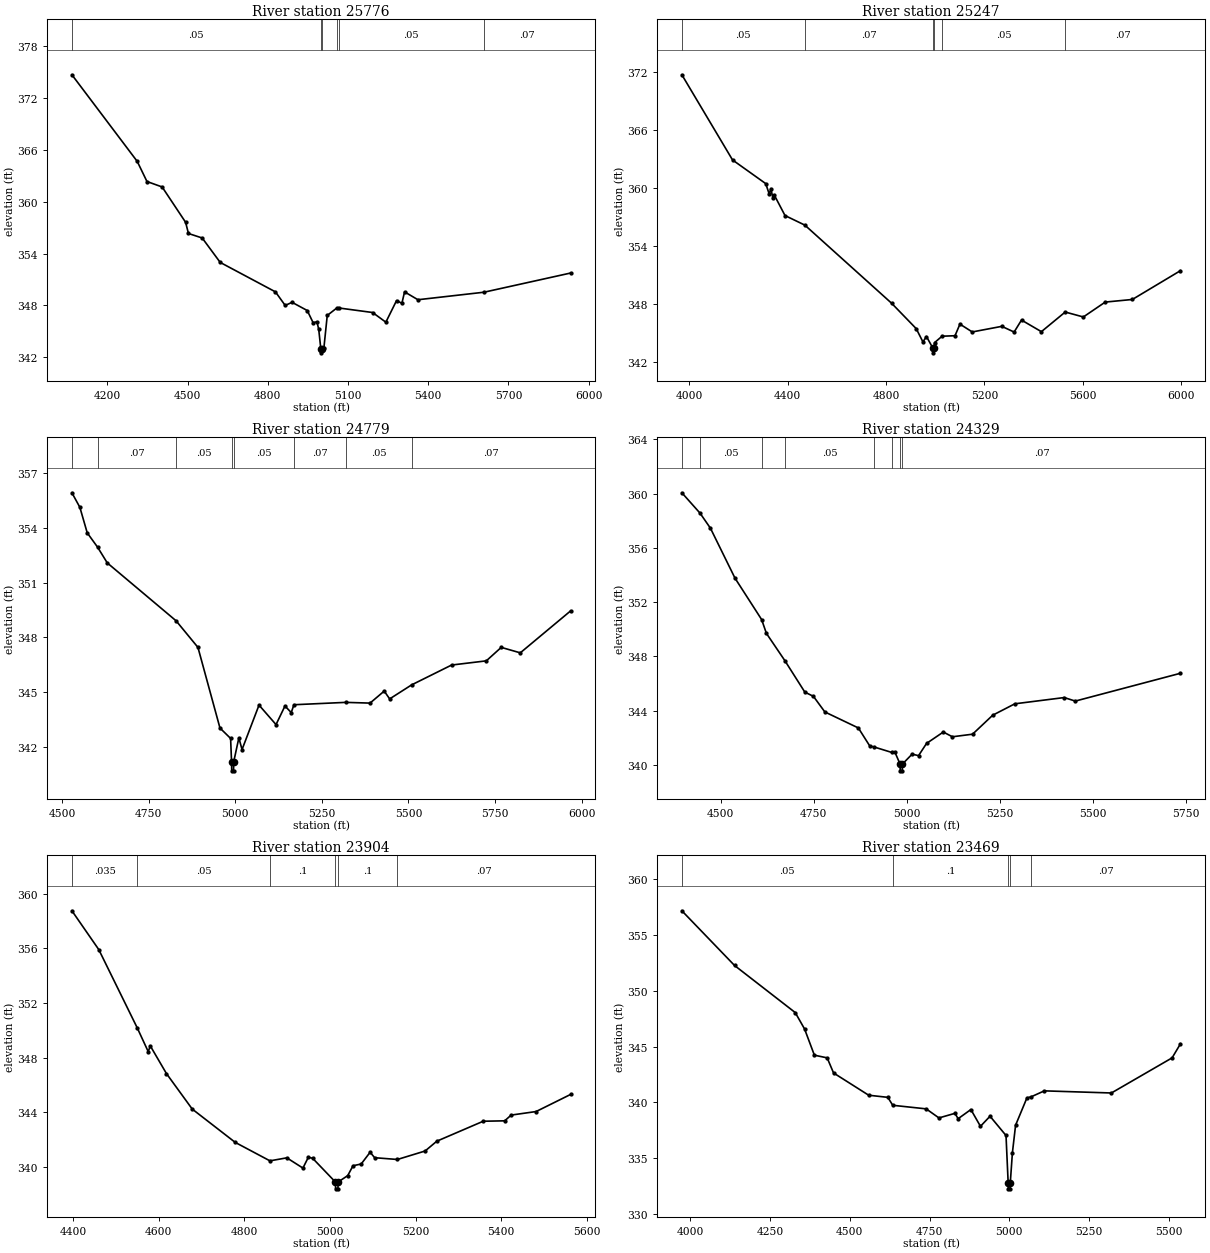
Type RM Length L Ch R = 1 ,25776   ,529,529,529
BEGIN DESCRIPTION:
A19486
END DESCRIPTION:
XS GIS Cut Line= 3
      2371713.58     13598197.87       2372770.9     13598567.67
      2373515.68     13598567.67
#Sta/Elev= 30
  4067.2  374.71  4311.5  364.68  4347.9  362.35  4404.6  361.72  4492.4  357.63
  4503.1  356.33  4554.5  355.81  4621.9  352.98  4828.5  349.57  4864.9     348
  4890.6  348.36  4947.4  347.41  4969.2  346.01  4983.7   346.1  4990.4  345.22
    4998  343.01  4998.5  342.51    5004  343.01  5009.5  343.03  5022.2  346.84
  5058.7  347.72  5064.4  347.71  5191.9  347.18  5241.4  346.06  5281.4  348.56
  5301.4  348.25  5311.4  349.57  5361.4  348.66  5608.4  349.53  5932.1  351.75
#Mann= 6 ,-1 , 0
  4067.2     .05       0    4998     .05       0    5004     .05       0
  5058.7     .07       0  5064.4     .05       0  5608.4     .07       0
Bank Sta=4998,5004
XS Rating Curve= 0 ,0
Exp/Cntr=0.3,0.1

Type RM Length L Ch R = 1 ,25247   ,468,468,468
BEGIN DESCRIPTION:
JACK PUMP CREEK 31.0
END DESCRIPTION:
XS GIS Cut Line= 3
      2371725.03     13598325.03        2372525.       13598975.
      2373520.46     13598916.65
#Sta/Elev= 30
  3969.3  371.72  4175.4  362.91  4310.5  360.46  4324.8  359.36  4331.3  359.95
  4339.2  358.99  4345.6  359.26  4388.8  357.16  4469.5  356.17  4821.9   348.1
  4922.5  345.46  4949.7  344.09  4964.1  344.65  4989.8  343.46  4990.3  342.96
  4995.9  343.46  4996.8  344.01  5027.4  344.68  5080.2  344.73  5100.2  345.93
  5150.3  345.12  5270.5   345.7  5320.6  345.11  5350.6  346.35  5431.5  345.15
  5528.4  347.18  5602.1  346.67  5691.2  348.21  5801.4  348.48  5997.2  351.46
#Mann= 6 ,-1 , 0
  3969.3     .05       0  4469.5     .07       0  4989.8     .05       0
  4995.9     .07       0  5027.4     .05       0  5528.4     .07       0
Bank Sta=4989.8,4995.9
XS Rating Curve= 0 ,0
Exp/Cntr=0.3,0.1

Type RM Length L Ch R = 1 ,24779   ,450,450,450
BEGIN DESCRIPTION:
JACK PUMP CREEK 30.0
END DESCRIPTION:
XS GIS Cut Line= 3
      2372175.03     13599674.98        2372575.       13599425.
      2373520.42     13599218.81
#Sta/Elev= 30
  4528.6  355.94  4551.6  355.14  4572.8  353.74  4602.8  352.95  4630.6  352.09
  4829.3  348.91  4892.4  347.45    4956  343.02  4986.7  342.45  4989.4  341.17
  4989.9  340.67  4995.2  340.67  4995.7  341.17  5010.5  342.48  5019.7  341.84
  5068.7  344.28  5117.8  343.21  5143.6  344.23  5161.7  343.87  5169.5   344.3
    5319  344.43  5389.2  344.39  5430.1  345.05  5445.8  344.62  5509.2  345.39
  5624.6  346.48  5724.8  346.71  5767.9  347.45  5822.9  347.15  5967.9  349.45
#Mann= 8 ,-1 , 0
  4528.6     .05       0  4602.8     .07       0  4829.3     .05       0
  4989.4     .05       0  4995.7     .05       0  5169.5     .07       0
    5319     .05       0  5509.2     .07       0
Bank Sta=4989.4,4995.7
XS Rating Curve= 0 ,0
Exp/Cntr=0.3,0.1

Type RM Length L Ch R = 1 ,24329   ,425,425,425
BEGIN DESCRIPTION:
JACK PUMP CREEK 29.0
END DESCRIPTION:
XS GIS Cut Line= 3
      2372275.04     13600024.98        2372825.       13599775.
      2373510.22     13599505.27
#Sta/Elev= 30
  4395.9  360.06  4444.7  358.56  4472.7  357.45  4538.7  353.77  4610.3  350.72
  4623.2   349.7  4672.8  347.69  4726.5  345.37  4749.6  345.06  4780.3  343.91
  4870.4  342.73  4901.1   341.4  4912.4  341.33  4959.8  340.93  4968.1  340.98
  4982.5  340.07    4983  339.57  4988.4  339.57  4988.9  340.07  5014.9   340.8
  5032.2  340.69  5053.7  341.59  5098.8  342.43  5123.2  342.08  5177.4  342.27
  5231.6  343.67  5291.1  344.51  5423.8  344.97  5453.6  344.71  5736.4  346.76
#Mann= 8 ,-1 , 0
  4395.9    .035       0  4444.7     .05       0  4610.3     .07       0
  4672.8     .05       0  4912.4      .1       0  4959.8     .07       0
  4982.5     .05       0  4988.9     .07       0
Bank Sta=4982.5,4988.9
XS Rating Curve= 0 ,0
Exp/Cntr=0.3,0.1

Type RM Length L Ch R = 1 ,23904   ,435,435,435
BEGIN DESCRIPTION:
JACK PUMP CREEK 28.0
END DESCRIPTION:
XS GIS Cut Line= 3
      2372325.05       13600075.        2372925.       13600125.
      2373461.84     13599958.84
#Sta/Elev= 30
  4397.7  358.75  4460.4  355.91  4550.3  350.17  4575.8  348.44  4580.8  348.85
  4618.4  346.83  4678.6  344.23    4779  341.79    4860  340.44  4899.4  340.66
    4937  339.91  4949.6   340.7  4959.6  340.63  5012.8  338.89  5013.3  338.39
  5018.7  338.39  5019.2  338.89  5041.6  339.36  5053.9  340.08    5073  340.21
  5093.9  341.07  5104.4  340.67  5157.5  340.54  5222.2  341.16  5249.6  341.88
  5357.9  343.34    5408  343.37  5423.1  343.79  5481.3  344.05  5561.7   345.3
#Mann= 6 ,-1 , 0
  4397.7    .035       0  4550.3     .05       0    4860      .1       0
  5012.8     .05       0  5019.2      .1       0  5157.5     .07       0
Bank Sta=5012.8,5019.2
XS Rating Curve= 0 ,0
Exp/Cntr=0.3,0.1

Type RM Length L Ch R = 1 ,23469   ,401,401,401
BEGIN DESCRIPTION:
A19485
END DESCRIPTION:
XS GIS Cut Line= 2
      2372000.06     13600546.83      2373561.29     13600479.18
#Sta/Elev= 30
  3973.9  357.14    4139  352.25  4329.2  348.04  4358.5  346.57  4389.2  344.23
  4429.3  343.99  4449.3  342.64  4559.4  340.65  4619.4  340.46  4634.8  339.75
  4739.6  339.43  4779.6  338.62  4829.7  339.03  4839.7  338.55  4879.7  339.37
  4909.7  337.87  4939.7  338.77  4989.8  337.05  4996.6  332.78  4997.1  332.28
  5002.6  332.28  5003.1  332.78  5009.8   335.5  5019.8  337.97  5055.3  340.41
  5068.7  340.51  5109.9  341.04  5320.1  340.85  5510.3  343.99  5536.6  345.25
#Mann= 5 ,-1 , 0
  3973.9     .05       0  4634.8      .1       0  4996.6     .05       0
  5003.1      .1       0  5068.7     .07       0
Bank Sta=4996.6,5003.1
XS Rating Curve= 0 ,0
Exp/Cntr=0.3,0.1