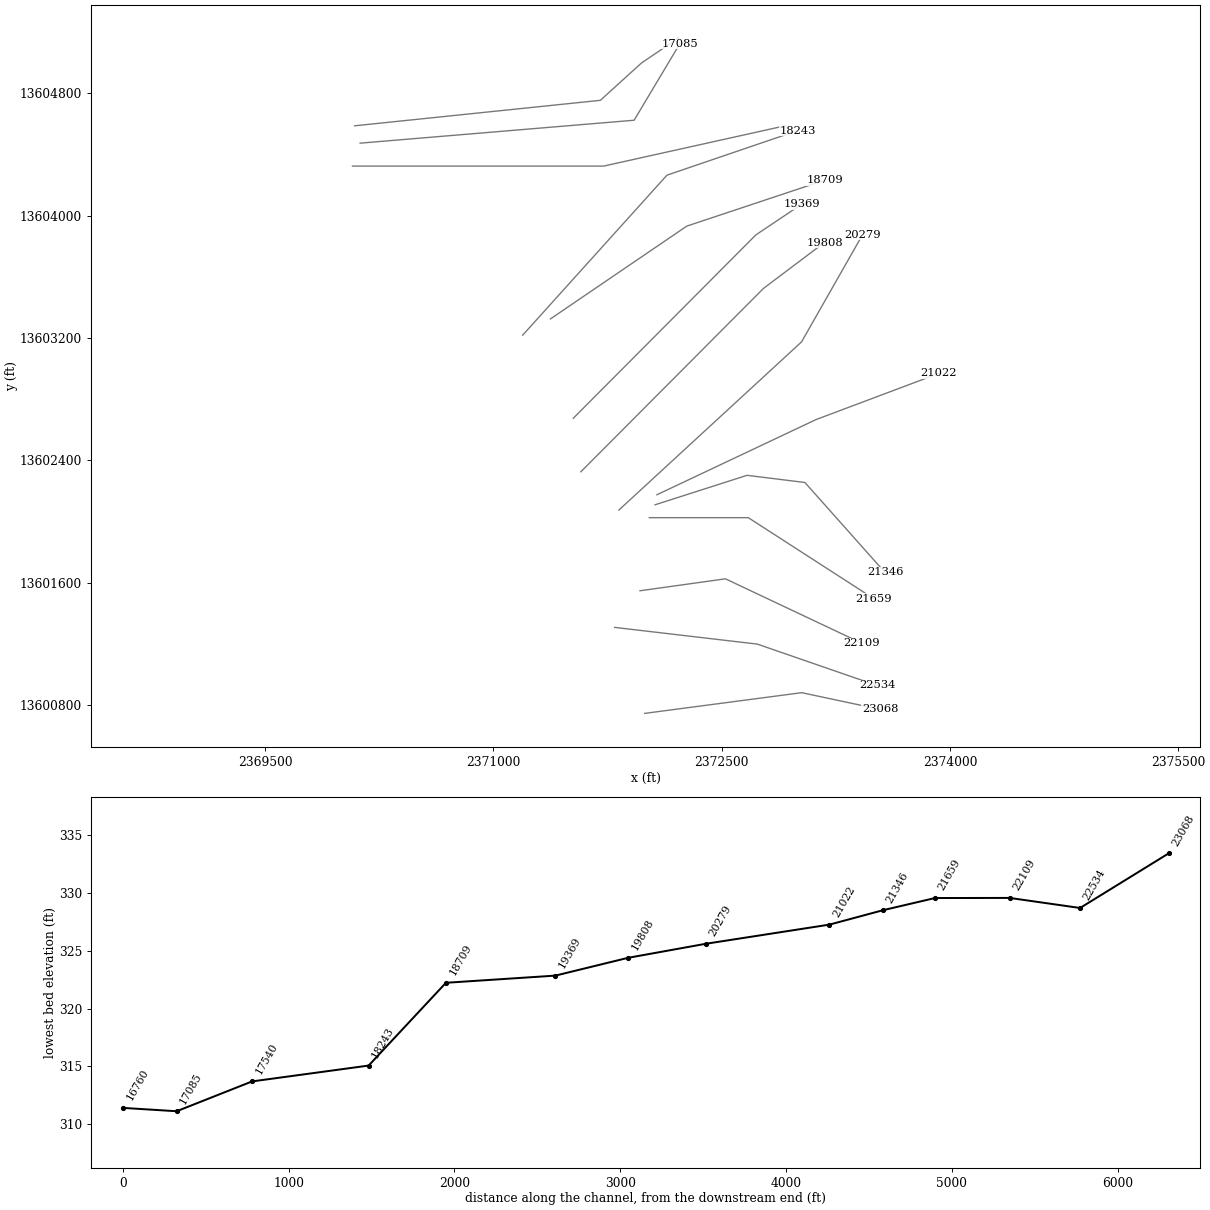
HEC-RAS study JACK PUMP CREEK.prj: JACK PUMP CREEK Base Level Engineering

--- JACK PUMP CREEK.g01 (geometry) --- (continued)

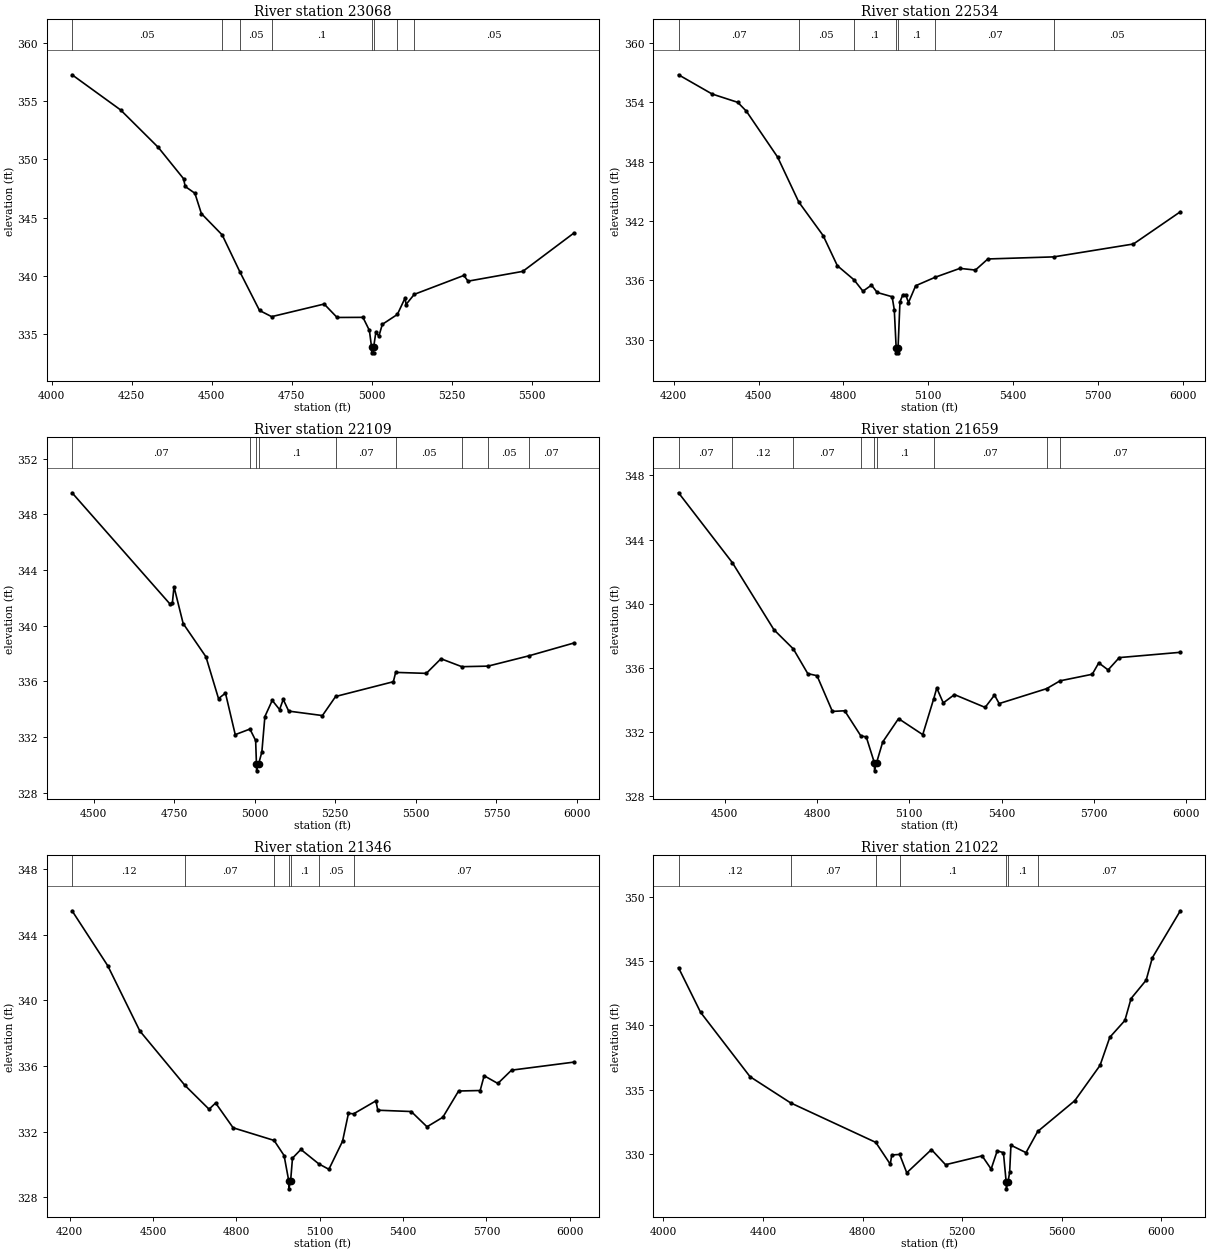
Type RM Length L Ch R = 1 ,23068   ,534,534,534
BEGIN DESCRIPTION:
A19484
END DESCRIPTION:
XS GIS Cut Line= 3
      2371994.84     13600744.75      2373026.11     13600880.17
      2373540.83     13600770.98
#Sta/Elev= 30
  4063.9  357.24  4215.3  354.23    4333  351.02  4411.8  348.34  4417.1  347.67
  4447.3  347.09  4467.5  345.35  4532.5  343.52    4588  340.34    4649  337.05
  4686.9  336.52  4850.8   337.6  4891.1  336.45  4971.8  336.46    4992  335.34
  4998.7  333.92  4999.2  333.42  5004.8  333.42  5005.3  333.92  5012.1  335.17
  5021.6  334.85  5032.3  335.86  5079.3  336.71  5103.4  338.12  5106.4  337.56
    5132  338.43  5286.9  340.05  5299.9  339.56  5470.9   340.4  5630.2  343.68
#Mann= 8 ,-1 , 0
  4063.9     .05       0  4532.5     .07       0    4588     .05       0
  4686.9      .1       0  4998.7     .05       0  5005.3      .1       0
  5079.3     .07       0    5132     .05       0
Bank Sta=4998.7,5005.3
XS Rating Curve= 0 ,0
Exp/Cntr=0.3,0.1

Type RM Length L Ch R = 1 ,22534   ,425,425,425
BEGIN DESCRIPTION:
A19483
END DESCRIPTION:
XS GIS Cut Line= 3
      2371796.99     13601307.25      2372734.45     13601197.88
      2373520.43     13600927.21
#Sta/Elev= 30
  4216.8  356.75  4335.6  354.81  4426.2  353.97  4456.7  353.08  4567.2  348.45
    4642  343.92  4728.3  340.53  4778.6  337.49  4837.4  336.07  4869.2  334.92
  4899.4  335.53  4919.5  334.79  4972.3  334.36    4980  333.06  4986.7   329.2
  4987.2   328.7  4992.9   328.7  4993.4   329.2  5000.1  333.84  5010.2  334.56
  5020.2  334.57  5030.3  333.77  5055.7  335.47  5125.1  336.33  5212.2  337.22
    5267  337.05  5311.1  338.17  5544.3  338.38    5826  339.68  5991.9  342.93
#Mann= 7 ,-1 , 0
  4216.8     .07       0    4642     .05       0  4837.4      .1       0
  4986.7     .05       0  4993.4      .1       0  5125.1     .07       0
  5544.3     .05       0
Bank Sta=4986.7,4993.4
XS Rating Curve= 0 ,0
Exp/Cntr=0.3,0.1

Type RM Length L Ch R = 1 ,22109   ,450,450,450
BEGIN DESCRIPTION:
JACK PUMP CREEK 27.0
END DESCRIPTION:
XS GIS Cut Line= 3
      2371963.58     13601546.83        2372525.       13601625.
      2373420.99     13601203.54
#Sta/Elev= 30
  4433.2  349.54  4737.5  341.54  4744.4  341.63  4749.5  342.79  4777.9  340.15
  4848.6  337.76  4887.6  334.76  4909.2  335.15  4939.5  332.17  4985.1  332.57
  5002.8  331.75  5005.3  330.07  5005.8  329.57  5012.1  330.07  5022.1  330.93
  5031.5  333.47  5054.3  334.63  5077.1  333.97  5088.4   334.7  5105.4  333.86
    5210  333.54    5251  334.91  5430.1  335.97  5437.3  336.64  5532.3  336.57
  5577.9  337.62  5642.6  337.05  5723.8  337.09  5850.7  337.83  5990.2  338.75
#Mann= 9 ,-1 , 0
  4433.2     .07       0  4985.1      .1       0  5005.3     .05       0
  5012.1      .1       0    5251     .07       0  5437.3     .05       0
  5642.6     .07       0  5723.8     .05       0  5850.7     .07       0
Bank Sta=5005.3,5012.1
XS Rating Curve= 0 ,0
Exp/Cntr=0.3,0.1

Type RM Length L Ch R = 1 ,21659   ,313,313,313
BEGIN DESCRIPTION:
JACK PUMP CREEK 26.0
END DESCRIPTION:
XS GIS Cut Line= 3
      2372025.02       13602025.        2372675.       13602025.
      2373500.03     13601494.77
#Sta/Elev= 30
    4350  346.92  4525.2  342.55    4660  338.37  4723.1  337.17    4770  335.63
    4800   335.5    4850  333.27    4890  333.31  4942.5  331.74    4960  331.68
  4986.5  330.06    4987  329.56  4993.4  330.06  5013.5  331.36    5065  332.82
  5143.6  331.82    5179  334.04  5189.2  334.73  5210.3   333.8  5246.7  334.32
  5346.4  333.52  5376.8  334.29    5392  333.76  5546.1  334.69    5590  335.18
  5694.5  335.59  5715.6   336.3    5746  335.86  5782.3  336.63  5980.7  336.96
#Mann= 9 ,-1 , 0
    4350     .07       0  4525.2     .12       0  4723.1     .07       0
  4942.5      .1       0  4986.5     .05       0  4993.4      .1       0
    5179     .07       0  5546.1     .05       0    5590     .07       0
Bank Sta=4986.5,4993.4
XS Rating Curve= 0 ,0
Exp/Cntr=0.3,0.1

Type RM Length L Ch R = 1 ,21346   ,324,324,324
BEGIN DESCRIPTION:
A19482
END DESCRIPTION:
XS GIS Cut Line= 4
      2372062.61     13602109.35      2372666.74     13602302.04
      2373046.95     13602255.17      2373573.01      13601666.6
#Sta/Elev= 30
  4208.2  345.45  4336.7   342.1  4452.1  338.13  4614.2  334.82  4701.4  333.36
    4725  333.74    4788  332.23  4935.5  331.46  4971.5  330.54  4988.2  329.01
  4988.7  328.51  4995.1  329.01  5001.8  330.38    5032  330.91  5096.6  330.03
  5132.8   329.7    5182  331.41  5203.3  333.11  5221.8  333.08  5302.2  333.87
  5308.9   333.3  5429.3  333.22  5486.1  332.29    5543  332.87  5599.8  334.47
  5677.5   334.5  5691.8   335.4  5741.1  334.93  5790.4  335.74  6014.8  336.23
#Mann= 7 ,-1 , 0
  4208.2     .12       0  4614.2     .07       0  4935.5      .1       0
  4988.2     .05       0  4995.1      .1       0  5096.6     .05       0
  5221.8     .07       0
Bank Sta=4988.2,4995.1
XS Rating Curve= 0 ,0
Exp/Cntr=0.3,0.1

Type RM Length L Ch R = 1 ,21022   ,743,743,743
BEGIN DESCRIPTION:
JACK PUMP CREEK 25.0
END DESCRIPTION:
XS GIS Cut Line= 3
      2372074.96     13602174.98      2373119.86     13602666.63
       2373927.2     13602968.73
#Sta/Elev= 30
  4060.6  344.49  4149.1  341.02    4348     336    4511  333.96  4853.4  330.88
  4911.6  329.18  4917.6   329.9  4949.3  329.94  4977.9  328.51  5077.1  330.32
  5133.8  329.14  5280.8  329.83    5317   328.8  5341.4  330.22  5366.4  330.08
  5377.6  327.76  5378.1  327.26  5384.5  327.76  5391.3  328.54  5396.6  330.66
  5457.2  330.08  5504.1  331.73  5653.2  334.13  5754.7  336.88  5793.9  339.07
  5854.5  340.38  5879.4  342.09    5940  343.52  5964.9  345.27  6077.4  348.93
#Mann= 7 ,-1 , 0
  4060.6     .12       0    4511     .07       0  4853.4     .05       0
  4949.3      .1       0  5377.6     .05       0  5384.5      .1       0
  5504.1     .07       0
Bank Sta=5377.6,5384.5
XS Rating Curve= 0 ,0
Exp/Cntr=0.3,0.1

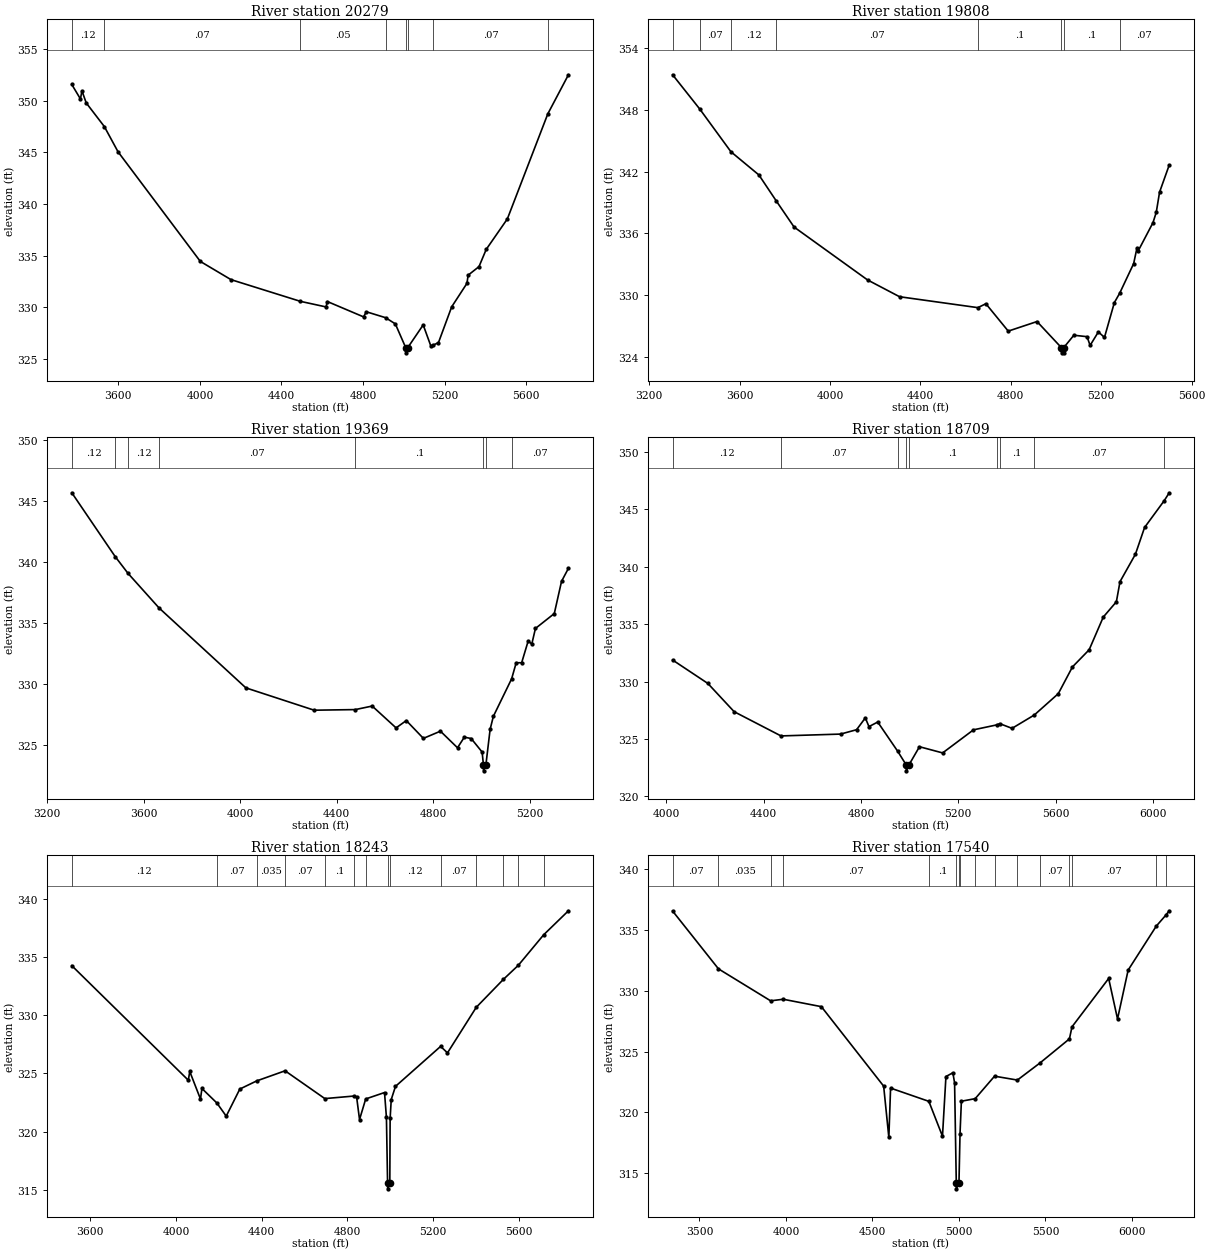
Type RM Length L Ch R = 1 ,20279   ,471,471,471
BEGIN DESCRIPTION:
JACK PUMP CREEK 24.0
END DESCRIPTION:
XS GIS Cut Line= 3
      2371824.98     13602074.98        2373025.       13603175.
      2373424.98     13603874.97
#Sta/Elev= 30
  3372.3  351.56  3414.6  350.16    3422  350.95  3442.9  349.78  3531.8  347.49
  3598.9  345.05  4002.2  334.45  4152.4  332.69  4492.6  330.59  4618.2  330.05
    4625  330.57    4802  329.09  4816.1  329.58  4910.1  329.01    4958  328.41
  5008.9  326.11  5009.4  325.61  5018.8  326.11  5094.5  328.31  5131.9  326.28
    5144  326.36  5169.4   326.6  5234.2  330.06    5309  332.33  5314.8  333.12
  5368.1  333.95  5403.3  335.61    5507  338.56  5705.3  348.72  5806.4   352.5
#Mann= 8 ,-1 , 0
  3372.3     .12       0  3531.8     .07       0  4492.6     .05       0
  4910.1      .1       0  5008.9     .05       0  5018.8      .1       0
    5144     .07       0  5705.3    .035       0
Bank Sta=5008.9,5018.8
XS Rating Curve= 0 ,0
Exp/Cntr=0.3,0.1

Type RM Length L Ch R = 1 ,19808   ,439,439,439
BEGIN DESCRIPTION:
JACK PUMP CREEK 23.0
END DESCRIPTION:
XS GIS Cut Line= 3
      2371575.02     13602325.02        2372775.       13603525.
      2373174.98     13603824.99
#Sta/Elev= 30
  3303.7   351.4  3424.3  348.06  3561.9  343.92  3685.5  341.67  3762.8  339.13
  3841.1  336.61  4166.3  331.47  4307.8  329.84  4654.1  328.78  4689.6  329.16
  4788.6   326.5  4915.9  327.43  5023.9  324.89  5024.4  324.39  5033.3  324.39
  5033.8  324.89  5078.8   326.1  5137.2  325.96  5150.7  325.11  5187.2  326.42
  5214.3  325.89    5258  329.27  5281.3  330.17  5343.4  333.06    5358  334.58
  5364.3  334.33  5428.8  337.03  5443.4  338.04    5458     340  5500.7  342.63
#Mann= 8 ,-1 , 0
  3303.7     .12       0  3424.3     .07       0  3561.9     .12       0
  3762.8     .07       0  4654.1      .1       0  5023.9     .05       0
  5033.8      .1       0  5281.3     .07       0
Bank Sta=5023.9,5033.8
XS Rating Curve= 0 ,0
Exp/Cntr=0.3,0.1

Type RM Length L Ch R = 1 ,19369   ,660,660,660
BEGIN DESCRIPTION:
JACK PUMP CREEK 22.0
END DESCRIPTION:
XS GIS Cut Line= 3
      2371525.03     13602675.03        2372725.       13603875.
      2373025.02     13604075.01
#Sta/Elev= 30
  3302.7  345.64  3482.4  340.41  3535.8  339.03  3664.2   336.2  4023.9  329.65
  4306.8  327.82  4477.2  327.87  4547.2  328.16  4646.2  326.37  4688.6  326.97
  4759.3  325.51    4830   326.1  4900.7  324.74    4929  325.61  4957.3   325.5
  5002.7  324.39  5008.1  323.35  5008.6  322.85  5018.4  323.35  5035.8  326.25
  5049.3  327.32  5124.9  330.39  5143.9  331.71  5166.5  331.71  5193.5  333.49
  5208.5  333.24  5223.6  334.52  5301.7  335.74  5331.7  338.38  5360.3  339.45
#Mann= 8 ,-1 , 0
  3302.7     .12       0  3482.4     .07       0  3535.8     .12       0
  3664.2     .07       0  4477.2      .1       0  5008.1     .05       0
  5018.4      .1       0  5124.9     .07       0
Bank Sta=5008.1,5018.4
XS Rating Curve= 0 ,0
Exp/Cntr=0.3,0.1

Type RM Length L Ch R = 1 ,18709   ,466,466,466
BEGIN DESCRIPTION:
JACK PUMP CREEK 21.0
END DESCRIPTION:
XS GIS Cut Line= 3
      2371375.04     13603325.03       2372270.9     13603932.25
      2373181.15     13604233.93
#Sta/Elev= 30
  4026.1  331.88    4171  329.84  4279.1  327.38  4471.6  325.27  4716.5  325.43
  4782.3  325.81  4818.3  326.84  4833.2  326.08  4869.2  326.48  4950.8  323.95
  4986.7  322.73  4987.2  322.23  4997.1  322.73  5040.8  324.33    5136  323.79
  5262.8   325.8  5360.5  326.24  5370.6  326.34  5421.3  325.93  5512.7  327.09
  5611.4  328.95  5669.6  331.28  5738.2  332.77  5796.3  335.62  5850.1  336.95
    5865   338.7  5928.4  341.09    5966  343.42    6047  345.76  6067.3  346.44
#Mann= 9 ,-1 , 0
  4026.1     .12       0  4471.6     .07       0  4950.8      .1       0
  4986.7     .05       0  4997.1      .1       0  5360.5     .12       0
  5370.6      .1       0  5512.7     .07       0    6047    .035       0
Bank Sta=4986.7,4997.1
XS Rating Curve= 0 ,0
Exp/Cntr=0.3,0.1

Type RM Length L Ch R = 1 ,18243   ,703,703,703
BEGIN DESCRIPTION:
A19481
END DESCRIPTION:
XS GIS Cut Line= 3
      2371192.77      13603218.7       2372140.7     13604265.58
      2373000.07     13604557.25
#Sta/Elev= 30
  3513.3  334.26  4057.5  324.41  4064.3  325.16  4114.3  322.79  4121.1   323.7
    4191  322.45  4234.6  321.32  4298.1  323.65  4376.8  324.35  4509.5  325.22
  4695.2  322.83  4831.8  323.05  4843.6  322.98  4857.3  321.03  4886.1   322.8
    4974  323.35  4982.9  321.22  4988.3  315.57  4988.8  315.07  4998.7  315.57
  5000.2  321.12  5005.4  322.75  5025.2  323.88  5236.1  327.32  5268.1  326.76
  5402.6  330.68  5529.2  333.08  5598.9  334.29  5717.7  336.92  5833.1  338.98
#Mann= 14 ,-1 , 0
  3513.3     .12       0    4191     .07       0  4376.8    .035       0
  4509.5     .07       0  4695.2      .1       0  4831.8     .07       0
  4886.1     .12       0  4988.3     .05       0  4998.7     .12       0
  5236.1     .07       0  5402.6     .12       0  5529.2     .07       0
  5598.9     .12       0  5717.7     .07       0
Bank Sta=4988.3,4998.7
XS Rating Curve= 0 ,0
Exp/Cntr=0.3,0.1

Type RM Length L Ch R = 1 ,17540   ,455,455,455
BEGIN DESCRIPTION:
JACK PUMP CREEK 20.0
END DESCRIPTION:
XS GIS Cut Line= 3
      2370074.95       13604325.        2371725.       13604325.
      2372916.77     13604588.51
#Sta/Elev= 30
  3344.9  336.56  3610.1   331.8  3911.6  329.17  3984.3   329.3  4204.9  328.69
  4564.9  322.15  4594.9  317.93  4604.9  321.99  4826.1   320.9  4904.9  318.03
  4924.9  322.94  4964.9  323.25  4974.9  322.42  4984.7   314.2  4985.2   313.7
  5000.2   314.2  5006.3  318.25  5014.2  320.91  5093.9  321.12  5205.9  322.97
  5337.8  322.65  5468.8  324.06  5638.7  326.04  5653.5  327.03  5865.5  331.01
  5916.7  327.68  5978.1   331.7  6140.8  335.32  6195.9  336.22  6215.5  336.58
#Mann= 16 ,-1 , 0
  3344.9     .07       0  3610.1    .035       0  3911.6     .05       0
  3984.3     .07       0  4826.1      .1       0  4984.7     .05       0
  5000.2      .1       0  5006.3     .07       0  5093.9     .12       0
  5205.9     .07       0  5337.8     .12       0  5468.8     .07       0
  5638.7     .12       0  5653.5     .07       0  6140.8     .12       0
  6195.9     .07       0
Bank Sta=4984.7,5000.2
XS Rating Curve= 0 ,0
Exp/Cntr=0.3,0.1

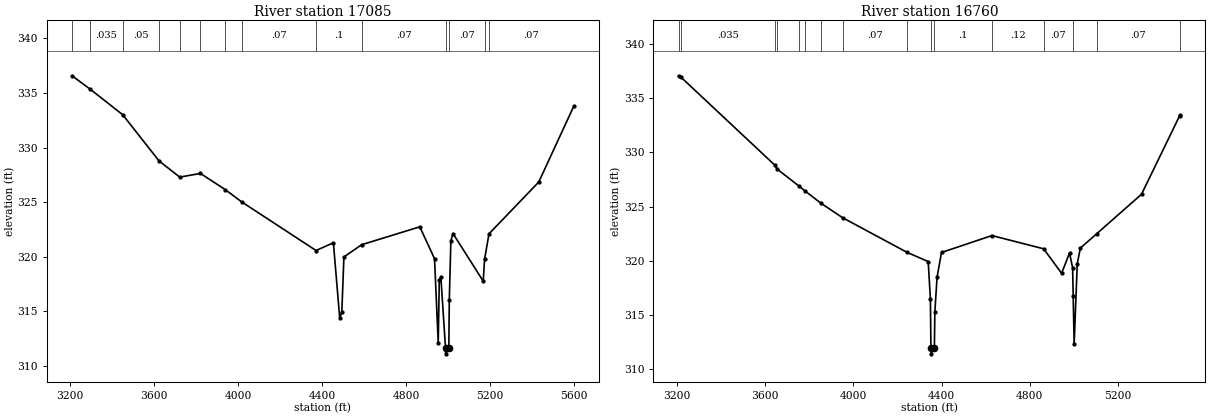
Type RM Length L Ch R = 1 ,17085   ,325,325,325
BEGIN DESCRIPTION:
JACK PUMP CREEK 19.0
END DESCRIPTION:
XS GIS Cut Line= 3
      2370125.04       13604475.        2371925.       13604625.
        2372225.     13605125.01
#Sta/Elev= 30
  3209.4  336.58  3293.8  335.38  3450.7  333.01  3623.7  328.78  3722.2   327.3
  3820.7  327.64  3939.9  326.14  4016.6  325.04  4371.1  320.58  4453.7  321.29
  4483.8  314.41  4493.8  314.91  4503.8  319.99    4588  321.11  4865.1  322.75
  4935.3  319.83  4952.9  312.12  4957.9  317.87  4965.4  318.17  4987.7  311.62
  4988.2  311.12  5003.3  311.62  5005.6  316.05  5013.1  321.48  5023.4  322.13
  5167.2  317.77  5173.6  319.78  5194.6  322.11  5431.5  326.85  5598.7  333.81
#Mann= 14 ,-1 , 0
  3209.4     .07       0  3293.8    .035       0  3450.7     .05       0
  3623.7    .035       0  3722.2     .05       0  3820.7     .07       0
  3939.9     .05       0  4016.6     .07       0  4371.1      .1       0
    4588     .07       0  4987.7     .05       0  5003.3     .07       0
  5173.6     .12       0  5194.6     .07       0
Bank Sta=4987.7,5003.3
XS Rating Curve= 0 ,0
Exp/Cntr=0.3,0.1

Type RM Length L Ch R = 1 ,16760   ,540,540,540
BEGIN DESCRIPTION:
A19480
END DESCRIPTION:
XS GIS Cut Line= 4
      2370088.59      13604588.5       2371703.2     13604755.17
      2371974.03     13604999.96      2372212.57     13605160.71
#Sta/Elev= 30
    3207  337.06    3216  336.97  3642.9  328.83  3655.1  328.44  3753.7  326.88
  3780.6  326.44  3852.3  325.31  3950.9  323.97  4242.6  320.78  4339.4  319.92
  4349.4  316.47  4351.7  311.91  4352.2  311.41  4367.3  311.91  4369.6  315.31
  4379.6  318.48  4399.7  320.76  4628.5  322.32  4862.8   321.1  4944.5  318.84
  4980.3  320.71  4994.4  319.36    4997   316.7  5001.3   312.3  5015.5  319.73
  5029.7  321.17  5102.7  322.47  5306.8  326.13  5481.9  333.46  5482.9  333.38
#Mann= 16 ,-1 , 0
    3207     .07       0    3216    .035       0  3642.9     .05       0
  3655.1    .035       0  3753.7     .05       0  3780.6    .035       0
  3852.3     .05       0  3950.9     .07       0  4242.6      .1       0
  4351.7     .05       0  4367.3      .1       0  4628.5     .12       0
  4862.8     .07       0    4997     .12       0  5102.7     .07       0
  5481.9     .12       0
Bank Sta=4351.7,4367.3
XS Rating Curve= 0 ,0
Exp/Cntr=0.3,0.1