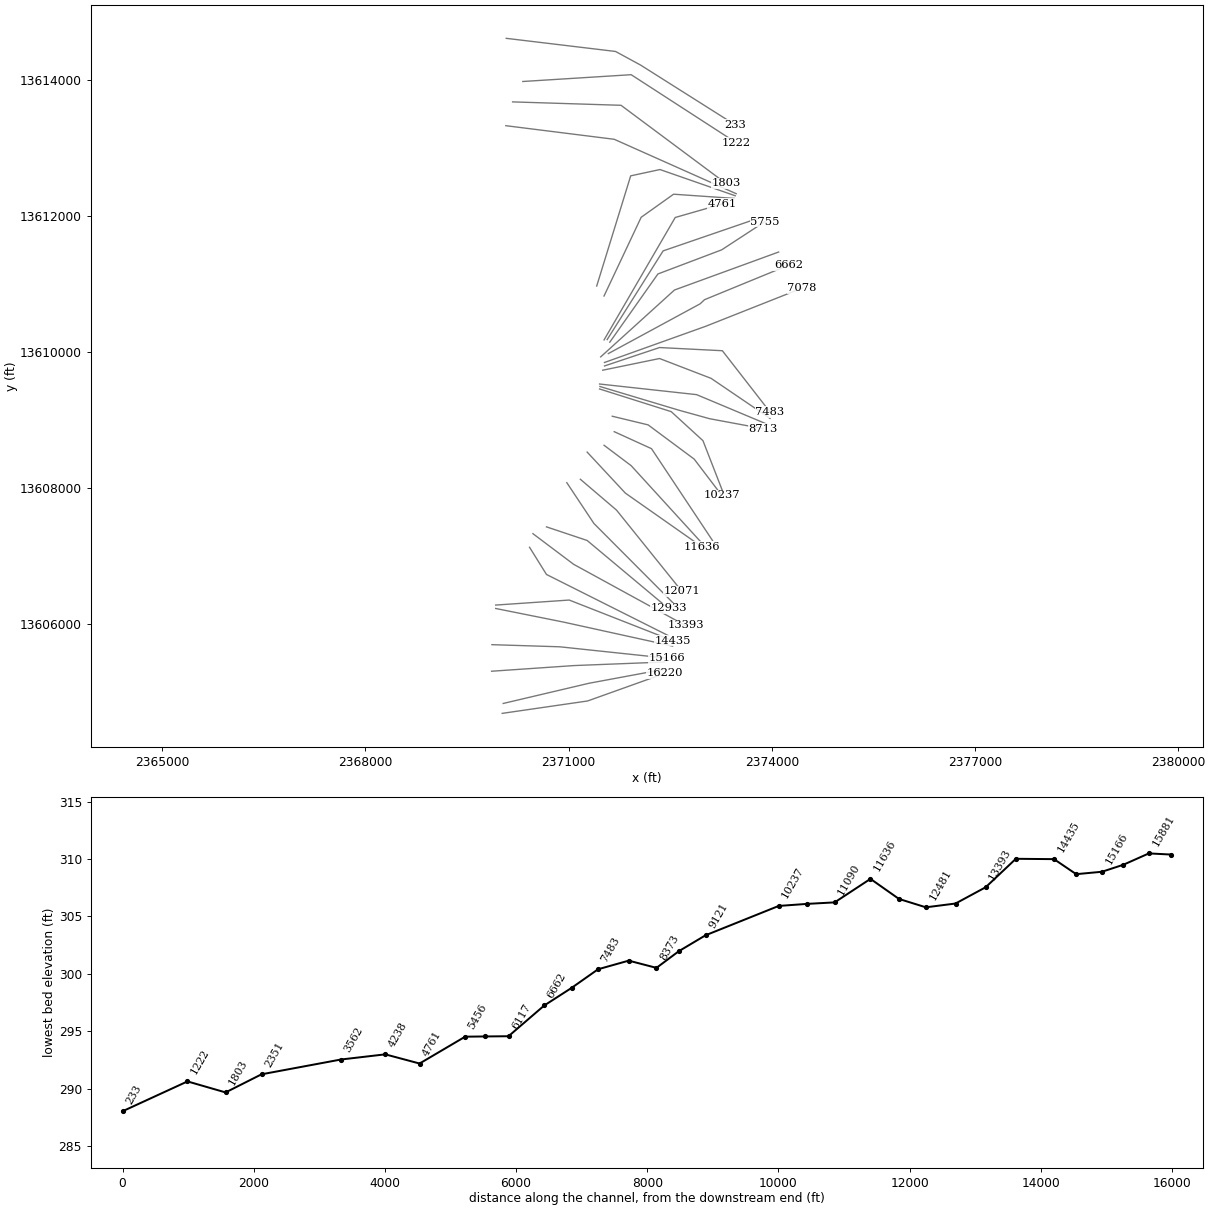
HEC-RAS study JACK PUMP CREEK.prj: JACK PUMP CREEK Base Level Engineering

--- JACK PUMP CREEK.g01 (geometry) --- (continued)

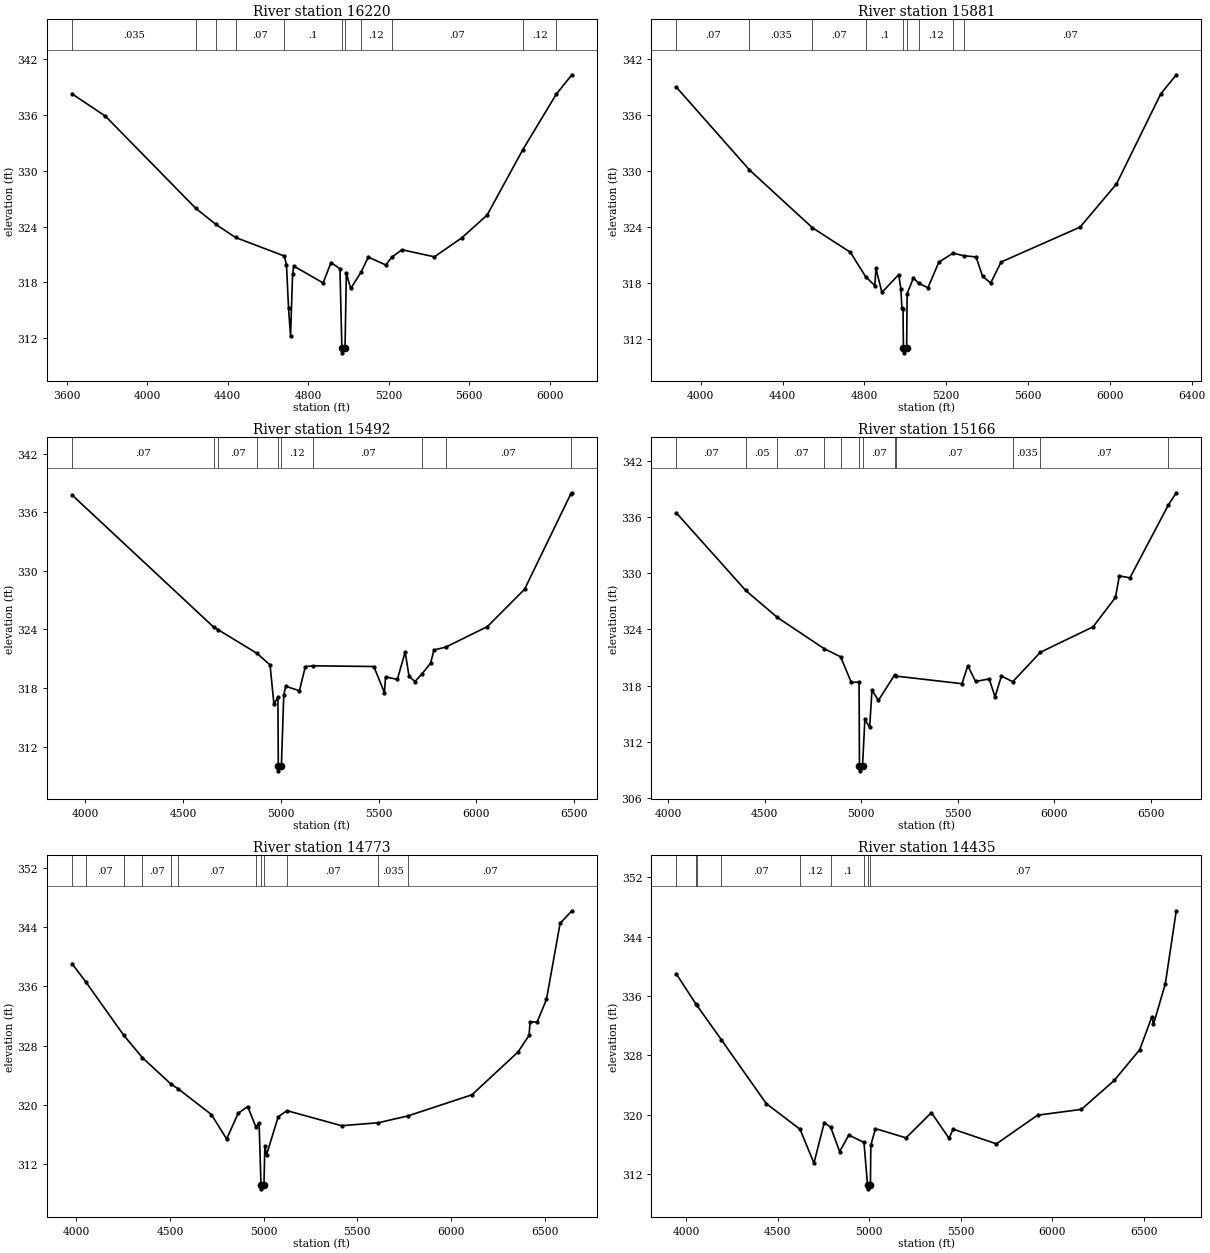
Type RM Length L Ch R = 1 ,16220   ,339,339,339
BEGIN DESCRIPTION:
A19479
END DESCRIPTION:
XS GIS Cut Line= 3
      2370020.86     13604682.24      2371281.32     13604864.54
      2372419.89     13605270.06
#Sta/Elev= 30
  3626.8  338.29  3792.6  335.89    4241  325.97    4340  324.25    4439  322.82
  4680.6  320.83  4691.9   319.9    4702  315.26  4712.1   312.2  4722.2  318.85
  4728.1  319.74  4873.8  317.93  4913.1  320.12  4957.4  319.46    4967   310.9
  4967.5   310.4  4982.6   310.9  4989.2  318.96  5010.9  317.33    5063  319.11
  5098.1  320.71  5185.2  319.86  5213.8  320.68  5265.2   321.5  5426.5  320.74
  5562.4  322.78    5688  325.23  5864.7  332.25  6031.8  338.26    6109  340.34
#Mann= 11 ,-1 , 0
  3626.8    .035       0    4241     .07       0    4340     .05       0
    4439     .07       0  4680.6      .1       0    4967     .05       0
  4982.6      .1       0    5063     .12       0  5213.8     .07       0
  5864.7     .12       0  6031.8     .07       0
Bank Sta=4967,4982.6
XS Rating Curve= 0 ,0
Exp/Cntr=0.3,0.1

Type RM Length L Ch R = 1 ,15881   ,389,389,389
BEGIN DESCRIPTION:
A19478
END DESCRIPTION:
XS GIS Cut Line= 3
      2370036.52     13604828.08      2371302.15     13605124.96
      2372427.14     13605333.29
#Sta/Elev= 30
  3880.4  339.02  4237.6  330.14    4545  323.94  4731.4  321.29  4806.3  318.66
  4850.8  317.72    4856  319.56  4885.4  316.99  4967.6   318.9  4977.9  317.39
  4983.3  315.27  4988.4  315.19  4990.6     311  4991.1   310.5  5006.3     311
  5008.7  316.85  5039.5  318.56  5064.8  317.96  5110.6  317.49  5163.3  320.22
  5232.4   321.2  5284.9  320.93    5346  320.79  5377.2  318.72  5417.2     318
    5468  320.25  5854.5     324  6032.2  328.63  6248.8   338.3  6324.5  340.35
#Mann= 9 ,-1 , 0
  3880.4     .07       0  4237.6    .035       0    4545     .07       0
  4806.3      .1       0  4990.6     .05       0  5006.3      .1       0
  5064.8     .12       0  5232.4      .1       0  5284.9     .07       0
Bank Sta=4990.6,5006.3
XS Rating Curve= 0 ,0
Exp/Cntr=0.3,0.1

Type RM Length L Ch R = 1 ,15492   ,326,326,326
BEGIN DESCRIPTION:
A19477
END DESCRIPTION:
XS GIS Cut Line= 3
      2369864.67     13605302.04       2371083.4     13605385.38
      2372416.71     13605437.46
#Sta/Elev= 30
  3932.1  337.78    4658  324.21    4681  323.95  4877.8  321.55  4944.8  320.36
  4964.8  316.32  4984.9  317.08  4987.1  310.01  4987.6  309.51  5002.8  310.01
  5014.9  317.28    5025  318.17  5095.1  317.72  5125.2  320.19  5165.8  320.27
  5475.5   320.2  5529.5  317.53  5535.6  319.14  5595.6  318.88  5635.6  321.69
  5655.7  319.18  5685.7  318.66  5722.3  319.46  5765.7  320.54  5782.7  321.89
  5843.8  322.19    6056  324.29  6246.1  328.11  6481.6  337.85    6488     338
#Mann= 10 ,-1 , 0
  3932.1     .07       0    4658     .12       0    4681     .07       0
  4877.8     .12       0  4987.1     .05       0  5002.8     .12       0
  5165.8     .07       0  5722.3    .035       0  5843.8     .07       0
  6481.6     .12       0
Bank Sta=4987.1,5002.8
XS Rating Curve= 0 ,0
Exp/Cntr=0.3,0.1

Type RM Length L Ch R = 1 ,15166   ,393,393,393
BEGIN DESCRIPTION:
A19476
END DESCRIPTION:
XS GIS Cut Line= 3
      2369869.82     13605692.67      2370869.86     13605661.42
      2372447.96     13605494.75
#Sta/Elev= 30
  4043.4  336.43  4402.5  328.15  4566.4  325.27  4808.4  321.94  4893.4  321.07
    4949  318.33    4989  318.38  4991.1   309.4  4991.6   308.9  5006.9   309.4
  5019.1   314.4  5043.9  313.55  5055.8   317.5  5089.3  316.42  5172.5  319.12
  5181.3  319.01  5521.7   318.2  5551.9  320.12  5592.1  318.44  5662.5  318.71
  5692.7   316.8  5725.9  319.02  5784.4  318.41  5927.8  321.56  6200.2  324.27
  6316.1  327.41  6336.2  329.71    6391   329.5  6589.3  337.26  6630.8  338.58
#Mann= 12 ,-1 , 0
  4043.4     .07       0  4402.5     .05       0  4566.4     .07       0
  4808.4     .12       0  4893.4     .07       0  4991.1     .05       0
  5006.9     .07       0  5172.5     .12       0  5181.3     .07       0
  5784.4    .035       0  5927.8     .07       0  6589.3     .12       0
Bank Sta=4991.1,5006.9
XS Rating Curve= 0 ,0
Exp/Cntr=0.3,0.1

Type RM Length L Ch R = 1 ,14773   ,338,338,338
BEGIN DESCRIPTION:
JACK PUMP CREEK 18.0
END DESCRIPTION:
XS GIS Cut Line= 3
        2369925.       13606225.        2370925.       13606025.
      2372536.55     13605671.83
#Sta/Elev= 30
  3975.9   339.1    4052  336.54  4252.3  329.42  4351.7   326.4  4506.3  322.79
  4541.9  322.21  4720.4  318.72  4801.9  315.42  4863.1  318.88  4914.1   319.8
    4958  317.06  4975.3  317.57  4985.3  309.19  4985.8  308.69  5001.1  309.19
  5005.9  314.44  5015.1   313.3  5077.6  318.44  5124.6  319.24  5415.4  317.21
  5611.5  317.61  5769.5  318.53  6111.6  321.38  6357.3  327.14    6417   329.4
  6422.1  331.25  6459.6  331.18  6509.8  334.26  6582.5  344.51  6645.5  346.22
#Mann= 12 ,-1 , 0
  3975.9     .05       0    4052     .07       0  4252.3     .05       0
  4351.7     .07       0  4506.3     .05       0  4541.9     .07       0
    4958     .12       0  4985.3     .05       0  5001.1     .12       0
  5124.6     .07       0  5611.5    .035       0  5769.5     .07       0
Bank Sta=4985.3,5001.1
XS Rating Curve= 0 ,0
Exp/Cntr=0.3,0.1

Type RM Length L Ch R = 1 ,14435   ,582,582,582
BEGIN DESCRIPTION:
JACK PUMP CREEK 17.0
END DESCRIPTION:
XS GIS Cut Line= 3
      2369925.05       13606275.      2371010.49     13606348.92
      2372540.82     13605750.32
#Sta/Elev= 30
  3947.4  338.96  4055.8  334.85  4059.5  334.73  4193.5  330.09  4438.5  321.49
  4623.1  318.03  4699.1  313.47  4755.6  318.94    4791  318.28  4839.4  315.03
  4889.5  317.25  4972.4  316.25  4991.9   310.5  4992.4     310  5007.7   310.5
  5009.8  315.87  5035.1  318.12  5201.9  316.87  5340.9  320.27  5437.5   316.8
    5459  318.05  5695.9  316.06  5920.7  319.93  6160.1  320.71  6339.5  324.61
  6479.1  328.76  6545.5  333.21  6554.2   332.2  6618.7  337.62  6678.6  347.48
#Mann= 9 ,-1 , 0
  3947.4     .05       0  4055.8     .07       0  4059.5     .05       0
  4193.5     .07       0  4623.1     .12       0    4791      .1       0
  4972.4     .07       0  4991.9     .05       0  5007.7     .07       0
Bank Sta=4991.9,5007.7
XS Rating Curve= 0 ,0
Exp/Cntr=0.3,0.1

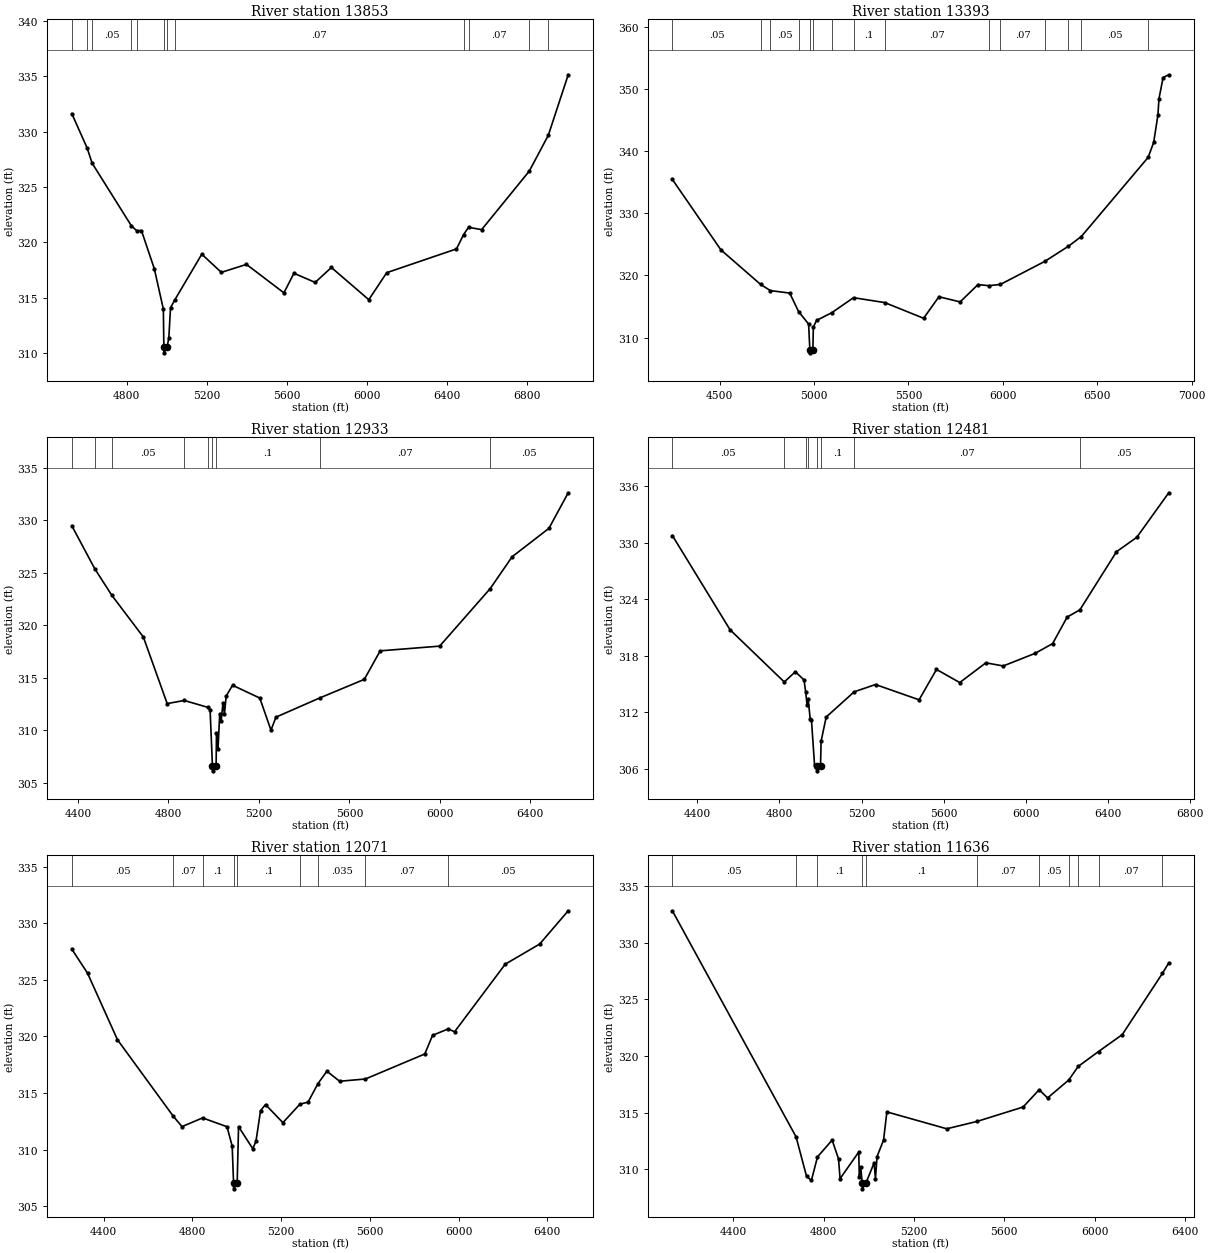
Type RM Length L Ch R = 1 ,13853   ,460,460,460
BEGIN DESCRIPTION:
JACK PUMP CREEK 16.0
END DESCRIPTION:
XS GIS Cut Line= 3
      2370425.02     13607124.96        2370675.       13606725.
      2372474.99     13605825.01
#Sta/Elev= 30
  4524.5  331.64  4601.1  328.54  4626.3  327.16  4822.5  321.51  4849.4  321.06
  4872.9  321.08  4937.2  317.64  4982.6  313.99  4985.2  310.53  4985.7  310.03
  5001.3  310.53  5010.1   311.4  5018.5   314.1  5039.8  314.81    5175  318.94
  5272.9   317.3  5398.6  318.02  5585.9  315.45  5636.2  317.22  5742.4  316.39
  5823.5  317.74  6010.8  314.83  6100.2  317.27  6449.6  319.42    6485  320.71
  6509.7  321.37  6575.4  321.16  6813.9  326.45    6909  329.68  7008.6  335.15
#Mann= 12 ,-1 , 0
  4524.5     .05       0  4601.1     .07       0  4626.3     .05       0
  4822.5     .07       0  4849.4     .05       0  4985.2     .05       0
  5001.3     .05       0  5039.8     .07       0    6485     .05       0
  6509.7     .07       0  6813.9     .05       0    6909     .07       0
Bank Sta=4985.2,5001.3
XS Rating Curve= 0 ,0
Exp/Cntr=0.3,0.1

Type RM Length L Ch R = 1 ,13393   ,460,460,460
BEGIN DESCRIPTION:
JACK PUMP CREEK 15.0
END DESCRIPTION:
XS GIS Cut Line= 3
      2370475.02     13607324.98        2371075.       13606875.
      2372725.03     13605974.98
#Sta/Elev= 30
  4249.1  335.44  4506.4  324.11  4716.7  318.55  4768.4  317.56  4870.9  317.16
  4917.7  314.19  4970.9  312.18  4977.5  308.05    4978  307.55  4993.6  308.05
  4995.9  311.68  5012.8  312.76  5093.9  314.01  5208.8  316.42  5374.5  315.63
    5580  313.11  5661.2  316.57  5773.6  315.74  5868.1  318.53  5925.1  318.35
  5986.8  318.55  6222.7  322.27  6347.5   324.7  6415.6  326.26  6769.6  338.99
  6798.8  341.39  6821.1  345.77  6826.8  348.42  6848.7  351.83  6878.6  352.27
#Mann= 15 ,-1 , 0
  4249.1     .05       0  4716.7     .07       0  4768.4     .05       0
  4917.7     .12       0  4977.5     .05       0  4993.6     .12       0
  5093.9     .07       0  5208.8      .1       0  5374.5     .07       0
  5925.1     .05       0  5986.8     .07       0  6222.7     .05       0
  6347.5     .07       0  6415.6     .05       0  6769.6     .07       0
Bank Sta=4977.5,4993.6
XS Rating Curve= 0 ,0
Exp/Cntr=0.3,0.1

Type RM Length L Ch R = 1 ,12933   ,452,452,452
BEGIN DESCRIPTION:
JACK PUMP CREEK 14.0
END DESCRIPTION:
XS GIS Cut Line= 3
      2370674.97     13607425.01        2371275.       13607225.
      2372474.97     13606225.02
#Sta/Elev= 30
  4372.9   329.5  4474.3   325.4  4549.9  322.86  4689.2  318.89  4794.6  312.54
  4869.9  312.84  4974.6  312.18  4984.3  311.95  4994.6  306.63  4995.1  306.13
  5010.9  306.63  5012.5  309.73  5019.1  308.17  5026.9  311.58  5033.4   310.9
  5041.2  312.61  5047.7  311.57  5055.5  313.26  5083.5  314.29  5203.9  313.07
  5253.4  310.01  5275.5  311.25    5468  313.07    5666  314.85  5736.3  317.57
  5999.2  318.02  6222.4   323.5  6319.5  326.54  6482.2  329.25  6567.4  332.64
#Mann= 9 ,-1 , 0
  4372.9     .05       0  4474.3    .035       0  4549.9     .05       0
  4869.9     .07       0  4974.6      .1       0  4994.6     .05       0
  5010.9      .1       0    5468     .07       0  6222.4     .05       0
Bank Sta=4994.6,5010.9
XS Rating Curve= 0 ,0
Exp/Cntr=0.3,0.1

Type RM Length L Ch R = 1 ,12481   ,410,410,410
BEGIN DESCRIPTION:
JACK PUMP CREEK 13.0
END DESCRIPTION:
XS GIS Cut Line= 3
      2370974.99     13608075.02        2371375.       13607475.
      2372575.01     13606274.99
#Sta/Elev= 30
  4278.3  330.75  4559.3  320.76  4823.6  315.22  4877.7  316.31  4919.8  315.43
  4928.1  314.11  4934.8  312.73  4939.8  313.41  4949.9  311.31  4955.9  311.23
  4970.9  306.46  4983.8   306.3  4984.3   305.8  5000.1   306.3    5003  308.94
  5027.7   311.5  5164.1  314.18  5268.1  314.95  5480.3  313.33  5565.1  316.55
  5678.3  315.16  5805.5  317.25  5890.4  316.92  6045.9  318.26  6130.8  319.29
  6201.5   322.1  6263.7  322.87  6441.9  329.03  6540.9  330.56  6696.5  335.28
#Mann= 8 ,-1 , 0
  4278.3     .05       0  4823.6    .035       0  4928.1     .07       0
  4939.8      .1       0  4983.8     .05       0  5000.1      .1       0
  5164.1     .07       0  6263.7     .05       0
Bank Sta=4983.8,5000.1
XS Rating Curve= 0 ,0
Exp/Cntr=0.3,0.1

Type RM Length L Ch R = 1 ,12071   ,435,435,435
BEGIN DESCRIPTION:
JACK PUMP CREEK 12.0
END DESCRIPTION:
XS GIS Cut Line= 3
      2371175.01     13608124.99       2371708.4     13607671.83
      2372674.99     13606475.01
#Sta/Elev= 30
  4256.1  327.72  4326.9   325.6    4462  319.71  4713.6  312.95  4753.1  312.03
  4845.9   312.8    4956  312.02  4979.3   310.3  4985.5  307.03    4986  306.53
  5001.8  307.03    5008  312.03    5072  310.08  5086.4  310.72  5107.2  313.44
  5129.5  313.98  5207.9  312.38  5284.5  314.01  5321.4   314.2  5366.4  315.84
  5406.2  316.93  5463.8  316.04    5580  316.24  5847.6  318.45  5882.8   320.1
  5953.9  320.67  5981.9  320.41  6210.5  326.39  6365.9  328.17  6494.4  331.11
#Mann= 9 ,-1 , 0
  4256.1     .05       0  4713.6     .07       0  4845.9      .1       0
  4985.5     .05       0  5001.8      .1       0  5284.5     .07       0
  5366.4    .035       0    5580     .07       0  5953.9     .05       0
Bank Sta=4985.5,5001.8
XS Rating Curve= 0 ,0
Exp/Cntr=0.3,0.1

Type RM Length L Ch R = 1 ,11636   ,546,546,546
BEGIN DESCRIPTION:
JACK PUMP CREEK 11.0
END DESCRIPTION:
XS GIS Cut Line= 3
      2371275.02     13608524.98      2371838.61     13607921.83
       2372963.6     13607135.39
#Sta/Elev= 30
  4129.9  332.82  4677.7  312.87  4724.1  309.39  4745.6  309.02  4772.6   311.1
  4837.5  312.58  4865.8  310.92  4872.6  309.18  4955.4  311.53  4957.8  309.36
  4963.9  310.22  4970.6  308.78  4971.1  308.28    4987  308.78  5023.2  310.57
  5029.3  309.19  5036.4  311.13  5065.1  312.58  5079.9  315.07    5345  313.58
  5479.2  314.23    5683   315.5  5754.3  317.03  5791.5   316.3  5885.5  317.89
  5926.9  319.08  6017.2   320.4  6122.1  321.89  6299.8  327.29    6328  328.22
#Mann= 11 ,-1 , 0
  4129.9     .05       0  4677.7     .07       0  4772.6      .1       0
  4970.6     .05       0    4987      .1       0  5479.2     .07       0
  5754.3     .05       0  5885.5     .07       0  5926.9     .05       0
  6017.2     .07       0  6299.8     .05       0
Bank Sta=4970.6,4987
XS Rating Curve= 0 ,0
Exp/Cntr=0.3,0.1

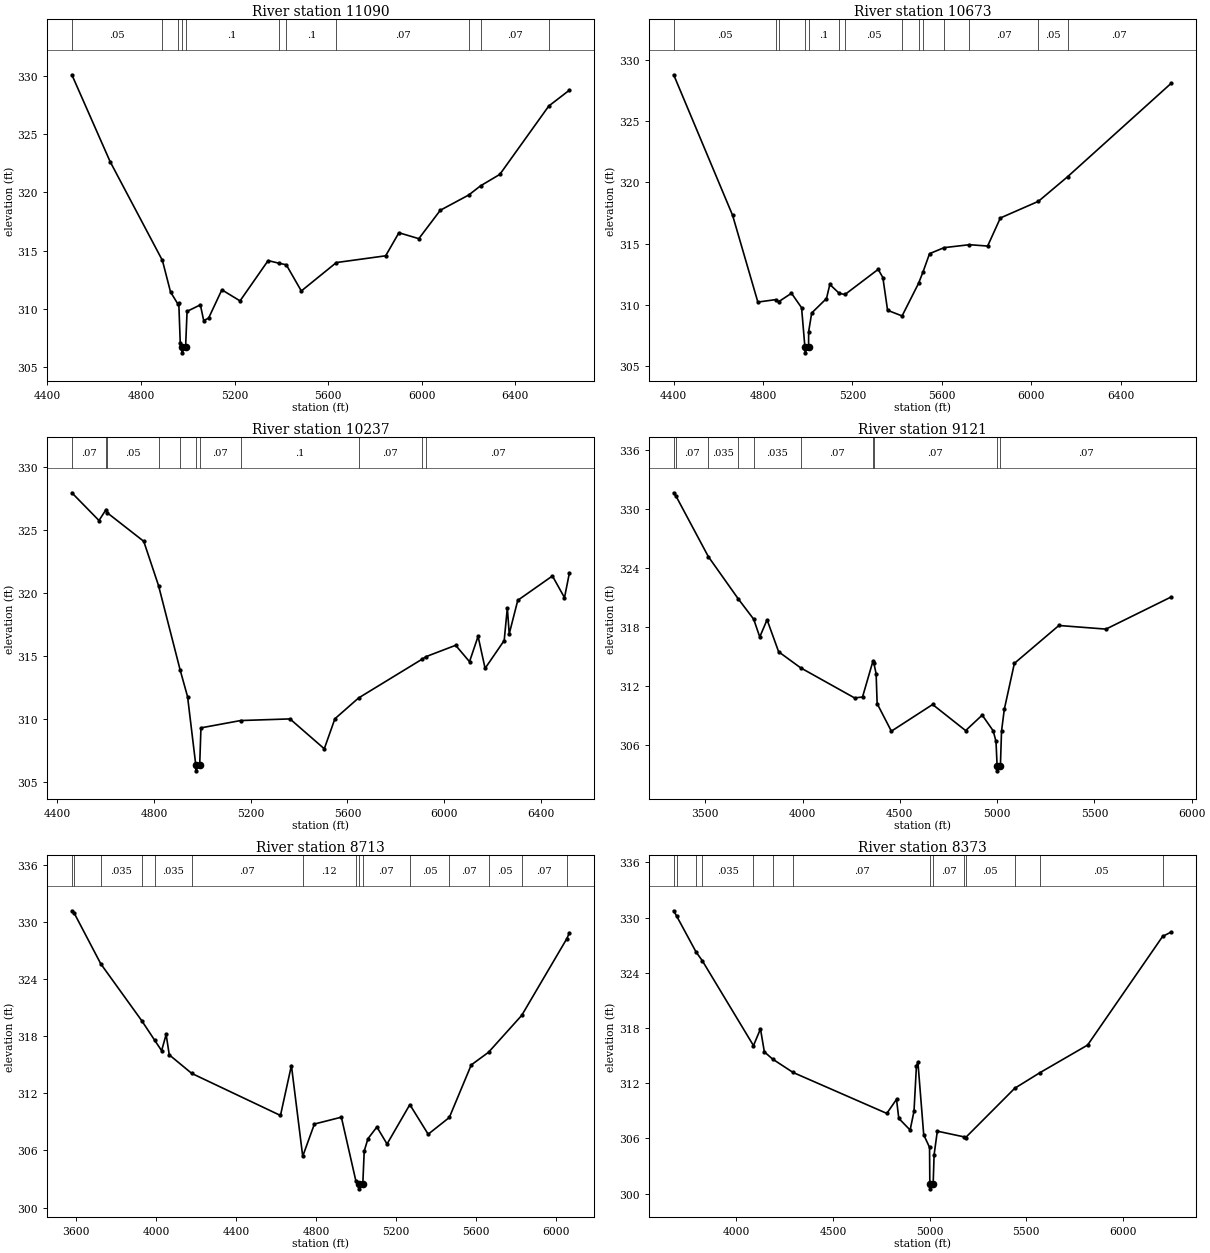
Type RM Length L Ch R = 1 ,11090   ,417,417,417
BEGIN DESCRIPTION:
JACK PUMP CREEK 10.0
END DESCRIPTION:
XS GIS Cut Line= 3
      2371525.02     13608624.99        2371925.       13608325.
      2373025.03     13607124.97
#Sta/Elev= 30
  4504.4   330.1  4667.9  322.65  4891.7  314.16  4926.3  311.46  4956.9  310.45
  4961.7  310.51  4967.9  307.11  4974.3  306.73  4974.8  306.23  4990.8  306.73
  4997.1  309.79    5054  310.35  5068.2     309  5089.2  309.21  5145.9  311.64
  5223.6  310.69  5343.8  314.15  5388.5  313.93  5421.4  313.79  5485.7  311.54
  5635.5  313.98  5846.4  314.56  5903.1  316.54  5988.2  316.03  6080.1  318.47
  6201.7  319.78  6252.5  320.57  6334.7  321.55  6544.1  327.42  6632.3  328.78
#Mann= 11 ,-1 , 0
  4504.4     .05       0  4891.7     .07       0  4956.9      .1       0
  4974.3     .05       0  4990.8      .1       0  5388.5     .07       0
  5421.4      .1       0  5635.5     .07       0  6201.7     .05       0
  6252.5     .07       0  6544.1     .05       0
Bank Sta=4974.3,4990.8
XS Rating Curve= 0 ,0
Exp/Cntr=0.3,0.1

Type RM Length L Ch R = 1 ,10673   ,436,436,436
BEGIN DESCRIPTION:
JACK PUMP CREEK 9.0
END DESCRIPTION:
XS GIS Cut Line= 3
      2371675.02     13608824.99        2372225.       13608575.
      2373124.99     13607225.02
#Sta/Elev= 30
    4400  328.78  4663.6  317.32  4776.7  310.24  4856.3  310.44  4869.8  310.27
  4927.2  310.96  4972.3  309.78  4987.1   306.6  4987.6   306.1  5003.6   306.6
  5004.1  307.84  5017.6  309.35  5083.8  310.53  5098.8  311.68  5140.9  310.95
  5166.7  310.86  5315.1  312.91  5336.1  312.24  5357.2  309.57  5422.1  309.11
  5495.6  311.76  5515.2  312.67    5545  314.19  5610.2  314.68  5723.3  314.92
  5804.9  314.81  5861.9   317.1  6032.3  318.46  6162.5  320.46  6626.6  328.09
#Mann= 14 ,-1 , 0
    4400     .05       0  4856.3     .07       0  4869.8      .1       0
  4987.1     .05       0  5003.6      .1       0  5140.9     .07       0
  5166.7     .05       0  5422.1     .07       0  5495.6     .05       0
  5515.2     .07       0  5610.2     .05       0  5723.3     .07       0
  6032.3     .05       0  6162.5     .07       0
Bank Sta=4987.1,5003.6
XS Rating Curve= 0 ,0
Exp/Cntr=0.3,0.1

Type RM Length L Ch R = 1 ,10237   ,1116,1116,1116
BEGIN DESCRIPTION:
JACK PUMP CREEK 8.0
END DESCRIPTION:
XS GIS Cut Line= 4
      2371645.88     13609052.05        2372175.       13608925.
      2372855.22     13608421.34      2373260.22     13607890.93
#Sta/Elev= 30
  4460.3  327.98  4572.5  325.78  4601.8  326.65  4606.8  326.39  4757.6  324.13
  4818.9  320.61  4908.2  313.92  4938.9   311.8  4972.6  306.42  4973.1  305.92
  4989.1  306.42  4994.2  309.33  5158.4  309.91  5362.4  310.04  5504.3  307.67
  5548.2  310.05  5646.1   311.7  5908.2  314.77    5925  314.98  6047.6  315.88
    6105  314.58  6140.4  316.59  6169.4  314.05  6248.4  316.26  6261.4  318.85
  6269.2  316.79  6304.6  319.45  6447.9  321.38  6497.8  319.66  6518.2  321.63
#Mann= 11 ,-1 , 0
  4460.3     .07       0  4601.8    .035       0  4606.8     .05       0
  4818.9    .035       0  4908.2     .07       0  4972.6     .05       0
  4989.1     .07       0  5158.4      .1       0  5646.1     .07       0
  5908.2     .05       0    5925     .07       0
Bank Sta=4972.6,4989.1
XS Rating Curve= 0 ,0
Exp/Cntr=0.3,0.1

Type RM Length L Ch R = 1 ,9121    ,408,408,408
BEGIN DESCRIPTION:
A19475
END DESCRIPTION:
XS GIS Cut Line= 4
      2371458.38     13609453.09       2372515.7     13609119.75
      2372984.45     13608692.67      2373280.68      13607933.9
#Sta/Elev= 30
  3337.8  331.69  3350.3  331.33  3515.8  325.19  3670.1  320.87    3749  318.81
  3780.2     317  3817.8  318.75  3877.2  315.49    3990  313.86  4267.4  310.79
  4308.3  310.88  4361.4   314.5    4366  314.39  4378.3  313.25  4383.5  310.21
  4456.6   307.4  4668.7  310.12  4838.3  307.46  4923.5  309.04  4980.2  307.43
  4994.4  306.35  5000.1  303.86  5000.6  303.36    5017  303.86  5022.8   307.4
    5037  309.62  5088.8  314.31  5317.7  318.17  5559.5   317.8  5895.1  321.08
#Mann= 10 ,-1 , 0
  3337.8    .035       0  3350.3     .07       0  3515.8    .035       0
  3670.1     .07       0    3749    .035       0    3990     .07       0
  4361.4    .035       0    4366     .07       0  5000.1     .05       0
    5017     .07       0
Bank Sta=5000.1,5017
XS Rating Curve= 0 ,0
Exp/Cntr=0.3,0.1

Type RM Length L Ch R = 1 ,8713    ,340,340,340
BEGIN DESCRIPTION:
A19474
END DESCRIPTION:
XS GIS Cut Line= 4
      2371463.58     13609489.55      2372630.28     13609140.58
       2373083.4     13609015.58      2373869.19     13608869.87
#Sta/Elev= 30
  3578.8  331.19  3589.6  330.98  3723.5  325.61  3928.4  319.63  3993.5  317.56
  4027.4  316.49    4050  318.19  4065.7  316.05    4178   314.1  4621.5  309.68
  4676.2  314.93  4732.7  305.39  4791.1  308.78  4925.9   309.5  4998.4   302.8
  5015.8  302.47  5016.3  301.97    5033  302.47  5040.1  305.94  5058.8  307.24
  5103.5  308.47  5154.2  306.68  5268.1  310.82  5359.8  307.71  5465.5  309.47
    5575  314.99  5661.4  316.32  5827.4   320.2  6053.1  328.27  6065.8  328.89
#Mann= 15 ,-1 , 0
  3578.8    .035       0  3589.6     .07       0  3723.5    .035       0
  3928.4     .07       0  3993.5    .035       0    4178     .07       0
  4732.7     .12       0  4998.4     .07       0  5015.8     .05       0
    5033     .07       0  5268.1     .05       0  5465.5     .07       0
  5661.4     .05       0  5827.4     .07       0  6053.1     .05       0
Bank Sta=5015.8,5033
XS Rating Curve= 0 ,0
Exp/Cntr=0.3,0.1

Type RM Length L Ch R = 1 ,8373    ,423,423,423
BEGIN DESCRIPTION:
A19473
END DESCRIPTION:
XS GIS Cut Line= 3
      2371458.45       13609526.       2372890.7     13609369.75
      2373937.61     13608932.24
#Sta/Elev= 30
  3675.8  330.75  3691.8  330.15  3791.1  326.29    3824  325.32  4088.9  316.09
    4125  317.91  4145.1  315.41  4188.2  314.62    4294  313.17  4778.9  308.72
  4829.2  310.25  4840.9  308.18  4899.6  306.91  4919.7  308.96  4932.3   313.9
  4939.8  314.31    4970  306.39  5000.2  305.03  5001.6  301.02  5002.1  300.52
  5018.8  301.02  5023.7  304.22  5040.4  306.79  5180.8  306.16  5186.6  306.09
  5440.9  311.45  5571.7  313.15  5818.2  316.15  6206.8  327.97  6251.2  328.44
#Mann= 14 ,-1 , 0
  3675.8     .07       0  3691.8    .035       0  3791.1     .07       0
    3824    .035       0  4088.9     .07       0  4188.2    .035       0
    4294     .07       0  5001.6     .05       0  5018.8     .07       0
  5180.8     .12       0  5186.6     .05       0  5440.9     .07       0
  5571.7     .05       0  6206.8     .07       0
Bank Sta=5001.6,5018.8
XS Rating Curve= 0 ,0
Exp/Cntr=0.3,0.1

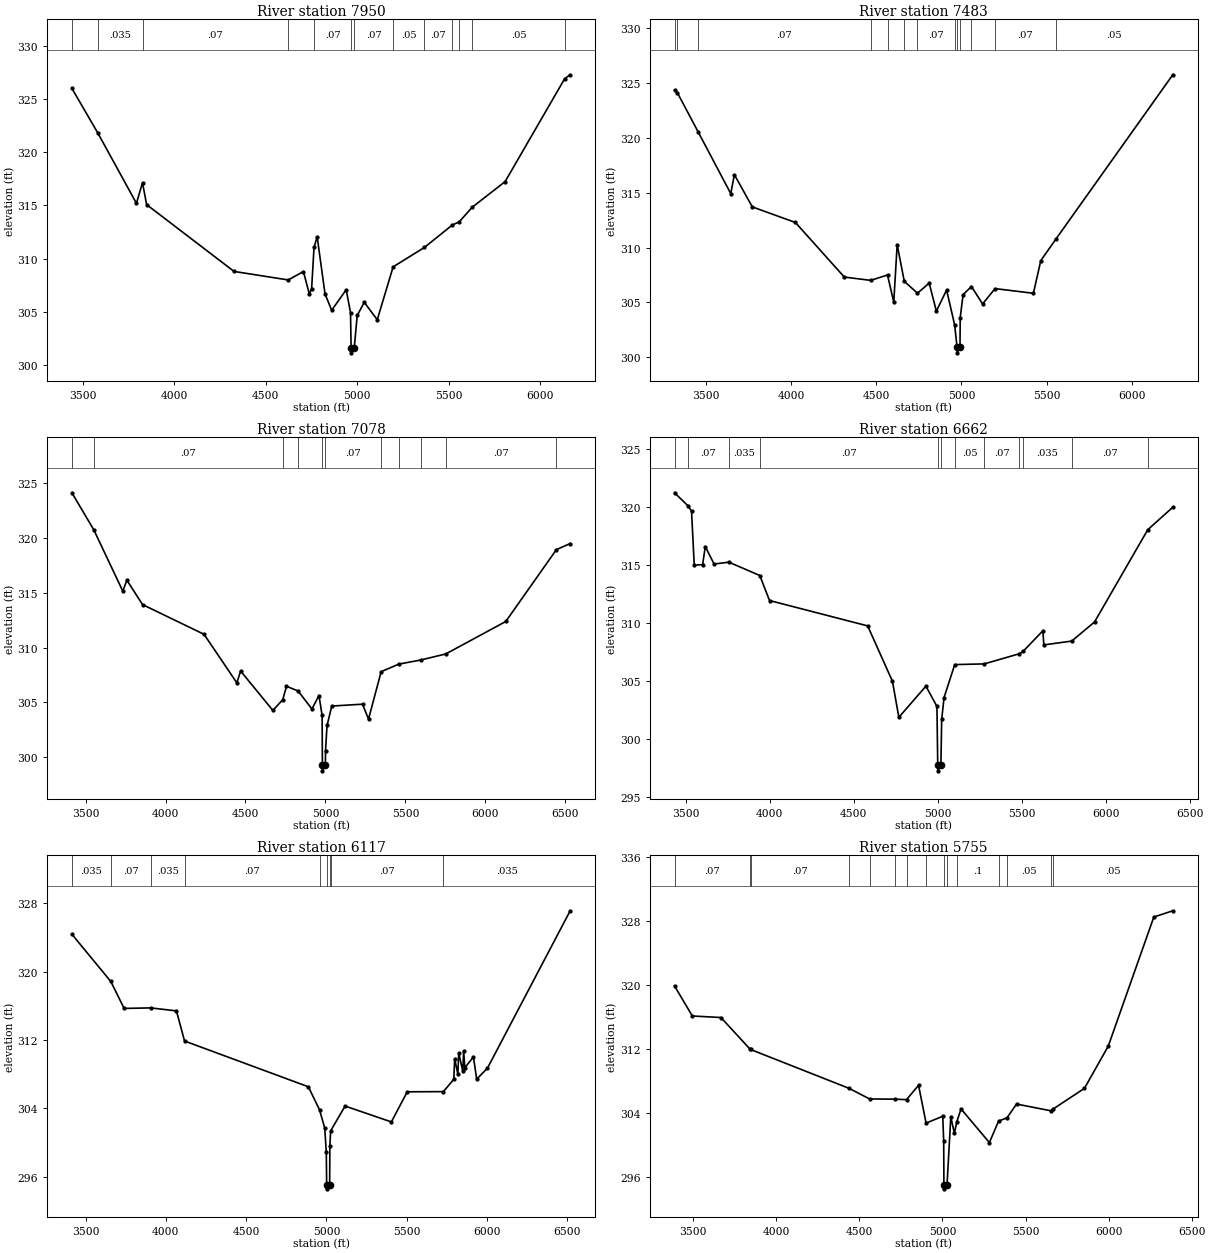
Type RM Length L Ch R = 1 ,7950    ,467,467,467
BEGIN DESCRIPTION:
A19472
END DESCRIPTION:
XS GIS Cut Line= 4
      2371505.32     13609729.13      2372343.82       13609901.
      2373104.24     13609609.33      2373974.05     13609020.77
#Sta/Elev= 30
  3441.7     326  3582.6  321.83  3794.1   315.2  3827.2  317.14  3849.7  315.08
    4327   308.8  4622.7     308  4705.9  308.79    4738  306.68  4750.6  307.18
  4763.7  311.05  4780.9  312.06  4823.7  306.69    4860  305.15  4939.4  307.08
  4962.9  304.94  4966.2  301.65  4966.7  301.15  4983.4  301.65  4999.5  304.66
  5037.9   305.9  5108.9  304.26  5195.6  309.23  5366.1  311.05  5518.5  313.16
  5556.7  313.46  5626.5  314.82    5807  317.24  6132.5  326.92  6162.3  327.28
#Mann= 13 ,-1 , 0
  3441.7     .07       0  3582.6    .035       0  3827.2     .07       0
  4622.7     .12       0  4763.7     .07       0  4966.2     .05       0
  4983.4     .07       0  5195.6     .05       0  5366.1     .07       0
  5518.5     .05       0  5556.7     .07       0  5626.5     .05       0
  6132.5     .07       0
Bank Sta=4966.2,4983.4
XS Rating Curve= 0 ,0
Exp/Cntr=0.3,0.1

Type RM Length L Ch R = 1 ,7483    ,405,405,405
BEGIN DESCRIPTION:
A19471
END DESCRIPTION:
XS GIS Cut Line= 4
      2371531.33     13609791.63      2372343.82     13610062.46
       2373270.9     13610015.58      2373974.01     13609114.57
#Sta/Elev= 30
  3314.1  324.34  3330.3  324.14    3452  320.58  3644.7  314.92  3665.8  316.65
  3771.2  313.71  4024.2  312.29  4311.9  307.31  4466.8  307.01  4565.5   307.5
  4602.3  305.02  4622.3  310.27  4664.1  306.92  4741.7  305.84  4810.4  306.76
  4852.6   304.2  4912.7  306.13  4960.1  302.94  4974.2   300.9  4974.7   300.4
  4991.4   300.9  4992.8  303.62  5009.6  305.71  5058.7  306.45  5124.2  304.86
  5197.4  306.26  5422.7  305.83  5466.1  308.81  5553.7  310.75  6241.7  325.76
#Mann= 13 ,-1 , 0
  3314.1     .07       0  3330.3    .035       0    3452     .07       0
  4466.8     .12       0  4565.5     .07       0  4664.1    .035       0
  4741.7     .07       0  4960.1    .035       0  4974.2    .035       0
  4991.4    .035       0  5058.7     .05       0  5197.4     .07       0
  5553.7     .05       0
Bank Sta=4974.2,4991.4
XS Rating Curve= 0 ,0
Exp/Cntr=0.3,0.1

Type RM Length L Ch R = 1 ,7078    ,416,416,416
BEGIN DESCRIPTION:
JACK PUMP CREEK 7.0
END DESCRIPTION:
XS GIS Cut Line= 3
      2371531.29     13609842.66        2373025.       13610375.
      2374448.02     13610936.43
#Sta/Elev= 30
  3414.7  324.09  3551.9  320.71  3733.1  315.13  3758.4  316.13  3856.4  313.91
  4241.1   311.2  4446.2  306.78  4469.6  307.86  4671.3  304.27  4733.1  305.25
  4756.3  306.47  4829.3  306.04  4915.5   304.4  4959.5  305.63  4979.2  303.82
    4981  299.27  4981.5  298.77  4999.7  299.27  5000.4  300.59  5009.9   302.9
  5039.7  304.67  5231.8  304.84  5269.2  303.48  5348.4   307.8  5459.2  308.49
  5595.1  308.86  5751.8  309.41  6127.5  312.37  6443.8  318.91  6530.2  319.47
#Mann= 11 ,-1 , 0
  3414.7    .035       0  3551.9     .07       0  4733.1     .12       0
  4829.3     .07       0    4981     .05       0  4999.7     .07       0
  5348.4     .05       0  5459.2     .07       0  5595.1    .035       0
  5751.8     .07       0  6443.8     .05       0
Bank Sta=4981,4999.7
XS Rating Curve= 0 ,0
Exp/Cntr=0.3,0.1

Type RM Length L Ch R = 1 ,6662    ,545,545,545
BEGIN DESCRIPTION:
JACK PUMP CREEK 6.0
END DESCRIPTION:
XS GIS Cut Line= 4
      2371587.72      13609973.5      2372943.26     13610705.72
      2373006.95     13610765.73      2374246.19      13611272.7
#Sta/Elev= 30
  3432.4  321.24  3511.1  320.14  3533.8  319.65    3550  314.99  3599.8  315.04
  3615.6   316.6    3668  315.09    3756  315.25  3940.3   314.1  3998.2  311.94
  4582.6  309.75  4730.1  304.97  4768.2  301.86  4929.6  304.55    4995   302.8
  4999.8  297.74  5000.3  297.24  5018.5  297.74  5023.3  301.68  5037.5  303.57
    5101  306.41  5276.5  306.47  5486.6  307.35  5507.9  307.55  5626.1  309.33
  5631.5  308.11  5797.6  308.44  5933.6  310.09  6250.3  318.05  6399.5  319.99
#Mann= 12 ,-1 , 0
  3432.4    .035       0  3511.1     .07       0    3756    .035       0
  3940.3     .07       0  4999.8     .05       0  5018.5     .07       0
    5101     .05       0  5276.5     .07       0  5486.6     .05       0
  5507.9    .035       0  5797.6     .07       0  6250.3    .035       0
Bank Sta=4999.8,5018.5
XS Rating Curve= 0 ,0
Exp/Cntr=0.3,0.1

Type RM Length L Ch R = 1 ,6117    ,362,362,362
BEGIN DESCRIPTION:
JACK PUMP CREEK 5.0
END DESCRIPTION:
XS GIS Cut Line= 3
      2371475.02     13609925.02      2372564.02     13610908.49
      2374101.77     13611467.33
#Sta/Elev= 30
  3414.7  324.39  3656.9  318.86  3740.1   315.7    3906  315.76  4065.9  315.41
  4116.3  311.88  4887.4  306.52  4957.1  303.82  4989.5  301.68  4999.2  298.86
  5001.4  295.06  5001.9  294.56  5020.1  295.06  5021.4  299.57  5026.1  301.35
  5116.3  304.26  5404.4   302.4  5503.4  305.93  5728.4  305.95  5793.4   307.4
  5798.8   309.8  5818.7     308    5824  310.47  5849.3  308.35  5854.6  310.72
    5862  308.75  5915.8  310.02  5935.8  307.41  6002.3  308.68  6518.2  327.14
#Mann= 9 ,-1 , 0
  3414.7    .035       0  3656.9     .07       0    3906    .035       0
  4116.3     .07       0  4957.1     .12       0  5001.4     .05       0
  5020.1     .12       0  5026.1     .07       0  5728.4    .035       0
Bank Sta=5001.4,5020.1
XS Rating Curve= 0 ,0
Exp/Cntr=0.3,0.1

Type RM Length L Ch R = 1 ,5755    ,299,299,299
BEGIN DESCRIPTION:
A19470
END DESCRIPTION:
XS GIS Cut Line= 4
      2371609.17     13610140.86      2372319.23     13611144.21
      2373260.86     13611499.25      2373900.73     13611915.55
#Sta/Elev= 30
  3387.6  319.86  3494.9  316.11  3667.2  315.92  3839.2  312.04  3845.5  311.93
  4438.4  307.08  4561.6  305.76  4713.9  305.73  4783.9  305.67  4856.3  307.46
  4901.8  302.74    5002   303.6  5007.7  300.46    5009  295.04  5009.5  294.54
  5027.8  295.04  5050.4  303.52  5071.8  301.48  5086.5   302.9  5112.1  304.51
  5282.7  300.31  5337.9  302.99  5389.2  303.41  5445.9  305.12  5652.8  304.28
    5666   304.5  5854.7  307.08  5997.9  312.34  6272.3  328.46  6386.5  329.24
#Mann= 15 ,-1 , 0
  3387.6     .07       0  3839.2    .035       0  3845.5     .07       0
  4438.4    .035       0  4561.6     .05       0  4713.9    .035       0
  4783.9     .05       0  4901.8      .1       0    5009     .05       0
  5027.8      .1       0  5086.5      .1       0  5337.9    .035       0
  5389.2     .05       0  5652.8    .035       0    5666     .05       0
Bank Sta=5009,5027.8
XS Rating Curve= 0 ,0
Exp/Cntr=0.3,0.1

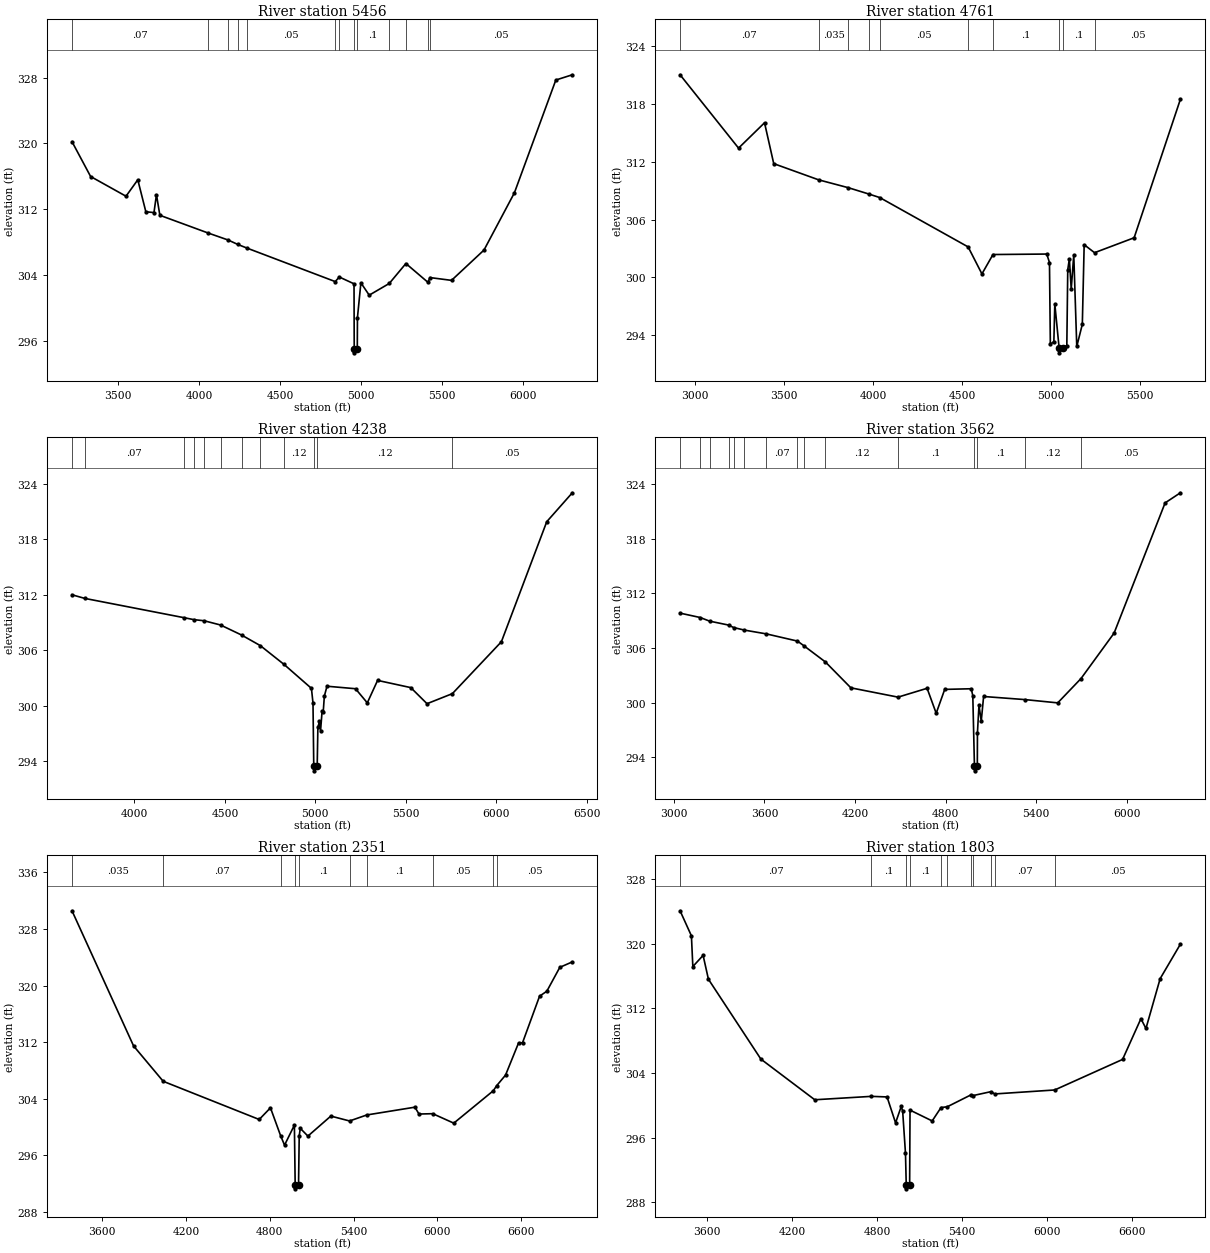
Type RM Length L Ch R = 1 ,5456    ,695,695,695
BEGIN DESCRIPTION:
A19469
END DESCRIPTION:
XS GIS Cut Line= 3
      2371570.53     13610179.39      2372396.41     13611483.81
      2373861.46     13611985.01
#Sta/Elev= 30
    3215  320.22  3330.1  315.98  3548.8  313.58  3621.7  315.58  3671.4  311.69
  3721.7  311.59    3737  313.77  3758.1  311.26    4054  309.12  4180.1  308.25
    4240  307.71  4298.9  307.25    4842  303.19  4866.9  303.75  4958.1  302.92
  4959.3  295.02  4959.8  294.52  4978.3  295.02  4979.3  298.82  5000.5  303.04
    5052  301.54  5175.8  302.96  5278.7  305.39  5415.1   303.1  5427.2  303.68
  5560.6  303.34  5761.4  307.03  5949.2  313.99  6205.3  327.72  6307.3  328.36
#Mann= 13 ,-1 , 0
    3215     .07       0    4054    .035       0  4180.1     .05       0
    4240    .035       0  4298.9     .05       0    4842     .07       0
  4866.9      .1       0  4959.3     .05       0  4978.3      .1       0
  5175.8     .12       0  5278.7     .05       0  5415.1     .12       0
  5427.2     .05       0
Bank Sta=4959.3,4978.3
XS Rating Curve= 0 ,0
Exp/Cntr=0.3,0.1

Type RM Length L Ch R = 1 ,4761    ,523,523,523
BEGIN DESCRIPTION:
JACK PUMP CREEK 4.0
END DESCRIPTION:
XS GIS Cut Line= 3
      2371524.98     13610174.96        2372575.       13611975.
      2373274.98     13612174.99
#Sta/Elev= 30
    2916  321.03  3244.7  313.42  3390.7  316.05  3442.4  311.81  3694.7  310.13
  3862.3  309.31  3978.3  308.65  4038.4  308.29  4534.9  303.17  4612.5  300.37
  4674.5  302.38  4976.8  302.43  4992.1  301.55    4997  293.06  5016.8  293.35
    5022  297.27  5046.3  292.68  5046.8  292.18  5065.3  292.68  5089.6  292.94
  5094.8  300.79  5103.9  301.94  5114.3  298.79  5128.6  302.34  5145.5  292.84
  5176.7  295.14  5187.1   303.4  5245.4  302.57  5467.9  304.12  5727.9  318.49
#Mann= 10 ,-1 , 0
    2916     .07       0  3694.7    .035       0  3862.3     .05       0
  3978.3     .07       0  4038.4     .05       0  4534.9     .07       0
  4674.5      .1       0  5046.3     .05       0  5065.3      .1       0
  5245.4     .05       0
Bank Sta=5046.3,5065.3
XS Rating Curve= 0 ,0
Exp/Cntr=0.3,0.1

Type RM Length L Ch R = 1 ,4238    ,676,676,676
BEGIN DESCRIPTION:
A19468
END DESCRIPTION:
XS GIS Cut Line= 4
      2371524.25     13610820.05      2372072.24     13611977.78
      2372550.78     13612317.39      2373446.07     13612255.65
#Sta/Elev= 30
    3655  312.02  3725.1  311.63  4274.8  309.54  4328.9  309.33  4385.3  309.21
  4476.1  308.75  4591.8  307.67  4695.9  306.52  4827.4  304.48  4978.2   301.9
  4986.9  300.32  4991.1  293.48  4991.6  292.98  5010.1  293.48  5013.9  297.68
  5022.5  298.32  5028.7  297.32  5037.3  299.45  5043.4  299.33  5049.6  301.06
  5064.3  302.13  5221.8  301.86    5287  300.33  5343.9  302.76  5527.3  301.98
  5617.1  300.24  5757.3  301.33  6028.1  306.94  6278.7  319.92  6420.1  323.05
#Mann= 12 ,-1 , 0
    3655    .035       0  3725.1     .07       0  4274.8     .05       0
  4328.9     .07       0  4385.3     .05       0  4476.1     .07       0
  4591.8     .05       0  4695.9     .07       0  4827.4     .12       0
  4991.1     .05       0  5010.1     .12       0  5757.3     .05       0
Bank Sta=4991.1,5010.1
XS Rating Curve= 0 ,0
Exp/Cntr=0.3,0.1

Type RM Length L Ch R = 1 ,3562    ,1211,1211,1211
BEGIN DESCRIPTION:
A19467
END DESCRIPTION:
XS GIS Cut Line= 4
      2371416.19      13610966.7      2371917.88     13612587.53
       2372350.1     13612680.15      2373460.72     13612294.52
#Sta/Elev= 30
  3041.1  309.84  3174.3  309.36    3237  308.96  3362.4  308.53  3395.6  308.26
  3466.5  307.98  3613.2  307.56    3819  306.77  3860.4  306.27  4003.9  304.48
  4172.6  301.64    4485  300.62  4677.5  301.59  4737.8  298.85  4794.2  301.47
  4970.1  301.54  4980.3  300.77  4991.2  293.03  4991.7  292.53  5010.3  293.03
    5011   296.7  5021.2  299.73  5036.2  297.99  5051.9  300.69  5325.8  300.35
  5542.9  299.99  5697.1  302.66  5916.3  307.65  6254.2  321.94  6355.5  323.05
#Mann= 15 ,-1 , 0
  3041.1     .07       0  3174.3     .05       0    3237     .07       0
  3362.4     .05       0  3395.6     .07       0  3466.5     .05       0
  3613.2     .07       0    3819     .05       0  3860.4     .07       0
  4003.9     .12       0    4485      .1       0  4991.2     .05       0
  5010.3      .1       0  5325.8     .12       0  5697.1     .05       0
Bank Sta=4991.2,5010.3
XS Rating Curve= 0 ,0
Exp/Cntr=0.3,0.1

Type RM Length L Ch R = 1 ,2351    ,548,548,548
BEGIN DESCRIPTION:
JACK PUMP CREEK 3.0
END DESCRIPTION:
XS GIS Cut Line= 3
      2370074.95     13613325.01        2371675.       13613125.
      2373475.03     13612324.99
#Sta/Elev= 30
  3383.4  330.57  3824.4  311.45  4036.4  306.45  4723.8  301.05  4804.4   302.7
  4877.2  298.75  4905.2  297.42  4975.7  300.25  4981.4  291.74  4981.9  291.24
  5005.4  291.74  5010.3  298.73  5017.8   299.8  5072.5   298.7  5236.6  301.53
  5370.8  300.84  5494.3  301.69  5838.5  302.79  5867.9  301.82  5966.3  301.87
  6116.9  300.53  6400.2  305.12  6423.6  305.82  6487.6  307.33  6580.6  311.87
  6609.3  311.91  6731.1  318.49  6783.1  319.19  6876.1  322.57  6965.7  323.34
#Mann= 10 ,-1 , 0
  3383.4    .035       0  4036.4     .07       0  4877.2      .1       0
  4981.4     .05       0  5005.4      .1       0  5370.8     .12       0
  5494.3      .1       0  5966.3     .05       0  6400.2     .12       0
  6423.6     .05       0
Bank Sta=4981.4,5005.4
XS Rating Curve= 0 ,0
Exp/Cntr=0.3,0.1

Type RM Length L Ch R = 1 ,1803    ,581,581,581
BEGIN DESCRIPTION:
JACK PUMP CREEK 2.0
END DESCRIPTION:
XS GIS Cut Line= 3
      2370174.96       13613675.        2371775.       13613625.
      2373325.04     13612474.97
#Sta/Elev= 30
  3410.8  324.06  3490.9  320.96  3500.9  317.16  3573.4  318.54  3610.9  315.59
  3981.1  305.71  4361.3  300.68  4759.6   301.1  4871.6  301.03  4931.6  297.82
  4971.6  299.85  4981.6  299.29  5001.6  294.05  5006.9  290.16  5007.4  289.66
  5030.9  290.16  5033.6   299.4    5190  298.06  5252.4  299.72  5296.1  299.81
  5463.1  301.28    5479   301.2  5604.2  301.68  5631.5   301.4  6054.4  301.89
  6533.7  305.67  6663.1  310.71  6698.6   309.5  6798.7  315.66  6941.7  319.93
#Mann= 11 ,-1 , 0
  3410.8     .07       0  4759.6      .1       0  5006.9     .05       0
  5030.9      .1       0  5252.4     .07       0  5296.1     .12       0
  5463.1     .07       0    5479     .12       0  5604.2     .05       0
  5631.5     .07       0  6054.4     .05       0
Bank Sta=5006.9,5030.9
XS Rating Curve= 0 ,0
Exp/Cntr=0.3,0.1

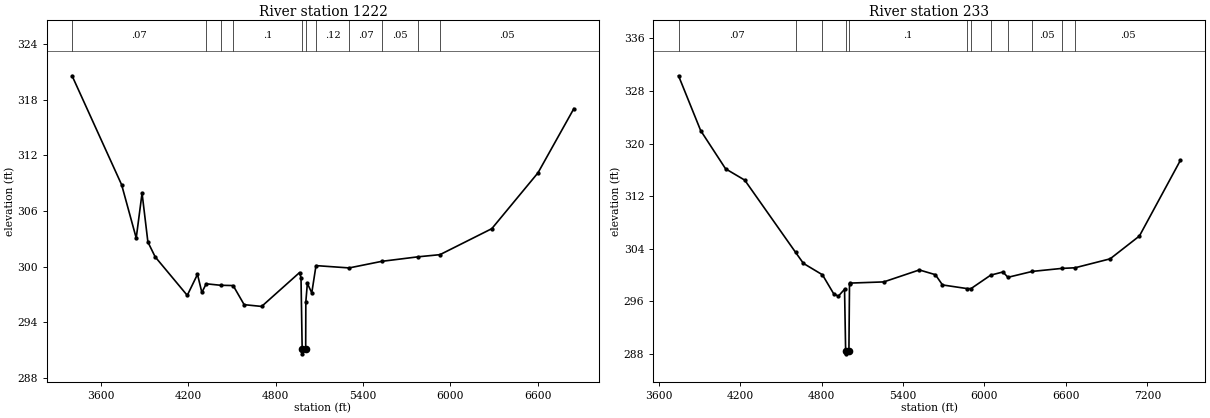
Type RM Length L Ch R = 1 ,1222    ,989,989,989
BEGIN DESCRIPTION:
JACK PUMP CREEK 1.0
END DESCRIPTION:
XS GIS Cut Line= 3
      2370325.01       13613975.        2371925.       13614075.
        2373475.       13613075.
#Sta/Elev= 30
  3401.3  320.59  3741.9  308.84  3842.1   303.1  3882.2  307.94  3922.3  302.67
  3972.4  301.07  4192.8  296.92    4263  299.19    4293  297.24  4323.1  298.17
  4421.5  298.01    4508  297.98  4583.6  295.92  4703.8  295.73  4964.3  299.38
  4974.3  298.83  4982.3  291.12  4982.8  290.62  5006.4  291.12  5007.4  296.22
  5017.9  298.21  5048.3  297.19  5077.3  300.13  5305.1  299.88  5529.2  300.59
  5779.8  301.08  5929.1  301.31  6285.1  304.11  6602.5  310.13    6849  317.05
#Mann= 11 ,-1 , 0
  3401.3     .07       0  4323.1     .12       0  4421.5     .07       0
    4508      .1       0  4982.3     .05       0  5006.4      .1       0
  5077.3     .12       0  5305.1     .07       0  5529.2     .05       0
  5779.8     .07       0  5929.1     .05       0
Bank Sta=4982.3,5006.4
XS Rating Curve= 0 ,0
Exp/Cntr=0.3,0.1

Type RM Length L Ch R = 1 ,233     ,0,0,0
BEGIN DESCRIPTION:
A19466
END DESCRIPTION:
XS GIS Cut Line= 4
      2370080.89     13614609.73      2371694.05     13614416.77
      2372064.52     13614216.09      2373460.77     13613336.69
#Sta/Elev= 30
  3746.6  330.31  3909.8  321.97  4093.2  316.16  4234.2  314.44    4609  303.45
  4666.3  301.78  4806.7  300.04  4888.8  297.18  4923.6  296.78  4969.4  297.85
  4977.4  288.52  4977.9  288.02  5001.6  288.52  5005.9  298.65    5011  298.78
  5258.1  298.96  5520.2  300.78  5638.5  300.06  5690.8   298.5  5873.6  297.94
  5901.5  297.95  6046.1  299.99  6135.9  300.47    6173  299.66  6353.2  300.56
  6568.2  301.01  6667.4  301.11  6925.8  302.47  7141.3  305.94  7442.7  317.43
#Mann= 12 ,-1 , 0
  3746.6     .07       0    4609     .12       0  4806.7      .1       0
  4977.4     .05       0  5001.6      .1       0  5873.6     .12       0
  5901.5      .1       0  6046.1     .12       0    6173     .07       0
  6353.2     .05       0  6568.2     .07       0  6667.4     .05       0
Bank Sta=4977.4,5001.6
XS Rating Curve= 0 ,0
Exp/Cntr=0.3,0.1

Chan Stop Cuts=-1
Use User Specified Reach Order=0
Composite Channel Slope=5