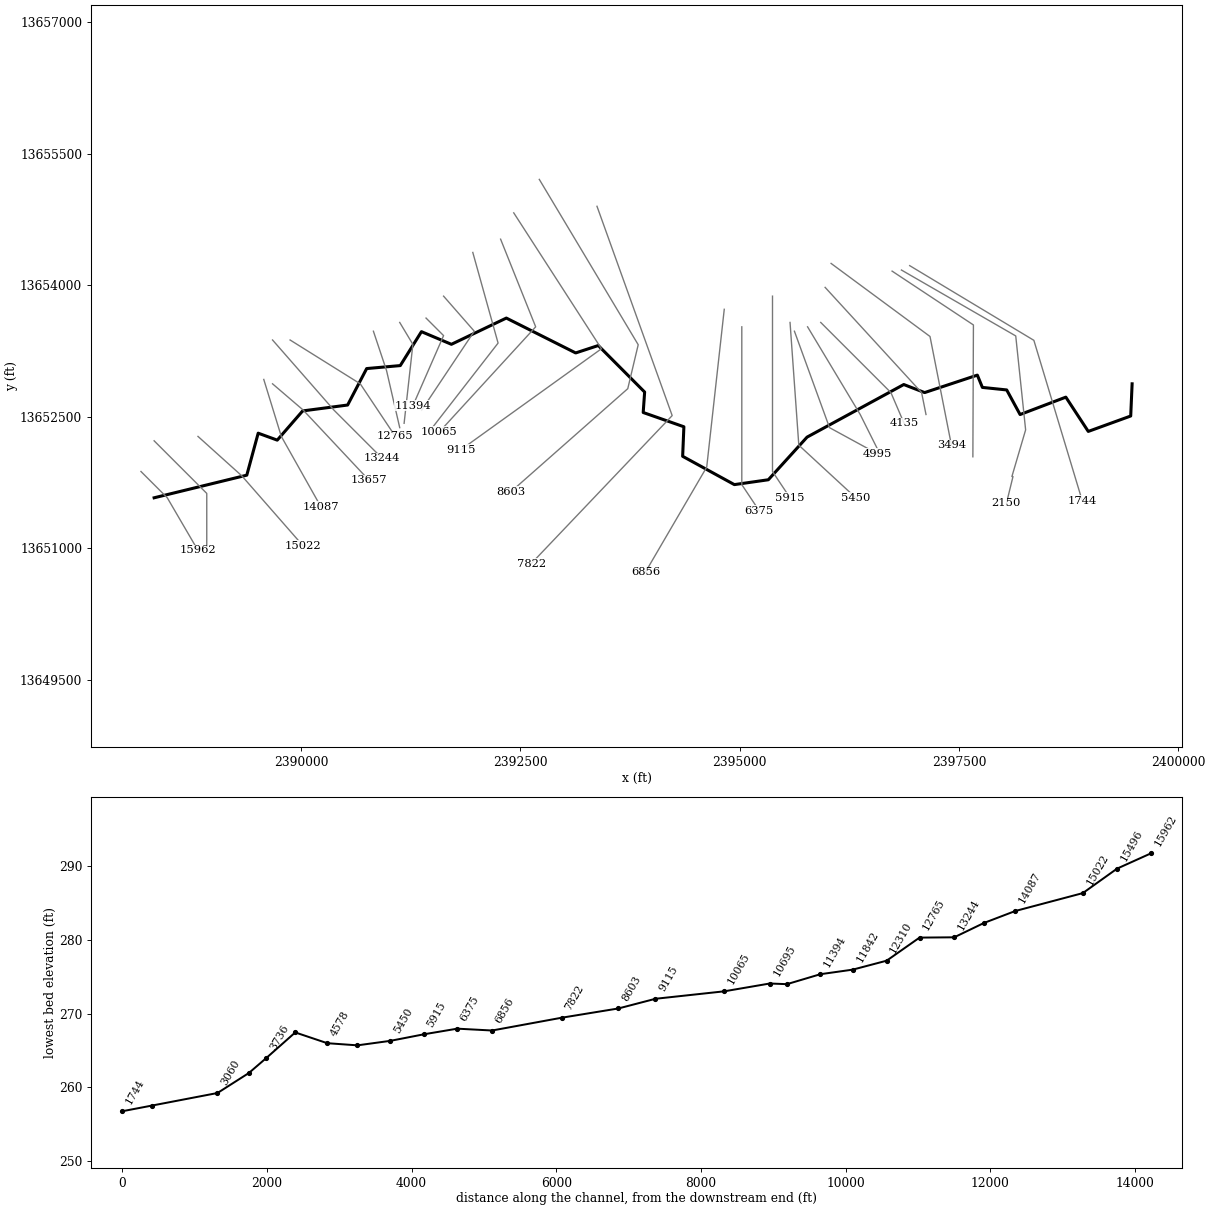
--- LITTLE ELM CREEK.prj (project) ---

Proj Title=LITTLE ELM CREEK Base Level Engineering
Current Plan=p01
Default Exp/Contr=0.3,0.1
English Units
Geom File=g01
Flow File=f01
Plan File=p01
Y Axis Title=Elevation
X Axis Title(PF)=Main Channel Distance
X Axis Title(XS)=Station
BEGIN DESCRIPTION:
LITTLE ELM CREEK
END DESCRIPTION:
DSS Export Rating Curves= 0
DSS Export Rating Curve Sorted= 0
DSS Export Volume Flow Curves= 0
DXF OffsetX= 0
DXF OffsetY= 0
DXF ScaleX= 1
DXF ScaleY= 10

--- LITTLE ELM CREEK.p01 (plan) ---

Plan Title=Multiple Run
Short Identifier=Multiple
Geom File=g01
Flow File=f01
Subcritical Flow
K Sum by GR= 0
Std Step Tol= 0.01
Critical Tol= 0.01
Num of Std Step Trials= 20
Max Error Tol= 0.3
Flow Tol Ratio= 0.001
Split Flow NTrial= 30
Split Flow Tol= 0.02
Split Flow Ratio= 0.02
Log Output Level= 0
Friction Slope Method= 1
Unsteady Friction Slope Method= 2
Unsteady Bridges Friction Slope Method= 1
Parabolic Critical Depth
Global Vel Dist=  1 , 1 , 1
Global Log Level= 0
CheckData=True
Encroach Param= -1, 0, 0, 0
BEGIN DESCRIPTION:
Multiple Run
END DESCRIPTION:

--- LITTLE ELM CREEK.f01 (steady flow) ---

Flow Title=Multiple
Number of Profiles=7
Profile Names=10-year,25-year,50-year,1pct_min,100-year,1pct_plu,500-year
River Rch & RM= LITTLE ELM CREEK,Reach-1,15962
     655    1059    1424     927    1850    3691    3094
River Rch & RM= LITTLE ELM CREEK,Reach-1,15022
     828    1346    1816    1185    2364    4716    3970
River Rch & RM= LITTLE ELM CREEK,Reach-1,6375
    1334    2213    3025    1995    3980    7940    6834
Boundary for River Rch & Prof#=LITTLE ELM CREEK,Reach-1,1
Up Type=0
Dn Type=3
Dn Slope=0.005
Boundary for River Rch & Prof#=LITTLE ELM CREEK,Reach-1,2
Up Type=0
Dn Type=3
Dn Slope=0.005
Boundary for River Rch & Prof#=LITTLE ELM CREEK,Reach-1,3
Up Type=0
Dn Type=3
Dn Slope=0.005
Boundary for River Rch & Prof#=LITTLE ELM CREEK,Reach-1,4
Up Type=0
Dn Type=3
Dn Slope=0.005
Boundary for River Rch & Prof#=LITTLE ELM CREEK,Reach-1,5
Up Type=0
Dn Type=3
Dn Slope=0.005
Boundary for River Rch & Prof#=LITTLE ELM CREEK,Reach-1,6
Up Type=0
Dn Type=3
Dn Slope=0.005
Boundary for River Rch & Prof#=LITTLE ELM CREEK,Reach-1,7
Up Type=0
Dn Type=3
Dn Slope=0.005

--- LITTLE ELM CREEK.g01 (geometry) ---

Geom Title=Existing Conditions
Program Version=4.10

River Reach=LITTLE ELM CREEK,Reach-1
Reach XY= 30
        2388325.       13651575.      2389381.34     13651833.02
      2389511.35     13652312.05      2389728.69     13652232.65
      2390018.27     13652565.85      2390531.07     13652633.13
      2390748.11     13653048.99      2391131.34     13653083.02
      2391372.69     13653469.92      2391714.25     13653325.68
      2392340.42     13653624.97      2393130.93     13653227.23
      2393388.68     13653311.73      2393917.24     13652781.17
      2393900.91     13652547.86      2394364.68     13652385.18
      2394350.69     13652048.24      2394940.27     13651725.37
      2395327.55     13651780.72      2395768.93     13652266.89
      2396871.68     13652866.96      2397109.61     13652775.09
      2397710.56     13652974.22      2397767.94       13652834.
      2398045.13     13652805.24      2398197.75     13652524.61
      2398719.35     13652723.03      2398975.21     13652331.98
      2399458.97     13652507.85        2399475.       13652875.

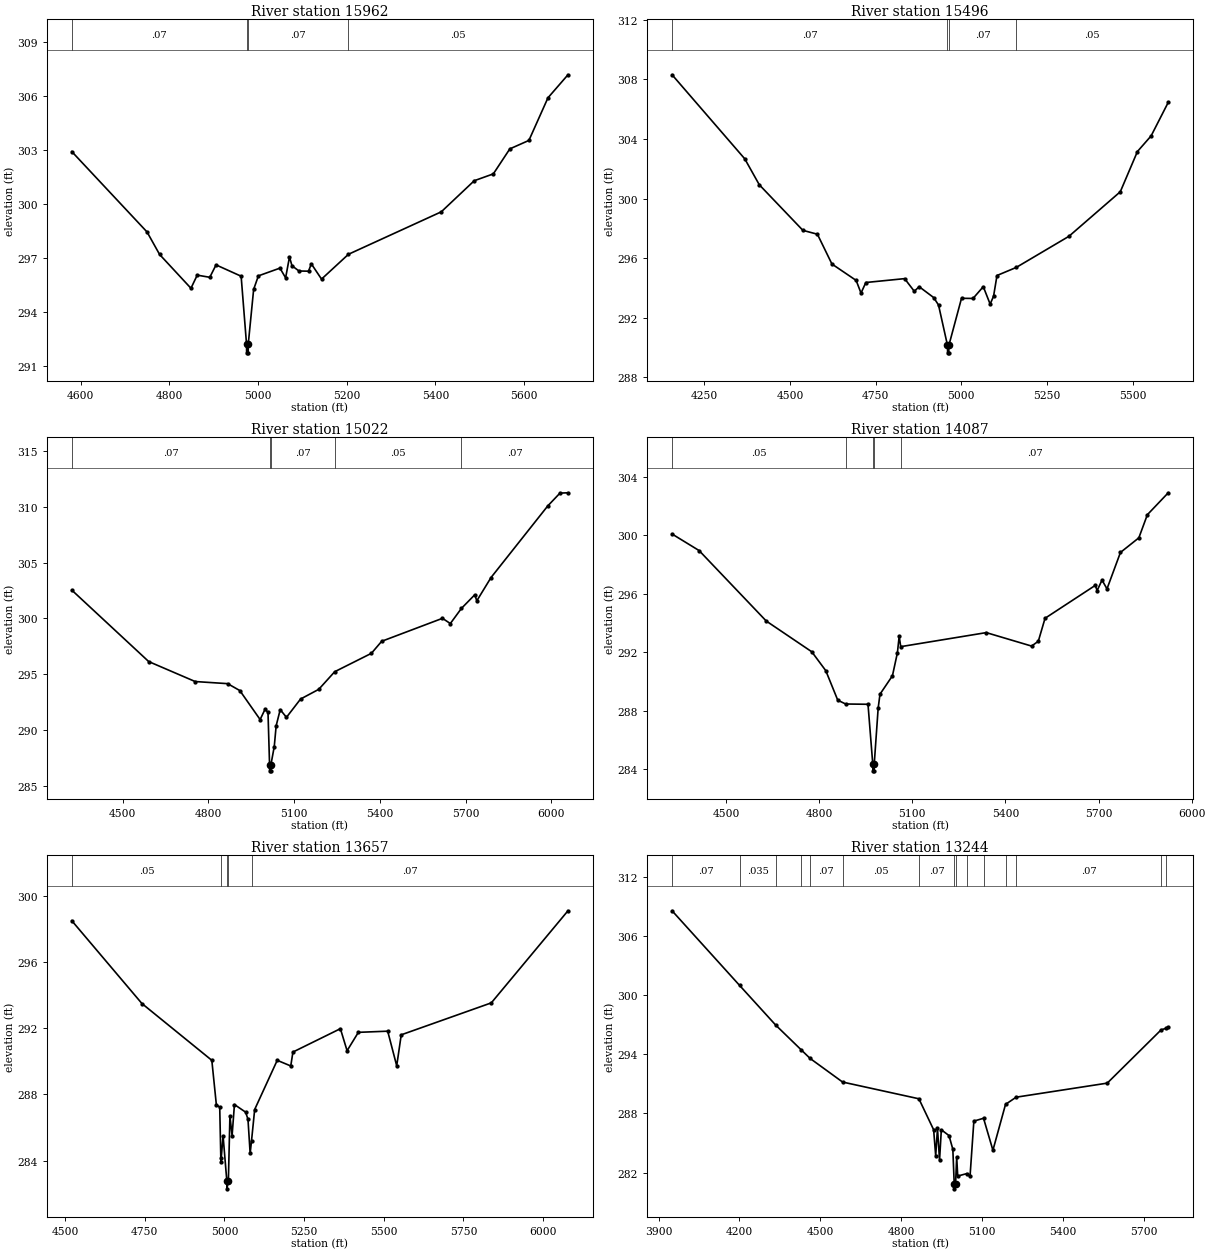
Type RM Length L Ch R = 1 ,15962   ,466,466,466
BEGIN DESCRIPTION:
LITTLE ELM CREEK 29.0
END DESCRIPTION:
XS GIS Cut Line= 3
      2388174.98     13651875.02        2388475.       13651575.
      2388824.99     13650975.01
#Sta/Elev= 30
  4579.9   302.9  4749.6  298.43  4777.9  297.18  4848.6   295.3  4862.8  296.03
  4891.1  295.91  4905.2   296.6  4961.8  295.97  4973.9  292.21  4974.2  291.71
  4977.7  291.71  4977.9  292.21    4990  295.24  5000.7  295.99  5049.3  296.42
  5062.1  295.88  5070.8  297.04  5076.5  296.55  5092.3  296.26  5113.8  296.25
    5120  296.66  5143.1  295.81  5203.8  297.19  5413.1  299.55  5487.5  301.28
  5530.5  301.66  5567.7  303.05  5610.7  303.52  5653.7  305.89  5698.8  307.17
#Mann= 4 ,-1 , 0
  4579.9     .07       0  4973.9     .05       0  4977.9     .07       0
  5203.8     .05       0
Bank Sta=4973.9,4977.9
XS Rating Curve= 0 ,0
Exp/Cntr=0.3,0.1

Type RM Length L Ch R = 1 ,15496   ,474,474,474
BEGIN DESCRIPTION:
LITTLE ELM CREEK 28.0
END DESCRIPTION:
XS GIS Cut Line= 3
      2388324.97     13652225.03        2388925.       13651625.
        2388925.     13651024.97
#Sta/Elev= 30
  4155.7  308.31  4367.9  302.67  4410.3  300.93  4537.6  297.87    4580  297.61
  4622.4  295.61  4693.1  294.51  4707.3  293.66  4721.4  294.37  4834.6  294.63
  4862.9  293.78    4877  294.09  4919.4  293.36  4933.6  292.86  4959.8  290.15
  4960.1  289.65  4963.6  289.65  4963.8  290.15  5000.7  293.31  5034.3   293.3
  5064.3  294.09  5084.3  292.92  5094.3  293.45  5104.3  294.84  5160.4  295.38
  5314.3  297.47  5464.3  300.46  5514.3  303.16  5554.3  304.21  5604.3  306.46
#Mann= 4 ,-1 , 0
  4155.7     .07       0  4959.8     .05       0  4963.8     .07       0
  5160.4     .05       0
Bank Sta=4959.8,4963.8
XS Rating Curve= 0 ,0
Exp/Cntr=0.3,0.1

Type RM Length L Ch R = 1 ,15022   ,935,935,935
BEGIN DESCRIPTION:
LITTLE ELM CREEK 27.0
END DESCRIPTION:
XS GIS Cut Line= 3
      2388825.01       13652275.        2389325.       13651825.
      2390025.01     13651024.99
#Sta/Elev= 30
  4322.4  302.54  4591.5  296.13    4754  294.34  4867.6  294.15  4910.2  293.53
  4981.2  290.93  4998.4  291.85  5008.8  291.57  5014.3  286.83  5014.6  286.33
  5018.3  286.33  5018.6  286.83  5030.7  288.51  5037.3  290.37  5051.5  291.82
  5073.4  291.13  5122.7  292.77  5186.3  293.64  5242.1  295.22  5370.5  296.87
  5406.5  297.95  5619.1  300.01  5646.6  299.54  5685.4   300.9  5732.1  302.12
  5739.2  301.58    5789  303.67  5987.4  310.09  6030.1  311.24  6058.1  311.27
#Mann= 5 ,-1 , 0
  4322.4     .07       0  5014.3     .05       0  5018.6     .07       0
  5242.1     .05       0  5685.4     .07       0
Bank Sta=5014.3,5018.6
XS Rating Curve= 0 ,0
Exp/Cntr=0.3,0.1

Type RM Length L Ch R = 1 ,14087   ,430,430,430
BEGIN DESCRIPTION:
LITTLE ELM CREEK 26.0
END DESCRIPTION:
XS GIS Cut Line= 3
        2389575.     13652925.01        2389775.       13652275.
      2390225.02     13651474.97
#Sta/Elev= 30
  4326.6  300.09  4413.6  298.96    4630  294.14  4776.5  292.04  4821.6  290.75
  4860.2  288.73  4885.6  288.47  4957.6  288.45  4972.8   284.4  4973.2   283.9
  4977.4   283.9  4977.8   284.4  4990.3  288.18  4996.2  289.14  5036.3   290.4
  5052.3  291.97    5058   293.1    5063  292.39  5338.5  293.35  5484.4  292.43
  5506.1  292.76  5527.8  294.33  5689.7  296.58  5695.4  296.22  5711.3  296.94
  5727.3  296.34  5770.6  298.83  5829.9  299.83  5857.3  301.41  5924.6  302.91
#Mann= 5 ,-1 , 0
  4326.6     .05       0  4885.6     .12       0  4972.8     .05       0
  4977.8     .12       0    5063     .07       0
Bank Sta=4972.8,4977.8
XS Rating Curve= 0 ,0
Exp/Cntr=0.3,0.1

Type RM Length L Ch R = 1 ,13657   ,413,413,413
BEGIN DESCRIPTION:
LITTLE ELM CREEK 25.0
END DESCRIPTION:
XS GIS Cut Line= 3
        2389675.       13652875.        2390025.       13652575.
      2390775.02     13651774.98
#Sta/Elev= 30
  4520.7  298.48  4740.8  293.48  4960.3  290.05  4974.5  287.37  4985.1  287.22
  4988.8  283.91  4989.8  284.14  4995.6  285.49  5007.3  282.79  5007.6  282.29
  5012.3  282.79  5017.1   286.7  5023.9   285.5  5031.3  287.38  5066.4  286.92
  5073.8  286.49  5080.6  284.43    5085   285.2  5094.8  287.08  5165.6  290.05
  5208.1  289.71  5214.9  290.55  5363.9  291.96  5384.9  290.63  5420.3  291.74
  5512.4  291.81  5540.7  289.72  5554.9  291.59  5837.7  293.52  6078.3  299.08
#Mann= 5 ,-1 , 0
  4520.7     .05       0  4989.8     .12       0  5007.3     .05       0
  5012.3     .12       0    5085     .07       0
Bank Sta=5007.3,5012.3
XS Rating Curve= 0 ,0
Exp/Cntr=0.3,0.1

Type RM Length L Ch R = 1 ,13244   ,479,479,479
BEGIN DESCRIPTION:
LITTLE ELM CREEK 24.0
END DESCRIPTION:
XS GIS Cut Line= 3
      2389675.02     13653374.98        2390375.       13652575.
        2390925.       13652025.
#Sta/Elev= 30
  3950.2  308.59  4200.9     301  4334.5  296.98  4428.2  294.49  4462.2  293.59
  4582.8  291.19  4865.9  289.49  4920.6  286.34  4928.2   283.7  4934.9  286.48
  4942.5  283.25  4949.1  286.34  4977.6  285.75  4991.8  284.36  4996.9  280.84
  4997.3  280.34    5002  280.84  5006.1   283.6  5009.9  281.64    5044  281.89
  5055.6   281.6  5069.8  287.22  5105.7  287.51  5140.5  284.26  5187.3  288.92
  5226.6  289.65  5564.7  291.08  5764.5  296.49  5782.6  296.65    5791  296.76
#Mann= 15 ,-1 , 0
  3950.2     .07       0  4200.9    .035       0  4334.5     .07       0
  4428.2     .05       0  4462.2     .07       0  4582.8     .05       0
  4865.9     .07       0  4996.9     .05       0    5002     .07       0
    5044     .12       0  5105.7     .07       0  5187.3     .12       0
  5226.6     .07       0  5764.5     .05       0  5782.6     .12       0
Bank Sta=4996.9,5002
XS Rating Curve= 0 ,0
Exp/Cntr=0.3,0.1

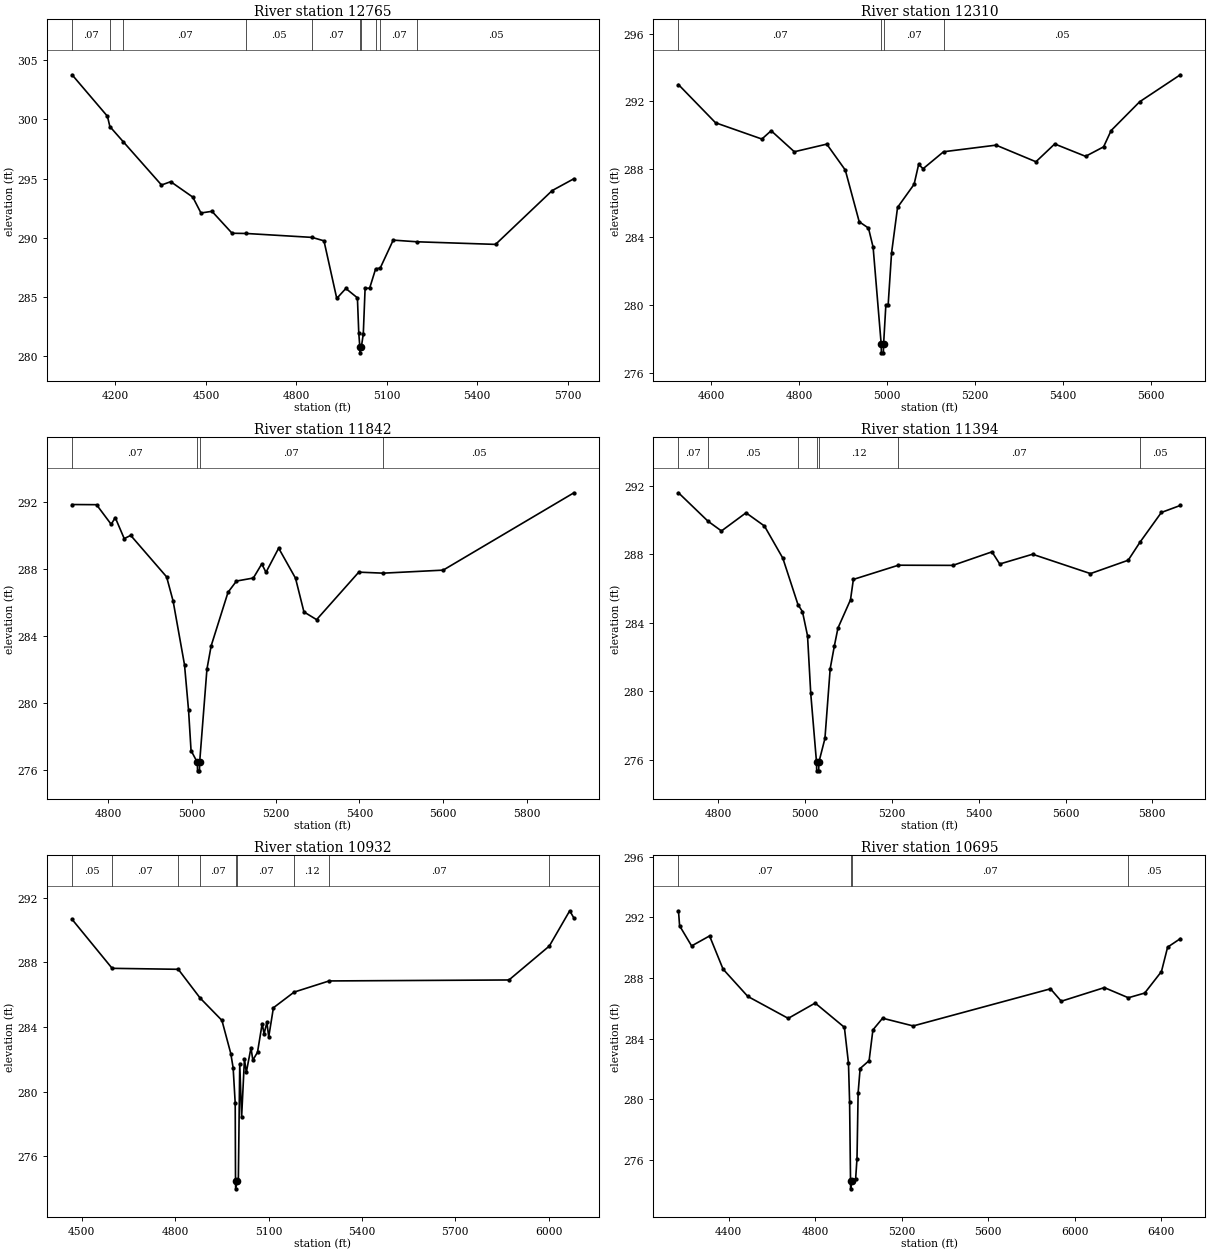
Type RM Length L Ch R = 1 ,12765   ,455,455,455
BEGIN DESCRIPTION:
LITTLE ELM CREEK 23.0
END DESCRIPTION:
XS GIS Cut Line= 3
        2389875.       13653375.        2390675.       13652875.
        2391075.     13652275.01
#Sta/Elev= 30
    4056  303.76  4173.3  300.26  4181.4  299.39  4225.1  298.13  4352.6  294.46
  4383.2  294.74  4456.4  293.44  4483.5   292.1    4520  292.24  4586.7  290.39
  4634.4  290.37  4852.1  290.04  4891.5  289.75  4933.9  284.89    4964  285.73
  5002.4  284.94  5006.9  281.98  5010.4   280.8  5010.8   280.3  5015.5   280.8
  5021.9  281.89  5027.9  285.74    5043  285.76  5062.9  287.39    5078  287.45
  5121.1  289.81  5199.7  289.67  5460.6  289.45  5648.4  293.99  5720.5  294.99
#Mann= 10 ,-1 , 0
    4056     .07       0  4181.4    .035       0  4225.1     .07       0
  4634.4     .05       0  4852.1     .07       0  5010.4     .05       0
  5015.5     .07       0  5062.9     .12       0    5078     .07       0
  5199.7     .05       0
Bank Sta=5010.4,5015.5
XS Rating Curve= 0 ,0
Exp/Cntr=0.3,0.1

Type RM Length L Ch R = 1 ,12310   ,468,468,468
BEGIN DESCRIPTION:
LITTLE ELM CREEK 22.0
END DESCRIPTION:
XS GIS Cut Line= 3
      2390825.01     13653474.97        2390975.       13653025.
        2391125.       13652375.
#Sta/Elev= 30
  4525.2  292.99  4609.5  290.74  4714.9  289.78    4736  290.27  4788.7  289.03
  4862.5  289.48  4904.6  287.95  4936.3   284.9  4957.3  284.53  4967.9   283.4
  4986.3  277.67  4986.7  277.17  4991.2  277.17  4991.7  277.67  4996.9     280
  5002.1     280  5009.8  283.05  5023.5  285.75  5061.1  287.11  5071.4  288.28
  5081.6  288.03  5128.1  289.03  5247.5  289.42  5338.2  288.44  5380.9  289.49
  5451.1  288.76  5492.1  289.32  5509.2  290.28  5574.2  291.98  5666.6  293.57
#Mann= 4 ,-1 , 0
  4525.2     .07       0  4986.3     .05       0  4991.7     .07       0
  5128.1     .05       0
Bank Sta=4986.3,4991.7
XS Rating Curve= 0 ,0
Exp/Cntr=0.3,0.1

Type RM Length L Ch R = 1 ,11842   ,448,448,448
BEGIN DESCRIPTION:
LITTLE ELM CREEK 21.0
END DESCRIPTION:
XS GIS Cut Line= 3
        2391125.       13653575.        2391275.       13653325.
        2391175.     13652424.99
#Sta/Elev= 30
  4714.4  291.83  4772.7  291.82  4807.7  290.65  4817.4  291.05  4838.8   289.8
  4854.3  289.99  4939.9  287.52  4955.4  286.08  4982.6  282.28  4992.3  279.56
  4998.2  277.17  5013.3  276.46  5013.7  275.96  5018.3  275.96  5018.7  276.46
  5036.1  282.02  5046.2  283.41  5086.4   286.6  5106.6  287.27  5146.8  287.45
  5166.9  288.29    5177  287.79  5207.2  289.23  5247.4  287.44  5267.5  285.43
  5297.7  284.97  5398.3   287.8  5456.5  287.74  5599.6  287.92  5911.5  292.53
#Mann= 4 ,-1 , 0
  4714.4     .07       0  5013.3     .05       0  5018.7     .07       0
  5456.5     .05       0
Bank Sta=5013.3,5018.7
XS Rating Curve= 0 ,0
Exp/Cntr=0.3,0.1

Type RM Length L Ch R = 1 ,11394   ,462,462,462
BEGIN DESCRIPTION:
LITTLE ELM CREEK 20.0
END DESCRIPTION:
XS GIS Cut Line= 3
      2391424.99     13653625.01        2391625.       13653425.
      2391274.99     13652624.97
#Sta/Elev= 30
  4708.4  291.58  4776.4  289.92  4807.4  289.35    4864  290.41  4906.4  289.64
  4948.8  287.76  4983.8  285.04    4994  284.64  5005.7  283.23  5013.1  279.86
  5026.4  275.84  5026.8  275.34  5031.4  275.34  5031.8  275.84  5045.8  277.23
  5057.9  281.31  5067.7  282.66  5075.8  283.68  5104.7  285.33  5111.3  286.52
  5215.1  287.35  5340.5  287.34  5430.6  288.13  5448.5  287.42  5524.1  287.99
  5657.5  286.86  5744.4  287.64  5771.5  288.69  5820.8  290.43  5864.5  290.84
#Mann= 7 ,-1 , 0
  4708.4     .07       0  4776.4     .05       0  4983.8     .12       0
  5026.4     .05       0  5031.8     .12       0  5215.1     .07       0
  5771.5     .05       0
Bank Sta=5026.4,5031.8
XS Rating Curve= 0 ,0
Exp/Cntr=0.3,0.1

Type RM Length L Ch R = 1 ,10932   ,237,237,237
BEGIN DESCRIPTION:
LITTLE ELM CREEK 19.0
END DESCRIPTION:
XS GIS Cut Line= 3
      2391624.99     13653875.01        2391975.       13653475.
      2391374.99     13652574.99
#Sta/Elev= 30
  4468.5  290.66  4597.3  287.63  4809.9  287.57  4880.2  285.79  4950.2  284.41
  4978.7  282.36  4986.3  281.47  4992.9  279.29  4993.9  274.49  4994.4  273.99
  4999.4  274.49    5003  274.49  5007.5  281.74  5013.5  278.42  5022.6  282.02
  5028.6   281.2  5043.6  282.71  5049.6  281.95  5064.6  282.44  5079.6  284.21
  5085.7  283.58  5094.7  284.28  5100.7  283.39  5115.7  285.19  5182.3  286.16
  5294.8  286.85  5872.9  286.91  6002.7  289.01  6068.2  291.19  6081.7  290.74
#Mann= 9 ,-1 , 0
  4468.5     .05       0  4597.3     .07       0  4809.9     .05       0
  4880.2     .07       0  4993.9     .05       0  4999.4     .07       0
  5182.3     .12       0  5294.8     .07       0  6002.7     .05       0
Bank Sta=4993.9,4999.4
XS Rating Curve= 0 ,0
Exp/Cntr=0.3,0.1

Type RM Length L Ch R = 1 ,10695   ,630,630,630
BEGIN DESCRIPTION:
A19687
END DESCRIPTION:
XS GIS Cut Line= 3
      2391958.17     13654373.43      2392246.36      13653339.7
      2391482.04     13652356.11
#Sta/Elev= 30
  4168.8  292.43    4174  291.44  4229.5  290.11  4312.5  290.77  4374.8  288.58
    4489  286.78  4675.9  285.33  4800.4  286.34  4935.4  284.74  4954.3  282.37
  4959.5  279.81  4963.8  274.58  4964.2  274.08  4969.3  274.58  4987.3  274.73
  4993.7  276.08  4998.9  280.42  5008.1  282.02  5049.6  282.54  5067.2  284.57
  5111.9  285.34  5253.3  284.83  5887.7  287.28  5937.5  286.46  6136.6  287.36
  6247.4  286.69    6323     287  6400.4  288.42  6428.9  290.03  6487.6  290.59
#Mann= 4 ,-1 , 0
  4168.8     .07       0  4963.8     .05       0  4969.3     .07       0
  6247.4     .05       0
Bank Sta=4963.8,4969.3
XS Rating Curve= 0 ,0
Exp/Cntr=0.3,0.1

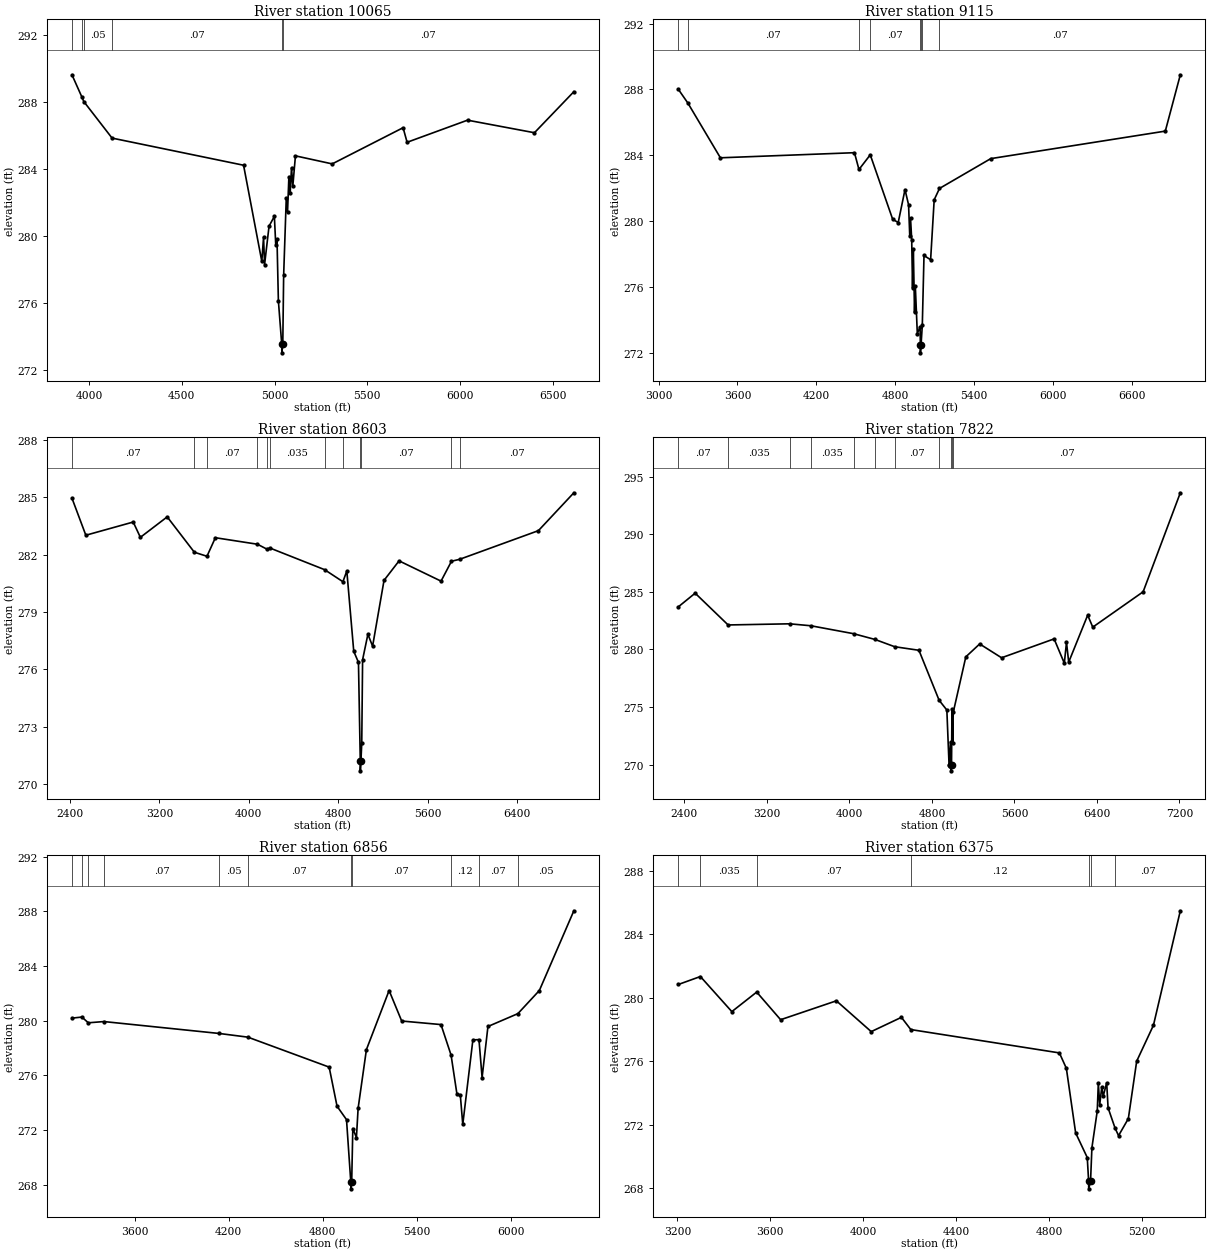
Type RM Length L Ch R = 1 ,10065   ,950,950,950
BEGIN DESCRIPTION:
LITTLE ELM CREEK 18.0
END DESCRIPTION:
XS GIS Cut Line= 3
      2392274.99     13654525.02        2392675.       13653525.
      2391575.02     13652325.02
#Sta/Elev= 30
  3908.3  289.62  3961.5   288.3  3972.3  288.02  4124.5  285.84  4833.2  284.22
  4931.5  278.48  4940.9  279.93  4946.3  278.28  4970.5  280.58  4999.2  281.17
  5006.6  279.47  5013.4   279.8  5020.8  276.13    5039  273.52  5039.5  273.02
  5044.5  273.52  5049.2  277.64  5063.4  282.28  5070.1  281.42  5077.5  283.54
  5084.3  282.56  5091.7  284.08  5098.5  282.96  5112.7  284.78  5310.9   284.3
  5692.9  286.46  5714.5  285.59  6040.1  286.91  6400.8  286.16  6613.2  288.61
#Mann= 6 ,-1 , 0
  3908.3     .05       0  3961.5     .07       0  3972.3     .05       0
  4124.5     .07       0    5039     .05       0  5044.5     .07       0
Bank Sta=5039,5044.5
XS Rating Curve= 0 ,0
Exp/Cntr=0.3,0.1

Type RM Length L Ch R = 1 ,9115    ,512,512,512
BEGIN DESCRIPTION:
LITTLE ELM CREEK 17.0
END DESCRIPTION:
XS GIS Cut Line= 3
      2392424.98     13654825.03        2393425.       13653275.
      2391825.03     13652125.02
#Sta/Elev= 30
    3151     288  3222.3  287.18  3470.1  283.85  4489.1  284.16  4523.3  283.14
  4609.2  284.03  4779.5  280.12  4821.7  279.92  4873.2  281.92  4900.4     281
  4909.5  279.09  4915.4  280.18  4924.2  278.89  4930.6  275.95  4936.6   278.3
  4945.8  274.46  4951.7  276.07  4966.9  273.18    4988  273.59  4989.9  272.51
  4990.3  272.01  4995.5  272.51  5004.8  273.69  5017.7  277.92    5068  277.66
  5095.1   281.3  5135.5  281.99  5525.2   283.8  6851.9  285.47    6966  288.89
#Mann= 8 ,-1 , 0
    3151     .05       0  3222.3     .07       0  4523.3     .05       0
  4609.2     .07       0  4989.9     .05       0  4995.5     .07       0
  5004.8     .12       0  5135.5     .07       0
Bank Sta=4989.9,4995.5
XS Rating Curve= 0 ,0
Exp/Cntr=0.3,0.1

Type RM Length L Ch R = 1 ,8603    ,781,781,781
BEGIN DESCRIPTION:
A19686
END DESCRIPTION:
XS GIS Cut Line= 4
      2392716.26     13655206.71      2393843.98     13653320.91
      2393724.94     13652819.69      2392390.44     13651641.82
#Sta/Elev= 30
  2416.6  284.96  2540.9  283.02  2964.9  283.71  3029.1  282.91  3269.2  283.98
  3512.3  282.13  3625.1  281.92  3700.3  282.89  4076.4  282.55  4159.3   282.3
  4189.2  282.35  4677.8  281.22  4841.8  280.59  4876.9  281.15  4938.9  276.95
  4981.1  276.37  4997.4   271.2  4997.9   270.7    5003   271.2  5010.5  272.13
  5018.1  276.51  5065.5  277.84  5107.7  277.22  5209.9  280.66  5344.6  281.68
  5720.2  280.62  5813.7  281.66  5886.2  281.76  6591.9  283.26    6909  285.24
#Mann= 12 ,-1 , 0
  2416.6     .07       0  3512.3    .035       0  3625.1     .07       0
  4076.4    .035       0  4159.3     .05       0  4189.2    .035       0
  4677.8     .05       0  4841.8     .07       0  4997.4     .05       0
    5003     .07       0  5813.7     .12       0  5886.2     .07       0
Bank Sta=4997.4,5003
XS Rating Curve= 0 ,0
Exp/Cntr=0.3,0.1

Type RM Length L Ch R = 1 ,7822    ,966,966,966
BEGIN DESCRIPTION:
LITTLE ELM CREEK 16.0
END DESCRIPTION:
XS GIS Cut Line= 3
      2393374.09     13654899.75      2394231.27     13652512.71
      2392624.99     13650824.99
#Sta/Elev= 30
  2342.3   283.7  2504.6  284.88  2824.2  282.12  3419.8  282.22    3627  282.05
  4041.3  281.36  4248.5  280.86  4439.1  280.23  4674.3  279.92  4869.9  275.58
  4944.9  274.73  4966.3  269.97  4980.4  271.98  4984.6  269.95    4985  269.45
  4990.2  269.95  4994.6   274.8  5001.5  271.89  5006.8  274.53  5128.9  279.35
  5263.2  280.47  5475.5  279.27  5984.8  280.91  6083.8   278.8  6104.9  280.61
  6126.3  278.89  6310.3  282.97  6359.7  281.93  6847.9     285  7208.5   293.6
#Mann= 11 ,-1 , 0
  2342.3     .07       0  2824.2    .035       0  3419.8     .05       0
    3627    .035       0  4041.3     .07       0  4248.5     .05       0
  4439.1     .07       0  4869.9     .12       0  4984.6     .05       0
  4990.2     .12       0  5006.8     .07       0
Bank Sta=4984.6,4990.2
XS Rating Curve= 0 ,0
Exp/Cntr=0.3,0.1

Type RM Length L Ch R = 1 ,6856    ,481,481,481
BEGIN DESCRIPTION:
LITTLE ELM CREEK 15.0
END DESCRIPTION:
XS GIS Cut Line= 3
        2394825.     13653724.97        2394625.       13651925.
        2393925.     13650724.99
#Sta/Elev= 30
  3200.9  280.19  3264.1  280.27  3305.2  279.85  3404.7  279.94  4139.7  279.07
  4322.8   278.8  4840.9  276.61  4891.2  273.75  4951.6  272.77  4978.9  268.21
  4979.4  267.71  4984.6  268.21  4991.8  272.12  5014.8  271.46  5025.6   273.6
  5078.5  277.89  5223.2  282.21  5303.4  279.98    5554  279.72  5618.3  277.49
  5655.7  274.64  5677.2  274.57  5692.9  272.42  5757.4   278.6  5796.2  278.62
  5816.1  275.85  5853.4  279.58  6044.4  280.52  6181.2  282.21  6401.2  288.04
#Mann= 11 ,-1 , 0
  3200.9     .07       0  3264.1     .12       0  3305.2    .035       0
  3404.7     .07       0  4139.7     .05       0  4322.8     .07       0
  4978.9     .05       0  4984.6     .07       0  5618.3     .12       0
  5796.2     .07       0  6044.4     .05       0
Bank Sta=4978.9,4984.6
XS Rating Curve= 0 ,0
Exp/Cntr=0.3,0.1

Type RM Length L Ch R = 1 ,6375    ,460,460,460
BEGIN DESCRIPTION:
LITTLE ELM CREEK 14.0
END DESCRIPTION:
XS GIS Cut Line= 3
        2395025.     13653525.04        2395025.       13651725.
        2395225.       13651425.
#Sta/Elev= 30
  3204.5  280.83  3299.1  281.33  3434.5  279.12  3541.5  280.35  3644.5  278.61
  3884.5   279.8  4034.5  277.86  4164.5  278.76  4204.8  277.99  4844.5  276.52
  4874.5  275.55  4914.5  271.48  4964.5  269.93  4970.3  268.46  4970.8  267.96
  4978.7  268.46  4984.5  270.55  5007.5  272.86  5012.1  274.62  5018.1  273.26
  5027.1  274.38  5033.1  273.79  5048.1  274.64  5054.1  273.06  5084.3  271.78
  5099.2  271.31  5141.3  272.38  5177.3     276  5249.4  278.26  5365.1  285.47
#Mann= 7 ,-1 , 0
  3204.5     .07       0  3299.1    .035       0  3541.5     .07       0
  4204.8     .12       0  4970.3     .05       0  4978.7     .12       0
  5084.3     .07       0
Bank Sta=4970.3,4978.7
XS Rating Curve= 0 ,0
Exp/Cntr=0.3,0.1

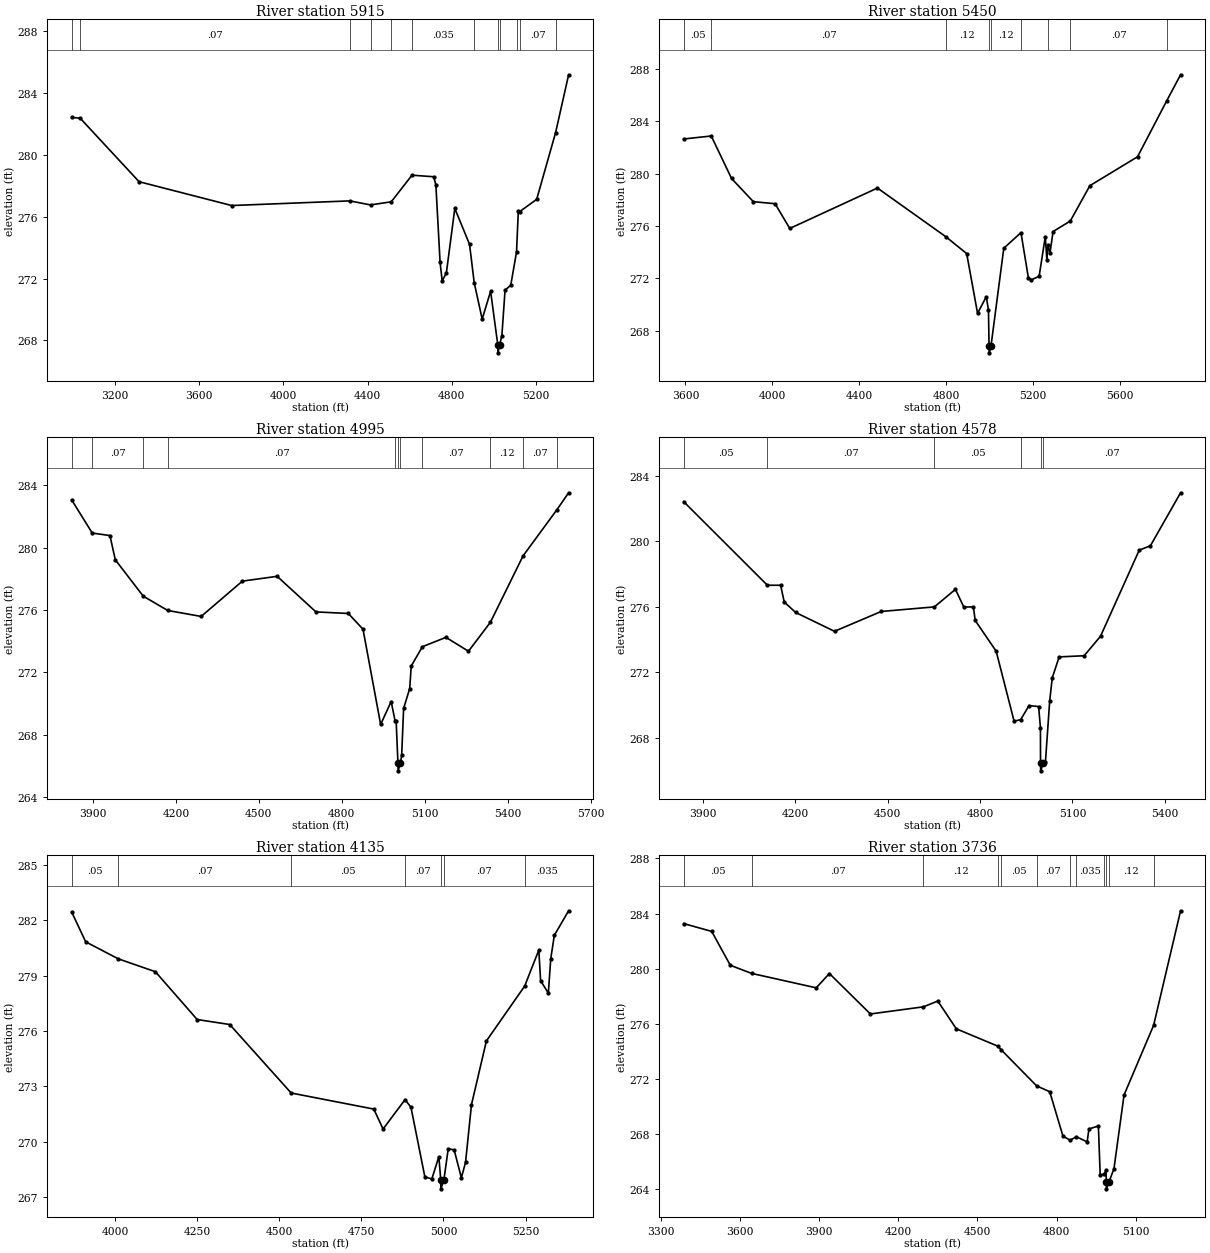
Type RM Length L Ch R = 1 ,5915    ,465,465,465
BEGIN DESCRIPTION:
LITTLE ELM CREEK 13.0
END DESCRIPTION:
XS GIS Cut Line= 3
        2395375.     13653875.05        2395375.       13651875.
        2395575.       13651575.
#Sta/Elev= 30
  2994.2  282.42  3034.7  282.36  3314.2  278.26  3754.2  276.72  4315.2  277.02
  4413.7  276.76  4512.2  276.96  4610.7  278.68  4714.2  278.58  4724.2  278.05
  4744.2  273.06  4754.2  271.84  4774.2  272.38  4814.2  276.53  4884.2  274.21
  4906.2  271.74  4944.2  269.38  4984.2  271.18  5018.5   267.7    5019   267.2
    5027   267.7  5037.8  268.32  5052.8  271.25  5079.9  271.57  5107.4  273.72
  5115.9  276.39  5122.7  276.33  5203.1  277.12  5292.9  281.43  5354.8  285.17
#Mann= 12 ,-1 , 0
  2994.2     .12       0  3034.7     .07       0  4315.2     .12       0
  4413.7     .07       0  4512.2     .12       0  4610.7    .035       0
  4906.2     .12       0  5018.5     .05       0    5027     .12       0
  5107.4    .035       0  5122.7     .07       0  5292.9    .035       0
Bank Sta=5018.5,5027
XS Rating Curve= 0 ,0
Exp/Cntr=0.3,0.1

Type RM Length L Ch R = 1 ,5450    ,455,455,455
BEGIN DESCRIPTION:
LITTLE ELM CREEK 12.0
END DESCRIPTION:
XS GIS Cut Line= 3
        2395575.       13653575.        2395675.       13652175.
      2396325.03     13651574.97
#Sta/Elev= 30
  3591.7  282.66  3718.8  282.89  3812.3  279.64  3912.5  277.87  4012.8  277.71
  4080.4  275.82    4484  278.91  4798.8  275.19    4895   273.9  4945.1  269.33
  4985.2   270.6  4995.3  269.59    4998  266.81  4998.5  266.31  5006.8  266.81
  5065.9  274.31    5145   275.5  5179.3  272.02  5193.4   271.9  5228.6  272.16
    5257   275.2  5264.3  273.39  5269.2  274.56  5278.5  273.92  5292.7  275.58
  5372.2  276.39  5462.2  279.09  5681.7   281.3  5815.8  285.57  5879.9  287.57
#Mann= 9 ,-1 , 0
  3591.7     .05       0  3718.8     .07       0  4798.8     .12       0
    4998     .05       0  5006.8     .12       0    5145     .07       0
  5269.2     .12       0  5372.2     .07       0  5815.8    .035       0
Bank Sta=4998,5006.8
XS Rating Curve= 0 ,0
Exp/Cntr=0.3,0.1

Type RM Length L Ch R = 1 ,4995    ,417,417,417
BEGIN DESCRIPTION:
LITTLE ELM CREEK 11.0
END DESCRIPTION:
XS GIS Cut Line= 3
      2395625.01     13653474.98        2396025.       13652375.
      2396574.96     13652075.02
#Sta/Elev= 30
  3823.3  283.05  3897.6  280.93  3961.6  280.77  3980.9  279.22  4081.9  276.89
  4170.6  275.97  4291.5  275.59  4440.4  277.85  4566.1  278.16  4706.5  275.88
  4823.5  275.78  4876.7  274.77  4940.5  268.67  4978.5  270.14  4992.9  268.88
  4996.6  268.88    5003   266.2  5003.5   265.7  5012.1   266.2  5016.5   266.7
  5023.6   269.7  5045.5  270.97  5051.2  272.42  5091.5  273.65  5176.5  274.25
  5258.1  273.36  5337.5  275.22  5455.2  279.46  5578.1  282.43  5620.2  283.51
#Mann= 11 ,-1 , 0
  3823.3     .05       0  3897.6     .07       0  4081.9     .05       0
  4170.6     .07       0  4992.9     .12       0    5003     .05       0
  5012.1     .12       0  5091.5     .07       0  5337.5     .12       0
  5455.2     .07       0  5578.1    .035       0
Bank Sta=5003,5012.1
XS Rating Curve= 0 ,0
Exp/Cntr=0.3,0.1

Type RM Length L Ch R = 1 ,4578    ,443,443,443
BEGIN DESCRIPTION:
LITTLE ELM CREEK 10.0
END DESCRIPTION:
XS GIS Cut Line= 3
        2395775.       13653525.        2396375.       13652525.
        2396575.       13652125.
#Sta/Elev= 30
  3837.8  282.41  4109.7  277.31  4152.7  277.31  4164.3  276.29  4201.3  275.65
  4327.6   274.5  4479.2  275.71  4651.9  275.99  4720.2  277.06  4747.4  275.98
  4778.5  275.99  4784.4  275.16  4852.4  273.29  4910.7  269.02  4931.9  269.11
  4959.3  269.97  4990.4  269.91  4996.2  268.61  4996.5  266.49    4997  265.99
  5005.6  266.49  5012.4  266.52  5026.4  270.28  5034.7  271.67  5057.1  272.94
  5138.2  273.01  5191.3   274.2    5317  279.45  5353.4  279.72  5451.2  282.95
#Mann= 6 ,-1 , 0
  3837.8     .05       0  4109.7     .07       0  4651.9     .05       0
  4931.9     .07       0  4996.5     .05       0  5005.6     .07       0
Bank Sta=4996.5,5005.6
XS Rating Curve= 0 ,0
Exp/Cntr=0.3,0.1

Type RM Length L Ch R = 1 ,4135    ,399,399,399
BEGIN DESCRIPTION:
LITTLE ELM CREEK 9.0
END DESCRIPTION:
XS GIS Cut Line= 3
      2395924.98     13653575.02        2396725.       13652775.
        2396875.     13652424.99
#Sta/Elev= 30
  3868.6  282.44  3911.1  280.83  4009.9  279.91  4123.2  279.21  4250.5  276.62
  4349.5  276.35  4536.5  272.64  4787.9  271.77  4816.2  270.69    4883  272.28
    4901  271.87  4943.4  268.09  4964.6  267.99  4985.9  269.19  4991.6  267.95
  4992.1  267.45  5001.4  267.95  5014.5  269.63  5032.6  269.55  5054.4  268.05
  5067.1  268.88  5085.2  272.01  5130.6  275.46    5247  278.43  5290.1  280.38
  5295.6  278.72  5319.1  278.05  5326.4  279.91  5337.3  281.18  5380.8  282.51
#Mann= 7 ,-1 , 0
  3868.6     .05       0  4009.9     .07       0  4536.5     .05       0
    4883     .07       0  4991.6     .05       0  5001.4     .07       0
    5247    .035       0
Bank Sta=4991.6,5001.4
XS Rating Curve= 0 ,0
Exp/Cntr=0.3,0.1

Type RM Length L Ch R = 1 ,3736    ,242,242,242
BEGIN DESCRIPTION:
LITTLE ELM CREEK 8.0
END DESCRIPTION:
XS GIS Cut Line= 3
      2395974.99     13653975.01        2397075.       13652775.
      2397125.01     13652524.95
#Sta/Elev= 30
  3387.2  283.27  3493.6   282.7  3563.9  280.24  3644.3  279.65  3889.5   278.6
  3939.4  279.64  4094.8   276.7    4296  277.22  4350.1  277.64  4420.4  275.62
  4577.7  274.36  4591.2  274.08  4724.9  271.47  4774.3  271.05  4824.3  267.83
  4851.6  267.52  4875.3  267.78  4916.1   267.4  4922.9  268.34  4958.7  268.56
  4965.5  265.01  4981.7  265.05    4987  265.36  4988.9  264.49  4989.4  263.99
  4998.8  264.49  5017.7  265.45  5055.9  270.81  5167.9  275.87  5270.1   284.2
#Mann= 12 ,-1 , 0
  3387.2     .05       0  3644.3     .07       0    4296     .12       0
  4577.7     .07       0  4591.2     .05       0  4724.9     .07       0
  4851.6     .12       0  4875.3    .035       0  4981.7     .12       0
  4988.9     .05       0  4998.8     .12       0  5167.9     .05       0
Bank Sta=4988.9,4998.8
XS Rating Curve= 0 ,0
Exp/Cntr=0.3,0.1

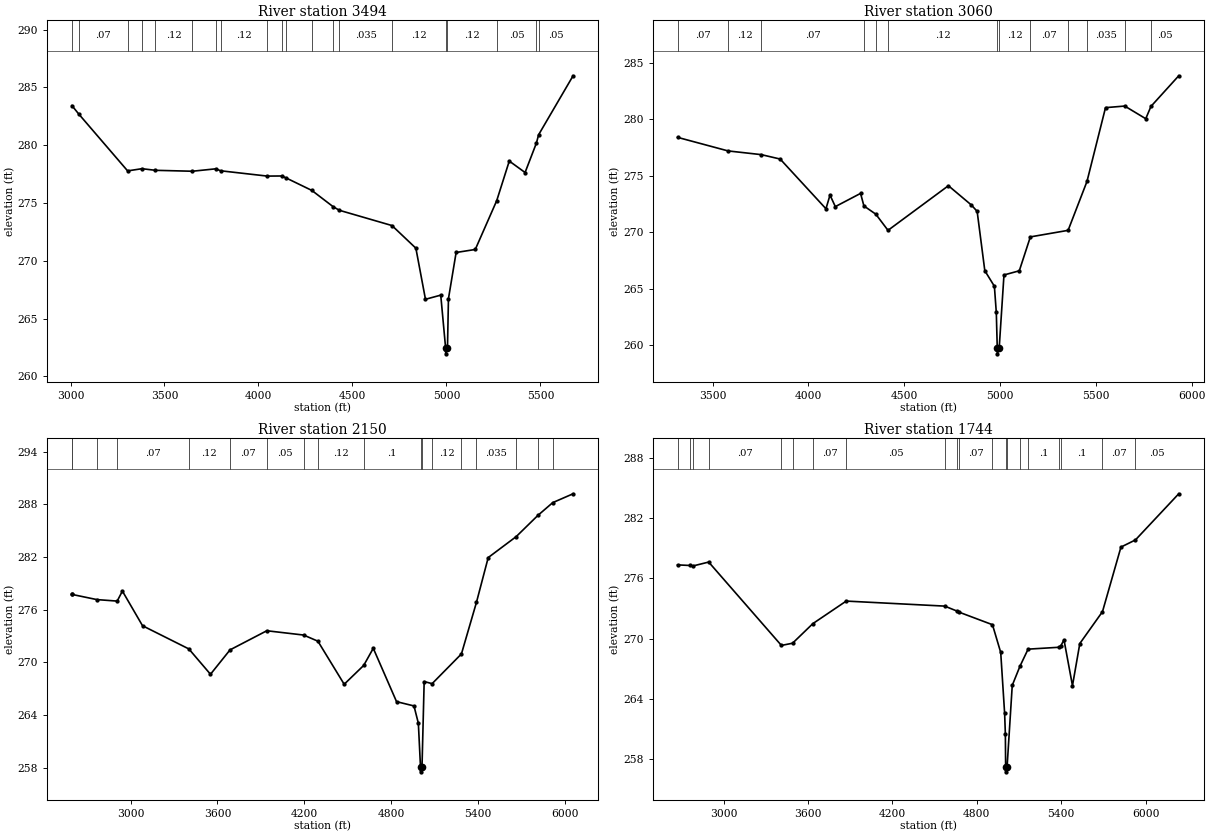
Type RM Length L Ch R = 1 ,3494    ,434,434,434
BEGIN DESCRIPTION:
A19685
END DESCRIPTION:
XS GIS Cut Line= 3
      2396043.06     13654248.16       2397170.8     13653414.89
      2397415.13     13652174.41
#Sta/Elev= 30
  3007.4  283.43  3043.8   282.7  3303.8  277.78  3380.1  277.97  3452.1  277.83
  3648.1  277.75  3773.1  277.96  3798.4  277.79  4046.9  277.33  4124.4  277.34
  4148.2  277.16  4283.9  276.09  4398.2  274.67  4430.7  274.37  4710.3  273.05
  4837.5  271.09  4888.5  266.67  4969.8  267.03  4995.7  262.45  4996.2  261.95
  5005.6  262.45  5010.8  266.72  5051.6  270.72  5153.5  270.98  5267.5   275.2
  5334.4  278.63  5418.5  277.64  5478.8  280.19  5490.6  280.91  5673.9  286.01
#Mann= 20 ,-1 , 0
  3007.4     .05       0  3043.8     .07       0  3303.8    .035       0
  3380.1     .07       0  3452.1     .12       0  3648.1     .12       0
  3773.1     .07       0  3798.4     .12       0  4046.9     .07       0
  4124.4     .12       0  4148.2     .07       0  4283.9     .07       0
  4398.2     .12       0  4430.7    .035       0  4710.3     .12       0
  4995.7     .05       0  5005.6     .12       0  5267.5     .05       0
  5478.8    .035       0  5490.6     .05       0
Bank Sta=4995.7,5005.6
XS Rating Curve= 0 ,0
Exp/Cntr=0.3,0.1

Type RM Length L Ch R = 1 ,3060    ,910,910,910
BEGIN DESCRIPTION:
A19684
END DESCRIPTION:
XS GIS Cut Line= 3
      2396738.48     13654160.45      2397665.75     13653546.45
      2397659.48     13652042.79
#Sta/Elev= 30
  3316.9   278.4  3580.2   277.2  3754.1  276.87  3852.4  276.48  4091.4  272.08
  4112.5  273.29  4140.3  272.27    4272  273.44  4289.5  272.33  4351.6   271.6
  4415.2  270.17  4730.5  274.12  4850.5  272.41  4880.5  271.85  4920.5   266.6
  4970.5  265.22  4980.5   262.9  4985.5  259.74    4986  259.24  4995.5  259.74
  5020.5  266.22  5100.5  266.59  5158.2  269.59  5355.3  270.17  5453.8   274.5
  5550.5  281.03  5650.8  281.17  5760.5  280.05  5787.7  281.14  5932.7  283.85
#Mann= 13 ,-1 , 0
  3316.9     .07       0  3580.2     .12       0  3754.1     .07       0
  4289.5     .12       0  4351.6     .07       0  4415.2     .12       0
  4985.5     .05       0  4995.5     .12       0  5158.2     .07       0
  5355.3     .12       0  5453.8    .035       0  5650.8     .07       0
  5787.7     .05       0
Bank Sta=4985.5,4995.5
XS Rating Curve= 0 ,0
Exp/Cntr=0.3,0.1

Type RM Length L Ch R = 1 ,2150    ,406,406,406
BEGIN DESCRIPTION:
A19683
END DESCRIPTION:
XS GIS Cut Line= 6
      2396845.04     13654172.96      2398148.17     13653421.15
      2398260.94      13652349.8      2398104.31     13651817.26
      2398116.84     13651817.26      2398041.66     13651510.28
#Sta/Elev= 30
  2593.6  277.75  2594.3  277.75  2766.3  277.16  2906.6  276.99  2942.7  278.13
    3082  274.18    3402  271.54  3551.8  268.65    3687  271.43  3941.3  273.61
  4195.6  273.12  4294.4  272.42  4476.3  267.51  4611.3  269.66  4677.4  271.61
  4838.3  265.53  4958.9  265.04  4989.1  263.07  5004.1  258.03  5004.6  257.53
  5014.3  258.03  5029.3  267.82  5084.3  267.58    5287  270.97  5390.6  276.83
  5472.2  281.95  5665.8  284.34  5815.9  286.76  5918.1  288.21    6059  289.22
#Mann= 18 ,-1 , 0
  2593.6     .12       0  2594.3     .07       0  2766.3     .12       0
  2906.6     .07       0    3402     .12       0    3687     .07       0
  3941.3     .05       0  4195.6     .07       0  4294.4     .12       0
  4611.3      .1       0  5004.1     .05       0  5014.3      .1       0
  5084.3     .12       0    5287     .07       0  5390.6    .035       0
  5665.8     .05       0  5815.9    .035       0  5918.1     .05       0
Bank Sta=5004.1,5014.3
XS Rating Curve= 0 ,0
Exp/Cntr=0.3,0.1

Type RM Length L Ch R = 1 ,1744    ,0,0,0
BEGIN DESCRIPTION:
A19682
END DESCRIPTION:
XS GIS Cut Line= 3
      2396939.01     13654223.08      2398354.92     13653371.03
      2398906.25     13651541.61
#Sta/Elev= 30
    2673  277.35  2761.4  277.29  2784.8  277.25  2894.2  277.63  3411.3  269.34
  3490.5  269.56    3635  271.51  3872.1  273.75  4572.2  273.25  4660.7  272.75
  4672.1  272.66  4911.9   271.4  4970.5  268.64  4998.3  262.58  5003.5  260.55
  5005.5  257.27    5006  256.77  5015.8  257.27  5052.5  265.37  5107.9  267.29
  5165.1  268.97  5388.1  269.16  5397.6  269.29  5420.3   269.9  5480.7  265.34
  5532.9  269.53  5694.1   272.7  5825.3  279.12  5928.3  279.83  6236.2  284.42
#Mann= 20 ,-1 , 0
    2673     .12       0  2761.4     .07       0  2784.8     .12       0
  2894.2     .07       0  3411.3     .05       0  3490.5     .12       0
    3635     .07       0  3872.1     .05       0  4572.2     .07       0
  4660.7     .05       0  4672.1     .07       0  4911.9      .1       0
  5005.5     .05       0  5015.8      .1       0  5107.9     .12       0
  5165.1      .1       0  5388.1     .12       0  5397.6      .1       0
  5694.1     .07       0  5928.3     .05       0
Bank Sta=5005.5,5015.8
XS Rating Curve= 0 ,0
Exp/Cntr=0.3,0.1

Chan Stop Cuts=-1
Use User Specified Reach Order=0
Composite Channel Slope=5