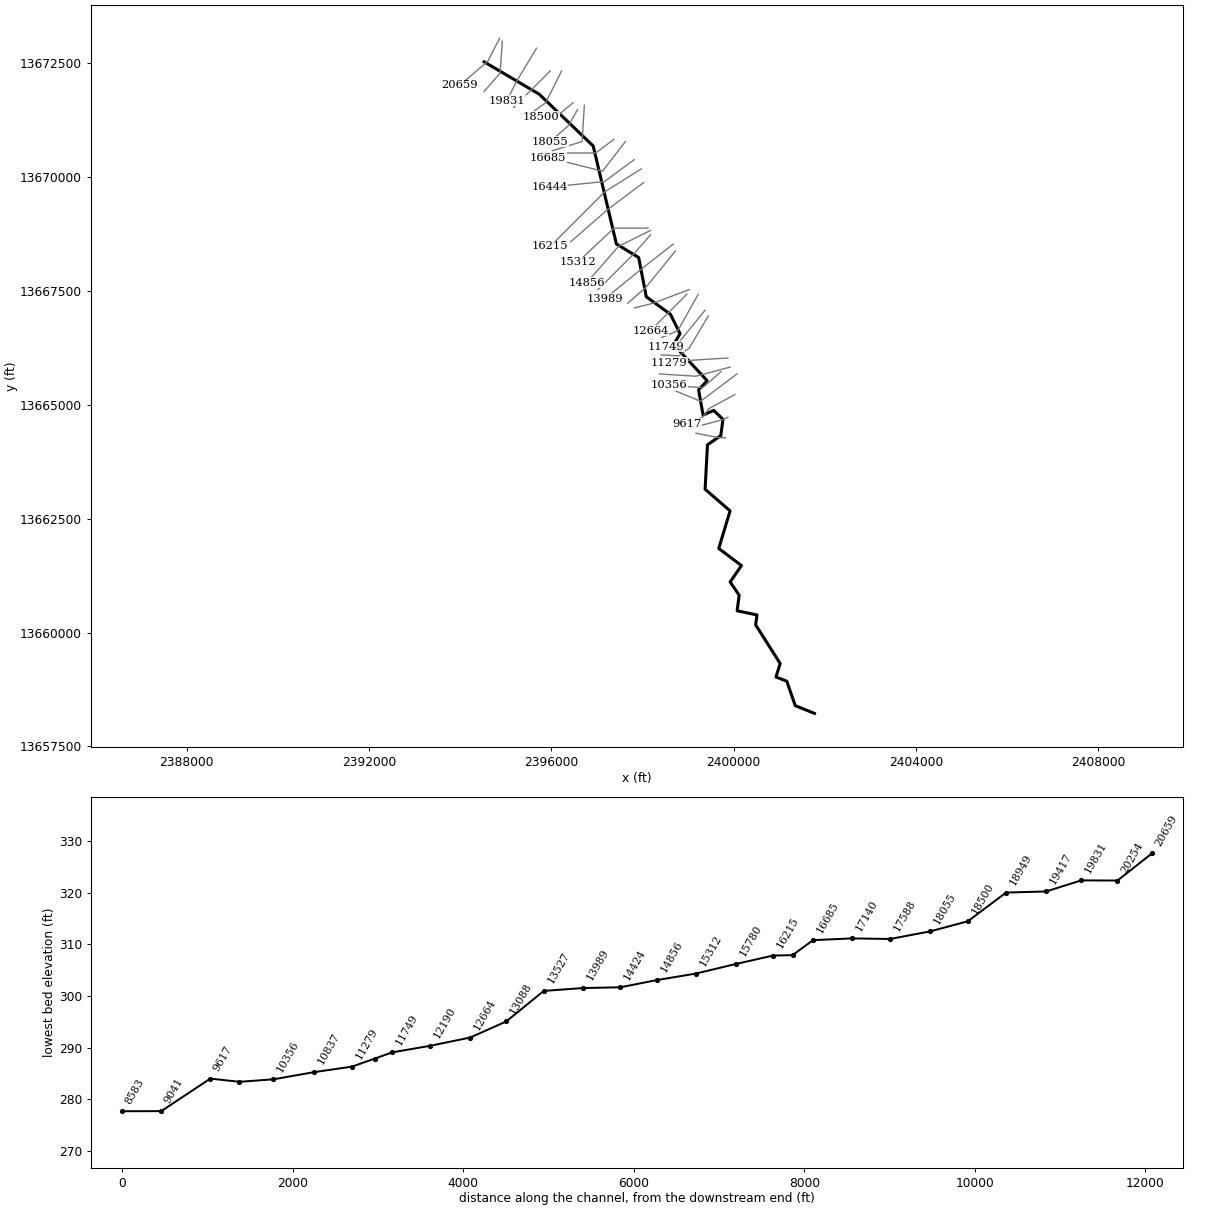
--- LONG HOLLOW.prj (project) ---

Proj Title=LONG HOLLOW Base Level Engineering
Current Plan=p01
Default Exp/Contr=0.3,0.1
English Units
Geom File=g01
Flow File=f01
Plan File=p01
Y Axis Title=Elevation
X Axis Title(PF)=Main Channel Distance
X Axis Title(XS)=Station
BEGIN DESCRIPTION:
LONG HOLLOW
END DESCRIPTION:
DSS Export Rating Curves= 0
DSS Export Rating Curve Sorted= 0
DSS Export Volume Flow Curves= 0
DXF OffsetX= 0
DXF OffsetY= 0
DXF ScaleX= 1
DXF ScaleY= 10

--- LONG HOLLOW.p01 (plan) ---

Plan Title=Multiple Run
Short Identifier=Multiple
Geom File=g01
Flow File=f01
Subcritical Flow
K Sum by GR= 0
Std Step Tol= 0.01
Critical Tol= 0.01
Num of Std Step Trials= 20
Max Error Tol= 0.3
Flow Tol Ratio= 0.001
Split Flow NTrial= 30
Split Flow Tol= 0.02
Split Flow Ratio= 0.02
Log Output Level= 0
Friction Slope Method= 1
Unsteady Friction Slope Method= 2
Unsteady Bridges Friction Slope Method= 1
Parabolic Critical Depth
Global Vel Dist=  1 , 1 , 1
Global Log Level= 0
CheckData=True
Encroach Param= -1, 0, 0, 0
BEGIN DESCRIPTION:
Multiple Run
END DESCRIPTION:

--- LONG HOLLOW.f01 (steady flow) ---

Flow Title=Multiple
Number of Profiles=7
Profile Names=10-year,25-year,50-year,1pct_min,100-year,1pct_plu,500-year
River Rch & RM= LONG HOLLOW,Reach-1,20659
     636    1028    1381     899    1793    3578    2996
River Rch & RM= LONG HOLLOW,Reach-1,19831
     960    1583    2157    1421    2835    5657    4857
River Rch & RM= LONG HOLLOW,Reach-1,14856
    1282    2145    2950    1959    3910    7801    6812
River Rch & RM= LONG HOLLOW,Reach-1,9617
    1331    2224    3057    2028    4047    8076    7037
River Rch & RM= LONG HOLLOW,Reach-1,4122
    1564    2634    3639    2426    4840    9658    8495
River Rch & RM= LONG HOLLOW,Reach-1,3255
    1604    2696    3720    2476    4940    9857    8644
Boundary for River Rch & Prof#=LONG HOLLOW,Reach-1,1
Up Type=0
Dn Type=3
Dn Slope=0.005
Boundary for River Rch & Prof#=LONG HOLLOW,Reach-1,2
Up Type=0
Dn Type=3
Dn Slope=0.005
Boundary for River Rch & Prof#=LONG HOLLOW,Reach-1,3
Up Type=0
Dn Type=3
Dn Slope=0.005
Boundary for River Rch & Prof#=LONG HOLLOW,Reach-1,4
Up Type=0
Dn Type=3
Dn Slope=0.005
Boundary for River Rch & Prof#=LONG HOLLOW,Reach-1,5
Up Type=0
Dn Type=3
Dn Slope=0.005
Boundary for River Rch & Prof#=LONG HOLLOW,Reach-1,6
Up Type=0
Dn Type=3
Dn Slope=0.005
Boundary for River Rch & Prof#=LONG HOLLOW,Reach-1,7
Up Type=0
Dn Type=3
Dn Slope=0.005

--- LONG HOLLOW.g01 (geometry) ---

Geom Title=Existing Conditions
Program Version=4.10

River Reach=LONG HOLLOW     ,Reach-1
Reach XY= 30
        2394525.       13672525.      2395734.81     13671814.49
      2396919.27     13670677.55      2397428.54     13668526.47
      2397916.86     13668231.06      2398084.15     13667368.27
      2398614.23      13666984.7      2398824.76     13666559.78
      2398683.95     13666318.33      2399419.94      13665527.3
      2399232.01     13665325.21      2399330.46     13664771.97
      2399564.36     13664874.45      2399767.23     13664678.41
      2399719.55     13664322.55      2399426.96     13664119.35
      2399375.07     13663145.03      2399923.47     13662669.17
      2399674.91     13661844.87      2400172.95     13661469.14
      2399924.86     13661109.59      2400122.75     13660819.06
      2400078.44     13660476.25      2400514.68     13660385.18
      2400484.41     13660168.38      2401023.03     13659319.32
      2400930.06     13659022.68      2401167.26     13658931.55
      2401354.35     13658394.42        2401775.       13658225.

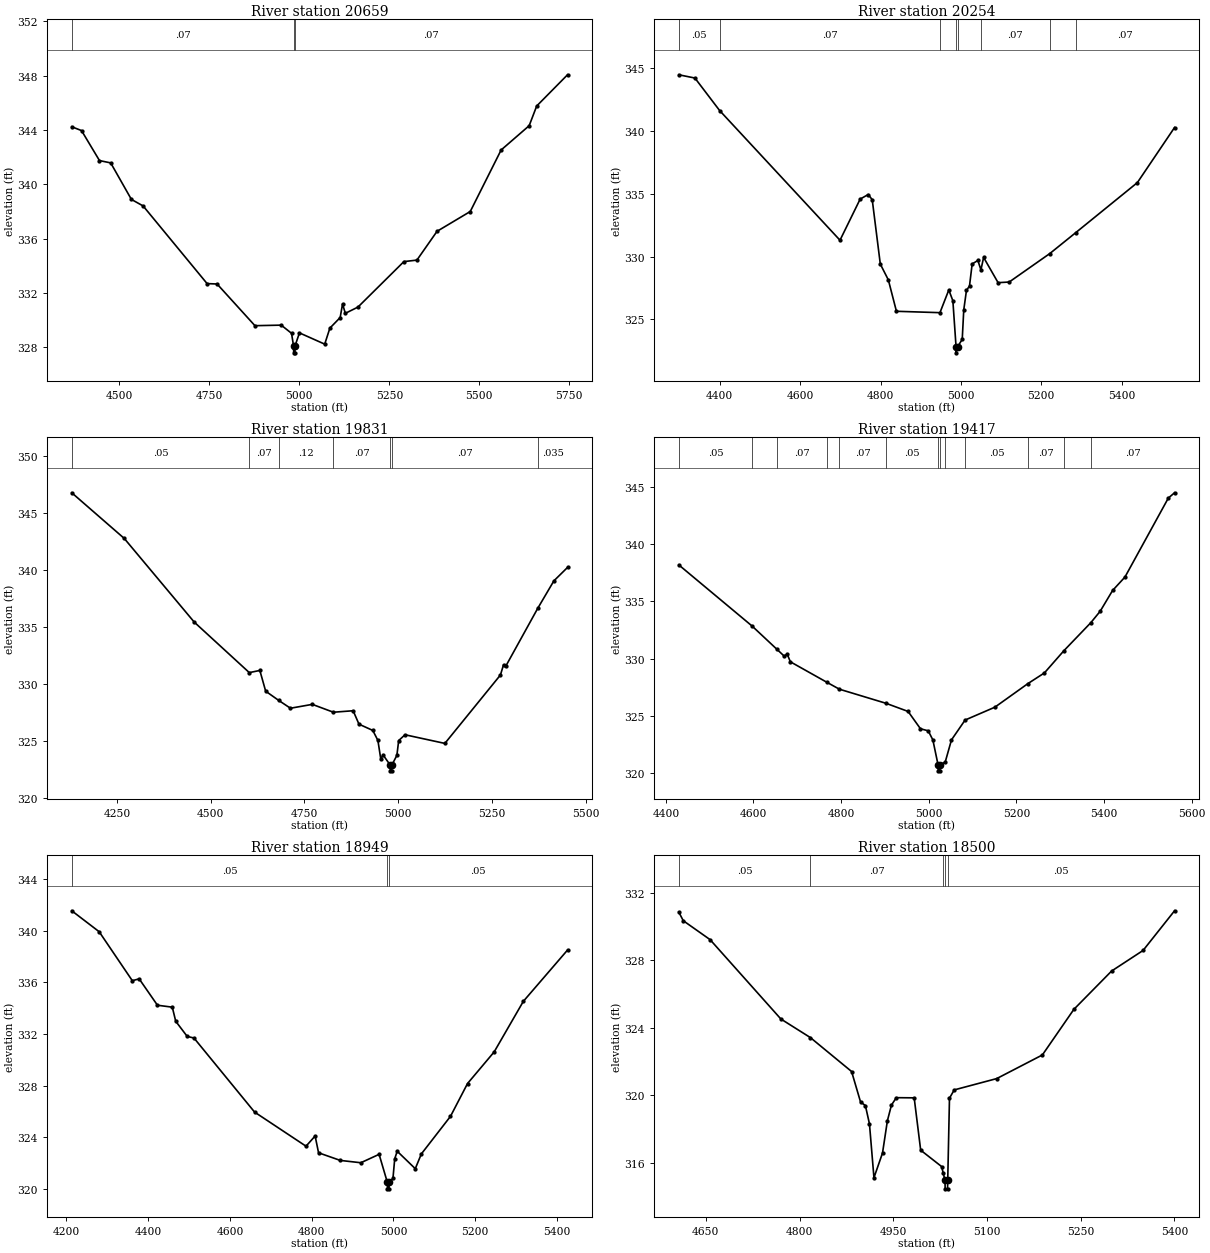
Type RM Length L Ch R = 1 ,20659   ,405,405,405
BEGIN DESCRIPTION:
A19833
END DESCRIPTION:
XS GIS Cut Line= 3
      2394864.05     13673041.01       2394600.6     13672531.29
      2393988.89     13672011.05
#Sta/Elev= 30
  4368.1  344.24  4395.2  343.96  4445.1  341.75  4476.2  341.58  4533.7  338.89
  4566.2  338.41  4743.9  332.69  4771.7  332.66  4876.8  329.59  4949.8  329.63
  4978.4  329.03  4984.1  328.09  4984.4  327.59  4987.9  327.59  4988.1  328.09
  5000.4  329.06  5070.6  328.23  5084.9  329.41  5113.5  330.19  5120.1  331.19
  5127.8   330.5  5162.9  330.96  5290.5  334.31  5326.6  334.42  5382.5  336.54
  5474.8     338  5560.5  342.53  5638.4  344.32  5659.3  345.77  5744.9  348.07
#Mann= 3 ,-1 , 0
  4368.1     .07       0  4984.1     .05       0  4988.1     .07       0
Bank Sta=4984.1,4988.1
XS Rating Curve= 0 ,0
Exp/Cntr=0.3,0.1

Type RM Length L Ch R = 1 ,20254   ,423,423,423
BEGIN DESCRIPTION:
LONG HOLLOW 39.0
END DESCRIPTION:
XS GIS Cut Line= 3
        2394925.     13672975.02        2394875.       13672275.
      2394525.01     13671875.01
#Sta/Elev= 30
  4298.2  344.48  4338.3  344.22  4399.8  341.63  4699.2   331.3  4749.4  334.58
  4769.4  334.94  4779.4  334.53  4799.5   329.4  4819.5  328.14  4839.6  325.64
  4947.9  325.53  4969.9  327.34    4980  326.48  4987.9  322.83  4988.2  322.33
    4992  322.83  5003.3   323.4  5007.1  325.75  5013.8   327.3  5021.4  327.66
    5028  329.41  5042.2  329.69  5049.8  328.94  5056.5  329.93  5092.5  327.92
  5120.1  327.97  5221.2  330.24  5285.9  331.91    5439  335.89  5531.5  340.28
#Mann= 8 ,-1 , 0
  4298.2     .05       0  4399.8     .07       0  4947.9     .12       0
  4987.9     .05       0    4992     .12       0  5049.8     .07       0
  5221.2     .12       0  5285.9     .07       0
Bank Sta=4987.9,4992
XS Rating Curve= 0 ,0
Exp/Cntr=0.3,0.1

Type RM Length L Ch R = 1 ,19831   ,414,414,414
BEGIN DESCRIPTION:
LONG HOLLOW 38.0
END DESCRIPTION:
XS GIS Cut Line= 3
        2395675.     13672825.01        2395225.       13672075.
      2395024.98     13671674.97
#Sta/Elev= 30
  4129.5   346.8  4269.4  342.79    4456  335.44  4602.9     331    4631  331.19
  4646.5  329.37  4681.2  328.56  4712.6  327.87  4770.9  328.21  4827.1  327.52
  4879.8  327.65  4895.3  326.47  4932.2  325.92  4945.8  325.04  4953.6  323.38
  4959.4  323.78  4978.7  322.87    4979  322.37  4982.7  322.37  4982.9  322.87
  4996.4  323.73  5001.2  325.03  5018.1  325.54  5124.3  324.78  5272.5  330.79
  5280.9   331.7  5286.5  331.55    5372  336.65    5415  339.06  5451.4  340.24
#Mann= 7 ,-1 , 0
  4129.5     .05       0  4602.9     .07       0  4681.2     .12       0
  4827.1     .07       0  4978.7     .05       0  4982.9     .07       0
    5372    .035       0
Bank Sta=4978.7,4982.9
XS Rating Curve= 0 ,0
Exp/Cntr=0.3,0.1

Type RM Length L Ch R = 1 ,19417   ,468,468,468
BEGIN DESCRIPTION:
LONG HOLLOW 37.0
END DESCRIPTION:
XS GIS Cut Line= 3
        2395975.       13672325.        2395575.       13671925.
      2395174.98     13671524.98
#Sta/Elev= 30
  4429.6  338.18  4596.8  332.85  4652.7  330.85    4670  330.23  4677.1  330.39
  4684.2  329.73  4767.2  327.95  4796.1  327.34  4902.5  326.11  4952.9   325.4
  4981.1  323.89  4998.8  323.71  5009.4  322.92  5021.4  320.72  5021.7  320.22
  5025.5  320.22  5025.7  320.72  5037.7     321  5051.9  322.92    5083  324.65
  5150.9  325.77  5226.4  327.83    5264  328.76  5308.3  330.69  5369.9  333.14
  5391.3  334.14  5419.6  335.95  5447.8  337.12  5546.8  344.01    5561  344.47
#Mann= 13 ,-1 , 0
  4429.6     .05       0  4596.8    .035       0  4652.7     .07       0
  4767.2     .05       0  4796.1     .07       0  4902.5     .05       0
  5021.4     .05       0  5025.7     .05       0  5037.7     .07       0
    5083     .05       0  5226.4     .07       0  5308.3     .05       0
  5369.9     .07       0
Bank Sta=5021.4,5025.7
XS Rating Curve= 0 ,0
Exp/Cntr=0.3,0.1

Type RM Length L Ch R = 1 ,18949   ,449,449,449
BEGIN DESCRIPTION:
LONG HOLLOW 36.0
END DESCRIPTION:
XS GIS Cut Line= 3
      2396224.98     13672324.96        2395875.       13671625.
        2395525.       13671375.
#Sta/Elev= 30
  4213.1  341.53  4280.1  339.91  4361.2  336.12    4378  336.26  4422.7  334.22
    4459  334.07  4467.4  332.98  4495.4  331.81  4512.1  331.68  4660.3  325.95
  4786.1  323.31  4808.4   324.1  4816.8   322.8  4869.9  322.21  4920.2  322.03
  4964.9  322.68  4985.1  320.51  4985.4  320.01  4989.2  320.01  4989.5  320.51
  4998.8  320.82  5003.1  322.34  5009.2  322.92  5053.4  321.57  5068.2  322.71
  5139.5  325.62  5181.2  328.16  5246.4  330.61  5317.7  334.52  5425.8  338.49
#Mann= 3 ,-1 , 0
  4213.1     .05       0  4985.1     .05       0  4989.5     .05       0
Bank Sta=4985.1,4989.5
XS Rating Curve= 0 ,0
Exp/Cntr=0.3,0.1

Type RM Length L Ch R = 1 ,18500   ,445,445,445
BEGIN DESCRIPTION:
LONG HOLLOW 35.0
END DESCRIPTION:
XS GIS Cut Line= 3
      2396474.99     13671624.99        2396175.       13671375.
      2395775.02       13671325.
#Sta/Elev= 30
  4606.7  330.84  4613.9  330.33  4656.8  329.21  4770.1  324.51  4817.3  323.41
  4883.3   321.4  4897.6   319.6  4905.4  319.38  4911.9   318.3  4919.1  315.11
  4932.8  316.57  4940.6  318.48  4947.1  319.41  4954.9  319.85  4983.5  319.84
  4993.9  316.74  5027.4  315.77    5030  315.38  5032.8  314.95  5033.1  314.45
  5036.9  314.45  5037.2  314.95    5040  319.82  5047.6  320.31  5115.6  320.98
  5188.7  322.38  5239.1  325.08  5299.5  327.35  5349.9  328.57  5400.3  330.92
#Mann= 5 ,-1 , 0
  4606.7     .05       0  4817.3     .07       0    5030     .05       0
  5032.8     .05       0  5037.2     .05       0
Bank Sta=5032.8,5037.2
XS Rating Curve= 0 ,0
Exp/Cntr=0.3,0.1

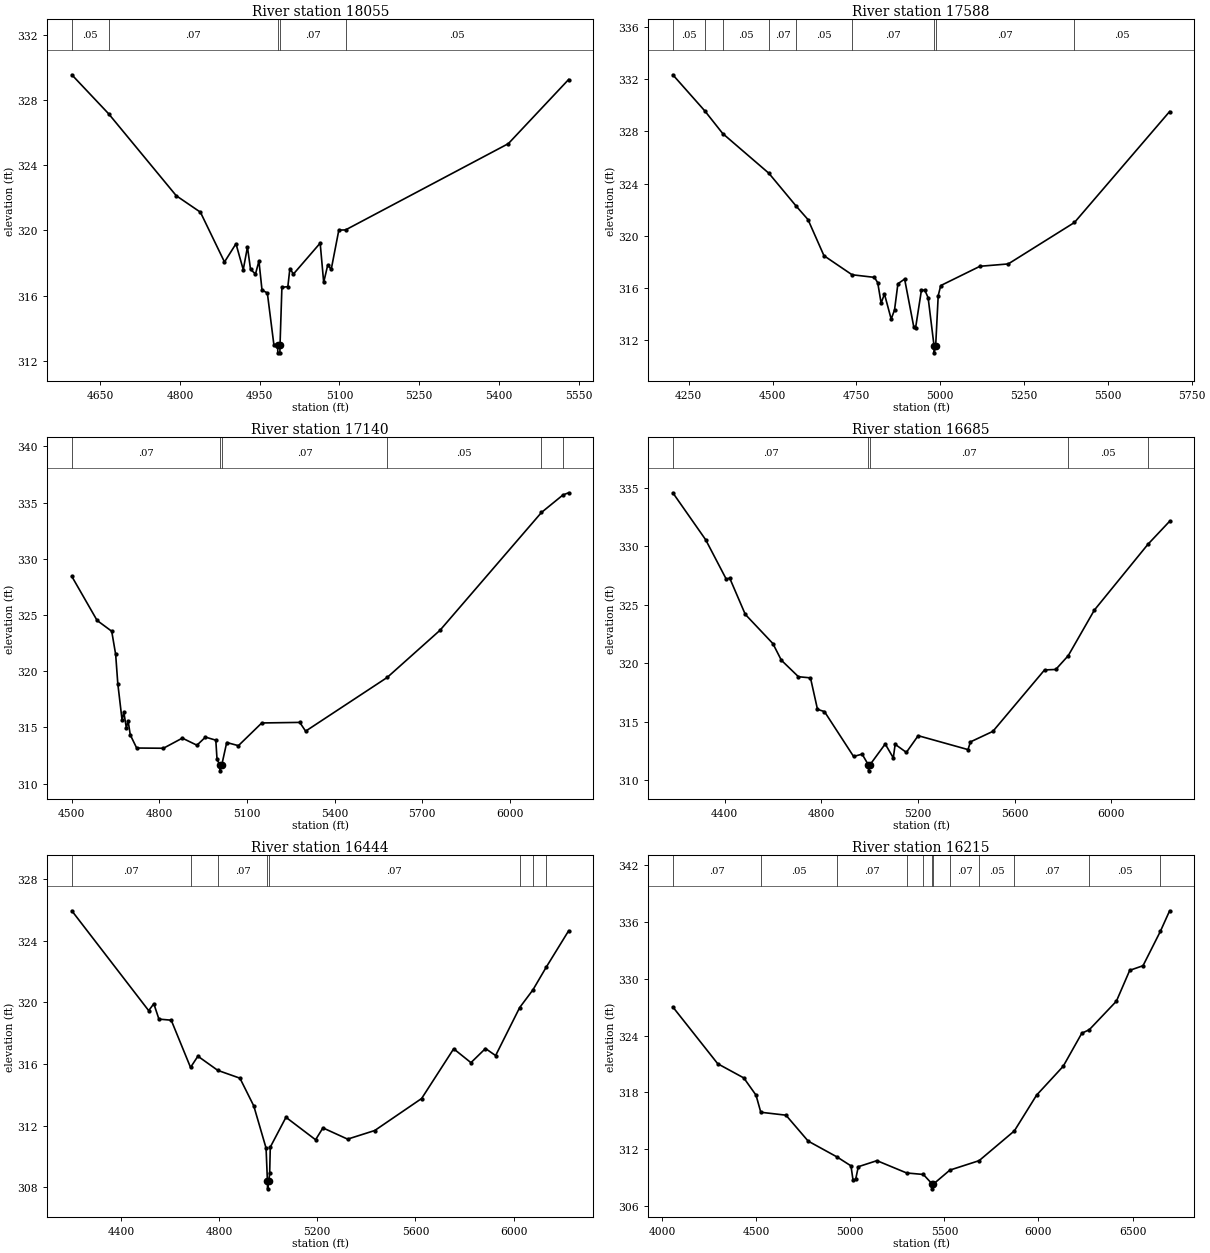
Type RM Length L Ch R = 1 ,18055   ,467,467,467
BEGIN DESCRIPTION:
LONG HOLLOW 34.0
END DESCRIPTION:
XS GIS Cut Line= 3
      2396574.99     13671474.99        2396375.       13671125.
      2395975.01     13670775.01
#Sta/Elev= 30
  4596.6  329.56  4665.7  327.17  4793.1  322.13  4838.5  321.12  4883.8  318.06
  4905.4  319.18  4919.1  317.59    4927  318.98  4932.8  317.61  4942.1  317.32
  4948.6  318.12  4954.4  316.33  4964.4  316.16  4976.7  312.98  4983.7  312.98
  4984.1  312.48    4988  312.48  4988.3  312.98  4991.8   316.5    5003  316.55
  5006.8  317.65  5013.5  317.32  5063.8  319.22  5070.4  316.81    5078  317.87
  5084.6  317.61  5098.9  320.02  5111.5  320.03  5417.8  325.33  5531.2  329.27
#Mann= 5 ,-1 , 0
  4596.6     .05       0  4665.7     .07       0  4983.7     .05       0
  4988.3     .07       0  5111.5     .05       0
Bank Sta=4983.7,4988.3
XS Rating Curve= 0 ,0
Exp/Cntr=0.3,0.1

Type RM Length L Ch R = 1 ,17588   ,448,448,448
BEGIN DESCRIPTION:
LONG HOLLOW 33.0
END DESCRIPTION:
XS GIS Cut Line= 3
        2396725.     13671574.96        2396675.       13670775.
      2396024.99       13670575.
#Sta/Elev= 30
  4202.7  332.35  4298.1  329.58  4351.6  327.84    4489   324.8  4571.1  322.26
  4605.9  321.24  4653.5  318.47  4737.2  317.01  4803.8  316.81  4813.8   316.4
  4823.9  314.84  4833.9  315.53  4853.9  313.61  4863.9  314.31    4874  316.32
    4894  316.68  4921.6  312.97  4926.6  312.92  4944.1  315.82  4954.1  315.83
  4964.1  315.25  4981.9  311.52  4982.2  311.02  4986.5  311.52  4994.2  315.41
  5001.7  316.18  5118.7  317.66    5203  317.84  5400.5  321.02  5684.3  329.53
#Mann= 9 ,-1 , 0
  4202.7     .05       0  4298.1     .07       0  4351.6     .05       0
    4489     .07       0  4571.1     .05       0  4737.2     .07       0
  4981.9     .05       0  4986.5     .07       0  5400.5     .05       0
Bank Sta=4981.9,4986.5
XS Rating Curve= 0 ,0
Exp/Cntr=0.3,0.1

Type RM Length L Ch R = 1 ,17140   ,455,455,455
BEGIN DESCRIPTION:
LONG HOLLOW 32.0
END DESCRIPTION:
XS GIS Cut Line= 3
        2397375.       13670825.        2396975.       13670525.
        2395775.       13670525.
#Sta/Elev= 30
  4500.5  328.43    4587  324.51    4637  323.55  4650.5  321.49  4657.8   318.9
  4672.4  315.65  4678.6  316.33    4687  314.96  4693.2  315.56  4700.5  314.33
  4722.4  313.16    4814  313.14  4878.6  314.04  4928.6  313.41  4957.8  314.13
  4993.2  313.86  4997.4  312.14  5007.7  311.63  5008.2  311.13  5013.4  311.63
  5030.5  313.65  5070.5  313.37  5150.5  315.39  5280.5  315.44  5300.5  314.66
  5579.7  319.44  5760.5  323.64  6107.6  334.12  6181.3  335.68  6200.5  335.87
#Mann= 6 ,-1 , 0
  4500.5     .07       0  5007.7     .05       0  5013.4     .07       0
  5579.7     .05       0  6107.6    .035       0  6181.3     .05       0
Bank Sta=5007.7,5013.4
XS Rating Curve= 0 ,0
Exp/Cntr=0.3,0.1

Type RM Length L Ch R = 1 ,16685   ,241,241,241
BEGIN DESCRIPTION:
LONG HOLLOW 31.0
END DESCRIPTION:
XS GIS Cut Line= 3
      2397625.02     13670775.03        2397125.       13670125.
      2395925.03     13670424.99
#Sta/Elev= 30
  4184.9   334.6  4320.9  330.58    4406  327.21  4420.5  327.29  4484.9  324.19
  4599.1  321.69  4634.4  320.26    4705  318.85  4754.9  318.75  4783.9  316.06
  4812.9  315.86  4933.4  312.02  4968.7  312.22  4994.9  311.29  4995.3  310.79
  5000.6  311.29  5064.3  313.09  5097.8   311.9  5105.5  313.06  5151.9  312.37
  5200.8   313.8    5407  312.61  5417.3  313.27  5510.1  314.17    5724  319.43
  5770.4  319.47  5822.1  320.65  5930.1  324.55  6152.1  330.19  6241.9  332.16
#Mann= 5 ,-1 , 0
  4184.9     .07       0  4994.9     .05       0  5000.6     .07       0
  5822.1     .05       0  6152.1    .035       0
Bank Sta=4994.9,5000.6
XS Rating Curve= 0 ,0
Exp/Cntr=0.3,0.1

Type RM Length L Ch R = 1 ,16444   ,229,229,229
BEGIN DESCRIPTION:
A19832
END DESCRIPTION:
XS GIS Cut Line= 3
      2397819.06     13670378.07      2397166.18       13669897.
      2395958.92     13669776.84
#Sta/Elev= 30
    4200  325.96  4513.2  319.47  4534.1  319.92  4554.9  318.92    4605  318.85
  4683.7  315.78  4713.7  316.51  4794.6  315.59    4885  315.08  4941.3  313.28
  4991.4  310.54    4997  308.39  4997.5  307.89  5002.7  308.39  5006.1  308.89
  5008.6   310.6  5072.5  312.54  5193.1  311.08  5223.2  311.85  5323.7  311.12
  5434.2  311.68  5625.2  313.76  5755.8  316.99  5826.2  316.09  5885.4  317.01
  5926.7  316.55  6024.7  319.67  6078.7  320.82  6132.7  322.29  6224.2  324.66
#Mann= 8 ,-1 , 0
    4200     .07       0  4683.7     .05       0  4794.6     .07       0
    4997     .05       0  5002.7     .07       0  6024.7     .05       0
  6078.7     .07       0  6132.7     .05       0
Bank Sta=4997,5002.7
XS Rating Curve= 0 ,0
Exp/Cntr=0.3,0.1

Type RM Length L Ch R = 1 ,16215   ,435,435,435
BEGIN DESCRIPTION:
LONG HOLLOW 30.0
END DESCRIPTION:
XS GIS Cut Line= 3
      2397974.96     13670174.98        2397175.       13669675.
      2395975.01     13668475.01
#Sta/Elev= 30
  4056.6  327.04  4295.4  321.03  4433.9  319.53  4498.8  317.71  4524.2   315.9
    4658  315.59  4775.9  312.85  4929.6  311.17  5003.5  310.23  5014.1  308.76
  5028.2  308.79  5042.4  310.14  5141.4  310.78  5299.1  309.48  5388.2  309.32
  5435.5   308.3    5436   307.8  5441.3   308.3  5528.9  309.78  5684.4  310.78
  5871.9  313.93  5989.9  317.71  6131.3  320.76  6230.3  324.26    6270  324.63
  6414.2  327.65  6484.9  330.91  6555.6   331.4  6647.9  335.04    6697  337.21
#Mann= 12 ,-1 , 0
  4056.6     .07       0  4524.2     .05       0  4929.6     .07       0
  5299.1     .05       0  5388.2      .1       0  5435.5     .05       0
  5441.3      .1       0  5528.9     .07       0  5684.4     .05       0
  5871.9     .07       0    6270     .05       0  6647.9    .035       0
Bank Sta=5435.5,5441.3
XS Rating Curve= 0 ,0
Exp/Cntr=0.3,0.1

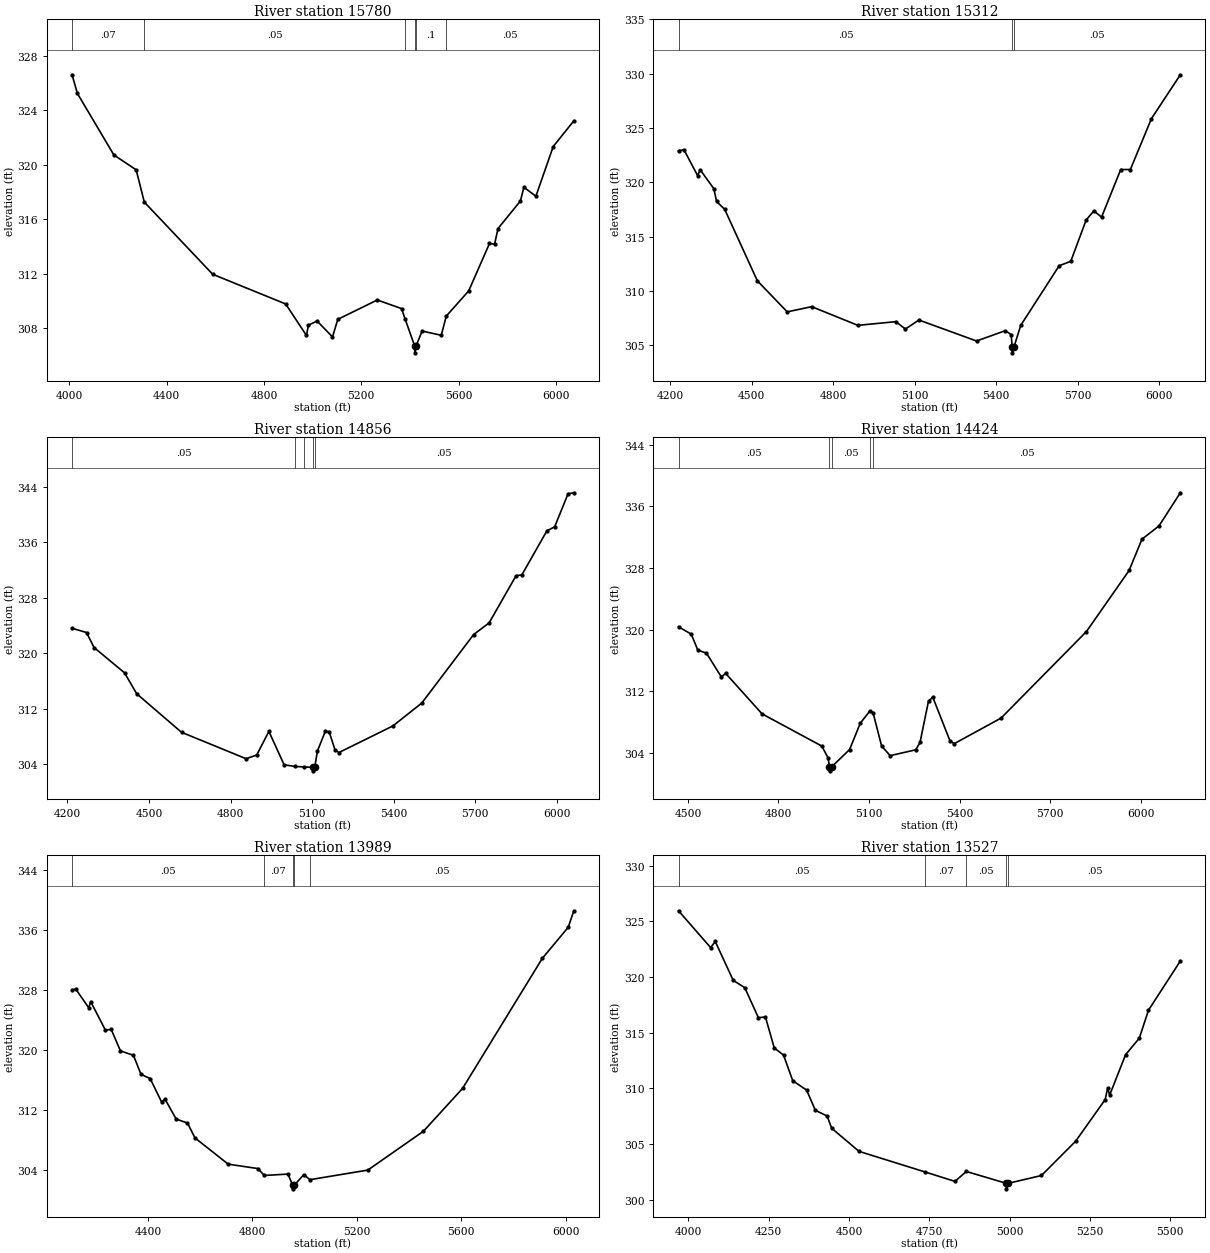
Type RM Length L Ch R = 1 ,15780   ,468,468,468
BEGIN DESCRIPTION:
LONG HOLLOW 29.0
END DESCRIPTION:
XS GIS Cut Line= 3
        2398025.       13669875.        2397225.       13669275.
      2396425.01     13668575.01
#Sta/Elev= 30
  4010.9   326.6  4032.8  325.23  4182.8  320.71  4274.4  319.62  4307.9  317.25
    4589  311.95    4889  309.77  4974.4  307.46  4982.8  308.21    5018  308.52
  5081.6  307.35  5103.4  308.64  5265.7  310.06  5365.4  309.43  5379.7  308.69
  5419.4  306.68  5419.9  306.18  5425.2  306.68  5449.9  307.78  5528.7  307.47
  5549.4  308.88  5641.6  310.73    5727  314.21  5747.9  314.16  5762.1  315.31
  5854.2  317.33  5868.4  318.34  5917.8  317.68    5989  321.33  6073.9  323.22
#Mann= 6 ,-1 , 0
  4010.9     .07       0  4307.9     .05       0  5379.7      .1       0
  5419.4     .05       0  5425.2      .1       0  5549.4     .05       0
Bank Sta=5419.4,5425.2
XS Rating Curve= 0 ,0
Exp/Cntr=0.3,0.1

Type RM Length L Ch R = 1 ,15312   ,456,456,456
BEGIN DESCRIPTION:
LONG HOLLOW 28.0
END DESCRIPTION:
XS GIS Cut Line= 3
      2398125.03       13668875.        2397375.       13668875.
      2396575.01     13668125.01
#Sta/Elev= 30
  4231.1  322.92  4251.1  323.01  4301.1  320.64  4311.1  321.16  4361.1  319.42
  4371.1  318.25  4401.1  317.52  4521.1  310.95  4631.1  308.09  4721.1  308.57
  4891.1  306.85  5030.7  307.19  5065.9  306.51  5115.7  307.34  5327.7  305.41
  5433.7  306.36  5455.2     306  5459.1  304.82  5459.6  304.32    5465  304.82
  5490.4  306.85    5632  312.34  5674.5  312.74  5731.2  316.55  5759.5  317.38
  5787.8  316.81  5858.4  321.19  5893.8  321.19  5971.5  325.88  6077.7  329.91
#Mann= 3 ,-1 , 0
  4231.1     .05       0  5459.1     .05       0    5465     .05       0
Bank Sta=5459.1,5465
XS Rating Curve= 0 ,0
Exp/Cntr=0.3,0.1

Type RM Length L Ch R = 1 ,14856   ,432,432,432
BEGIN DESCRIPTION:
LONG HOLLOW 27.0
END DESCRIPTION:
XS GIS Cut Line= 3
      2398174.99       13668825.        2397475.       13668475.
      2396775.02     13667675.02
#Sta/Elev= 30
  4217.1  323.63  4270.2  323.02  4298.1  320.85    4410  317.21  4454.7  314.19
  4619.6  308.63  4857.2  304.82  4896.3  305.35    4941  308.76  4996.9  303.95
  5035.9   303.7  5069.1  303.64  5102.6  303.57  5103.1  303.07  5109.4  303.57
  5119.8  305.95  5148.3  308.75  5162.5  308.73  5184.3  306.08  5198.6  305.71
  5396.9  309.54  5503.2  312.84    5694  322.72  5750.9   324.4  5850.1  331.21
  5871.5  331.33  5963.5  337.68    5992  338.26  6041.4  343.03  6062.7  343.17
#Mann= 5 ,-1 , 0
  4217.1     .05       0  5035.9     .15       0  5069.1     .05       0
  5102.6     .05       0  5109.4     .05       0
Bank Sta=5102.6,5109.4
XS Rating Curve= 0 ,0
Exp/Cntr=0.3,0.1

Type RM Length L Ch R = 1 ,14424   ,435,435,435
BEGIN DESCRIPTION:
LONG HOLLOW 26.0
END DESCRIPTION:
XS GIS Cut Line= 3
      2398174.97     13668724.97        2397825.       13668325.
      2397025.02     13667525.02
#Sta/Elev= 30
  4468.8  320.36    4511   319.4  4532.8  317.32  4561.3  316.94  4610.7  313.84
  4624.9  314.31  4745.4  309.06  4943.8  304.87  4964.7  303.31  4968.8  302.16
  4969.3  301.66  4975.7  302.16  5035.6  304.42    5071  307.84  5103.1  309.44
  5113.3  309.21  5141.7  304.89    5170  303.63  5254.8  304.39    5269  305.34
  5297.2  310.73  5311.4  311.21    5368  305.58  5382.1  305.18  5537.7  308.51
  5820.5  319.74  5961.9  327.67  6004.4  331.72  6060.9  333.45  6131.6  337.75
#Mann= 5 ,-1 , 0
  4468.8     .05       0  4968.8     .05       0  4975.7     .05       0
  5103.1     .15       0  5113.3     .05       0
Bank Sta=4968.8,4975.7
XS Rating Curve= 0 ,0
Exp/Cntr=0.3,0.1

Type RM Length L Ch R = 1 ,13989   ,462,462,462
BEGIN DESCRIPTION:
LONG HOLLOW 25.0
END DESCRIPTION:
XS GIS Cut Line= 3
      2398674.97     13668524.98        2397975.       13667975.
      2397174.97     13667324.98
#Sta/Elev= 30
  4109.9  327.98  4123.5  328.18  4173.5  325.67  4181.3  326.47  4237.3  322.69
  4259.9  322.77  4295.1  319.91  4344.9  319.32  4373.8  316.78    4409  316.22
  4452.4  313.11    4466  313.46  4508.4  310.82  4551.8  310.29  4580.4  308.31
  4707.6  304.81    4822  304.22  4845.5   303.3  4936.5  303.49  4954.1  302.02
  4954.6  301.52  4961.1  302.02  4996.9  303.41  5020.6  302.74  5242.2  304.02
  5454.8  309.19  5604.9  314.91  5910.2  332.25  6009.3  336.39  6030.9  338.59
#Mann= 5 ,-1 , 0
  4109.9     .05       0  4845.5     .07       0  4954.1     .05       0
  4961.1     .07       0  5020.6     .05       0
Bank Sta=4954.1,4961.1
XS Rating Curve= 0 ,0
Exp/Cntr=0.3,0.1

Type RM Length L Ch R = 1 ,13527   ,439,439,439
BEGIN DESCRIPTION:
LONG HOLLOW 24.0
END DESCRIPTION:
XS GIS Cut Line= 3
      2398725.02     13668375.02        2398075.       13667575.
      2397675.01     13667225.01
#Sta/Elev= 30
  3969.2  325.96  4069.1  322.65  4083.5   323.2  4139.5   319.7  4175.4  319.05
  4217.8  316.35  4239.8  316.41  4267.3  313.62  4296.1  312.99  4324.8  310.68
  4367.9  309.84  4395.2  308.02  4431.8  307.51    4446  306.41    4531  304.33
  4735.4  302.49  4829.8  301.63  4865.1  302.52  4989.3  301.46  4989.8  300.96
  4996.3  301.46  5099.2  302.16  5205.5  305.24  5297.6  308.99  5305.1  309.99
  5311.8  309.41  5361.1  313.02  5403.9  314.51  5432.3  317.02  5531.5  321.44
#Mann= 5 ,-1 , 0
  3969.2     .05       0  4735.4     .07       0  4865.1     .05       0
  4989.3     .05       0  4996.3     .05       0
Bank Sta=4989.3,4996.3
XS Rating Curve= 0 ,0
Exp/Cntr=0.3,0.1

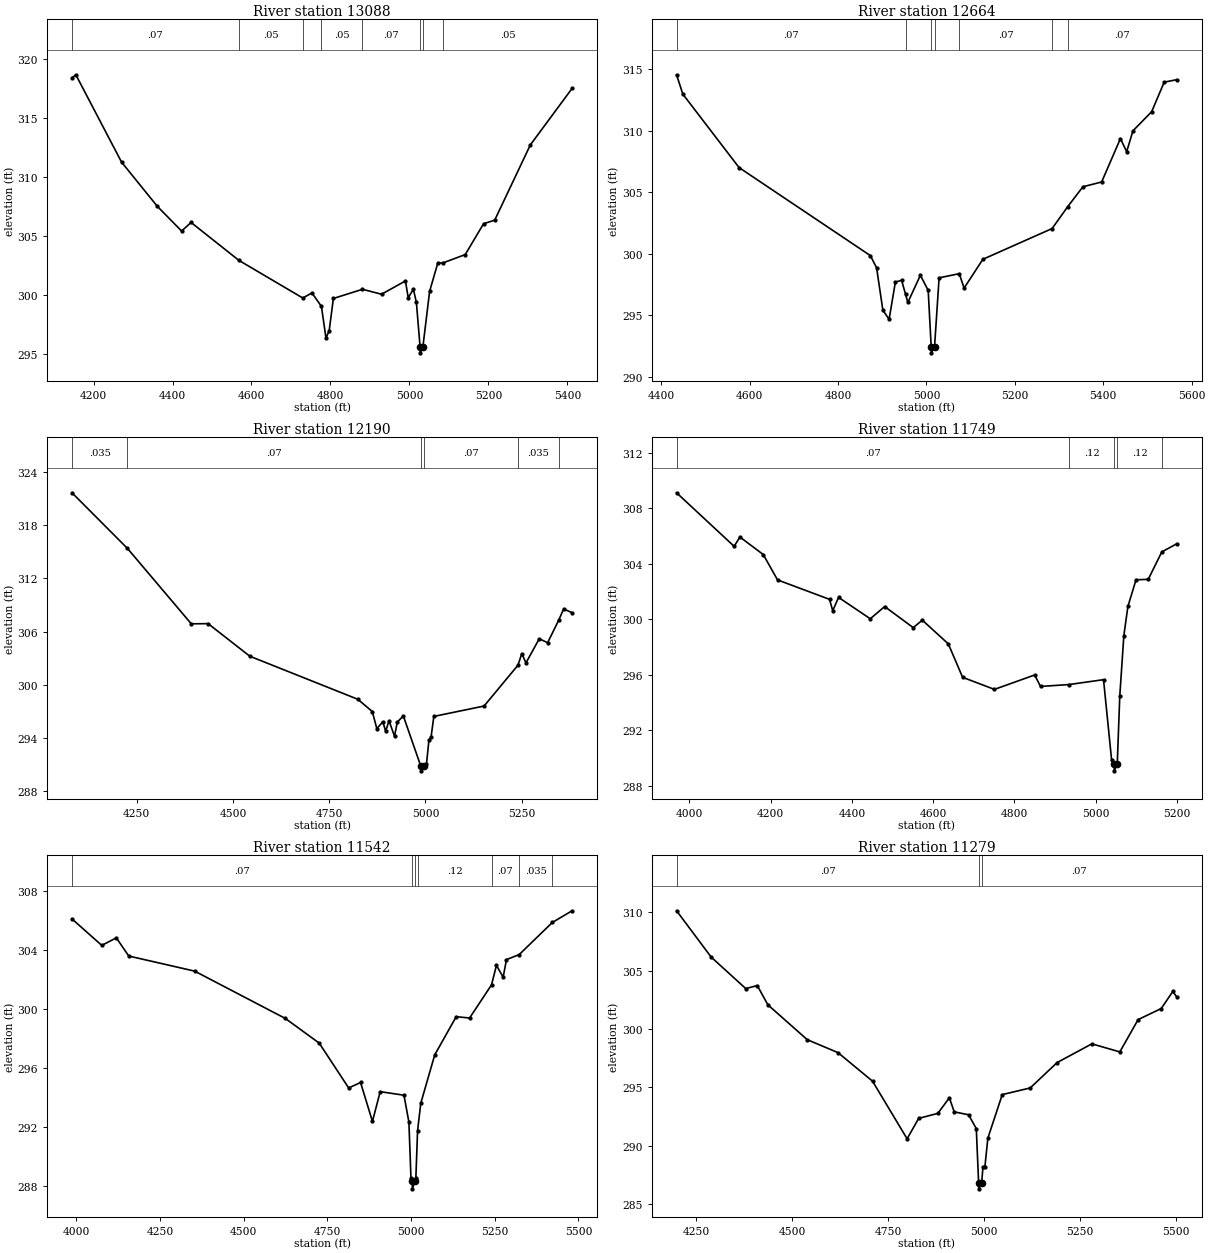
Type RM Length L Ch R = 1 ,13088   ,424,424,424
BEGIN DESCRIPTION:
LONG HOLLOW 23.0
END DESCRIPTION:
XS GIS Cut Line= 3
      2399024.97     13667524.99        2398225.       13667225.
      2397824.98       13667125.
#Sta/Elev= 30
  4145.3  318.43  4155.1  318.69  4270.8  311.27  4361.5  307.51    4423  305.41
    4447  306.14    4568  302.92  4729.9  299.72  4753.1  300.15  4777.1  299.01
  4788.7  296.31  4796.8  296.95  4807.4  299.68  4881.1  300.46  4929.4  300.04
  4989.9  301.17    4997  299.74    5010  300.47  5017.7  299.34    5027  295.56
  5027.5  295.06  5034.1  295.56  5051.2  300.29  5071.8  302.68  5086.3  302.72
  5141.4  303.41  5187.8  306.03  5216.1  306.34  5306.3  312.73    5412  317.53
#Mann= 8 ,-1 , 0
  4145.3     .07       0    4568     .05       0  4729.9     .07       0
  4777.1     .05       0  4881.1     .07       0    5027     .05       0
  5034.1     .07       0  5086.3     .05       0
Bank Sta=5027,5034.1
XS Rating Curve= 0 ,0
Exp/Cntr=0.3,0.1

Type RM Length L Ch R = 1 ,12664   ,474,474,474
BEGIN DESCRIPTION:
LONG HOLLOW 22.0
END DESCRIPTION:
XS GIS Cut Line= 3
      2398974.98     13667424.98        2398575.       13667025.
      2398175.03     13666625.03
#Sta/Elev= 30
  4434.8  314.55  4448.9  312.98  4576.2     307  4873.2  299.84  4887.3  298.85
  4901.5  295.39  4915.6  294.66  4929.8  297.69  4943.9  297.83  4952.8  296.69
    4958  296.03  4986.3  298.24    5004  297.01  5010.8  292.43  5011.3  291.93
  5018.4  292.43  5028.7  298.03  5074.2  298.37  5085.3   297.2  5127.7  299.54
  5284.3  302.04  5319.4  303.81    5354  305.44  5396.4  305.83  5438.9  309.36
    5453  308.29  5467.2  309.99  5509.6  311.55  5537.9  313.95  5566.1  314.15
#Mann= 7 ,-1 , 0
  4434.8     .07       0  4952.8     .05       0  5010.8     .05       0
  5018.4     .05       0  5074.2     .07       0  5284.3    .035       0
  5319.4     .07       0
Bank Sta=5010.8,5018.4
XS Rating Curve= 0 ,0
Exp/Cntr=0.3,0.1

Type RM Length L Ch R = 1 ,12190   ,441,441,441
BEGIN DESCRIPTION:
LONG HOLLOW 21.0
END DESCRIPTION:
XS GIS Cut Line= 3
      2399225.02     13667425.03        2398775.       13666625.
        2398425.       13666475.
#Sta/Elev= 30
  4082.1  321.64  4226.2  315.37  4391.9  306.88  4435.6   306.9  4543.9  303.23
  4824.4  298.38    4862     297  4873.8  295.07  4889.4  295.85  4896.7  294.78
  4905.4  295.96  4919.7  294.22    4927  295.82  4942.6   296.5  4988.2  290.82
  4988.7  290.32  4995.8  290.82  5002.7  291.07  5009.1  293.79  5014.5  294.08
  5021.8  296.45  5152.3  297.62  5240.3  302.22  5250.2  303.52  5261.1  302.48
  5295.6   305.2  5317.3  304.75  5346.1  307.29    5359  308.56  5380.8  308.13
#Mann= 6 ,-1 , 0
  4082.1    .035       0  4226.2     .07       0  4988.2     .05       0
  4995.8     .07       0  5240.3    .035       0  5346.1     .07       0
Bank Sta=4988.2,4995.8
XS Rating Curve= 0 ,0
Exp/Cntr=0.3,0.1

Type RM Length L Ch R = 1 ,11749   ,207,207,207
BEGIN DESCRIPTION:
LONG HOLLOW 20.0
END DESCRIPTION:
XS GIS Cut Line= 3
        2399375.       13667075.        2398725.       13666275.
      2398524.98       13666275.
#Sta/Elev= 30
  3968.7   309.1  4110.4  305.24  4124.6  305.91    4182  304.65  4217.2  302.82
  4345.1  301.42    4353   300.6  4367.4  301.56  4445.4  300.02  4480.9   300.9
  4551.2  299.38  4573.5  299.92  4637.5  298.21  4672.7   295.8    4751  294.93
  4850.1  295.97  4864.4  295.14  4934.7  295.28  5019.5  295.63  5039.5  289.81
  5045.6  289.56  5046.1  289.06  5053.3  289.56  5059.5  294.45  5069.5   298.8
  5079.5  300.91  5099.5  302.83  5129.5  302.86    5163  304.84  5199.5  305.42
#Mann= 5 ,-1 , 0
  3968.7     .07       0  4934.7     .12       0  5045.6     .05       0
  5053.3     .12       0    5163    .035       0
Bank Sta=5045.6,5053.3
XS Rating Curve= 0 ,0
Exp/Cntr=0.3,0.1

Type RM Length L Ch R = 1 ,11542   ,263,263,263
BEGIN DESCRIPTION:
A19831
END DESCRIPTION:
XS GIS Cut Line= 4
      2399445.41     13666947.72      2399027.36     13666243.34
      2398792.57     13666071.54      2398409.48     13666094.41
#Sta/Elev= 30
    3987  306.09    4076   304.3  4119.5  304.81  4156.6  303.58  4353.4  302.56
  4624.3  299.36  4725.6  297.69  4813.5  294.66    4849  295.03  4884.5   292.4
  4907.7  294.41  4978.7  294.17  4993.4  292.35  4999.6  288.54  5003.4  288.34
  5003.9  287.84  5011.1  288.34  5014.2  288.57  5019.3  291.77  5028.9  293.63
  5070.6   296.9  5134.7  299.48  5174.7  299.39  5240.2  301.63  5254.9  302.95
  5274.9  302.15  5284.9  303.34    5323  303.68  5421.8  305.85  5480.8  306.64
#Mann= 7 ,-1 , 0
    3987     .07       0  5003.4     .05       0  5011.1     .07       0
  5019.3     .12       0  5240.2     .07       0    5323    .035       0
  5421.8     .07       0
Bank Sta=5003.4,5011.1
XS Rating Curve= 0 ,0
Exp/Cntr=0.3,0.1

Type RM Length L Ch R = 1 ,11279   ,442,442,442
BEGIN DESCRIPTION:
LONG HOLLOW 19.0
END DESCRIPTION:
XS GIS Cut Line= 3
      2399875.04       13666025.        2399075.       13665975.
        2398575.       13665925.
#Sta/Elev= 30
  4198.2  310.14  4288.4  306.17  4378.6  303.47  4408.7  303.73  4436.2  302.08
  4538.9  299.09  4619.1  297.98  4709.2  295.53  4799.4  290.59  4829.5  292.34
  4879.6  292.77  4909.6  294.11  4922.2   292.9  4959.7  292.65  4979.8  291.46
  4985.9   286.8  4986.4   286.3  4993.7   286.8  4997.3   288.2  5002.3   288.2
  5009.9  290.64  5047.5  294.38  5120.4  294.95  5190.7  297.13  5281.2  298.73
  5354.1  298.04  5401.8  300.81  5462.1  301.76  5492.2  303.22  5502.3  302.77
#Mann= 3 ,-1 , 0
  4198.2     .07       0  4985.9     .05       0  4993.7     .07       0
Bank Sta=4985.9,4993.7
XS Rating Curve= 0 ,0
Exp/Cntr=0.3,0.1

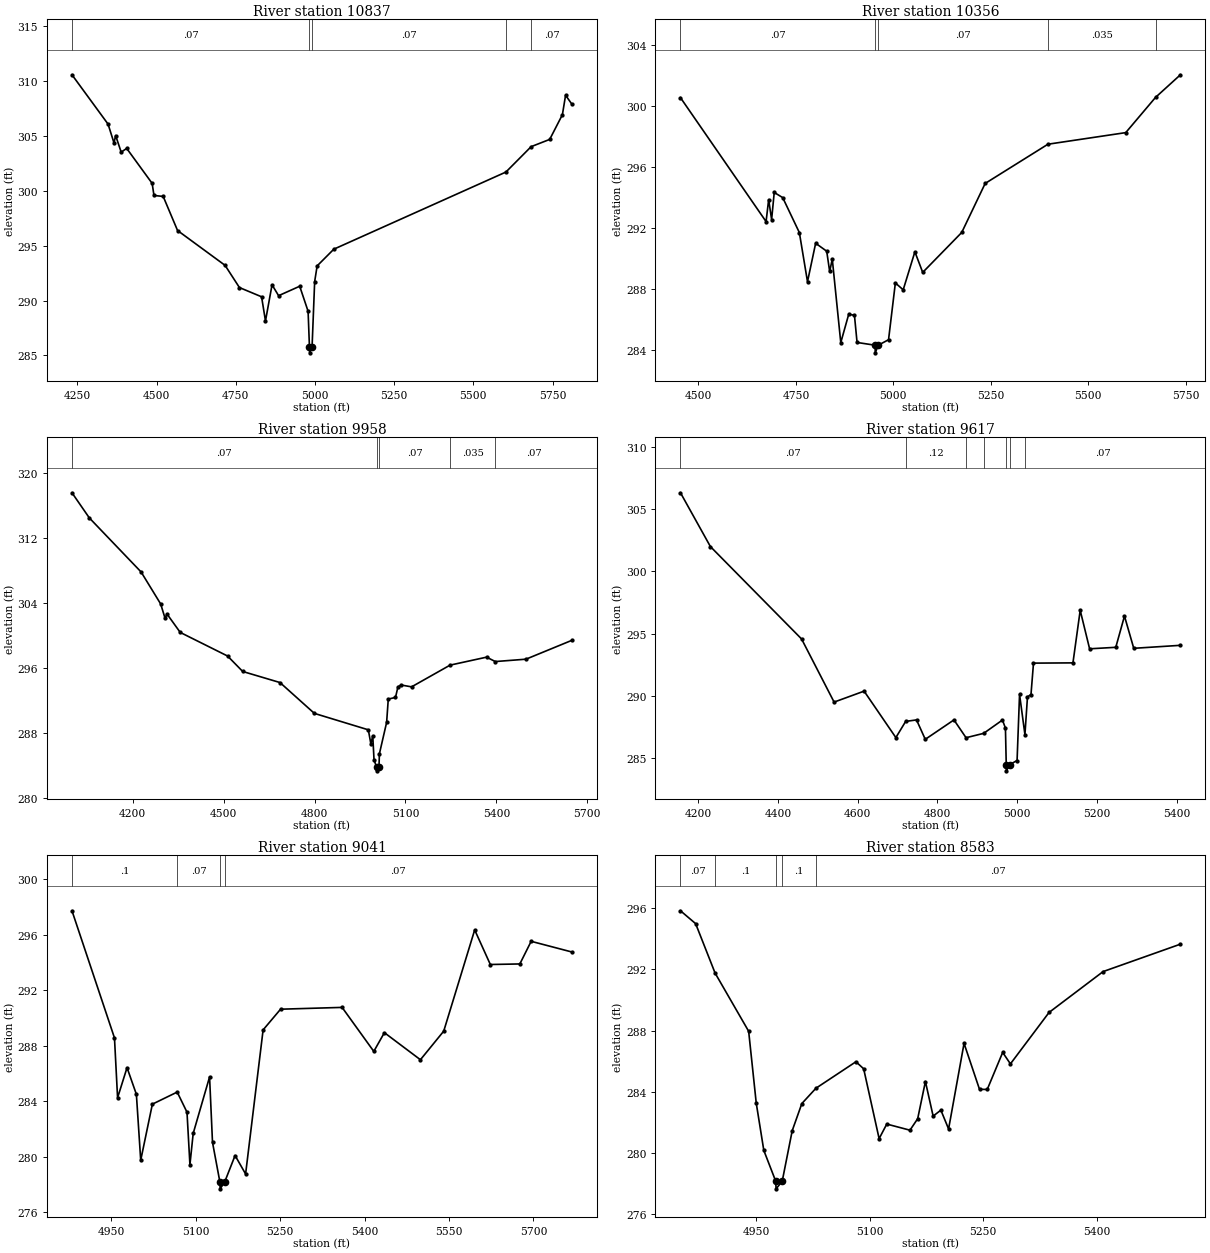
Type RM Length L Ch R = 1 ,10837   ,481,481,481
BEGIN DESCRIPTION:
LONG HOLLOW 18.0
END DESCRIPTION:
XS GIS Cut Line= 3
      2399925.04     13665825.01        2399175.       13665625.
      2398375.01       13665675.
#Sta/Elev= 30
  4233.2  310.54  4347.1  306.05  4365.8  304.34    4371  305.01  4388.5   303.5
  4405.9  303.84  4486.2  300.66    4492  299.56  4521.1  299.47  4566.4  296.37
  4716.4   293.2  4761.7  291.18  4831.6  290.34  4843.9  288.14  4864.6  291.43
  4885.3  290.44  4951.9   291.3  4978.4  289.02  4982.7  285.74  4983.2  285.24
  4990.9  285.74  4999.1  291.72  5006.9  293.15  5059.5  294.67  5602.7  301.69
  5682.3     304  5740.9  304.66    5781  306.91    5791  308.68    5811  307.86
#Mann= 5 ,-1 , 0
  4233.2     .07       0  4982.7     .05       0  4990.9     .07       0
  5602.7    .035       0  5682.3     .07       0
Bank Sta=4982.7,4990.9
XS Rating Curve= 0 ,0
Exp/Cntr=0.3,0.1

Type RM Length L Ch R = 1 ,10356   ,398,398,398
BEGIN DESCRIPTION:
LONG HOLLOW 17.0
END DESCRIPTION:
XS GIS Cut Line= 3
      2399724.97     13665724.97        2399325.       13665375.
      2398575.03       13665425.
#Sta/Elev= 30
  4453.8  300.56  4673.5  292.44  4680.1  293.88  4687.7  292.57  4694.4  294.35
  4716.2  294.01  4758.9  291.72  4779.8   288.5  4800.7  291.02  4829.1   290.5
  4836.7  289.17  4843.4  289.98  4865.2  284.51  4885.6  286.37  4900.3   286.3
    4907  284.52  4953.2  284.34  4953.7  283.84  4961.4  284.34  4987.8   284.7
  5005.3  288.42  5025.4  287.97  5055.4  290.46  5075.5  289.11  5175.7  291.73
  5235.8  294.94  5396.9  297.51  5596.6  298.27  5673.1  300.58  5736.9  302.06
#Mann= 5 ,-1 , 0
  4453.8     .07       0  4953.2     .05       0  4961.4     .07       0
  5396.9    .035       0  5673.1     .07       0
Bank Sta=4953.2,4961.4
XS Rating Curve= 0 ,0
Exp/Cntr=0.3,0.1

Type RM Length L Ch R = 1 ,9958    ,341,341,341
BEGIN DESCRIPTION:
LONG HOLLOW 16.0
END DESCRIPTION:
XS GIS Cut Line= 3
        2400075.       13665675.        2399275.       13665075.
      2398674.99       13665325.
#Sta/Elev= 30
  3999.5  317.53  4056.8  314.44  4227.6   307.8  4292.2  303.87  4306.8   302.1
    4313  302.64  4356.8  300.37    4513  297.47    4563  295.57    4686  294.21
  4799.5  290.42  4977.6   288.4    4986  286.66  4992.2  287.68  4996.4   284.7
  5004.6  283.86  5005.1  283.36  5012.8  283.86  5014.1  285.45    5038  289.32
  5043.4  292.18  5067.2  292.38  5075.3  293.67  5085.6  293.91  5120.3  293.68
  5247.4  296.35  5367.8  297.33  5396.7  296.79  5497.8  297.08  5649.5   299.4
#Mann= 5 ,-1 , 0
  3999.5     .07       0  5004.6     .05       0  5012.8     .07       0
  5247.4    .035       0  5396.7     .07       0
Bank Sta=5004.6,5012.8
XS Rating Curve= 0 ,0
Exp/Cntr=0.3,0.1

Type RM Length L Ch R = 1 ,9617    ,576,576,576
BEGIN DESCRIPTION:
A19830
END DESCRIPTION:
XS GIS Cut Line= 4
      2400029.53     13665223.98      2399462.59     13664914.74
      2399325.15     13664731.49      2398975.82     13664582.59
#Sta/Elev= 30
  4155.1  306.31  4230.2  301.99    4459  294.57  4540.6   289.5  4615.9  290.38
  4695.6  286.65  4720.2  287.95  4747.5  288.07  4769.4  286.51  4841.4  288.07
  4871.7  286.64  4915.9  286.99  4963.1  288.06  4970.6  287.41  4972.6  284.48
  4973.1  283.98  4981.1  284.48  4999.8  284.81    5006  290.12  5019.5  286.89
  5025.9  289.92  5034.7  290.11    5041  292.63    5140  292.65  5158.2  296.87
  5181.8  293.78  5247.5   293.9  5269.3  296.41  5292.6  293.82  5409.7  294.06
#Mann= 7 ,-1 , 0
  4155.1     .07       0  4720.2     .12       0  4871.7     .07       0
  4915.9     .12       0  4972.6     .05       0  4981.1     .12       0
  5019.5     .07       0
Bank Sta=4972.6,4981.1
XS Rating Curve= 0 ,0
Exp/Cntr=0.3,0.1

Type RM Length L Ch R = 1 ,9041    ,458,458,458
BEGIN DESCRIPTION:
LONG HOLLOW 15.0
END DESCRIPTION:
XS GIS Cut Line= 3
      2399874.99       13664725.        2399775.       13664675.
        2399025.       13664475.
#Sta/Elev= 30
  4880.3  297.71  4955.8  288.55  4961.3  284.24  4978.1  286.41  4994.7  284.49
  5002.4  279.74  5023.1  283.78  5067.2  284.65  5084.6   283.2  5089.8  279.42
  5095.6  281.67  5124.7  285.74  5129.9  281.03    5143  278.18  5143.5  277.68
  5151.6  278.18    5170  280.08  5188.7  278.75  5219.8  289.13  5250.8  290.62
  5360.1  290.75  5416.4  287.58  5435.2  288.93  5499.2  286.98  5540.6  289.04
  5595.6  296.33  5623.4  293.84  5675.8  293.88  5695.9  295.51  5768.3  294.74
#Mann= 4 ,-1 , 0
  4880.3      .1       0  5067.2     .07       0    5143     .05       0
  5151.6     .07       0
Bank Sta=5143,5151.6
XS Rating Curve= 0 ,0
Exp/Cntr=0.3,0.1

Type RM Length L Ch R = 1 ,8583    ,456,456,456
BEGIN DESCRIPTION:
LONG HOLLOW 14.0
END DESCRIPTION:
XS GIS Cut Line= 3
      2399824.97       13664275.        2399675.       13664275.
      2399174.98       13664375.
#Sta/Elev= 30
  4850.4  295.82  4870.4  294.98  4896.1  291.75  4940.4  287.95  4950.4  283.26
  4960.4  280.17  4976.1  278.16  4976.6  277.66  4984.7  278.16  4997.9  281.46
  5010.6  283.23  5029.2  284.23    5082  285.96  5092.2   285.5  5112.6  280.94
  5122.7  281.89  5153.3  281.49  5163.5  282.24  5173.7  284.67  5183.9  282.41
  5194.1   282.8  5204.3  281.57  5224.7  287.16  5245.1  284.16  5255.3  284.15
  5275.7  286.57  5285.9  285.82  5336.9  289.18  5408.3  291.85  5510.3  293.64
#Mann= 5 ,-1 , 0
  4850.4     .07       0  4896.1      .1       0  4976.1     .05       0
  4984.7      .1       0  5029.2     .07       0
Bank Sta=4976.1,4984.7
XS Rating Curve= 0 ,0
Exp/Cntr=0.3,0.1