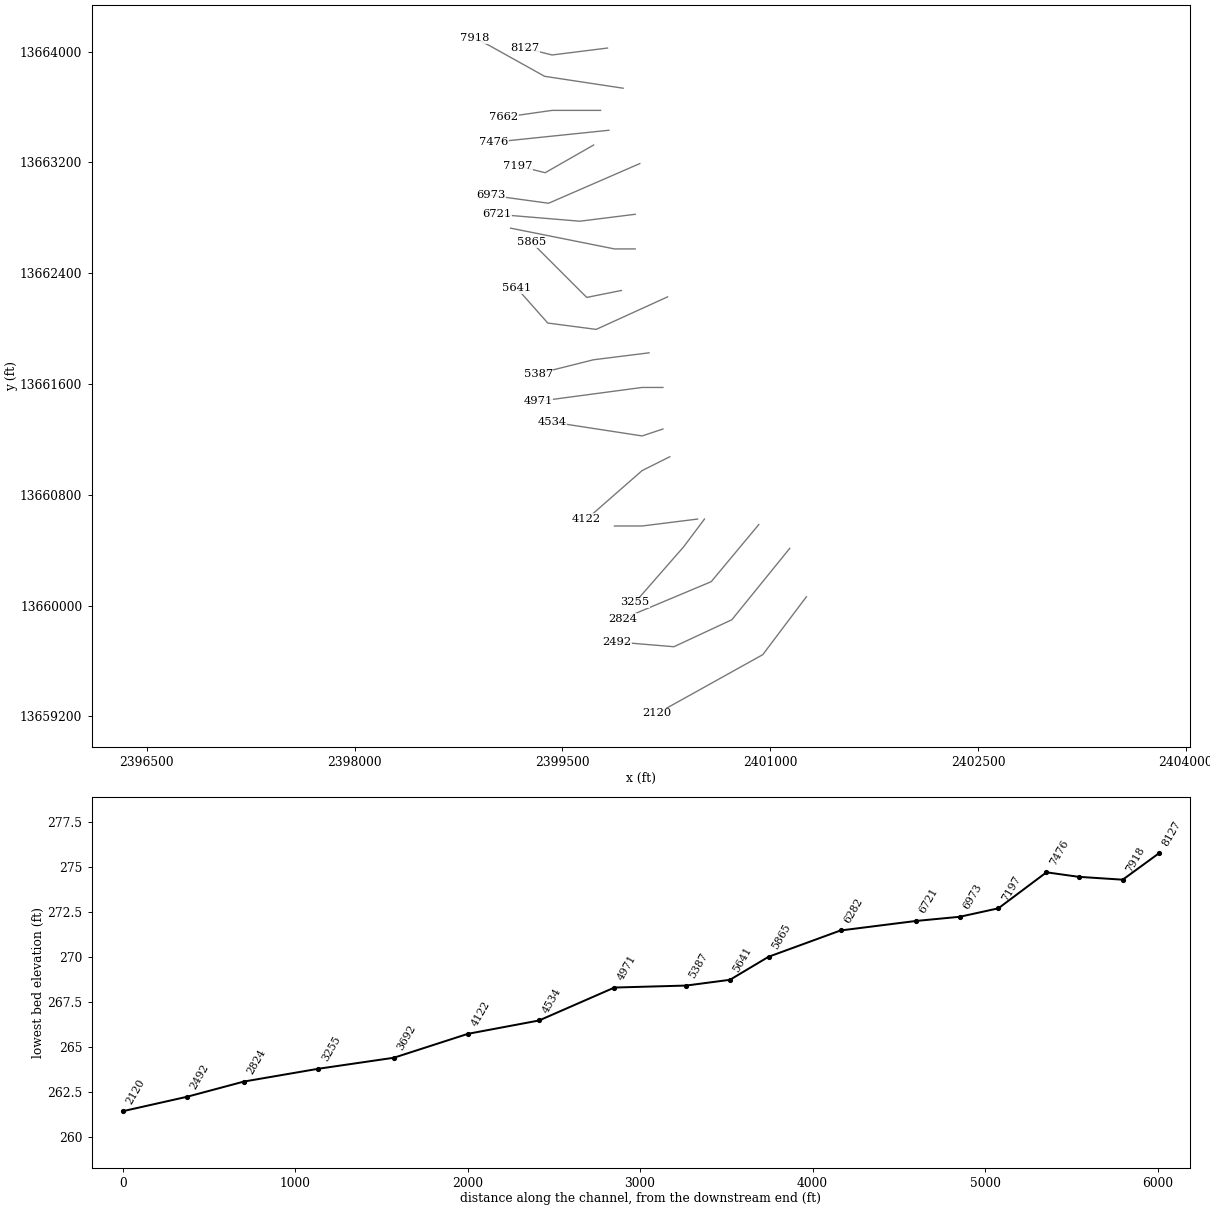
HEC-RAS study LONG HOLLOW.prj: LONG HOLLOW Base Level Engineering

--- LONG HOLLOW.g01 (geometry) --- (continued)

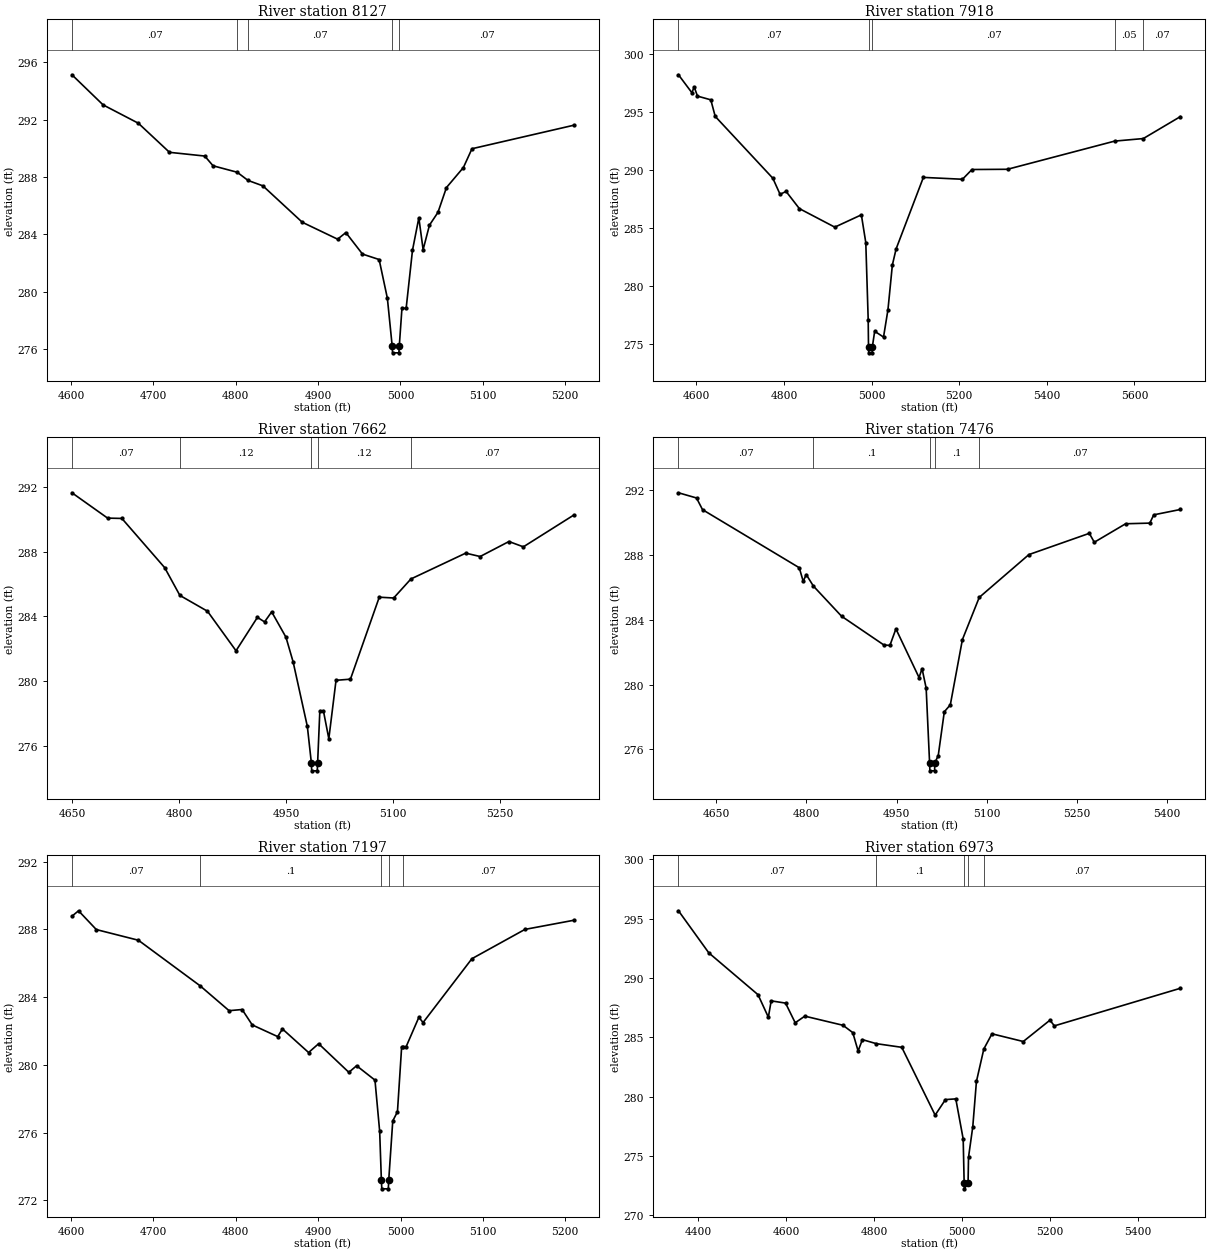
Type RM Length L Ch R = 1 ,8127    ,209,209,209
BEGIN DESCRIPTION:
LONG HOLLOW 13.0
END DESCRIPTION:
XS GIS Cut Line= 3
      2399824.98       13664025.        2399425.       13663975.
      2399225.04     13664024.99
#Sta/Elev= 30
  4601.2  295.13    4639  293.03  4681.8  291.75  4719.6  289.72  4762.4  289.46
  4772.5  288.78  4801.8  288.33  4814.9  287.76    4833  287.38  4880.8  284.84
  4923.7  283.66  4933.7  284.12  4953.9  282.62  4974.1  282.24  4984.1  279.54
  4989.9  276.23  4990.4  275.73  4998.1  275.73  4998.6  276.23  5001.8  278.84
  5006.9  278.84  5014.6  282.89  5022.3  285.15  5027.5  282.93  5035.2  284.64
  5045.5  285.53  5055.8  287.26  5076.4  288.66  5086.8  289.97  5210.4  291.61
#Mann= 5 ,-1 , 0
  4601.2     .07       0  4801.8      .1       0  4814.9     .07       0
  4989.9     .05       0  4998.6     .07       0
Bank Sta=4989.9,4998.6
XS Rating Curve= 0 ,0
Exp/Cntr=0.3,0.1

Type RM Length L Ch R = 1 ,7918    ,256,256,256
BEGIN DESCRIPTION:
A19829
END DESCRIPTION:
XS GIS Cut Line= 4
      2399937.92     13663735.03      2399370.97     13663820.94
      2398970.09     13664044.28       2398868.5     13664095.08
#Sta/Elev= 30
    4559  298.25  4589.7   296.7  4594.8  297.21  4602.4  296.41  4632.8  296.09
  4642.9  294.66  4774.4  289.33    4791  287.94  4804.7  288.19    4835  286.71
  4915.9  285.11  4976.6  286.17  4986.7  283.78  4992.2  277.13  4992.9  274.77
  4993.4  274.27  5001.1  274.27  5001.6  274.77    5007  276.13  5027.2  275.63
  5037.3  277.98  5047.4  281.85    5056  283.24  5118.2   289.4  5207.5  289.24
  5229.2  290.08  5310.3   290.1    5555  292.53  5620.4  292.75  5704.9  294.64
#Mann= 5 ,-1 , 0
    4559     .07       0  4992.9     .05       0  5001.6     .07       0
    5555     .05       0  5620.4     .07       0
Bank Sta=4992.9,5001.6
XS Rating Curve= 0 ,0
Exp/Cntr=0.3,0.1

Type RM Length L Ch R = 1 ,7662    ,186,186,186
BEGIN DESCRIPTION:
LONG HOLLOW 12.0
END DESCRIPTION:
XS GIS Cut Line= 3
      2399774.97       13663575.        2399425.       13663575.
      2399075.02       13663525.
#Sta/Elev= 30
    4650  291.66    4700  290.09    4720  290.07    4780  287.02  4801.3   285.3
    4840  284.32    4880  281.87    4910  283.94    4920  283.66    4930  284.28
    4950  282.71    4960  281.19    4980  277.18  4985.6  274.93  4986.1  274.43
  4993.9  274.43  4994.4  274.93  4997.5  278.15  5002.5  278.15  5010.1  276.42
  5020.2  280.04  5040.4  280.11  5080.8  285.19    5101  285.14  5125.2  286.32
    5202  287.92  5222.2  287.71  5262.6  288.64  5282.8  288.31  5353.5  290.28
#Mann= 5 ,-1 , 0
    4650     .07       0  4801.3     .12       0  4985.6     .05       0
  4994.4     .12       0  5125.2     .07       0
Bank Sta=4985.6,4994.4
XS Rating Curve= 0 ,0
Exp/Cntr=0.3,0.1

Type RM Length L Ch R = 1 ,7476    ,279,279,279
BEGIN DESCRIPTION:
A19828
END DESCRIPTION:
XS GIS Cut Line= 2
      2399834.81     13663431.52      2399004.45     13663345.62
#Sta/Elev= 30
  4587.3  291.82  4617.3   291.5  4627.3  290.78  4788.2   287.2  4794.8  286.36
  4799.8  286.78  4811.7  286.07  4858.6  284.21  4928.9  282.44    4939  282.41
    4949  283.43  4987.5  280.43  4992.5  280.98  4999.3  279.78    5005  275.18
  5005.5  274.68  5013.3  274.68  5013.8  275.18  5019.4  275.62  5029.5  278.32
  5039.5  278.75  5059.6  282.77  5087.6  285.37  5170.2  288.01  5270.7  289.32
    5279  288.77  5331.1  289.91  5371.3  289.95  5377.9  290.46  5422.1  290.79
#Mann= 5 ,-1 , 0
  4587.3     .07       0  4811.7      .1       0    5005     .05       0
  5013.8      .1       0  5087.6     .07       0
Bank Sta=5005,5013.8
XS Rating Curve= 0 ,0
Exp/Cntr=0.3,0.1

Type RM Length L Ch R = 1 ,7197    ,224,224,224
BEGIN DESCRIPTION:
LONG HOLLOW 11.0
END DESCRIPTION:
XS GIS Cut Line= 3
      2399725.03     13663325.02        2399375.       13663125.
      2399175.01       13663175.
#Sta/Elev= 30
    4601  288.78    4609   289.1  4630.6  287.99  4681.7  287.36  4756.6  284.67
  4791.8   283.2  4807.6  283.27  4819.9  282.36  4850.8  281.67  4856.6  282.12
  4888.3  280.73  4900.5  281.25  4937.2  279.56  4946.6  279.95  4968.9   279.1
  4974.6  276.08  4976.7  273.18  4977.2  272.68  4985.1  272.68  4985.6  273.18
  4990.5  276.69  4996.2  277.23  5001.3  281.07  5002.5  281.07  5006.7  281.07
  5022.2  282.81  5027.3   282.5  5086.6  286.27    5151     288  5210.3  288.54
#Mann= 5 ,-1 , 0
    4601     .07       0  4756.6      .1       0  4976.7     .05       0
  4985.6      .1       0  5002.5     .07       0
Bank Sta=4976.7,4985.6
XS Rating Curve= 0 ,0
Exp/Cntr=0.3,0.1

Type RM Length L Ch R = 1 ,6973    ,252,252,252
BEGIN DESCRIPTION:
A19827
END DESCRIPTION:
XS GIS Cut Line= 3
      2400058.16     13663190.99       2399399.6     13662904.66
      2398981.52     13662961.93
#Sta/Elev= 30
  4355.6  295.67  4424.5  292.12  4536.3  288.59  4559.8  286.69  4566.2  288.07
  4598.9  287.88  4620.8  286.22  4642.6  286.78  4729.3  286.01  4751.6  285.39
  4763.7  283.84  4773.4   284.8  4804.9  284.46  4862.9  284.15  4938.7  278.43
  4962.1  279.74  4985.6   279.8  5002.4  276.42  5004.6  272.71  5005.1  272.21
  5013.5  272.71  5014.5  274.87  5024.2  277.45  5032.5  281.27  5049.3  284.01
  5067.8  285.29  5138.9  284.64  5199.5  286.44  5209.6  285.96  5495.7  289.13
#Mann= 5 ,-1 , 0
  4355.6     .07       0  4804.9      .1       0  5004.6     .05       0
  5013.5      .1       0  5049.3     .07       0
Bank Sta=5004.6,5013.5
XS Rating Curve= 0 ,0
Exp/Cntr=0.3,0.1

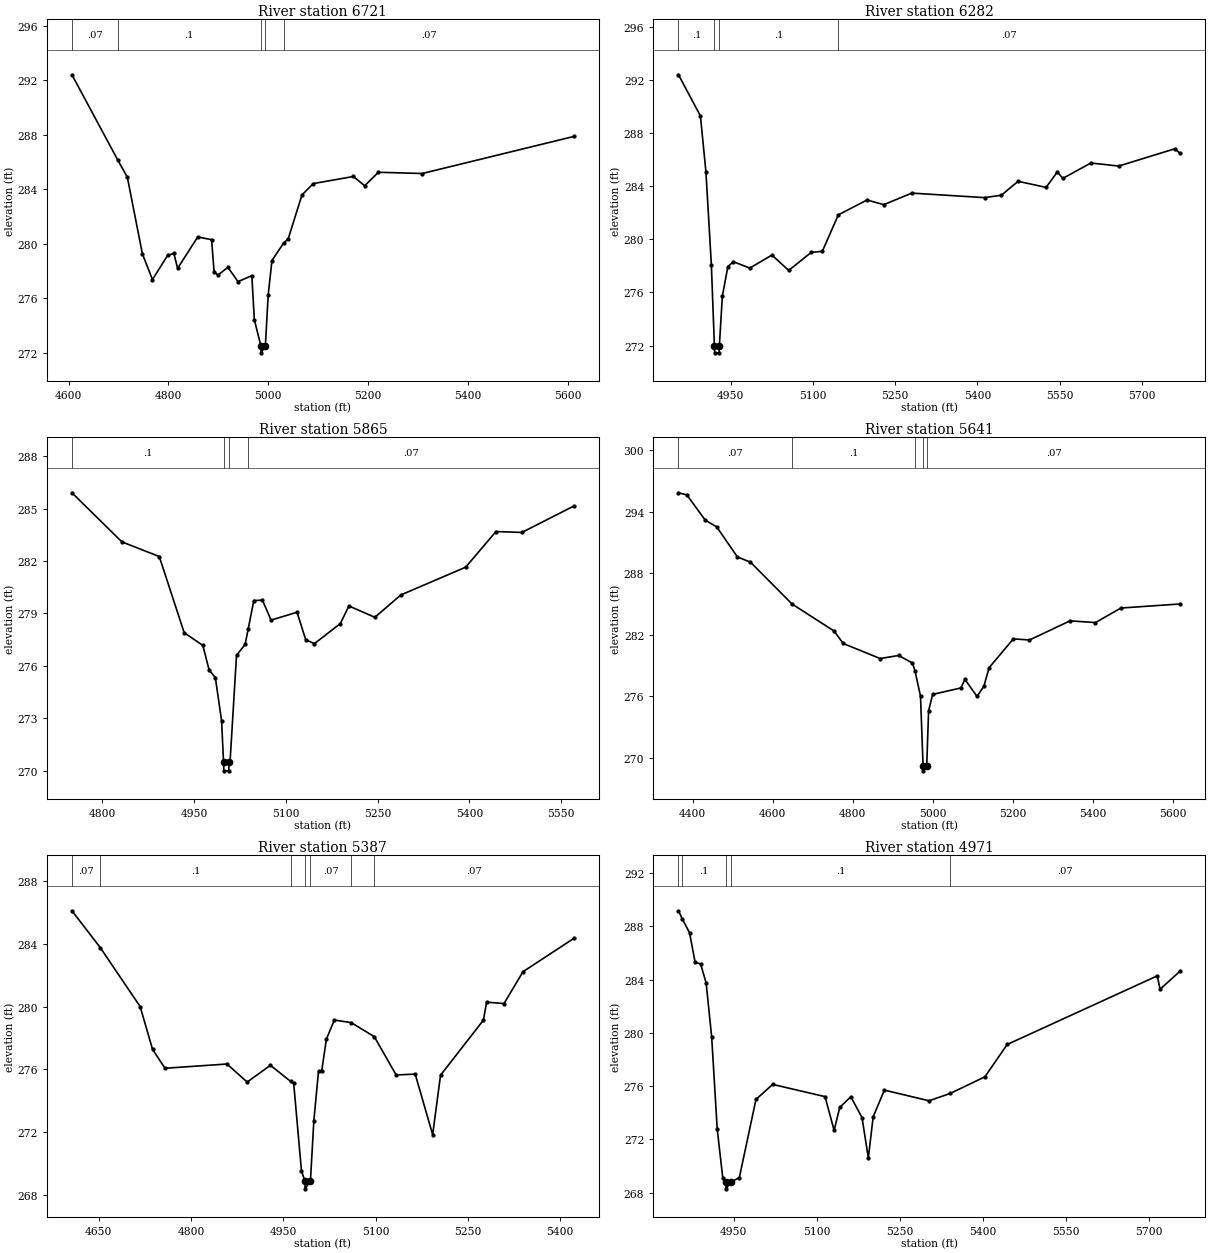
Type RM Length L Ch R = 1 ,6721    ,439,439,439
BEGIN DESCRIPTION:
LONG HOLLOW 10.0
END DESCRIPTION:
XS GIS Cut Line= 3
      2400025.02       13662825.        2399625.       13662775.
      2399025.02       13662825.
#Sta/Elev= 30
  4606.7   292.4    4698  286.17  4717.6  284.89  4747.8  279.25    4768  277.36
  4798.2  279.13  4810.8  279.28  4818.4  278.19  4858.7  280.49  4886.4  280.29
  4891.4  277.94    4899  277.69  4919.1  278.26  4939.3  277.21    4967  277.65
    4972  274.42  4985.2  272.48  4985.7  271.98  4994.1  272.48  4999.8  276.24
  5007.3  278.76  5030.5  280.03  5039.9  280.36  5067.5  283.58  5090.1  284.41
  5170.4  284.93    5193  284.25  5220.6  285.24  5308.4  285.15  5611.9  287.87
#Mann= 5 ,-1 , 0
  4606.7     .07       0    4698      .1       0  4985.2     .05       0
  4994.1      .1       0  5030.5     .07       0
Bank Sta=4985.2,4994.1
XS Rating Curve= 0 ,0
Exp/Cntr=0.3,0.1

Type RM Length L Ch R = 1 ,6282    ,417,417,417
BEGIN DESCRIPTION:
LONG HOLLOW 9.0
END DESCRIPTION:
XS GIS Cut Line= 3
      2400024.97       13662575.        2399875.       13662575.
      2399125.03     13662724.99
#Sta/Elev= 30
  4855.1  292.41  4895.1  289.31  4905.1  285.11  4915.1  278.06  4920.6  271.95
  4921.1  271.45  4929.1  271.45  4929.6  271.95  4935.1  275.73  4945.1  277.94
  4955.1  278.32  4985.1  277.84  5025.5  278.82  5056.1  277.66  5096.9  279.02
  5117.3   279.1  5146.5  281.85  5198.8  282.97  5229.4  282.62  5280.4  283.49
    5413  283.15  5443.6  283.33  5474.2  284.38  5525.2  283.92  5545.6  285.08
  5555.8   284.6  5606.8  285.76  5657.7  285.53  5759.7  286.83  5769.9  286.48
#Mann= 4 ,-1 , 0
  4855.1      .1       0  4920.6     .05       0  4929.6      .1       0
  5146.5     .07       0
Bank Sta=4920.6,4929.6
XS Rating Curve= 0 ,0
Exp/Cntr=0.3,0.1

Type RM Length L Ch R = 1 ,5865    ,224,224,224
BEGIN DESCRIPTION:
LONG HOLLOW 8.0
END DESCRIPTION:
XS GIS Cut Line= 3
      2399924.98       13662275.        2399675.       13662225.
      2399275.01     13662624.99
#Sta/Elev= 30
  4750.2  285.91  4831.8   283.1    4893  282.26  4933.7   277.9  4964.3  277.17
  4974.5  275.76  4984.7  275.33  4994.9  272.85  4998.1  270.49  4998.6  269.99
  5006.6  269.99  5007.1  270.49  5008.7  270.49  5019.3   276.6  5033.4  277.23
  5038.5  278.13  5047.6  279.74  5061.7  279.76  5075.8  278.62  5118.3  279.07
  5132.4   277.5  5146.6  277.27    5189  278.42  5203.1  279.43  5245.5  278.78
    5288  280.06    5394  281.65  5443.5  283.69    5486  283.64  5570.8  285.15
#Mann= 4 ,-1 , 0
  4750.2      .1       0  4998.1     .05       0  5007.1      .1       0
  5038.5     .07       0
Bank Sta=4998.1,5007.1
XS Rating Curve= 0 ,0
Exp/Cntr=0.3,0.1

Type RM Length L Ch R = 1 ,5641    ,254,254,254
BEGIN DESCRIPTION:
A19826
END DESCRIPTION:
XS GIS Cut Line= 4
      2400258.64     13662228.92       2399743.2     13661994.11
      2399393.87     13662039.92      2399171.35     13662290.98
#Sta/Elev= 30
  4364.8  295.85  4385.8  295.64  4431.9  293.17  4460.4  292.52    4512  289.59
  4544.6  289.08  4648.4     285  4753.5  282.36  4776.6  281.14  4868.8  279.67
  4914.9  279.97  4949.6  279.23  4955.9  278.47  4969.7  275.98  4976.1  269.21
  4976.6  268.71  4985.2  269.21  4989.9  274.58    5000  276.17  5070.6   276.8
  5080.7  277.64  5110.9  275.97  5128.2  276.98  5141.2  278.78  5201.7  281.59
    5242  281.48  5343.4  283.35  5406.9  283.18  5470.5   284.6    5619     285
#Mann= 5 ,-1 , 0
  4364.8     .07       0  4648.4      .1       0  4955.9     .07       0
  4976.1     .05       0  4985.2     .07       0
Bank Sta=4976.1,4985.2
XS Rating Curve= 0 ,0
Exp/Cntr=0.3,0.1

Type RM Length L Ch R = 1 ,5387    ,416,416,416
BEGIN DESCRIPTION:
LONG HOLLOW 7.0
END DESCRIPTION:
XS GIS Cut Line= 3
      2400124.99       13661825.        2399725.       13661775.
      2399325.01       13661675.
#Sta/Elev= 30
  4606.7   286.1  4652.8  283.75  4717.5     280  4737.7  277.27  4757.9  276.07
  4858.6  276.34  4891.4  275.19  4929.2  276.26  4962.1  275.23    4967  275.11
  4979.6  269.54  4985.1  268.89  4985.6  268.39  4994.2  268.89  4999.7  272.71
  5007.3  275.87  5012.4  275.87  5020.1  277.92    5033  279.14  5060.3  278.98
    5098  278.08  5133.5  275.64  5164.4   275.7  5192.8  271.84  5205.6  275.63
  5275.2  279.13  5280.4  280.28  5308.7  280.19  5339.6  282.22  5422.1  284.34
#Mann= 7 ,-1 , 0
  4606.7     .07       0  4652.8      .1       0  4962.1     .07       0
  4985.1     .05       0  4994.2     .07       0  5060.3      .1       0
    5098     .07       0
Bank Sta=4985.1,4994.2
XS Rating Curve= 0 ,0
Exp/Cntr=0.3,0.1

Type RM Length L Ch R = 1 ,4971    ,437,437,437
BEGIN DESCRIPTION:
LONG HOLLOW 6.0
END DESCRIPTION:
XS GIS Cut Line= 3
      2400225.03       13661575.        2400075.       13661575.
      2399324.97       13661475.
#Sta/Elev= 30
    4850  289.18  4857.1  288.55    4870  287.53    4880  285.32    4890  285.18
    4900  283.75    4910  279.68    4920  272.77    4930  269.11  4935.5  268.78
    4936  268.28  4944.6  268.78    4960  269.13    4990     275  5020.2  276.13
  5114.8  275.21  5131.2  272.67  5141.3   274.4  5161.4   275.2  5181.6  273.64
    5193   270.6  5201.8   273.7    5222   275.7  5302.7   274.9  5340.9  275.45
  5403.6   276.7  5443.9  279.13  5715.1  284.29  5720.1  283.28  5756.7  284.66
#Mann= 5 ,-1 , 0
    4850     .12       0  4857.1      .1       0  4935.5     .05       0
  4944.6      .1       0  5340.9     .07       0
Bank Sta=4935.5,4944.6
XS Rating Curve= 0 ,0
Exp/Cntr=0.3,0.1

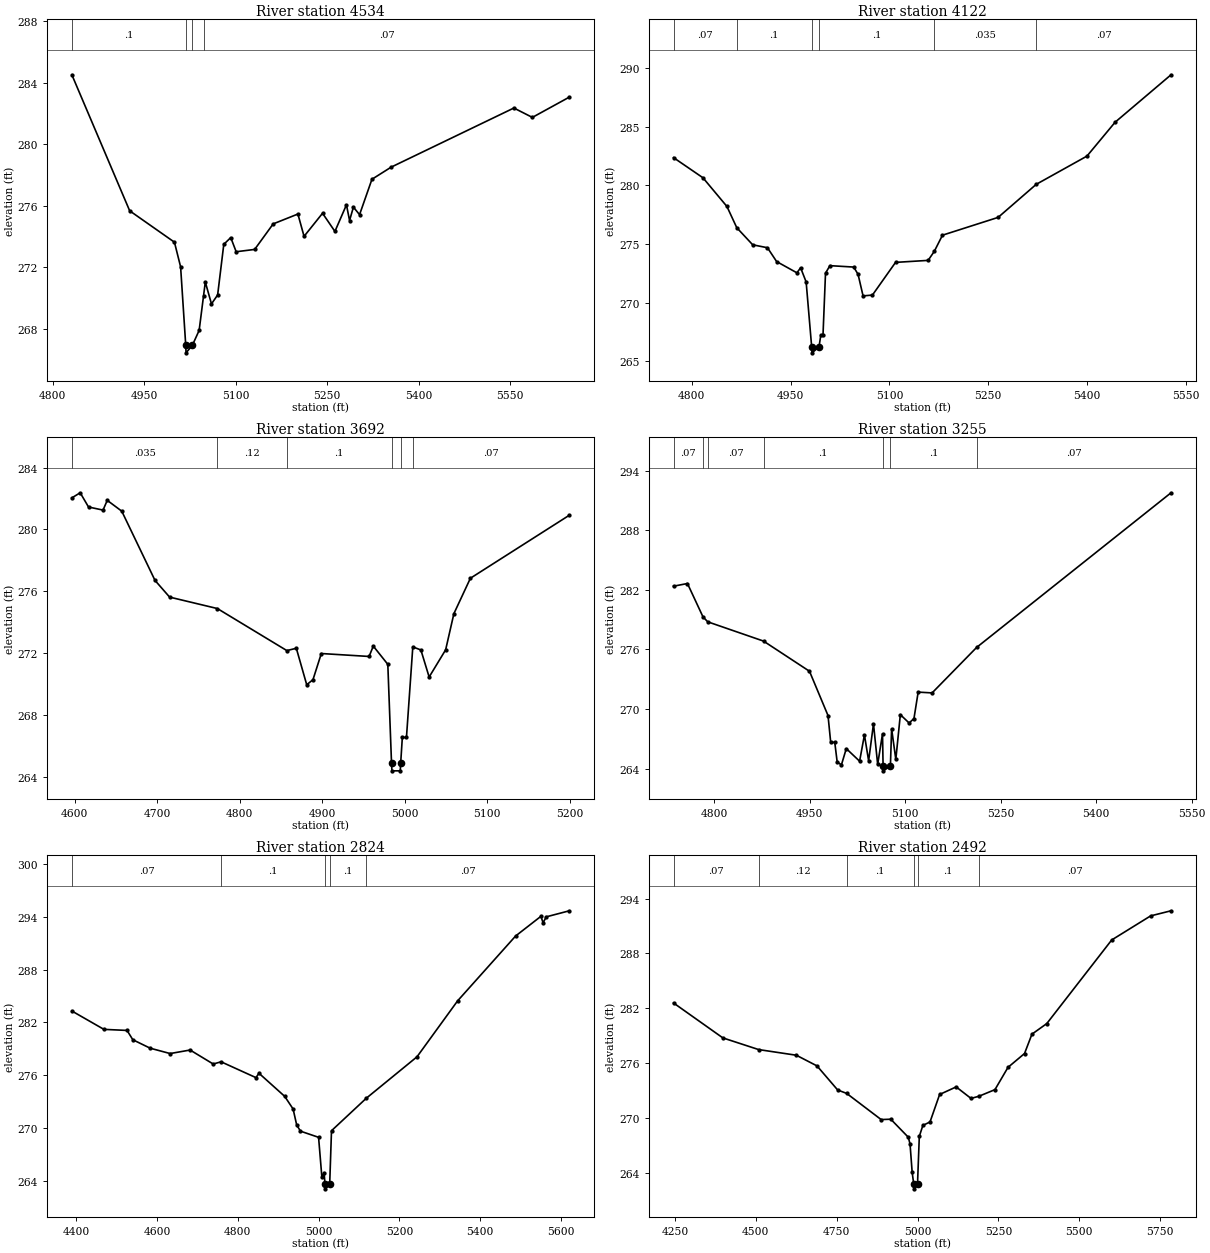
Type RM Length L Ch R = 1 ,4534    ,412,412,412
BEGIN DESCRIPTION:
LONG HOLLOW 5.0
END DESCRIPTION:
XS GIS Cut Line= 3
      2400224.98     13661274.99        2400075.       13661225.
      2399425.03     13661324.99
#Sta/Elev= 30
  4831.4  284.52  4926.2  275.68  4999.6  273.64  5009.7  272.04  5018.1  266.95
  5018.6  266.45  5029.1  266.95  5040.1  267.91  5047.3  270.15  5050.2  271.05
  5060.3  269.63  5070.4  270.21  5080.5   273.5  5091.9  273.94  5100.8  273.02
  5131.1  273.17  5161.5  274.83    5202  275.47  5212.1  274.02  5242.4  275.52
  5262.7  274.34  5281.6  276.07  5286.7  275.05    5293  275.92  5303.1  275.43
  5323.4  277.73    5355  278.52  5556.1  282.36  5586.4  281.75  5647.1  283.07
#Mann= 4 ,-1 , 0
  4831.4      .1       0  5018.1     .05       0  5029.1      .1       0
  5047.3     .07       0
Bank Sta=5018.1,5029.1
XS Rating Curve= 0 ,0
Exp/Cntr=0.3,0.1

Type RM Length L Ch R = 1 ,4122    ,430,430,430
BEGIN DESCRIPTION:
LONG HOLLOW 4.0
END DESCRIPTION:
XS GIS Cut Line= 3
      2400275.02     13661075.01        2400075.       13660975.
      2399675.02     13660625.02
#Sta/Elev= 30
  4772.3  282.37    4817  280.65  4853.4   278.2  4868.3  276.39  4892.5  274.93
  4914.9  274.68  4928.8   273.5  4959.6  272.54  4965.2  272.97  4973.6  271.76
    4982  266.21  4982.5  265.71  4993.1  266.21  4995.9  267.24  4999.2  267.24
    5003  272.51  5009.7  273.15  5045.8  273.03  5052.4  272.41    5060  270.57
  5074.2  270.64  5109.3  273.43  5158.7   273.6  5168.1  274.37  5180.5  275.75
    5265  277.27  5322.8  280.09  5399.8   282.5  5442.5  285.39  5527.4  289.44
#Mann= 6 ,-1 , 0
  4772.3     .07       0  4868.3      .1       0    4982     .05       0
  4993.1      .1       0  5168.1    .035       0  5322.8     .07       0
Bank Sta=4982,4993.1
XS Rating Curve= 0 ,0
Exp/Cntr=0.3,0.1

Type RM Length L Ch R = 1 ,3692    ,437,437,437
BEGIN DESCRIPTION:
LONG HOLLOW 3.0
END DESCRIPTION:
XS GIS Cut Line= 3
      2400475.04       13660625.        2400075.       13660575.
      2399875.05       13660575.
#Sta/Elev= 30
  4596.4  282.04  4606.5  282.37  4616.6  281.45  4634.2  281.25  4639.3  281.88
  4656.9  281.18  4697.2   276.7  4714.9  275.62  4772.8  274.88    4857  272.16
  4868.5  272.31  4881.1  269.95  4888.7  270.28  4898.8  271.97  4956.7  271.78
  4961.8  272.45  4979.4  271.27  4983.9  264.88  4984.4  264.38  4994.5  264.38
    4995  264.88    4997  266.54    5002  266.54  5009.7   272.4  5019.5   272.2
  5029.5  270.45  5049.5  272.21  5059.5  274.55  5079.5  276.84  5199.5  280.92
#Mann= 6 ,-1 , 0
  4596.4    .035       0  4772.8     .12       0    4857      .1       0
  4983.9     .05       0    4995      .1       0  5009.7     .07       0
Bank Sta=4983.9,4995
XS Rating Curve= 0 ,0
Exp/Cntr=0.3,0.1

Type RM Length L Ch R = 1 ,3255    ,431,431,431
BEGIN DESCRIPTION:
LONG HOLLOW 2.0
END DESCRIPTION:
XS GIS Cut Line= 3
      2400525.01     13660625.02        2400375.       13660425.
      2400025.02     13660025.02
#Sta/Elev= 30
  4736.1  282.37    4758  282.64  4782.4  279.28  4789.9  278.78  4877.5  276.84
  4949.7   273.8  4978.8  269.34    4983  266.64  4989.4  266.64  4993.2  264.65
  4999.9  264.38  5007.5  266.01  5028.4  264.74    5036  267.39  5042.6  264.78
  5050.2   268.5  5056.8  264.42  5064.4   267.5  5065.3  264.27  5065.8  263.77
  5076.8  264.27  5078.7     268  5085.3  264.92  5092.4  269.43  5106.2  268.59
  5113.8  269.04  5120.4   271.7  5142.3  271.62  5212.2   276.2  5517.6  291.78
#Mann= 7 ,-1 , 0
  4736.1     .07       0  4782.4    .035       0  4789.9     .07       0
  4877.5      .1       0  5065.3     .05       0  5076.8      .1       0
  5212.2     .07       0
Bank Sta=5065.3,5076.8
XS Rating Curve= 0 ,0
Exp/Cntr=0.3,0.1

Type RM Length L Ch R = 1 ,2824    ,332,332,332
BEGIN DESCRIPTION:
A19825
END DESCRIPTION:
XS GIS Cut Line= 3
      2400917.19     13660585.34      2400573.58     13660173.01
       2399932.2     13659903.86
#Sta/Elev= 30
  4388.9  283.29  4468.3   281.2  4525.6  281.08  4539.9  280.02  4582.8  279.06
  4632.3  278.45  4681.8  278.85    4739  277.26  4758.6  277.51  4844.9  275.71
  4852.3  276.21  4916.1  273.58  4936.9  272.14  4945.8  270.32  4955.2  269.62
    5000  268.92  5008.2  264.36  5013.6   264.9    5016  263.56  5016.5  263.06
  5027.5  263.56    5032  269.67  5118.3  273.37  5243.8  278.08  5344.3  284.44
    5488  291.82  5550.7  294.06  5556.1  293.32  5563.9     294  5621.2  294.69
#Mann= 5 ,-1 , 0
  4388.9     .07       0  4758.6      .1       0    5016     .05       0
  5027.5      .1       0  5118.3     .07       0
Bank Sta=5016,5027.5
XS Rating Curve= 0 ,0
Exp/Cntr=0.3,0.1

Type RM Length L Ch R = 1 ,2492    ,372,372,372
BEGIN DESCRIPTION:
A19824
END DESCRIPTION:
XS GIS Cut Line= 4
      2401140.51     13660413.52      2400722.47     13659898.13
      2400304.42     13659703.42      2399892.14     13659737.78
#Sta/Elev= 30
  4245.5  282.58  4398.1  278.75  4508.8  277.47  4625.4  276.85  4689.3  275.68
  4753.2  273.04  4780.9  272.67  4887.6   269.8  4917.4  269.84  4971.4  267.87
  4976.9  267.14  4983.5  264.02  4988.4  262.71  4988.9  262.21    5000  262.71
  5005.6  267.96  5016.6  269.16  5038.7  269.54  5068.4  272.55  5119.6  273.38
  5165.4  272.12  5189.5  272.35  5239.5  273.08  5279.8  275.52    5331  277.04
  5353.9  279.16  5399.8  280.32  5600.5  289.48  5720.9  292.12    5784  292.68
#Mann= 6 ,-1 , 0
  4245.5     .07       0  4508.8     .12       0  4780.9      .1       0
  4988.4     .05       0    5000      .1       0  5189.5     .07       0
Bank Sta=4988.4,5000
XS Rating Curve= 0 ,0
Exp/Cntr=0.3,0.1

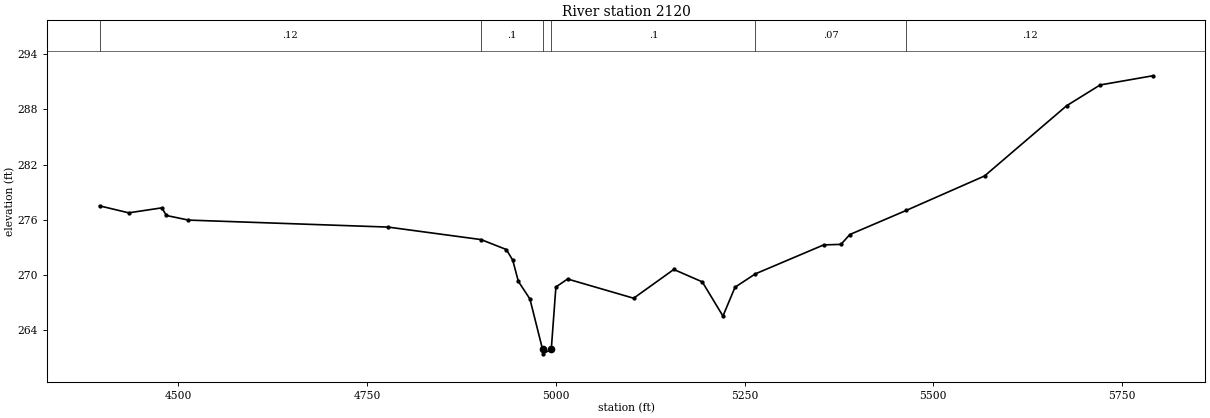
Type RM Length L Ch R = 1 ,2120    ,407,407,407
BEGIN DESCRIPTION:
A19823
END DESCRIPTION:
XS GIS Cut Line= 3
       2401260.8     13660064.21      2400945.82     13659646.15
      2400184.12     13659222.35
#Sta/Elev= 30
  4395.5  277.51  4434.2  276.75  4477.9  277.29  4484.2  276.46  4513.3  275.96
  4777.7   275.2  4900.9  273.84  4934.3  272.76  4942.8  271.61  4950.3  269.29
  4965.6  267.38  4982.3  261.91  4982.8  261.41  4993.9  261.91    5000  268.68
  5015.5  269.55    5103  267.46  5156.2  270.59  5193.9  269.24  5221.3  265.52
  5237.3  268.66  5264.2  270.11  5354.7  273.26  5377.6  273.32  5389.4  274.39
  5464.3  277.02  5567.8  280.76  5676.5   288.4  5720.9  290.66  5790.6  291.66
#Mann= 6 ,-1 , 0
  4395.5     .12       0  4900.9      .1       0  4982.3     .05       0
  4993.9      .1       0  5264.2     .07       0  5464.3     .12       0
Bank Sta=4982.3,4993.9
XS Rating Curve= 0 ,0
Exp/Cntr=0.3,0.1