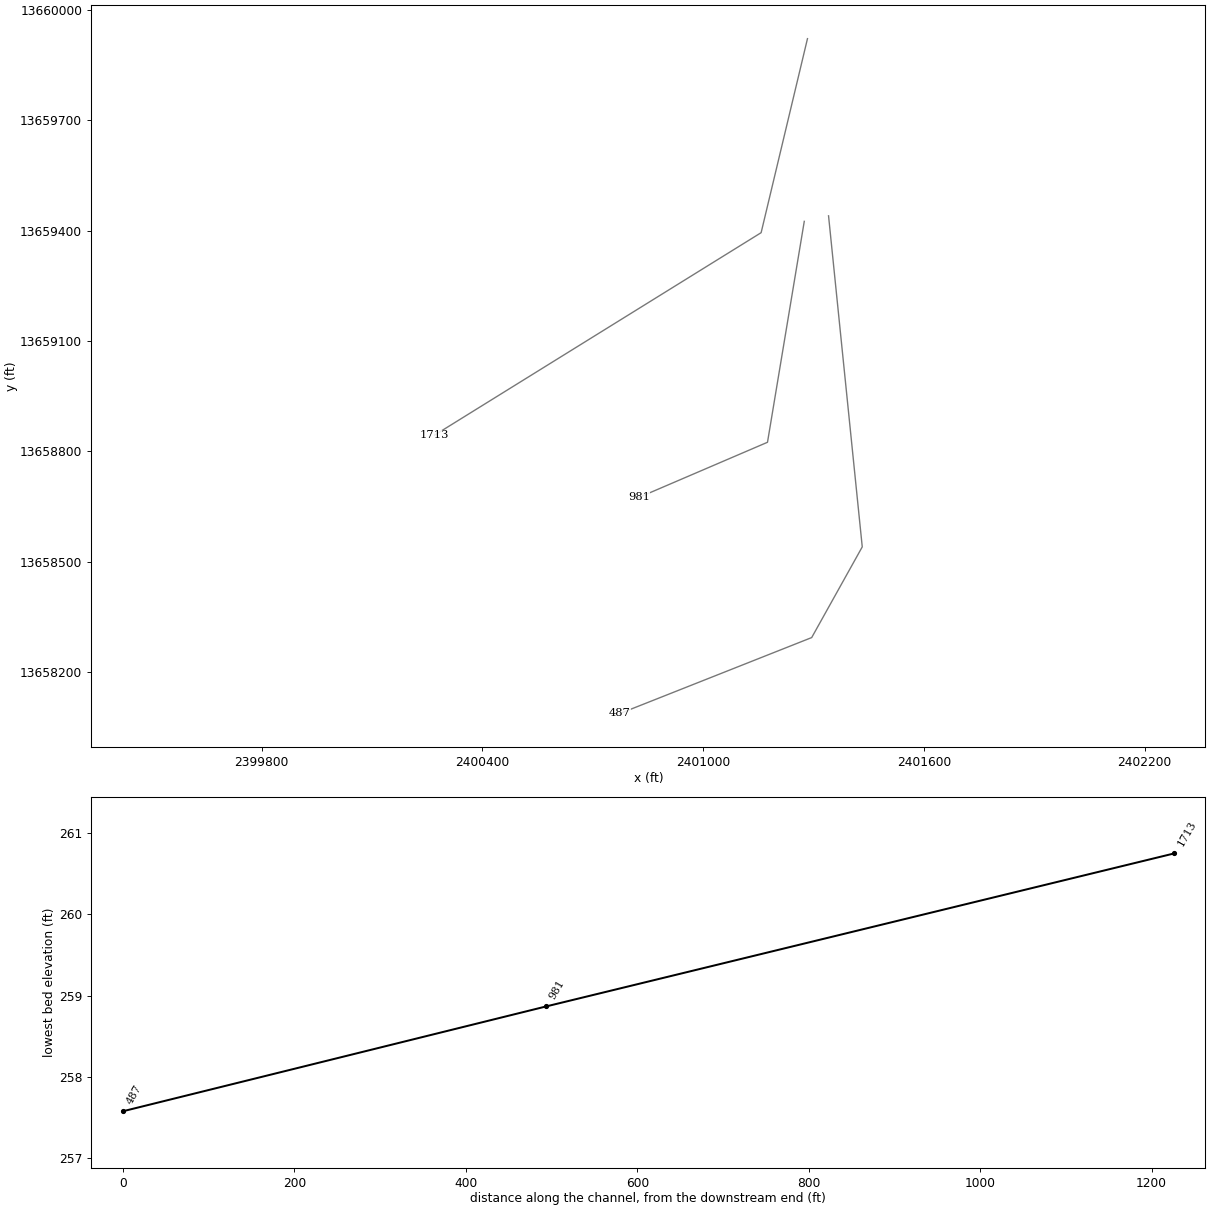
HEC-RAS study LONG HOLLOW.prj: LONG HOLLOW Base Level Engineering

--- LONG HOLLOW.g01 (geometry) --- (continued)

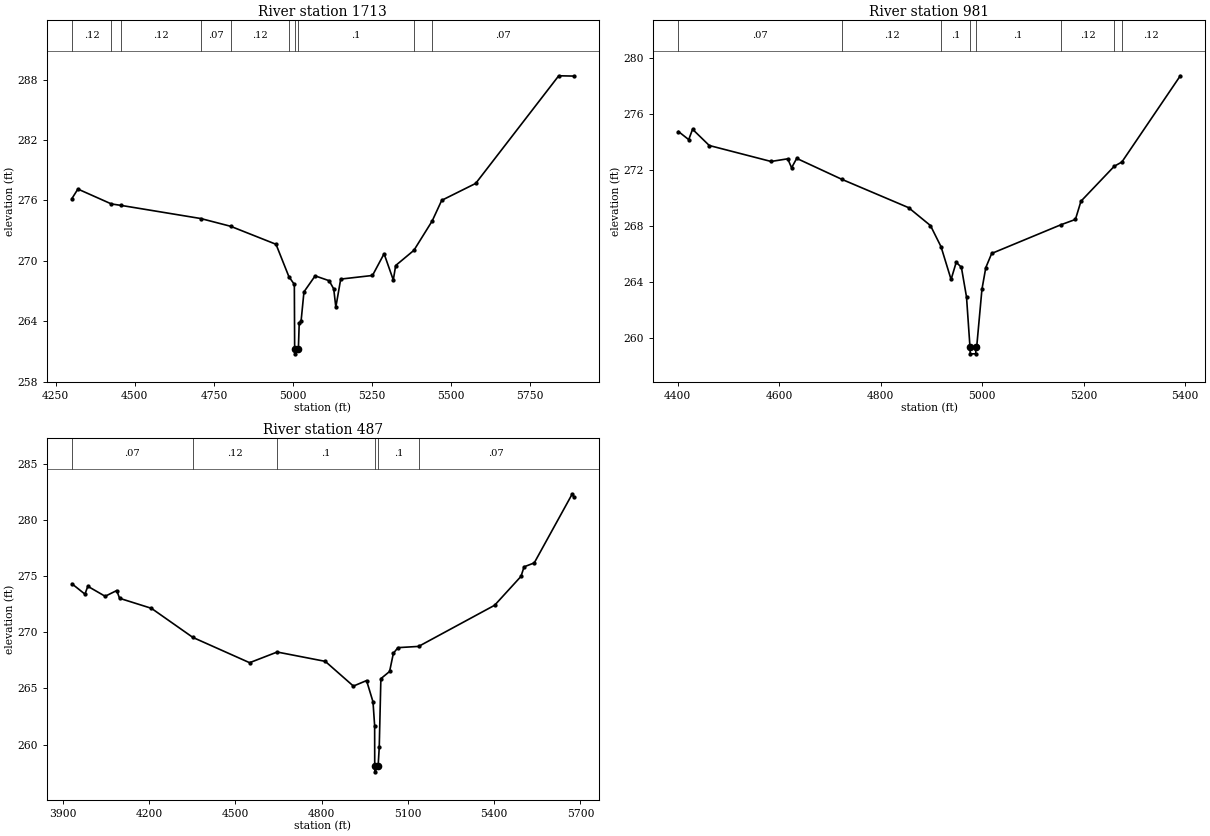
Type RM Length L Ch R = 1 ,1713    ,732,732,732
BEGIN DESCRIPTION:
A19822
END DESCRIPTION:
XS GIS Cut Line= 3
       2401283.7     13659921.08       2401157.7     13659394.17
      2400270.03     13658844.39
#Sta/Elev= 30
  4301.5  276.19  4320.3  277.13  4426.1  275.65  4457.8   275.5  4708.5   274.2
  4802.8  273.43  4946.3  271.64    4987  268.42  5004.2  267.65  5005.2  261.25
  5005.7  260.75    5017  261.25  5019.6   263.8  5025.4  263.97  5034.6  266.91
  5069.9   268.5  5114.1  268.02  5128.7   267.2  5135.3  265.39  5150.7  268.18
  5251.1  268.54  5287.8   270.7  5316.9  268.09  5324.4  269.53    5382  271.04
  5439.8  273.96  5469.9  276.01  5577.2  277.69  5839.6  288.39  5887.4  288.36
#Mann= 10 ,-1 , 0
  4301.5     .12       0  4426.1     .07       0  4457.8     .12       0
  4708.5     .07       0  4802.8     .12       0    4987      .1       0
  5005.2     .05       0    5017      .1       0    5382     .12       0
  5439.8     .07       0
Bank Sta=5005.2,5017
XS Rating Curve= 0 ,0
Exp/Cntr=0.3,0.1

Type RM Length L Ch R = 1 ,981     ,494,494,494
BEGIN DESCRIPTION:
LONG HOLLOW 1.0
END DESCRIPTION:
XS GIS Cut Line= 3
        2401275.     13659424.98        2401175.       13658825.
      2400825.04     13658675.02
#Sta/Elev= 30
  4401.3  274.75  4421.6  274.17  4429.2  274.91  4462.1  273.75  4583.8  272.61
  4616.7   272.8  4624.3  272.16  4634.4  272.83  4723.6  271.33  4854.9  269.31
    4898  268.03  4918.8  266.52  4938.6  264.18  4948.7  265.41  4958.9  265.05
    4969  262.93  4975.8  259.37  4976.3  258.87  4987.1  258.87  4987.6  259.37
  4989.3  259.46  4999.4  263.48    5007  265.03  5018.6  266.04  5154.4  268.08
  5183.6  268.47  5194.5  269.77  5260.2  272.27  5275.1  272.57  5390.3  278.73
#Mann= 8 ,-1 , 0
  4401.3     .07       0  4723.6     .12       0  4918.8      .1       0
  4975.8     .05       0  4987.6      .1       0  5154.4     .12       0
  5260.2     .07       0  5275.1     .12       0
Bank Sta=4975.8,4987.6
XS Rating Curve= 0 ,0
Exp/Cntr=0.3,0.1

Type RM Length L Ch R = 1 ,487     ,0,0,0
BEGIN DESCRIPTION:
A19821
END DESCRIPTION:
XS GIS Cut Line= 4
      2401340.96     13659439.95      2401432.59     13658540.89
      2401295.15     13658294.64      2400773.97     13658088.46
#Sta/Elev= 30
  3931.1  274.31  3976.3  273.39  3986.3  274.09  4046.6   273.2  4086.8  273.71
  4096.9  273.02  4207.5  272.13  4351.8  269.54  4549.2  267.29  4645.1  268.24
  4812.4  267.41  4910.3  265.21  4956.1   265.7  4978.5  263.81  4984.2  261.68
  4984.5  258.08    4985  257.58  4996.3  258.08  5000.2  259.75  5005.9  265.87
  5036.2  266.51  5049.4  268.13  5065.4  268.63  5137.1  268.74  5401.6   272.4
  5493.4  274.97  5504.1  275.82  5539.5  276.17    5672  282.32  5677.3  282.05
#Mann= 6 ,-1 , 0
  3931.1     .07       0  4351.8     .12       0  4645.1      .1       0
  4984.5     .05       0  4996.3      .1       0  5137.1     .07       0
Bank Sta=4984.5,4996.3
XS Rating Curve= 0 ,0
Exp/Cntr=0.3,0.1

Chan Stop Cuts=-1
Use User Specified Reach Order=0
Composite Channel Slope=5