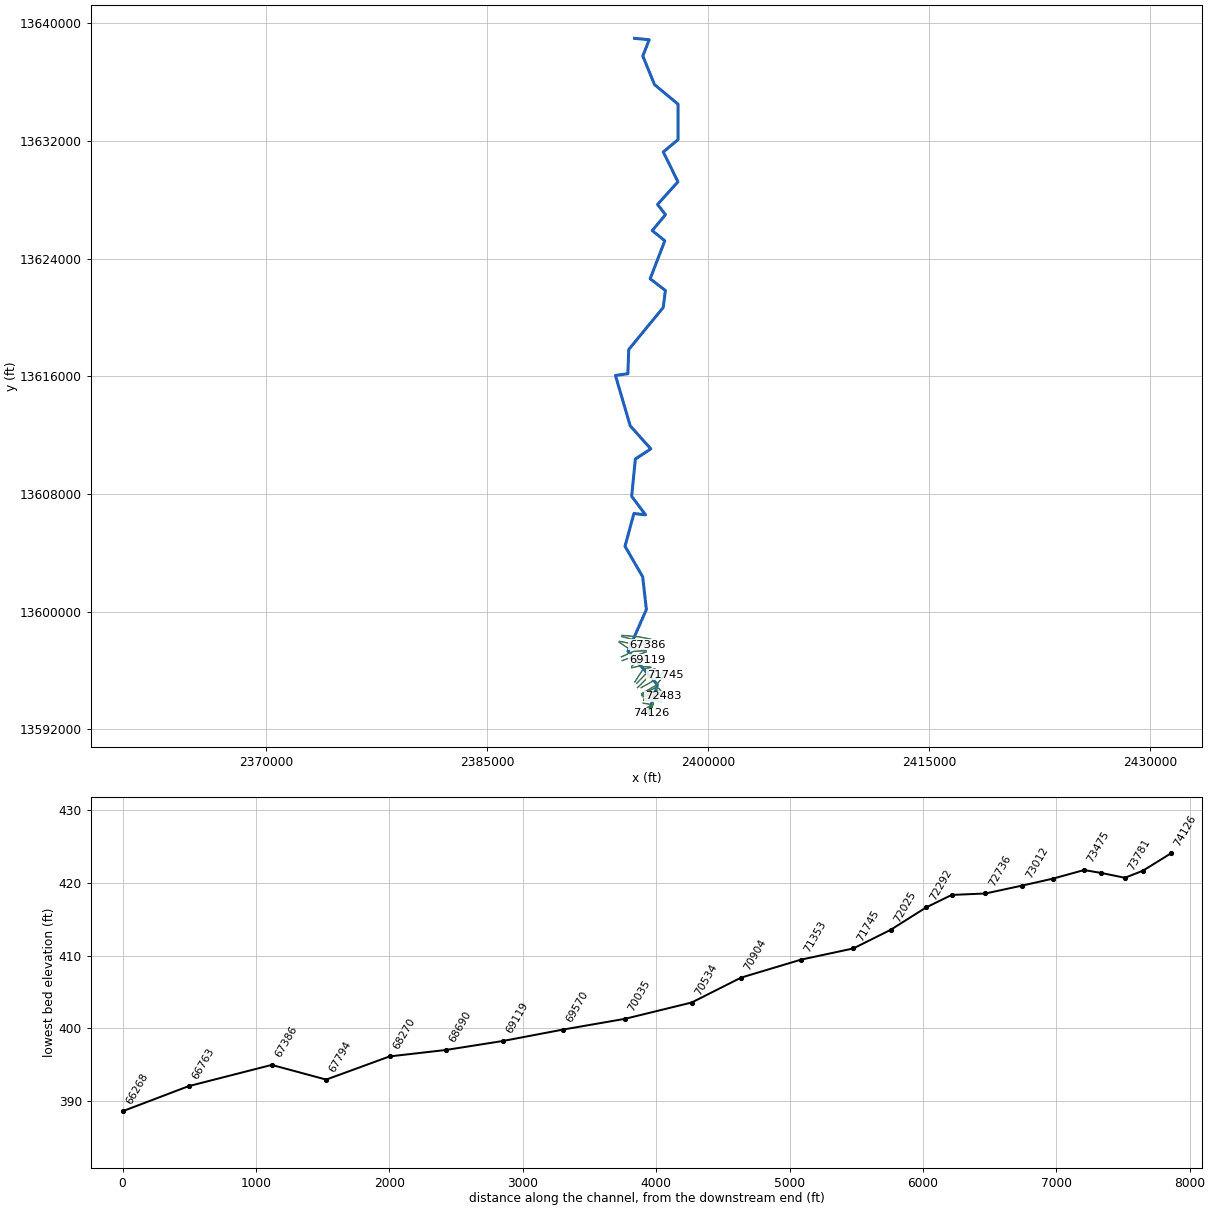
--- MOUND CREEK.prj (project) ---

Proj Title=MOUND CREEK Base Level Engineering
Current Plan=p01
Default Exp/Contr=0.3,0.1
English Units
Geom File=g01
Flow File=f01
Plan File=p01
Y Axis Title=Elevation
X Axis Title(PF)=Main Channel Distance
X Axis Title(XS)=Station
BEGIN DESCRIPTION:
MOUND CREEK
END DESCRIPTION:
DSS Export Rating Curves= 0
DSS Export Rating Curve Sorted= 0
DSS Export Volume Flow Curves= 0
DXF OffsetX= 0
DXF OffsetY= 0
DXF ScaleX= 1
DXF ScaleY= 10

--- MOUND CREEK.p01 (plan) ---

Plan Title=Multiple Run
Program Version=4.10
Short Identifier=Multiple
Geom File=g01
Flow File=f01
Subcritical Flow
K Sum by GR= 0
Std Step Tol= 0.01
Critical Tol= 0.01
Num of Std Step Trials= 20
Max Error Tol= 0.3
Flow Tol Ratio= 0.001
Split Flow NTrial= 30
Split Flow Tol= 0.02
Split Flow Ratio= 0.02
Log Output Level= 0
Friction Slope Method= 1
Unsteady Friction Slope Method= 2
Unsteady Bridges Friction Slope Method= 1
Parabolic Critical Depth
Global Vel Dist= 1 , 1 , 1
Global Log Level= 0
CheckData=True
Encroach Param=-1 ,0,0, 0
BEGIN DESCRIPTION:
Multiple Run
END DESCRIPTION:
Computation Interval=1HOUR
Output Interval=1HOUR
Run HTab= 0
Run UNet= 0
Run PostProcess= 0
Run WQNet= 0
UNET Theta= 1
UNET Theta Warmup= 1
UNET ZTol= 0.02
UNET ZSATol= 0.05
UNET MxIter= 20
UNET MaxInSteps= 0
UNET DtIC= 0
UNET DtMin= 0
UNET MaxCRTS= 20
UNET WFStab= 2
UNET SFStab= 1
UNET WFX= 1
UNET SFX= 1
UNET DSS MLevel= 4
UNET DZMax Abort= 100
UNET Convert EG Bridges= 0
UNET Use Existing IB Tables=-1
UNET Froude Reduction=False
UNET Froude Limit= 1
UNET Froude Power= 10
UNET Time Slicing=0,0, 5
UNET Junction Losses=0
Instantaneous Interval=1HOUR
Write IC File= 0
Write IC File at Sim End=0
Echo Input=False
Echo Parameters=False
Echo Output=False
Write Detailed= 0
WQ AD Non Conservative
WQ ULTIMATE=-1
WQ Max Comp Step=1HOUR
WQ Output Interval=15MIN
WQ Output Selected Increments= 0
WQ Output face flow=0
WQ Output face velocity=0
WQ Output face area=0
WQ Output face dispersion=0
WQ Output cell volume=0
WQ Output cell surface area=0
WQ Output cell continuity=0
WQ Output cumulative cell continuity=0
WQ Output face conc=0
WQ Output face dconc_dx=0
WQ Output face courant=0
WQ Output face peclet=0
WQ Output face adv mass=0
WQ Output face disp mass=0
WQ Output cell mass=0
WQ Output cell source sink temp=0
WQ Output cell source sink nsm=0
WQ Output MaxMinRange=-1
WQ Daily Max Min Mean=-1
WQ Daily Range=0
WQ Daily Time=0
WQ Create Restart=0
WQ Fixed Restart=0
WQ System Summary=0
WQ Use Fixed Temperature=0
Sorting and Armoring Iterations= 10
XS Update Threshold= 0.02
Hydraulics Update Threshold= 0.02
Energy Slope Method= 1
Volume Change Method= 0
XS Weighting Method= 0
Number of US Weighted Cross Sections= 1
Number of DS Weighted Cross Sections= 1
Upstream XS Weight=0.25
Main XS Weight=0.5
Downstream XS Weight=0.25
Number of DS XS's Weighted with US Boundary= 1
Upstream Boundary Weight= 1
Weight of XSs Associated with US Boundary= 0
Number of US XS's Weighted with DS Boundary= 1
Downstream Boundary Weight= 0.5
Weight of XSs Associated with DS Boundary= 0.5
Sediment Output Level= 4
Mass or Volume Output= 0
Output Increment Type= 1
Profile and TS Output Increment= 10
XS Output Flag= 0
XS Output Increment= 10
Disregard all LS=0
Disregard all Conn=0
Disregard all Breaches=0
Disregard all Pumps=0

--- MOUND CREEK.f01 (steady flow) ---

Flow Title=Multiple
Number of Profiles=7
Profile Names=10-year,25-year,50-year,1pct_min,100-year,1pct_plu,500-year
River Rch & RM= MOUND CREEK,Reach-1,74126
     510     826    1113     728    1453    2898    2450
River Rch & RM= MOUND CREEK,Reach-1,73012
     836    1392    1910    1270    2534    5056    4421
River Rch & RM= MOUND CREEK,Reach-1,71745
     979    1641    2260    1507    3007    5999    5276
River Rch & RM= MOUND CREEK,Reach-1,69570
    1152    1941    2684    1795    3581    7146    6325
River Rch & RM= MOUND CREEK,Reach-1,67794
    1238    2076    2860    1903    3797    7576    6640
River Rch & RM= MOUND CREEK,Reach-1,61590
    1673    2834    3929    2628    5243   10462    9267
River Rch & RM= MOUND CREEK,Reach-1,54007
    2037    3474    4838    3248    6481   12931   11541
River Rch & RM= MOUND CREEK,Reach-1,46355
    2030    3455    4806    3221    6427   12824   11411
River Rch & RM= MOUND CREEK,Reach-1,43832
    2194    3741    5209    3495    6973   13912   12401
River Rch & RM= MOUND CREEK,Reach-1,41531
    2283    3887    5406    3621    7225   14416   12811
River Rch & RM= MOUND CREEK,Reach-1,34789
    2330    3963    5509    3688    7358   14682   13029
River Rch & RM= MOUND CREEK,Reach-1,30742
    2497    4259    5932    3977    7935   15833   14098
River Rch & RM= MOUND CREEK,Reach-1,26597
    2637    4506    6282    4216    8412   16784   14972
River Rch & RM= MOUND CREEK,Reach-1,21594
    2734    4645    6453    4314    8607   17174   15193
River Rch & RM= MOUND CREEK,Reach-1,10939
    2770    4701    6525    4359    8697   17352   15326
River Rch & RM= MOUND CREEK,Reach-1,7296
    3040    5170    7188    4807    9592   19138   16944
Boundary for River Rch & Prof#=MOUND CREEK,Reach-1,1
Up Type=0
Dn Type=3
Dn Slope=0.0005
Boundary for River Rch & Prof#=MOUND CREEK,Reach-1,2
Up Type=0
Dn Type=3
Dn Slope=0.0005
Boundary for River Rch & Prof#=MOUND CREEK,Reach-1,3
Up Type=0
Dn Type=3
Dn Slope=0.0005
Boundary for River Rch & Prof#=MOUND CREEK,Reach-1,4
Up Type=0
Dn Type=3
Dn Slope=0.0005
Boundary for River Rch & Prof#=MOUND CREEK,Reach-1,5
Up Type=0
Dn Type=3
Dn Slope=0.0005
Boundary for River Rch & Prof#=MOUND CREEK,Reach-1,6
Up Type=0
Dn Type=3
Dn Slope=0.0005
Boundary for River Rch & Prof#=MOUND CREEK,Reach-1,7
Up Type=0
Dn Type=3
Dn Slope=0.0005

--- MOUND CREEK.g01 (geometry) ---

Geom Title=Existing Conditions
Program Version=4.10

River Reach=MOUND CREEK     ,Reach-1
Reach XY= 30
        2395975.       13593075.        2396575.       13595025.
      2394574.48     13597295.05      2395823.79     13600135.51
      2395574.41     13602363.16      2394374.43     13604435.13
      2394977.93     13606667.03      2395767.99      13606574.8
      2394826.04     13607835.43      2395076.97     13610369.32
      2396125.05     13611059.78      2394728.03     13612626.39
      2393724.53     13616054.84      2394567.36     13616168.54
      2394628.17     13617816.66      2396967.31     13620671.33
      2397115.59     13621831.62      2396082.29     13622624.91
      2397074.92     13625209.61      2396225.06     13625904.97
      2397124.47     13626985.69      2396580.28     13627677.72
      2397967.14     13629221.38      2396974.37     13631250.09
      2397973.39     13632081.02      2397975.39       13634500.
      2396378.12     13635826.63      2395582.29     13637774.91
      2396017.24     13638881.83        2395025.       13638975.

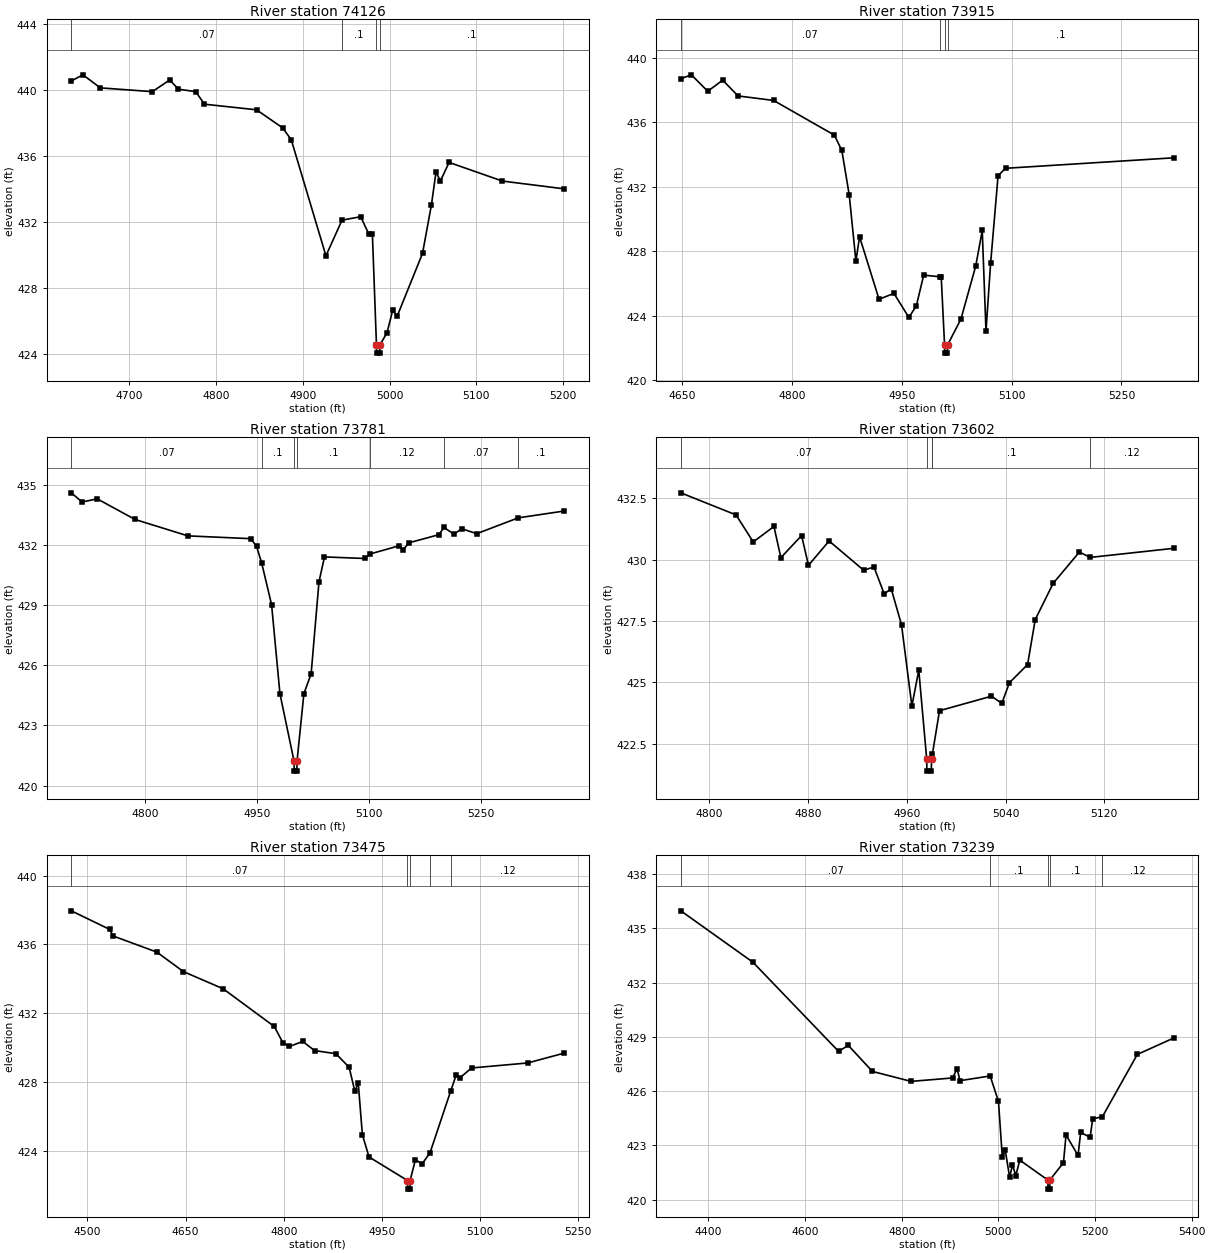
Type RM Length L Ch R = 1 ,74126   ,211,211,211
BEGIN DESCRIPTION:
MOUND CREEK 101.0
END DESCRIPTION:
XS GIS Cut Line= 3
       2395611.6     13593130.86      2395958.44     13593125.12
      2396174.52     13593079.63
#Sta/Elev= 30
  4633.3  440.57  4646.7  440.94  4666.7  440.15  4726.7  439.92  4746.7  440.63
  4756.7  440.07  4776.7  439.92  4786.7  439.16  4846.7  438.82  4876.7  437.73
  4886.7  437.01  4926.7  429.97  4945.2  432.13  4966.7  432.34    4976   431.3
  4980.2   431.3  4984.9  424.57  4985.1  424.07  4988.6  424.07  4988.9  424.57
  4997.1  425.31  5003.6  426.67  5008.7   426.3    5038  430.12  5048.2  433.05
  5053.5  435.04  5058.6  434.51  5068.6  435.63    5130   434.5    5201  434.03
#Mann= 4 ,-1 , 0
  4633.3     .07       0  4945.2      .1       0  4984.9     .05       0
  4988.9      .1       0
Bank Sta=4984.9,4988.9
XS Rating Curve= 0 ,0
Exp/Cntr=0.3,0.1

Type RM Length L Ch R = 1 ,73915   ,134,134,134
BEGIN DESCRIPTION:
B19669
END DESCRIPTION:
XS GIS Cut Line= 4
      2395628.81     13593236.91       2395978.5     13593299.97
       2396104.6     13593278.65      2396173.62     13593102.62
#Sta/Elev= 30
  4648.7  438.71  4663.1  438.95  4685.5  437.93  4705.8  438.62  4726.8  437.64
  4775.3  437.36  4858.2  435.21  4868.4  434.26  4878.5   431.5  4887.6   427.4
  4892.6   428.9  4919.2  425.02  4939.5  425.39  4959.8   423.9    4970   424.6
  4980.1  426.52  5001.8  426.42    5004  426.42  5008.6  422.18  5008.9  421.68
  5012.4  421.68  5012.6  422.18  5030.9  423.79  5051.2   427.1    5060  429.29
  5065.1  423.05  5071.5   427.3  5081.6  432.69  5091.8  433.15    5321   433.8
#Mann= 4 ,-1 , 0
  4648.7     .07       0  5001.8      .1       0  5008.6     .05       0
  5012.6      .1       0
Bank Sta=5008.6,5012.6
XS Rating Curve= 0 ,0
Exp/Cntr=0.3,0.1

Type RM Length L Ch R = 1 ,73781   ,179,179,179
BEGIN DESCRIPTION:
B19668
END DESCRIPTION:
XS GIS Cut Line= 4
       2395760.7     13593391.69      2395975.63     13593426.08
      2396140.98     13593375.76      2396187.47     13593109.79
#Sta/Elev= 30
  4701.4  434.62  4715.9  434.16  4736.1  434.32  4786.8  433.29  4857.7  432.47
  4942.2  432.33  4949.8  431.94  4956.5  431.13  4969.9  429.03  4981.1  424.58
    5000  421.22  5000.3  420.72  5003.8  420.72    5004  421.22  5013.2  424.59
  5022.9  425.58  5033.4  430.17  5040.8  431.42  5094.8  431.34  5102.3  431.57
  5141.3  431.98  5146.4  431.76  5153.6  432.12  5194.2  432.53    5201  432.89
  5214.5  432.55  5224.6  432.83  5244.9  432.58  5300.5  433.37  5361.9  433.71
#Mann= 7 ,-1 , 0
  4701.4     .07       0  4956.5      .1       0    5000     .05       0
    5004      .1       0  5102.3     .12       0    5201     .07       0
  5300.5      .1       0
Bank Sta=5000,5004
XS Rating Curve= 0 ,0
Exp/Cntr=0.3,0.1

Type RM Length L Ch R = 1 ,73602   ,127,127,127
BEGIN DESCRIPTION:
MOUND CREEK 100.0
END DESCRIPTION:
XS GIS Cut Line= 3
      2395874.97     13593474.98        2396075.       13593575.
      2396179.35     13593433.57
#Sta/Elev= 30
  4776.8  432.72  4821.6  431.82  4835.5  430.72  4852.3  431.35  4857.9  430.08
  4874.7  430.98  4880.3  429.77    4897  430.76    4925  429.57  4933.4   429.7
  4941.7   428.6  4947.3  428.82  4955.7  427.35  4964.1  424.04  4969.7   425.5
  4976.1  421.89  4976.3  421.39  4979.8  421.39  4980.1  421.89  4980.8   422.1
  4986.5  423.85  5028.6  424.44    5037  424.15  5043.2  424.99  5057.9  425.73
  5064.1  427.56  5078.7  429.04  5099.9  430.31  5108.6  430.09  5176.2  430.46
#Mann= 5 ,-1 , 0
  4776.8     .07       0  4976.1     .05       0  4980.1     .07       0
  4980.8      .1       0  5108.6     .12       0
Bank Sta=4976.1,4980.1
XS Rating Curve= 0 ,0
Exp/Cntr=0.3,0.1

Type RM Length L Ch R = 1 ,73475   ,236,236,236
BEGIN DESCRIPTION:
B19667
END DESCRIPTION:
XS GIS Cut Line= 3
       2395605.9     13593770.04      2396153.34     13593681.18
       2396190.6     13593486.32
#Sta/Elev= 30
  4475.4  437.95  4534.1  436.87  4539.2  436.49  4606.2  435.55  4646.7  434.42
  4707.5  433.42  4785.6  431.23  4798.7  430.29  4808.8  430.07  4829.1  430.36
  4847.2  429.83  4879.7  429.65    4900  428.86  4908.8  427.46  4913.9  427.97
  4920.2  424.95  4930.4  423.65  4989.2  422.28  4989.4  421.78  4992.9  421.78
  4993.2  422.28  5001.3  423.49  5011.4  423.24  5023.6  423.89  5055.4   427.5
  5063.6  428.41  5068.7  428.23  5087.2  428.82  5172.9  429.11  5228.4  429.68
#Mann= 5 ,-1 , 0
  4475.4     .07       0  4989.2     .05       0  4993.2     .07       0
  5023.6      .1       0  5055.4     .12       0
Bank Sta=4989.2,4993.2
XS Rating Curve= 0 ,0
Exp/Cntr=0.3,0.1

Type RM Length L Ch R = 1 ,73239   ,227,227,227
BEGIN DESCRIPTION:
B19666
END DESCRIPTION:
XS GIS Cut Line= 4
      2395648.91     13593947.75      2396193.47     13593919.09
      2396305.26     13593747.11      2396210.67     13593494.89
#Sta/Elev= 30
  4342.7  435.96    4492  433.12  4669.2   428.2  4689.3  428.53  4739.3  427.09
  4819.4  426.54  4905.4  426.73  4914.6  427.25  4920.5  426.58    4983  426.84
  5000.2  425.43  5008.1  422.36  5014.1  422.75  5023.3  421.25  5029.2  421.93
    5036  421.34  5044.4  422.19  5102.4  421.09  5102.7  420.59  5106.2  420.59
  5106.4  421.09  5134.7  422.05    5140  423.58  5164.9  422.45  5170.3  423.72
  5189.9  423.45  5195.2  424.47  5215.3  424.59  5287.6  428.03  5362.5  428.93
#Mann= 5 ,-1 , 0
  4342.7     .07       0    4983      .1       0  5102.4     .05       0
  5106.4      .1       0  5215.3     .12       0
Bank Sta=5102.4,5106.4
XS Rating Curve= 0 ,0
Exp/Cntr=0.3,0.1

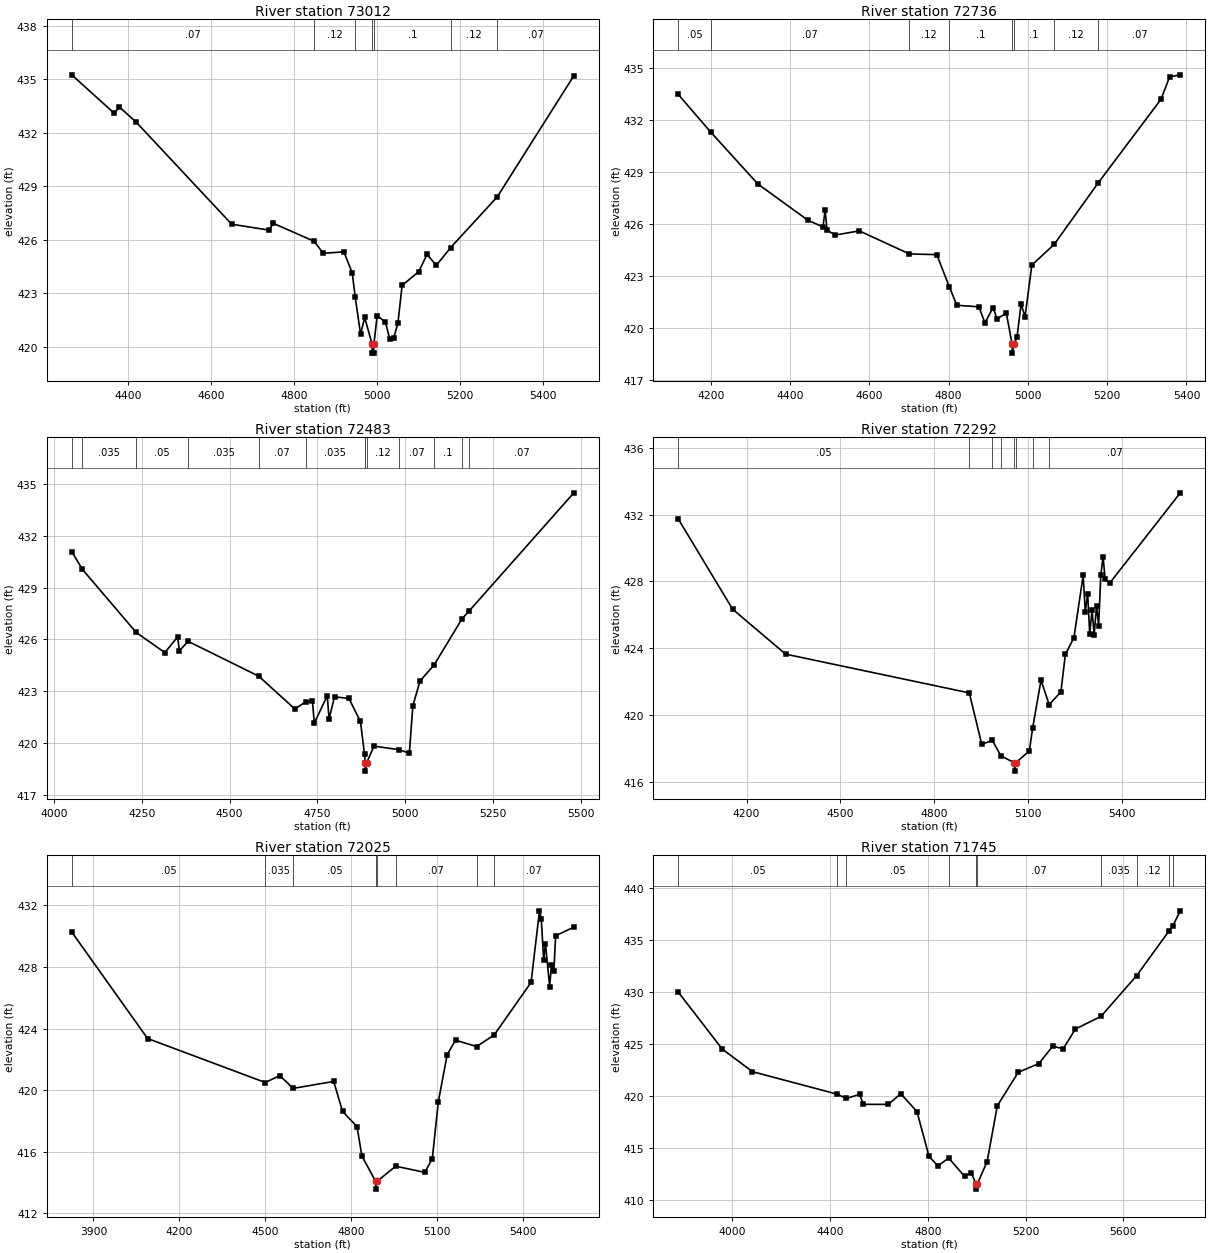
Type RM Length L Ch R = 1 ,73012   ,276,276,276
BEGIN DESCRIPTION:
B19665
END DESCRIPTION:
XS GIS Cut Line= 3
      2395640.24     13593970.68      2396517.36     13593964.95
      2396838.35      13593884.7
#Sta/Elev= 30
  4265.3  435.26  4367.1  433.11  4380.1  433.45  4420.1  432.61  4650.1  426.88
  4740.1  426.55  4750.1  426.93  4848.8  425.92  4870.1  425.25  4920.1  425.33
  4940.1  424.15  4947.2  422.81  4960.1  420.71  4970.1  421.65  4987.9  420.15
  4988.2  419.65  4991.9  419.65  4992.2  420.15  5000.1  421.76  5020.1  421.38
  5030.1  420.45  5040.1   420.5  5050.1  421.35  5060.1  423.45  5100.1  424.22
  5120.1  425.19  5142.4  424.57  5176.9  425.57  5289.2  428.42  5473.3  435.21
#Mann= 7 ,-1 , 0
  4265.3     .07       0  4848.8     .12       0  4947.2      .1       0
  4987.9     .05       0  4992.2      .1       0  5176.9     .12       0
  5289.2     .07       0
Bank Sta=4987.9,4992.2
XS Rating Curve= 0 ,0
Exp/Cntr=0.3,0.1

Type RM Length L Ch R = 1 ,72736   ,253,253,253
BEGIN DESCRIPTION:
B19664
END DESCRIPTION:
XS GIS Cut Line= 4
      2395648.89     13594048.07      2396293.79     13594194.25
      2396563.22     13594154.12      2396869.93     13594025.13
#Sta/Elev= 30
    4118  433.48  4200.2   431.3  4319.1  428.31  4445.3  426.22  4483.1  425.84
  4488.4   426.8  4493.6  425.65  4513.9  425.37  4574.7  425.61  4701.2  424.28
  4770.2  424.24  4801.4   422.4  4820.9  421.32  4876.3  421.23  4891.7   420.3
  4911.9  421.19    4922  420.54  4945.6  420.86  4960.3  419.06  4960.6  418.56
  4964.6  419.06  4972.6   419.5  4982.7  421.39  4992.8  420.66  5009.9  423.64
  5066.2  424.83    5178   428.4  5335.7   433.2  5357.4  434.49  5384.4  434.61
#Mann= 8 ,-1 , 0
    4118     .05       0  4200.2     .07       0  4701.2     .12       0
  4801.4      .1       0  4960.3     .05       0  4964.6      .1       0
  5066.2     .12       0    5178     .07       0
Bank Sta=4960.3,4964.6
XS Rating Curve= 0 ,0
Exp/Cntr=0.3,0.1

Type RM Length L Ch R = 1 ,72483   ,191,191,191
BEGIN DESCRIPTION:
B19663
END DESCRIPTION:
XS GIS Cut Line= 4
      2395597.24     13594199.97      2396414.18     13594394.89
      2396723.74     13594363.36      2396964.53      13594222.9
#Sta/Elev= 30
  4050.5   431.1  4080.7  430.07  4233.8  426.41  4315.5  425.24  4351.9  426.15
    4357  425.35    4382  425.89  4582.9  423.87  4685.6  421.97  4717.1  422.38
    4736  422.41  4741.1  421.15  4778.1  422.73  4783.2  421.39  4798.7  422.67
  4839.8  422.58  4872.6  421.24  4884.2  419.34  4886.1  418.86  4886.4  418.36
  4890.4  418.86  4911.3  419.81  4983.4   419.6  5011.8   419.4  5021.9  422.16
  5042.2  423.59  5082.6  424.53  5161.9   427.2  5181.5  427.64  5480.3  434.51
#Mann= 13 ,-1 , 0
  4050.5     .05       0  4080.7    .035       0  4233.8     .05       0
    4382    .035       0  4582.9     .07       0  4717.1    .035       0
  4884.2     .12       0  4886.1     .05       0  4890.4     .12       0
  4983.4     .07       0  5082.6      .1       0  5161.9     .12       0
  5181.5     .07       0
Bank Sta=4886.1,4890.4
XS Rating Curve= 0 ,0
Exp/Cntr=0.3,0.1

Type RM Length L Ch R = 1 ,72292   ,267,267,267
BEGIN DESCRIPTION:
MOUND CREEK 99.0
END DESCRIPTION:
XS GIS Cut Line= 3
      2395507.58     13594288.13      2396603.89     13594594.46
      2396957.48     13594289.08
#Sta/Elev= 30
  3981.4  431.74  4155.2  426.34  4324.7  423.65  4912.1  421.33    4952  418.25
  4985.6  418.49  5013.4  417.56  5056.4  417.15  5056.7  416.65  5060.7  417.15
  5104.2  417.86  5114.8  419.24  5141.4  422.08  5167.6  420.63    5205  421.39
  5219.3  423.63  5246.7  424.63  5276.3  428.37  5282.9   426.2  5290.6  427.26
  5297.2  424.88  5304.8  426.29  5311.4   424.8  5319.1  426.55  5325.7  425.34
  5332.6  428.37  5339.9  429.48  5346.6  428.12  5360.8  427.89  5586.9   433.3
#Mann= 8 ,-1 , 0
  3981.4     .05       0  4912.1    .035       0  4985.6     .05       0
  5013.4     .07       0  5056.4     .05       0  5060.7     .07       0
  5114.8    .035       0  5167.6     .07       0
Bank Sta=5056.4,5060.7
XS Rating Curve= 0 ,0
Exp/Cntr=0.3,0.1

Type RM Length L Ch R = 1 ,72025   ,280,280,280
BEGIN DESCRIPTION:
B19662
END DESCRIPTION:
XS GIS Cut Line= 4
      2395512.88     13594363.35      2396469.53     13594830.92
      2396689.88     13594761.06      2396958.58     13594390.25
#Sta/Elev= 30
  3824.3  430.27  4089.1  423.35  4500.4  420.49  4550.6  420.94  4598.1  420.11
  4739.4  420.56  4770.2  418.61  4820.8  417.62  4837.7  415.72  4885.9  414.06
  4886.2  413.56  4890.3  414.06  4955.8  415.05  5057.5  414.65  5083.7  415.53
  5104.7  419.23  5135.7   422.3  5164.8  423.24  5238.7  422.83  5299.8  423.58
  5428.8     427  5458.2  431.65  5464.3  431.13  5472.9  428.44    5479  429.51
  5493.7  426.73  5499.9  428.12  5508.4  427.76  5514.6  430.03  5578.2  430.59
#Mann= 8 ,-1 , 0
  3824.3     .05       0  4500.4    .035       0  4598.1     .05       0
  4885.9     .05       0  4890.3     .05       0  4955.8     .07       0
  5238.7    .035       0  5299.8     .07       0
Bank Sta=4885.9,4890.3
XS Rating Curve= 0 ,0
Exp/Cntr=0.3,0.1

Type RM Length L Ch R = 1 ,71745   ,392,392,392
BEGIN DESCRIPTION:
B19661
END DESCRIPTION:
XS GIS Cut Line= 3
      2395507.54     13594417.11      2396458.78     13594970.66
      2397081.12     13595694.93
#Sta/Elev= 30
  3778.2  429.99  3958.7  424.49    4082  422.32  4427.5  420.16  4466.4  419.74
  4520.6  420.13  4536.3  419.17  4638.1  419.17  4689.3  420.19  4755.5  418.48
    4805  414.15  4841.6  413.23  4885.2     414  4950.4  412.24  4978.1  412.55
  4997.4   411.5  4997.8     411  5002.5   411.5  5042.7  413.64  5084.5  419.03
  5170.1  422.26  5254.6   423.1  5311.6  424.78  5354.4  424.52  5403.8  426.42
    5509  427.65  5655.1  431.58  5786.3  435.84  5802.9  436.37  5833.7  437.82
#Mann= 10 ,-1 , 0
  3778.2     .05       0  4427.5    .035       0  4466.4     .05       0
  4885.2     .07       0  4997.4     .05       0  5002.5     .07       0
    5509    .035       0  5655.1     .12       0  5786.3     .07       0
  5802.9     .12       0
Bank Sta=4997.4,5002.5
XS Rating Curve= 0 ,0
Exp/Cntr=0.3,0.1

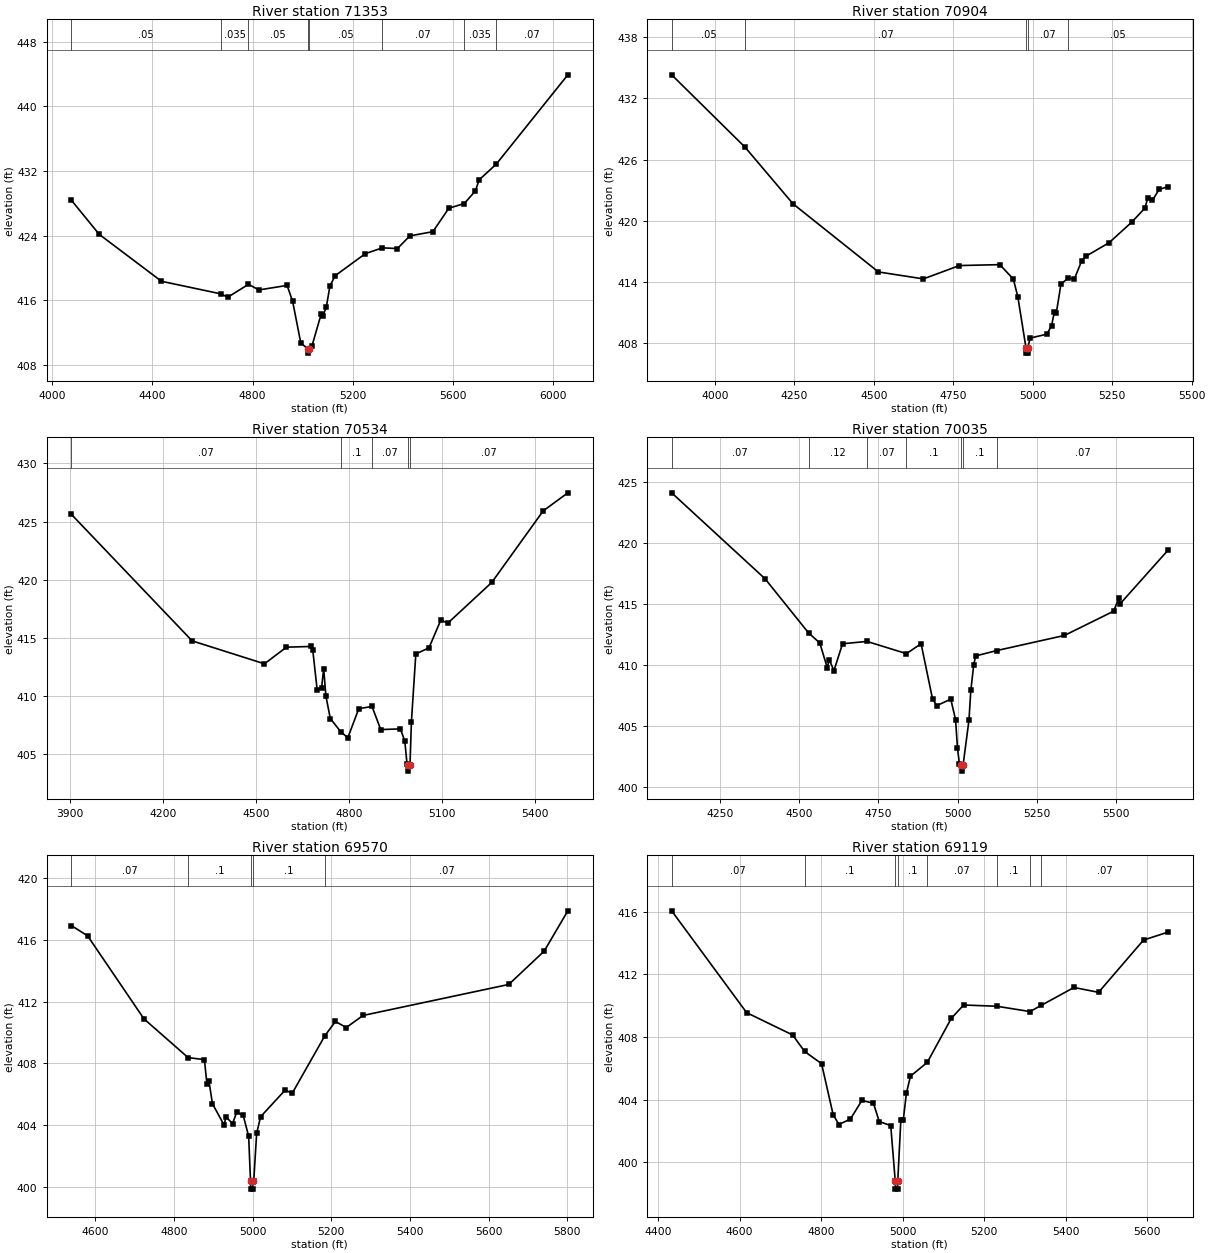
Type RM Length L Ch R = 1 ,71353   ,449,449,449
BEGIN DESCRIPTION:
MOUND CREEK 98.0
END DESCRIPTION:
XS GIS Cut Line= 3
      2395474.98     13594824.99        2396275.       13595275.
      2397074.99     13595974.99
#Sta/Elev= 30
  4077.6  428.37  4188.2  424.16  4436.8  418.35  4672.8   416.8  4701.3  416.38
  4783.9  417.97  4825.6  417.28  4938.1  417.84  4960.1  415.87  4992.6  410.74
  5020.9  409.96  5021.3  409.46    5026  409.96  5037.7  410.39  5073.8  414.27
  5080.4  414.01  5094.7  415.18  5108.9  417.76  5129.8  419.04  5250.3  421.77
  5318.2  422.49  5378.5   422.4  5427.8  423.97  5519.9  424.49  5583.5  427.39
    5645  427.97  5689.8  429.54    5704  430.89  5772.5  432.84  6058.5   443.9
#Mann= 8 ,-1 , 0
  4077.6     .05       0  4672.8    .035       0  4783.9     .05       0
  5020.9     .05       0    5026     .05       0  5318.2     .07       0
    5645    .035       0  5772.5     .07       0
Bank Sta=5020.9,5026
XS Rating Curve= 0 ,0
Exp/Cntr=0.3,0.1

Type RM Length L Ch R = 1 ,70904   ,370,370,370
BEGIN DESCRIPTION:
MOUND CREEK 97.0
END DESCRIPTION:
XS GIS Cut Line= 3
      2395225.02     13594825.02        2396025.       13595625.
      2396375.03     13595875.02
#Sta/Elev= 30
  3864.2  434.32  4094.8  427.22    4246  421.65  4514.7  414.96  4656.1  414.28
  4769.3  415.59  4896.5  415.68    4939  414.26  4953.1  412.53  4978.9  407.49
  4979.2  406.99  4983.6  406.99    4984  407.49    4992  408.47  5044.7  408.85
  5059.4   409.7    5068  411.04  5074.2  410.94  5088.9  413.78  5112.3  414.36
  5130.7  414.25  5154.1  416.06  5167.6  416.51  5240.1  417.83  5311.4  419.85
  5353.2  421.24  5361.8  422.23  5376.5  421.99  5397.4  423.06  5425.7  423.34
#Mann= 5 ,-1 , 0
  3864.2     .05       0  4094.8     .07       0  4978.9     .05       0
    4984     .07       0  5112.3     .05       0
Bank Sta=4978.9,4984
XS Rating Curve= 0 ,0
Exp/Cntr=0.3,0.1

Type RM Length L Ch R = 1 ,70534   ,499,499,499
BEGIN DESCRIPTION:
MOUND CREEK 96.0
END DESCRIPTION:
XS GIS Cut Line= 3
      2395174.97     13595124.97       2395975.1     13595948.78
      2396399.67     13596104.64
#Sta/Elev= 30
    3904  425.62  4293.1  414.76  4526.4  412.79  4597.1  414.22  4674.8  414.28
    4682  413.99  4696.2  410.57  4710.3  410.69  4717.3  412.36  4724.4  410.03
  4738.6  408.09  4773.1  406.93  4795.2  406.44  4830.4  408.93  4873.1  409.13
  4901.2  407.14  4964.7   407.2  4978.9  406.15  4986.1  404.18  4990.4  404.07
  4990.8  403.57  4995.6  404.07  5000.2  407.81  5014.4  413.64  5056.8  414.16
  5094.9  416.54  5117.8  416.29  5259.6  419.79  5425.2  425.93  5504.7  427.48
#Mann= 5 ,-1 , 0
    3904     .07       0  4773.1      .1       0  4873.1     .07       0
  4990.4     .05       0  4995.6     .07       0
Bank Sta=4990.4,4995.6
XS Rating Curve= 0 ,0
Exp/Cntr=0.3,0.1

Type RM Length L Ch R = 1 ,70035   ,465,465,465
BEGIN DESCRIPTION:
B19660
END DESCRIPTION:
XS GIS Cut Line= 3
      2395039.98     13595212.52      2395582.77     13596050.89
      2396130.47     13596201.24
#Sta/Elev= 30
  4097.7  424.14  4392.3   417.1  4529.7  412.66  4565.3  411.83  4588.8   409.8
  4594.8  410.47  4609.9  409.57    4637  411.77  4714.2  411.96  4838.7  410.96
  4884.9  411.77  4921.2  407.23  4934.6   406.7  4978.6  407.23  4993.8  405.54
  4999.7  403.24    5006   401.9  5012.3  401.83  5012.7  401.33  5017.5  401.83
    5036   405.5  5041.9  407.95  5051.1  410.04  5057.1  410.77  5123.5  411.21
  5337.3  412.45  5492.8  414.44  5508.5  415.49  5513.7  415.06  5664.4  419.44
#Mann= 7 ,-1 , 0
  4097.7     .07       0  4529.7     .12       0  4714.2     .07       0
  4838.7      .1       0  5012.3     .05       0  5017.5      .1       0
  5123.5     .07       0
Bank Sta=5012.3,5017.5
XS Rating Curve= 0 ,0
Exp/Cntr=0.3,0.1

Type RM Length L Ch R = 1 ,69570   ,451,451,451
BEGIN DESCRIPTION:
MOUND CREEK 95.0
END DESCRIPTION:
XS GIS Cut Line= 3
      2394824.98       13596175.        2395275.       13596275.
      2396075.05       13596225.
#Sta/Elev= 30
  4539.1  416.92  4580.1  416.26  4723.5  410.88  4835.8  408.37  4877.2  408.24
  4883.6  406.66  4888.7  406.86  4897.7  405.38  4927.1  404.01  4932.2  404.53
  4948.9  404.09  4959.1  404.83  4975.8  404.64  4989.8  403.27  4994.5  400.35
    4995  399.85  5000.1  399.85  5000.6  400.35  5002.6  400.35  5010.1  403.46
  5020.1  404.54  5082.8  406.27  5100.3  406.05  5183.7  409.79  5210.5  410.71
  5238.1  410.32  5280.6   411.1  5651.4  413.11  5741.5  415.27  5801.7  417.88
#Mann= 5 ,-1 , 0
  4539.1     .07       0  4835.8      .1       0  4994.5     .05       0
  5000.6      .1       0  5183.7     .07       0
Bank Sta=4994.5,5000.6
XS Rating Curve= 0 ,0
Exp/Cntr=0.3,0.1

Type RM Length L Ch R = 1 ,69119   ,429,429,429
BEGIN DESCRIPTION:
MOUND CREEK 94.0
END DESCRIPTION:
XS GIS Cut Line= 3
      2394824.97     13596274.97        2395225.       13596675.
      2395875.05       13596725.
#Sta/Elev= 30
  4433.6  416.07  4617.5  409.56  4730.6  408.13  4759.6  407.08  4801.3   406.3
  4829.6  403.05  4843.8  402.41  4872.1  402.76  4900.3  403.95  4928.6  403.77
  4942.8   402.6    4971  402.34  4982.1  398.78  4982.6  398.28  4987.7  398.28
  4988.2  398.78  4995.8  402.71  5001.8  402.71  5009.4  404.41  5019.4   405.5
  5060.6  406.38  5119.7   409.2  5149.8  410.05  5231.4  409.97  5312.6  409.63
  5340.4  410.03  5420.6  411.17  5480.8  410.86  5591.1   414.2  5651.3  414.71
#Mann= 8 ,-1 , 0
  4433.6     .07       0  4759.6      .1       0  4982.1     .05       0
  4988.2      .1       0  5060.6     .07       0  5231.4      .1       0
  5312.6     .05       0  5340.4     .07       0
Bank Sta=4982.1,4988.2
XS Rating Curve= 0 ,0
Exp/Cntr=0.3,0.1

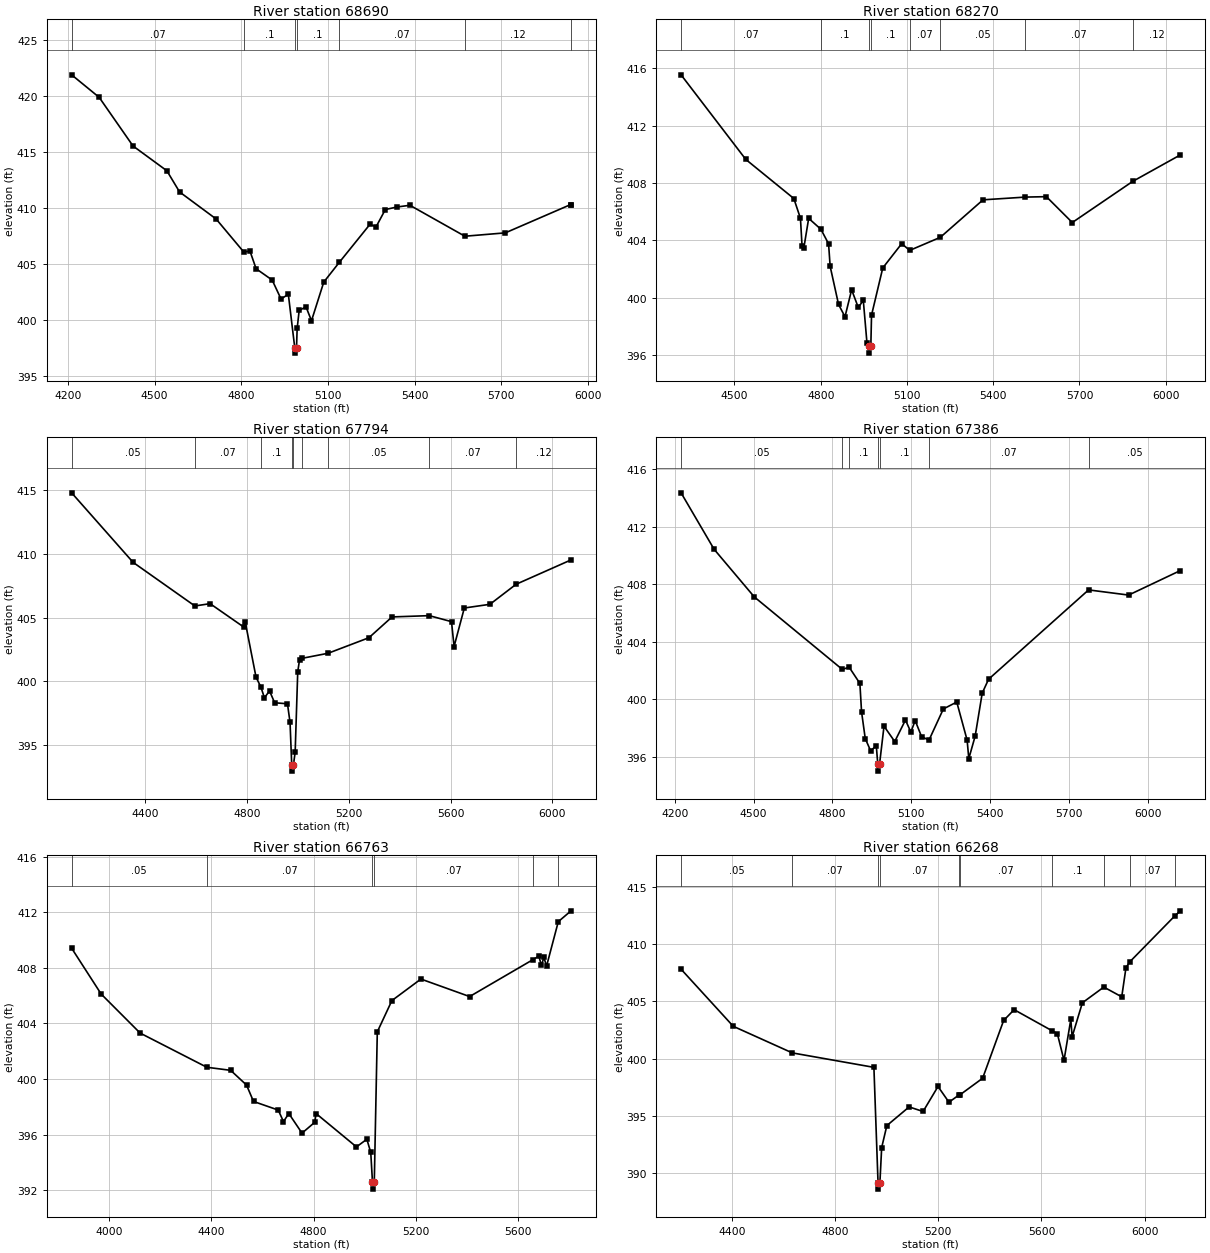
Type RM Length L Ch R = 1 ,68690   ,420,420,420
BEGIN DESCRIPTION:
B19659
END DESCRIPTION:
XS GIS Cut Line= 2
      2394185.45     13596663.56      2395808.54     13597254.75
#Sta/Elev= 30
  4213.3  421.87  4308.6  419.86  4425.7  415.52  4542.7  413.31  4586.7  411.42
    4713  409.01  4808.8  406.06  4830.1  406.15  4851.4  404.57    4907  403.56
  4937.6  401.87  4962.9  402.29    4985  397.54  4985.5  397.04  4991.2  397.54
  4993.4  399.24  5000.4  400.85    5024  401.17    5043  399.93  5085.5  403.38
  5138.9  405.13  5245.2  408.53  5266.4  408.31  5298.4  409.85    5339  410.08
  5383.5  410.23  5573.6  407.47  5713.4  407.77    5939  410.29  5940.7  410.29
#Mann= 7 ,-1 , 0
  4213.3     .07       0  4808.8      .1       0    4985     .05       0
  4991.2      .1       0  5138.9     .07       0  5573.6     .12       0
    5939     .05       0
Bank Sta=4985,4991.2
XS Rating Curve= 0 ,0
Exp/Cntr=0.3,0.1

Type RM Length L Ch R = 1 ,68270   ,476,476,476
BEGIN DESCRIPTION:
B19658
END DESCRIPTION:
XS GIS Cut Line= 3
      2394126.38     13596916.17      2394953.98     13597292.35
      2395780.84     13597329.94
#Sta/Elev= 30
  4314.3  415.53  4539.5  409.64  4706.5  406.92  4729.5  405.54    4735  403.64
  4741.2  403.47  4758.1  405.54  4800.7  404.78  4827.3  403.77  4832.8   402.2
    4862  399.55  4884.4  398.69  4907.5  400.57  4930.6  399.34  4948.1  399.83
  4960.9  396.85  4968.1  396.66  4968.6  396.16  4974.3  396.66  4976.7   398.8
  5015.8  402.09  5081.7  403.78  5109.4  403.31    5216  404.22  5364.5  406.83
  5511.6  407.02  5584.8  407.05  5674.9  405.25  5884.8  408.11  6051.1  409.96
#Mann= 8 ,-1 , 0
  4314.3     .07       0  4800.7      .1       0  4968.1     .05       0
  4974.3      .1       0  5109.4     .07       0    5216     .05       0
  5511.6     .07       0  5884.8     .12       0
Bank Sta=4968.1,4974.3
XS Rating Curve= 0 ,0
Exp/Cntr=0.3,0.1

Type RM Length L Ch R = 1 ,67794   ,408,408,408
BEGIN DESCRIPTION:
B19657
END DESCRIPTION:
XS GIS Cut Line= 3
       2393965.1     13597921.15      2394577.78     13597507.32
      2395791.23     13597373.09
#Sta/Elev= 30
  4112.5  414.79  4353.7  409.34  4596.2  405.92    4656   406.1  4787.8  404.27
  4793.8  404.68  4836.4  400.33  4855.3  399.57  4869.2  398.72  4889.3  399.26
  4909.4  398.33  4959.7  398.25  4969.8  396.79  4976.4  393.47  4976.9  392.97
  4983.2  393.47  4989.9  394.45    5000  400.75  5007.2  401.72  5015.8  401.81
  5119.1  402.21  5279.5  403.43  5370.2  405.06  5516.3  405.16  5603.6  404.69
  5613.7  402.74  5653.9  405.76  5754.5  406.05  5857.1  407.62  6072.7  409.53
#Mann= 9 ,-1 , 0
  4112.5     .05       0  4596.2     .07       0  4855.3      .1       0
  4976.4     .05       0  4983.2      .1       0  5015.8     .07       0
  5119.1     .05       0  5516.3     .07       0  5857.1     .12       0
Bank Sta=4976.4,4983.2
XS Rating Curve= 0 ,0
Exp/Cntr=0.3,0.1

Type RM Length L Ch R = 1 ,67386   ,623,623,623
BEGIN DESCRIPTION:
B19656
END DESCRIPTION:
XS GIS Cut Line= 3
      2394008.08     13597974.89      2395271.06      13597722.3
      2395881.88     13597749.09
#Sta/Elev= 30
  4224.4  414.37    4350  410.44    4503  407.12  4837.9  402.07  4863.6  402.23
  4904.5   401.1  4910.9  399.12  4924.9  397.26  4945.3  396.41    4967  396.75
  4972.5  395.49    4973  394.99  4979.4  395.49  4996.3  398.12  5037.1  397.05
  5077.9  398.55  5098.3  397.71  5114.9  398.51  5139.1  397.39  5167.4  397.15
    5222  399.32    5273   399.8  5312.4  397.15  5318.8  395.86    5343  397.43
  5369.8  400.42    5394  401.39  5774.4  407.61  5926.7  407.25  6123.8  408.96
#Mann= 7 ,-1 , 0
  4224.4     .05       0  4837.9     .07       0  4863.6      .1       0
  4972.5     .05       0  4979.4      .1       0  5167.4     .07       0
  5774.4     .05       0
Bank Sta=4972.5,4979.4
XS Rating Curve= 0 ,0
Exp/Cntr=0.3,0.1

Type RM Length L Ch R = 1 ,66763   ,495,495,495
BEGIN DESCRIPTION:
B19655
END DESCRIPTION:
XS GIS Cut Line= 3
      2394153.24     13598297.34      2395469.91     13597958.76
      2396060.53     13597926.55
#Sta/Elev= 30
  3854.9  409.41  3970.3  406.11  4122.6   403.3  4383.3  400.84  4476.2  400.62
  4538.2  399.56  4565.5  398.38  4662.1  397.76  4682.5  396.93  4703.4  397.51
    4755   396.1  4804.7  396.88  4809.9  397.51  4967.6  395.11  5008.3  395.66
  5023.5  394.71  5030.3  392.57  5030.8  392.07  5037.3  392.57  5049.1  403.39
  5106.1  405.64  5219.5  407.19  5409.8  405.93  5657.5  408.59  5680.2  408.84
  5690.2  408.18  5700.2  408.75  5710.2  408.11  5756.2  411.32  5805.9   412.1
#Mann= 6 ,-1 , 0
  3854.9     .05       0  4383.3     .07       0  5030.3     .05       0
  5037.3     .07       0  5657.5    .035       0  5756.2     .07       0
Bank Sta=5030.3,5037.3
XS Rating Curve= 0 ,0
Exp/Cntr=0.3,0.1

Type RM Length L Ch R = 1 ,66268   ,538,538,538
BEGIN DESCRIPTION:
B19654
END DESCRIPTION:
XS GIS Cut Line= 3
      2394180.04     13598377.96      2395335.55     13598275.85
      2396098.66     13598130.75
#Sta/Elev= 30
  4202.1   407.8  4404.5  402.82  4633.5   400.5    4950  399.24  4966.1  389.12
  4966.6  388.62  4973.1  389.12  4980.1  392.24  5000.2  394.16  5086.6  395.79
  5140.7  395.39  5198.6  397.57  5241.1   396.2  5281.8  396.86    5283  396.83
  5371.7  398.29  5453.2  403.33  5493.9  404.27  5640.3  402.44  5661.5  402.17
  5687.3  399.85  5713.7  403.42  5718.8  401.91  5758.5  404.87  5841.7  406.24
  5911.2  405.39  5927.6  407.93  5942.4  408.44  6117.6  412.46  6138.9  412.89
#Mann= 10 ,-1 , 0
  4202.1     .05       0  4633.5     .07       0  4966.1     .05       0
  4973.1     .07       0  5281.8      .1       0    5283     .07       0
  5640.3      .1       0  5841.7    .035       0  5942.4     .07       0
  6117.6     .05       0
Bank Sta=4966.1,4973.1
XS Rating Curve= 0 ,0
Exp/Cntr=0.3,0.1