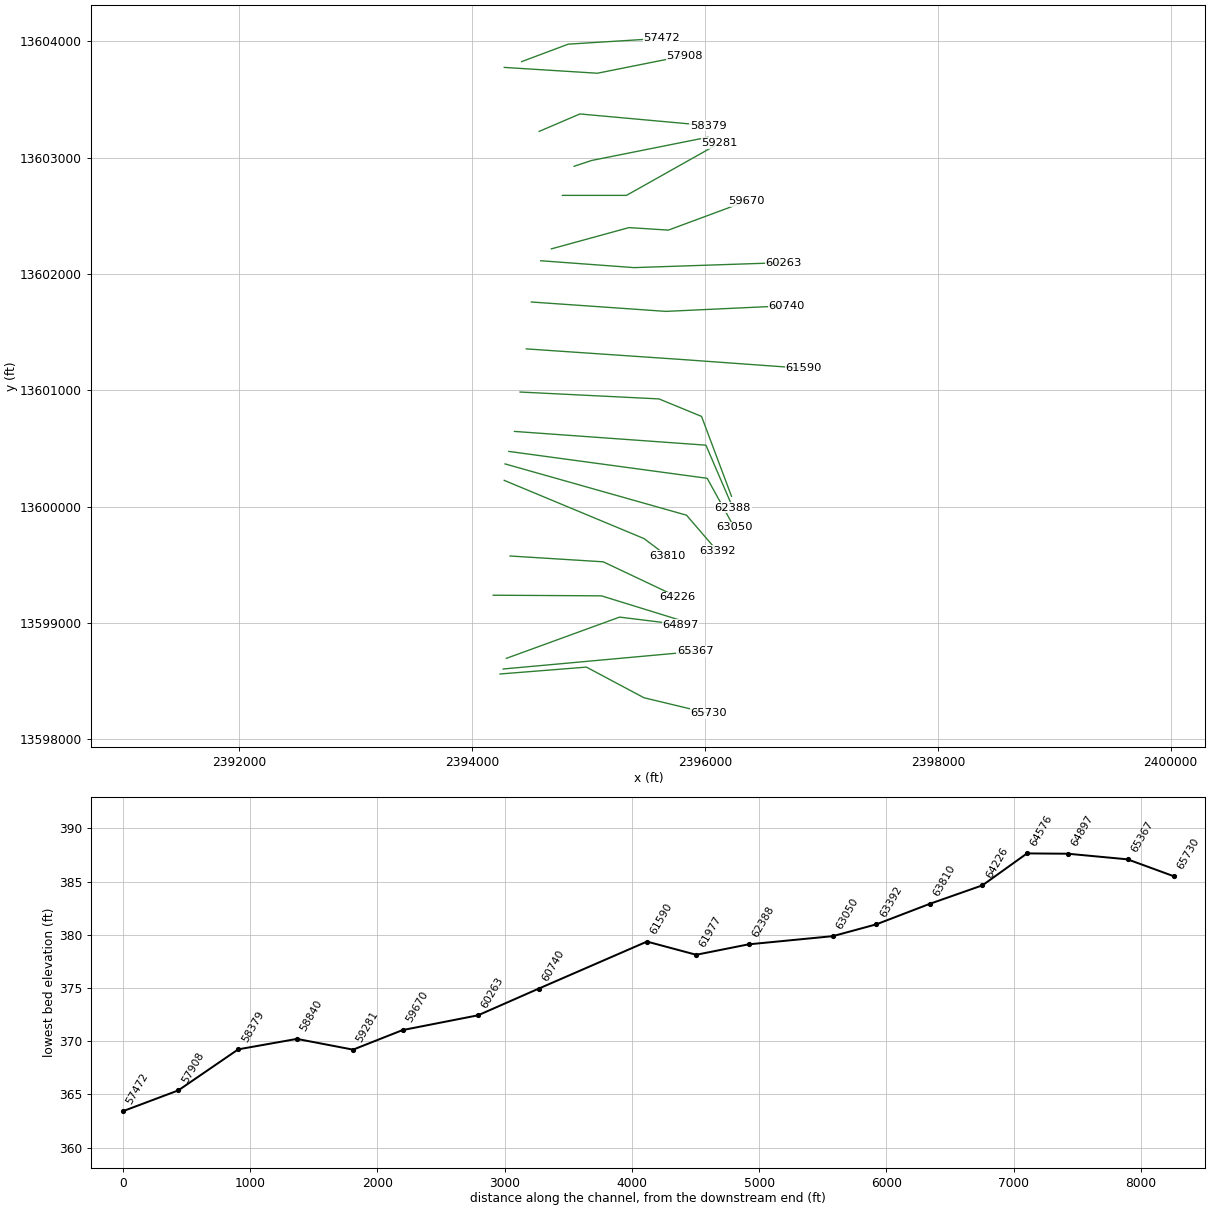
HEC-RAS study MOUND CREEK.prj: MOUND CREEK Base Level Engineering

--- MOUND CREEK.g01 (geometry) --- (continued)

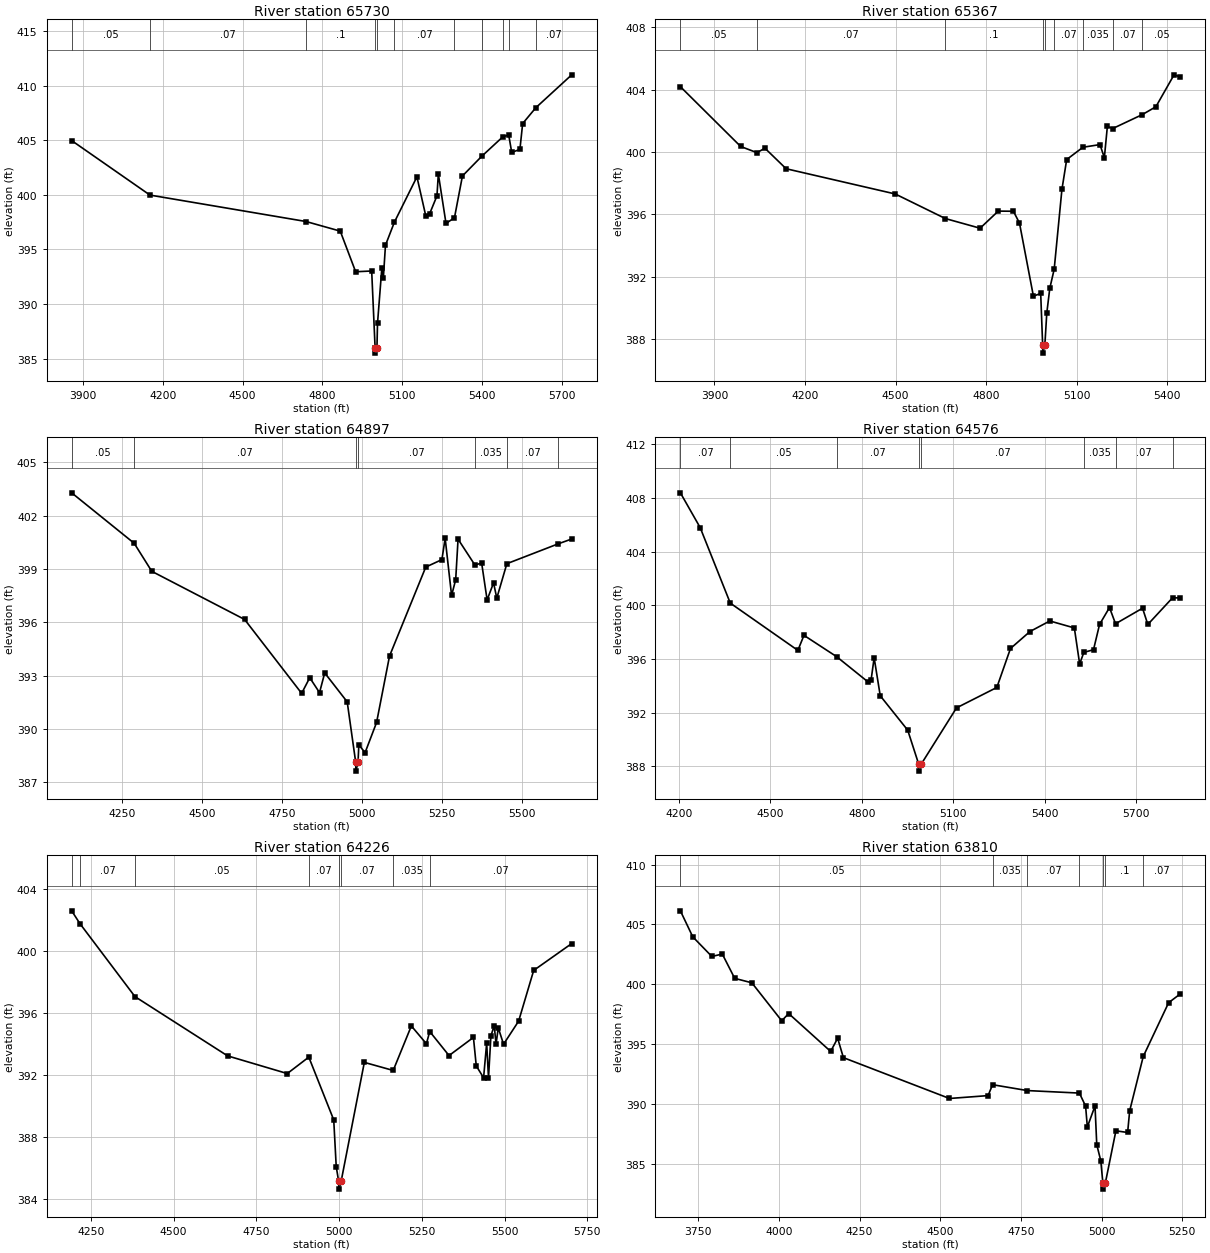
Type RM Length L Ch R = 1 ,65730   ,363,363,363
BEGIN DESCRIPTION:
B19653
END DESCRIPTION:
XS GIS Cut Line= 4
      2394239.21     13598560.69      2394980.85      13598619.8
      2395475.29     13598356.46      2396034.18     13598222.11
#Sta/Elev= 30
  3857.7  404.96  4151.9  399.97  4738.4  397.55    4867  396.67  4924.8  392.95
  4985.1  393.02  4997.9     386  4998.4   385.5  5004.9     386    5007  388.23
  5023.3   393.3    5029  392.42  5036.9  395.38  5070.6   397.5  5155.1  401.64
  5188.4  398.06  5202.7  398.25  5230.4   399.9  5235.5  401.91  5264.4  397.37
  5296.2   397.9  5326.1  401.72  5398.1  403.51  5477.6   405.3    5500  405.47
  5511.3  403.88  5542.1  404.15  5552.4  406.52  5601.9  407.97  5736.7  410.98
#Mann= 11 ,-1 , 0
  3857.7     .05       0  4151.9     .07       0  4738.4      .1       0
  4997.9     .05       0  5004.9      .1       0  5070.6     .07       0
  5296.2      .1       0  5398.1     .07       0  5477.6      .1       0
    5500    .035       0  5601.9     .07       0
Bank Sta=4997.9,5004.9
XS Rating Curve= 0 ,0
Exp/Cntr=0.3,0.1

Type RM Length L Ch R = 1 ,65367   ,470,470,470
BEGIN DESCRIPTION:
B19652
END DESCRIPTION:
XS GIS Cut Line= 2
      2394266.11     13598603.68      2395915.97     13598754.16
#Sta/Elev= 30
  3787.2   404.2  3986.9  400.36  4041.1  399.96  4067.2  400.25  4137.5  398.93
    4499  397.31  4665.3  395.73  4780.2  395.11  4840.4  396.21  4890.6   396.2
  4910.7  395.44  4956.8  390.75    4981  390.92  4987.5  387.59    4988  387.09
  4994.7  387.59  5001.1  389.65  5011.1  391.25  5025.7  392.48  5051.3   397.6
  5067.1  399.52    5121  400.31  5177.4  400.48  5191.9  399.64  5201.9  401.65
  5219.5  401.51    5318  402.41  5362.6  402.91  5422.8  404.96  5443.9  404.82
#Mann= 9 ,-1 , 0
  3787.2     .05       0  4041.1     .07       0  4665.3      .1       0
  4987.5     .05       0  4994.7      .1       0  5025.7     .07       0
    5121    .035       0  5219.5     .07       0    5318     .05       0
Bank Sta=4987.5,4994.7
XS Rating Curve= 0 ,0
Exp/Cntr=0.3,0.1

Type RM Length L Ch R = 1 ,64897   ,321,321,321
BEGIN DESCRIPTION:
B19651
END DESCRIPTION:
XS GIS Cut Line= 3
      2394292.96     13598695.05      2395265.69     13599049.75
      2395787.03     13598985.25
#Sta/Elev= 30
  4093.5  403.29  4288.6  400.45  4343.6  398.87  4633.3  396.16  4811.3     392
  4836.6  392.88  4867.1  392.04  4883.3  393.15  4953.5  391.52    4980  388.12
  4980.5  387.62  4987.3  388.12  4989.8   389.1  5009.3  388.66  5045.2  390.36
  5085.6   394.1  5198.7  399.11  5249.1  399.53  5259.2  400.73  5279.3  397.51
  5292.1   398.4  5299.5  400.68  5352.3  399.22  5373.1  399.34  5390.2  397.26
  5410.3  398.22  5420.4  397.36  5451.8   399.3  5610.9  400.41  5654.2  400.69
#Mann= 7 ,-1 , 0
  4093.5     .05       0  4288.6     .07       0    4980     .05       0
  4987.3     .07       0  5352.3    .035       0  5451.8     .07       0
  5610.9     .05       0
Bank Sta=4980,4987.3
XS Rating Curve= 0 ,0
Exp/Cntr=0.3,0.1

Type RM Length L Ch R = 1 ,64576   ,350,350,350
BEGIN DESCRIPTION:
B19650
END DESCRIPTION:
XS GIS Cut Line= 3
      2394180.05     13599237.85      2395109.83     13599232.47
      2395787.04     13599022.86
#Sta/Elev= 30
  4205.5  408.37  4270.4  405.78    4369  400.16  4590.5  396.64  4610.5  397.76
  4717.7  396.17  4820.5  394.29  4830.5  394.44  4840.5  396.09  4860.5  393.26
  4950.5   390.7  4986.8  388.15  4987.3  387.65  4994.2  388.15  5110.5  392.36
  5242.6  393.88  5287.3  396.78  5350.9  398.04  5416.2  398.83  5496.6  398.31
    5514  395.63  5527.7  396.49  5559.4  396.69  5579.2  398.57  5611.8  399.83
  5631.6  398.62  5720.1  399.78  5737.4  398.57  5818.6  400.56  5844.2  400.54
#Mann= 8 ,-1 , 0
  4205.5     .07       0    4369     .05       0  4717.7     .07       0
  4986.8     .05       0  4994.2     .07       0  5527.7    .035       0
  5631.6     .07       0  5818.6     .05       0
Bank Sta=4986.8,4994.2
XS Rating Curve= 0 ,0
Exp/Cntr=0.3,0.1

Type RM Length L Ch R = 1 ,64226   ,416,416,416
BEGIN DESCRIPTION:
MOUND CREEK 88.0
END DESCRIPTION:
XS GIS Cut Line= 3
      2394325.03       13599575.        2395125.       13599525.
       2395765.5     13599221.72
#Sta/Elev= 30
  4192.3  402.59  4217.1  401.77  4383.5  397.06  4663.2  393.24  4843.5   392.1
  4908.5  393.16  4983.8  389.11  4991.3   386.1  4998.7  385.15  4999.2  384.65
  5006.1  385.15  5076.2  392.82  5163.4   392.3  5218.2  395.17  5263.7  394.02
  5273.7  394.81    5332  393.26  5405.7  394.43  5414.3  392.59  5436.4  391.83
  5445.7  394.07  5451.2  391.81  5458.5  394.53  5468.5  395.19    5474  393.99
  5480.7  395.05  5496.7  393.99  5542.2  395.48  5587.7  398.75  5702.5  400.48
#Mann= 8 ,-1 , 0
  4192.3     .05       0  4217.1     .07       0  4383.5     .05       0
  4908.5     .07       0  4998.7     .05       0  5006.1     .07       0
  5163.4    .035       0  5273.7     .07       0
Bank Sta=4998.7,5006.1
XS Rating Curve= 0 ,0
Exp/Cntr=0.3,0.1

Type RM Length L Ch R = 1 ,63810   ,418,418,418
BEGIN DESCRIPTION:
MOUND CREEK 87.0
END DESCRIPTION:
XS GIS Cut Line= 3
      2394275.04     13600224.98        2395475.       13599725.
      2395675.04     13599574.97
#Sta/Elev= 30
  3694.6  406.14    3733  403.97  3792.1  402.33  3824.6  402.53    3863   400.5
  3916.1  400.13  4008.7  396.96  4030.4  397.56  4160.4   394.4  4182.1   395.5
  4199.9  393.88  4528.7  390.47  4648.4  390.71  4662.3  391.62  4770.1  391.13
  4931.5  390.92  4950.7  389.83  4956.1  388.09  4979.9  389.85  4985.3  386.61
  4997.7  385.28  5004.3   383.4  5004.8   382.9  5011.8   383.4  5044.6  387.77
    5081  387.63  5087.3  389.44  5129.4  393.98  5208.1  398.47  5244.6  399.21
#Mann= 7 ,-1 , 0
  3694.6     .05       0  4662.3    .035       0  4770.1     .07       0
  4931.5      .1       0  5004.3     .05       0  5011.8      .1       0
  5129.4     .07       0
Bank Sta=5004.3,5011.8
XS Rating Curve= 0 ,0
Exp/Cntr=0.3,0.1

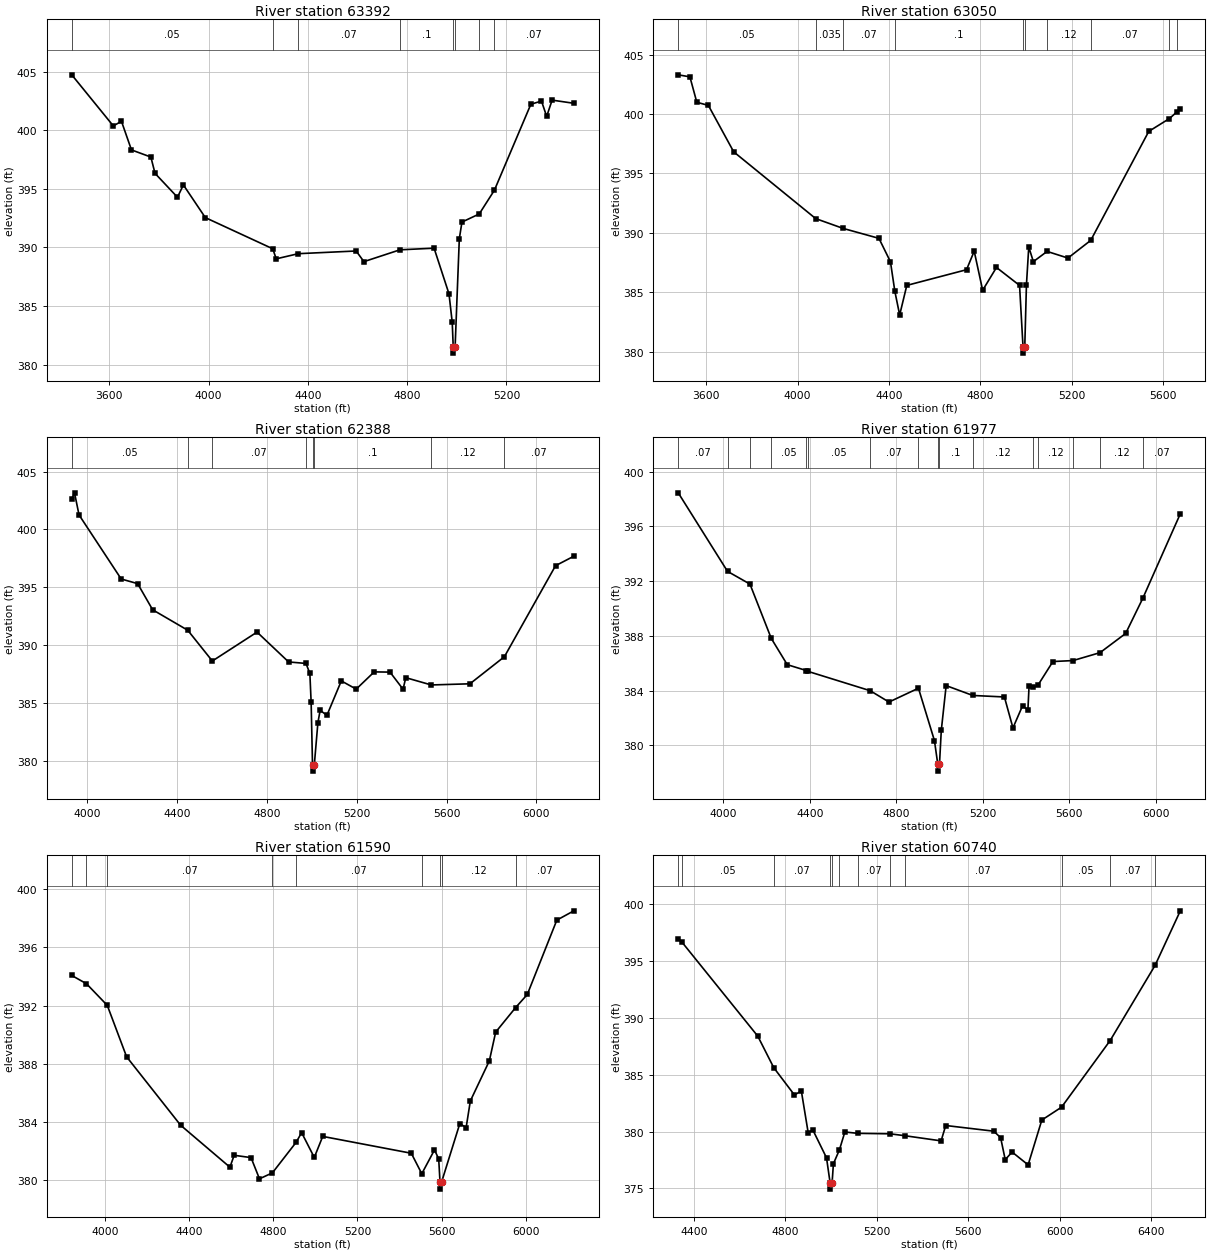
Type RM Length L Ch R = 1 ,63392   ,342,342,342
BEGIN DESCRIPTION:
B19649
END DESCRIPTION:
XS GIS Cut Line= 3
      2394282.21     13600366.44      2395840.74     13599925.76
      2396103.82     13599619.73
#Sta/Elev= 30
  3448.4  404.74  3615.7  400.38  3648.7  400.77  3688.9  398.33  3767.2  397.72
  3783.8  396.33  3874.3  394.29  3898.2  395.34  3986.6  392.55  4258.2  389.89
  4272.3  389.03  4361.2  389.47  4594.4   389.7  4625.6  388.79  4770.7   389.8
  4908.4  389.94  4968.5  386.04  4981.5  383.61  4985.6  381.48  4986.1  380.98
  4993.1  381.48  5010.1  390.75  5020.7  392.17  5090.3  392.86  5151.5  394.89
  5298.4  402.23  5341.2   402.5  5362.1  401.19    5384  402.58  5471.6  402.31
#Mann= 8 ,-1 , 0
  3448.4     .05       0  4258.2    .035       0  4361.2     .07       0
  4770.7      .1       0  4985.6     .05       0  4993.1      .1       0
  5090.3     .12       0  5151.5     .07       0
Bank Sta=4985.6,4993.1
XS Rating Curve= 0 ,0
Exp/Cntr=0.3,0.1

Type RM Length L Ch R = 1 ,63050   ,662,662,662
BEGIN DESCRIPTION:
B19648
END DESCRIPTION:
XS GIS Cut Line= 3
       2394314.4     13600473.94      2396018.09     13600242.84
       2396249.2     13599823.62
#Sta/Elev= 30
  3477.7  403.29  3528.8  403.12    3559  400.98  3609.5  400.72  3720.5  396.81
  4079.5  391.19  4200.4  390.36  4356.3  389.53  4406.7  387.56    4426  385.07
  4447.1  383.08  4478.3  385.57  4739.8  386.89  4773.4  388.45  4810.4  385.16
  4870.9  387.08  4971.9  385.57  4987.2  380.37  4987.7  379.87  4994.7  380.37
  5002.1  385.62  5012.2   388.8  5032.4  387.57  5092.5  388.43  5183.8  387.87
  5283.6  389.36  5537.6  398.53    5628  399.61  5659.1  400.14  5675.7  400.44
#Mann= 10 ,-1 , 0
  3477.7     .05       0  4079.5    .035       0  4200.4     .07       0
    4426      .1       0  4987.2     .05       0  4994.7      .1       0
  5092.5     .12       0  5283.6     .07       0    5628     .12       0
  5659.1     .07       0
Bank Sta=4987.2,4994.7
XS Rating Curve= 0 ,0
Exp/Cntr=0.3,0.1

Type RM Length L Ch R = 1 ,62388   ,411,411,411
BEGIN DESCRIPTION:
B19647
END DESCRIPTION:
XS GIS Cut Line= 3
      2394362.78     13600645.91      2396007.34     13600527.68
      2396238.43     13599990.26
#Sta/Elev= 30
  3932.7  402.63  3944.9  403.16    3965  401.25  4152.6  395.71  4225.7  395.31
  4292.5  393.05  4448.7  391.28  4558.1  388.62    4757  391.12  4897.4  388.54
  4974.7  388.41    4992  387.55  4997.7  385.04  5003.8   379.6  5004.3   379.1
  5011.6   379.6  5027.7  383.28  5037.8  384.36  5067.8  383.92  5131.9   386.9
  5198.2  386.19  5278.4  387.68  5348.6  387.66  5406.7  386.18  5418.7  387.18
  5532.3  386.55  5704.2  386.65  5857.5  388.99  6085.1  396.86  6166.5  397.68
#Mann= 8 ,-1 , 0
  3932.7     .05       0  4448.7    .035       0  4558.1     .07       0
  4974.7      .1       0  5003.8     .05       0  5011.6      .1       0
  5532.3     .12       0  5857.5     .07       0
Bank Sta=5003.8,5011.6
XS Rating Curve= 0 ,0
Exp/Cntr=0.3,0.1

Type RM Length L Ch R = 1 ,61977   ,387,387,387
BEGIN DESCRIPTION:
B19646
END DESCRIPTION:
XS GIS Cut Line= 4
      2394411.18     13600984.49      2395604.27     13600925.38
      2395969.72      13600774.9      2396227.11     13600088.54
#Sta/Elev= 30
  3791.1  398.46  4019.1  392.72  4122.9  391.79  4221.5  387.82  4295.5   385.9
  4384.3  385.47  4391.4  385.41  4678.7     384  4766.1  383.17  4902.4  384.18
  4976.4  380.35  4991.9  378.62  4992.4  378.12  4999.7  378.62  5008.1   381.1
  5030.6  384.37  5153.9  383.65  5300.1  383.54  5339.6  381.28  5383.9  382.89
  5408.8  382.59  5414.1  384.31  5434.4  384.25  5454.4  384.38  5524.5  386.13
  5617.5   386.2  5742.6  386.78  5860.9  388.18  5940.3  390.75  6113.9  396.93
#Mann= 16 ,-1 , 0
  3791.1     .07       0  4019.1     .05       0  4122.9    .035       0
  4221.5     .05       0  4384.3     .07       0  4391.4     .05       0
  4678.7     .07       0  4902.4      .1       0  4991.9     .05       0
  4999.7      .1       0  5153.9     .12       0  5434.4      .1       0
  5454.4     .12       0  5617.5      .1       0  5742.6     .12       0
  5940.3     .07       0
Bank Sta=4991.9,4999.7
XS Rating Curve= 0 ,0
Exp/Cntr=0.3,0.1

Type RM Length L Ch R = 1 ,61590   ,850,850,850
BEGIN DESCRIPTION:
MOUND CREEK 86.0
END DESCRIPTION:
XS GIS Cut Line= 3
      2394464.91     13601355.32      2395803.12     13601263.96
      2396845.68     13601188.72
#Sta/Elev= 30
  3841.9  394.07  3911.9   393.5  4010.7  392.01  4102.6  388.47  4359.3  383.76
  4593.7  380.87  4613.8  381.69    4694  381.53  4734.1  380.07  4795.6  380.48
  4908.2  382.58  4934.5  383.25  4994.7  381.54  5034.8  382.99  5455.8  381.83
  5505.7  380.42  5566.1  382.06  5586.1  381.44  5592.3  379.86  5592.8  379.36
  5600.1  379.86  5686.4  383.87  5716.5   383.6  5736.5  385.43  5826.8  388.19
  5856.9  390.17  5951.8  391.86  6007.2  392.76  6147.6  397.88  6228.5  398.52
#Mann= 9 ,-1 , 0
  3841.9     .05       0  3911.9    .035       0  4010.7     .07       0
  4795.6     .12       0  4908.2     .07       0  5505.7     .12       0
  5592.3     .05       0  5600.1     .12       0  5951.8     .07       0
Bank Sta=5592.3,5600.1
XS Rating Curve= 0 ,0
Exp/Cntr=0.3,0.1

Type RM Length L Ch R = 1 ,60740   ,477,477,477
BEGIN DESCRIPTION:
MOUND CREEK 85.0
END DESCRIPTION:
XS GIS Cut Line= 3
      2394507.94     13601758.39      2395663.39     13601677.78
      2396700.01     13601726.12
#Sta/Elev= 30
  4331.8  396.94  4346.9  396.67  4679.7  388.38  4749.6  385.61  4840.1  383.21
  4870.2  383.57  4900.2  379.89  4920.3  380.15  4980.4  377.69  4996.4  375.44
  4996.9  374.94  5004.6  375.44  5010.5  377.17  5036.8  378.39  5060.6  379.96
  5117.6  379.84  5258.4   379.8  5323.9  379.63  5481.6  379.18  5501.7  380.53
  5711.9  380.03  5741.9  379.46    5762  377.53    5792   378.2  5862.1  377.07
  5922.1  381.01  6008.3  382.14  6220.8  387.99  6417.5   394.6  6527.8  399.39
#Mann= 12 ,-1 , 0
  4331.8    .035       0  4346.9     .05       0  4749.6     .07       0
  4996.4     .05       0  5004.6     .07       0  5036.8     .12       0
  5117.6     .07       0  5258.4     .12       0  5323.9     .07       0
  6008.3     .05       0  6220.8     .07       0  6417.5     .05       0
Bank Sta=4996.4,5004.6
XS Rating Curve= 0 ,0
Exp/Cntr=0.3,0.1

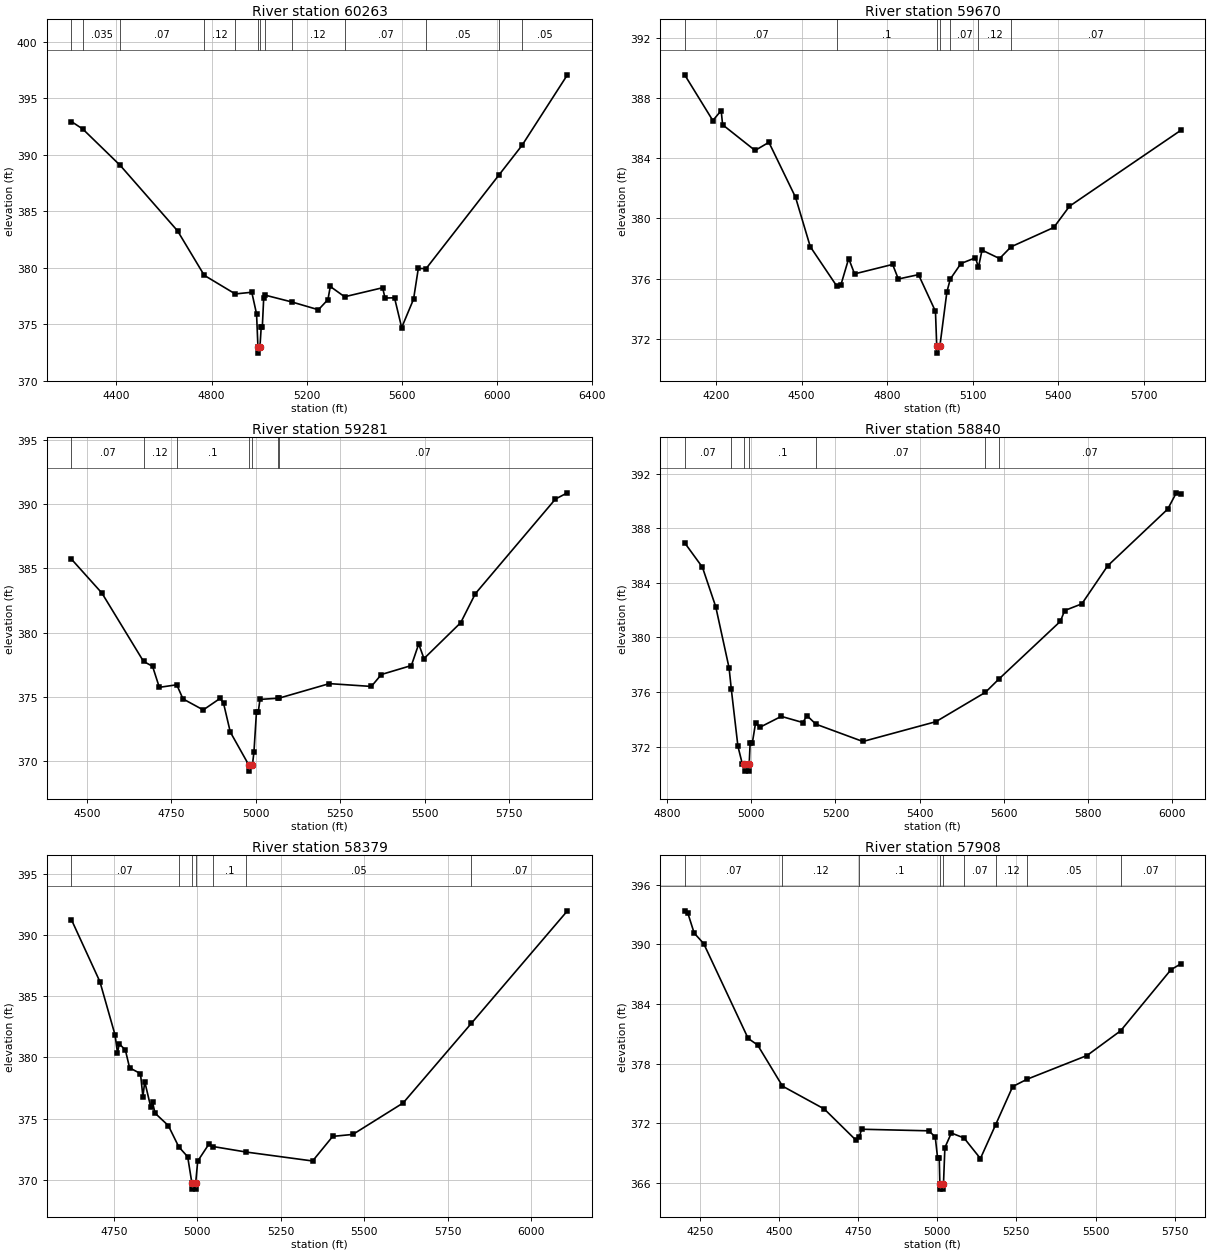
Type RM Length L Ch R = 1 ,60263   ,593,593,593
BEGIN DESCRIPTION:
MOUND CREEK 84.0
END DESCRIPTION:
XS GIS Cut Line= 3
      2394588.55     13602113.09       2395389.3     13602053.98
      2396671.85     13602096.91
#Sta/Elev= 30
  4210.7  392.93  4258.3  392.27  4415.8  389.05  4656.8  383.26  4769.2  379.32
  4899.7  377.67  4969.2  377.82  4989.3   375.9  4995.2  372.93  4995.7  372.43
  5003.4  372.93    5009  374.78  5013.6  374.78  5019.3  377.29  5024.1  377.57
  5137.7  376.96  5249.5  376.27  5289.5  377.17  5299.5  378.33  5359.6  377.42
  5519.6  378.22  5529.6  377.31  5569.6  377.33  5599.7  374.69  5649.7  377.21
  5669.7  379.93  5702.3  379.91  6007.4  388.16  6105.8  390.82  6296.9  397.07
#Mann= 13 ,-1 , 0
  4210.7     .07       0  4258.3    .035       0  4415.8     .07       0
  4769.2     .12       0  4899.7      .1       0  4995.2     .05       0
  5003.4      .1       0  5024.1     .07       0  5137.7     .12       0
  5359.6     .07       0  5702.3     .05       0  6007.4     .07       0
  6105.8     .05       0
Bank Sta=4995.2,5003.4
XS Rating Curve= 0 ,0
Exp/Cntr=0.3,0.1

Type RM Length L Ch R = 1 ,59670   ,389,389,389
BEGIN DESCRIPTION:
B19645
END DESCRIPTION:
XS GIS Cut Line= 4
      2394679.89     13602215.21       2395346.3     13602397.93
      2395684.88     13602376.44      2396350.68     13602623.42
#Sta/Elev= 30
  4089.8  389.55  4188.6  386.51  4217.9  387.17    4223  386.23  4336.8  384.52
  4385.4  385.06  4478.8  381.41  4530.6  378.12  4623.2  375.51  4638.4   375.6
  4665.4  377.33  4686.1  376.31  4819.6  376.94  4839.6  375.97  4910.4  376.26
  4969.9  373.82  4974.3  371.54  4974.8  371.04  4985.6  371.54    5010  375.11
    5022  375.97  5059.4     377  5110.2  377.38  5120.8  376.75  5133.3  377.89
  5194.9  377.33  5235.1  378.11  5385.3   379.4  5440.2  380.81  5830.2  385.85
#Mann= 7 ,-1 , 0
  4089.8     .07       0  4623.2      .1       0  4974.3     .05       0
  4985.6      .1       0    5022     .07       0  5120.8     .12       0
  5235.1     .07       0
Bank Sta=4974.3,4985.6
XS Rating Curve= 0 ,0
Exp/Cntr=0.3,0.1

Type RM Length L Ch R = 1 ,59281   ,441,441,441
BEGIN DESCRIPTION:
MOUND CREEK 83.0
END DESCRIPTION:
XS GIS Cut Line= 3
      2394775.04       13602675.        2395325.       13602675.
      2396124.97     13603124.98
#Sta/Elev= 30
  4454.8  385.72  4544.8  383.08  4668.1  377.75  4694.8  377.37  4714.8  375.73
  4766.4  375.93  4784.8  374.83  4844.8  373.97  4894.8  374.87  4904.8   374.5
  4924.8  372.25  4979.1   369.7  4979.6   369.2  4990.4   369.7  4994.8  370.67
  5002.3   373.8  5007.6   373.8  5012.7  374.79  5065.9  374.88  5068.3  374.88
    5218  376.02  5342.3   375.8  5371.9  376.73  5460.8  377.43  5482.5  379.11
  5498.1  377.97  5606.8  380.77  5650.1  383.03  5887.3  390.41  5922.6  390.89
#Mann= 7 ,-1 , 0
  4454.8     .07       0  4668.1     .12       0  4766.4      .1       0
  4979.1     .05       0  4990.4      .1       0  5065.9     .12       0
  5068.3     .07       0
Bank Sta=4979.1,4990.4
XS Rating Curve= 0 ,0
Exp/Cntr=0.3,0.1

Type RM Length L Ch R = 1 ,58840   ,461,461,461
BEGIN DESCRIPTION:
MOUND CREEK 82.0
END DESCRIPTION:
XS GIS Cut Line= 3
      2394874.96     13602924.99        2395025.       13602975.
      2396025.04     13603175.01
#Sta/Elev= 30
  4841.9  386.93  4884.1  385.14  4915.7  382.25  4947.4  377.77  4952.7  376.21
  4968.4  372.03    4979  370.72  4983.8  370.71  4984.3  370.21  4994.7  370.21
  4995.2  370.71  4997.4  372.27  5002.6  372.27  5010.3  373.73  5020.5  373.42
  5071.4  374.22  5122.4  373.77  5132.6  374.27  5153.5  373.65  5265.2  372.38
  5438.6  373.83  5556.2  375.98  5588.5  376.96  5734.3  381.18  5744.5  381.97
  5785.3  382.46  5846.5  385.24  5989.3   389.4  6009.7  390.59  6019.9  390.52
#Mann= 7 ,-1 , 0
  4841.9     .07       0  4952.7      .1       0  4983.8     .05       0
  4995.2      .1       0  5153.5     .07       0  5556.2     .05       0
  5588.5     .07       0
Bank Sta=4983.8,4995.2
XS Rating Curve= 0 ,0
Exp/Cntr=0.3,0.1

Type RM Length L Ch R = 1 ,58379   ,471,471,471
BEGIN DESCRIPTION:
MOUND CREEK 81.0
END DESCRIPTION:
XS GIS Cut Line= 3
      2394575.01       13603225.        2394925.       13603375.
      2396024.99       13603275.
#Sta/Elev= 30
  4623.4  391.24  4708.6  386.18  4753.9  381.83  4761.2  380.37  4766.6   381.1
  4784.8   380.6  4797.5  379.14  4830.1  378.67  4837.4  376.77  4842.8  378.02
  4860.9  375.93  4866.4  376.31  4873.6  375.44  4913.5  374.42  4944.7  372.69
  4971.5  371.87    4984  369.73  4984.5  369.23  4994.9  369.23  4995.4  369.73
  5001.5  371.52  5034.3  372.88  5047.5  372.71  5146.6  372.26  5345.6  371.53
  5405.8  373.54  5466.1   373.7  5616.7  376.27  5821.1  382.78  6108.7  391.97
#Mann= 7 ,-1 , 0
  4623.4     .07       0  4944.7     .12       0    4984     .05       0
  4995.4     .12       0  5047.5      .1       0  5146.6     .05       0
  5821.1     .07       0
Bank Sta=4984,4995.4
XS Rating Curve= 0 ,0
Exp/Cntr=0.3,0.1

Type RM Length L Ch R = 1 ,57908   ,436,436,436
BEGIN DESCRIPTION:
MOUND CREEK 80.0
END DESCRIPTION:
XS GIS Cut Line= 3
      2394275.03       13603775.        2395075.       13603725.
      2395825.01       13603875.
#Sta/Elev= 30
  4202.4  393.39  4212.4  393.16  4232.4  391.15  4262.5  390.09  4402.8  380.55
  4432.8  379.88  4511.4  375.74  4643.2  373.44  4743.4   370.3  4754.1  370.61
    4761   371.4  4973.9  371.24  4993.9  370.61  5001.4  368.46  5006.5  368.46
  5008.4  365.87  5008.9  365.37  5019.3  365.37  5019.8  365.87  5024.3  369.55
  5044.7  371.02  5084.7  370.52  5136.5  368.45  5184.5  371.85  5238.5   375.7
  5284.2  376.44    5473  378.82  5579.3  381.31  5738.2  387.46  5768.8  388.04
#Mann= 9 ,-1 , 0
  4202.4     .07       0  4511.4     .12       0  4754.1      .1       0
  5008.4     .05       0  5019.8      .1       0  5084.7     .07       0
  5184.5     .12       0  5284.2     .05       0  5579.3     .07       0
Bank Sta=5008.4,5019.8
XS Rating Curve= 0 ,0
Exp/Cntr=0.3,0.1

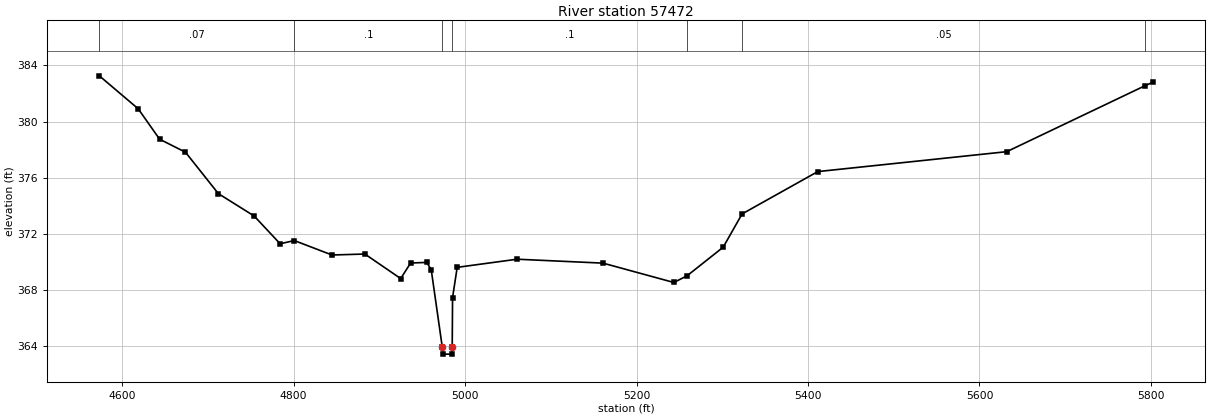
Type RM Length L Ch R = 1 ,57472   ,420,420,420
BEGIN DESCRIPTION:
MOUND CREEK 79.0
END DESCRIPTION:
XS GIS Cut Line= 3
      2394425.04     13603825.02        2394825.       13603975.
      2395624.99       13604025.
#Sta/Elev= 30
  4573.4  383.26  4618.7  380.91  4643.7  378.74  4673.9  377.81  4712.2  374.86
    4754  373.26  4784.3  371.28  4800.8  371.51  4844.8  370.48  4883.1  370.55
  4924.9   368.8  4936.5  369.91  4955.2  369.95  4960.5  369.44  4973.4  363.91
  4973.9  363.41  4984.5  363.41    4985  363.91  4985.4  367.44  4990.8   369.6
  5060.7  370.18  5160.9   369.9  5243.5  368.52    5259     369  5301.1  371.04
  5323.1  373.41  5411.4  376.43  5631.8  377.85  5792.6  382.54  5802.1   382.8
#Mann= 7 ,-1 , 0
  4573.4     .07       0  4800.8      .1       0  4973.4     .05       0
    4985      .1       0    5259     .07       0  5323.1     .05       0
  5792.6     .07       0
Bank Sta=4973.4,4985
XS Rating Curve= 0 ,0
Exp/Cntr=0.3,0.1