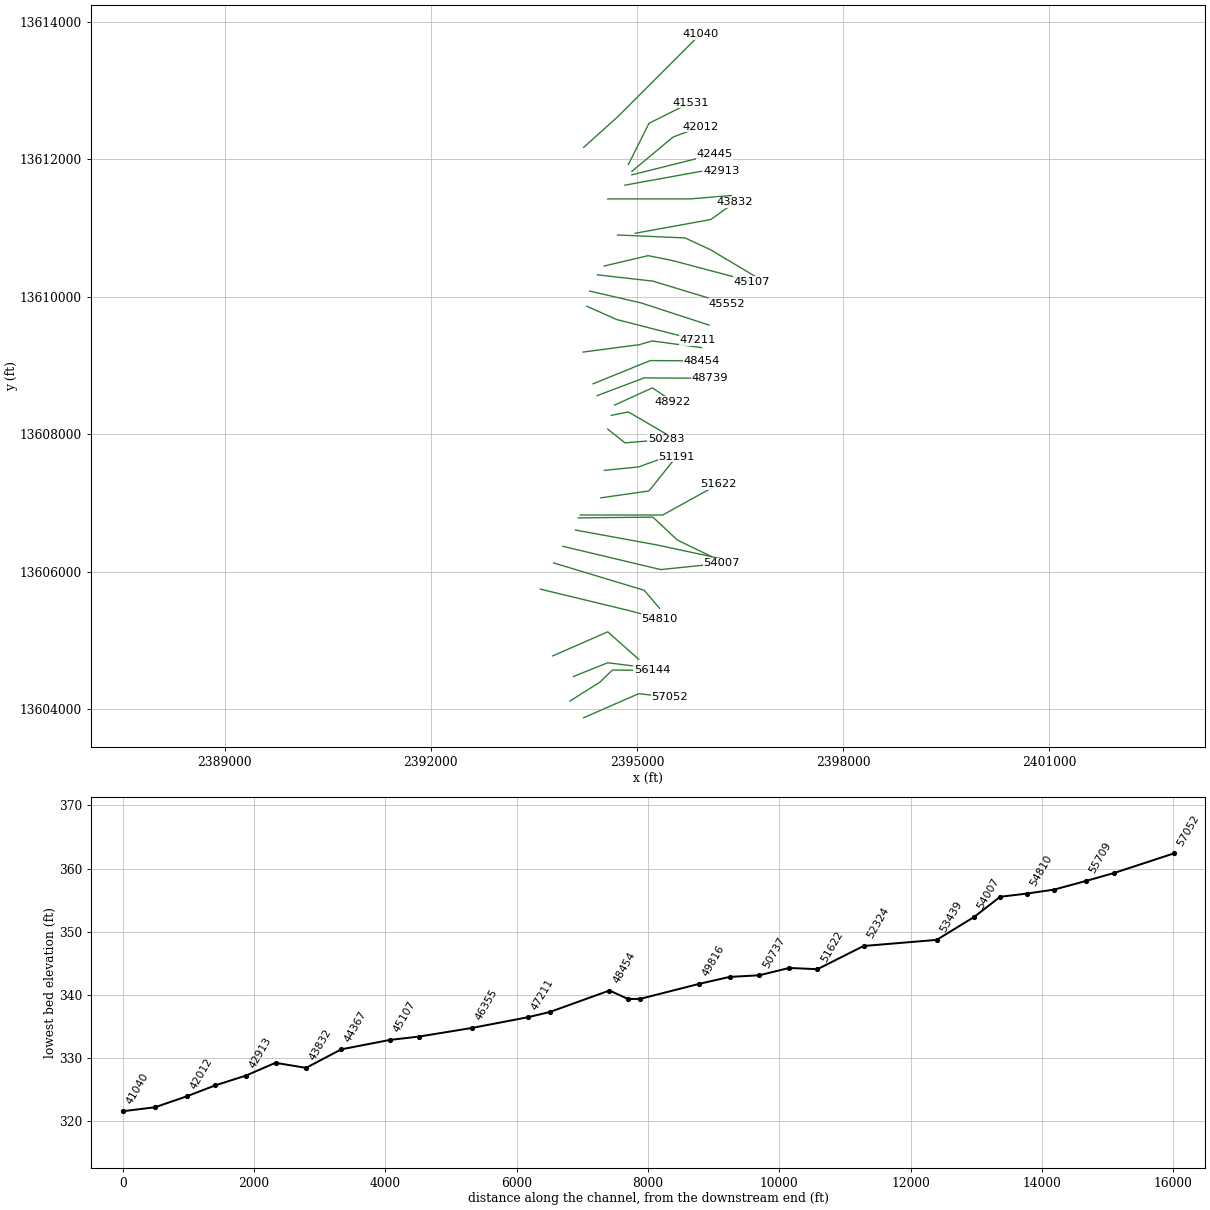
HEC-RAS study MOUND CREEK.prj: MOUND CREEK Base Level Engineering

--- MOUND CREEK.g01 (geometry) --- (continued)

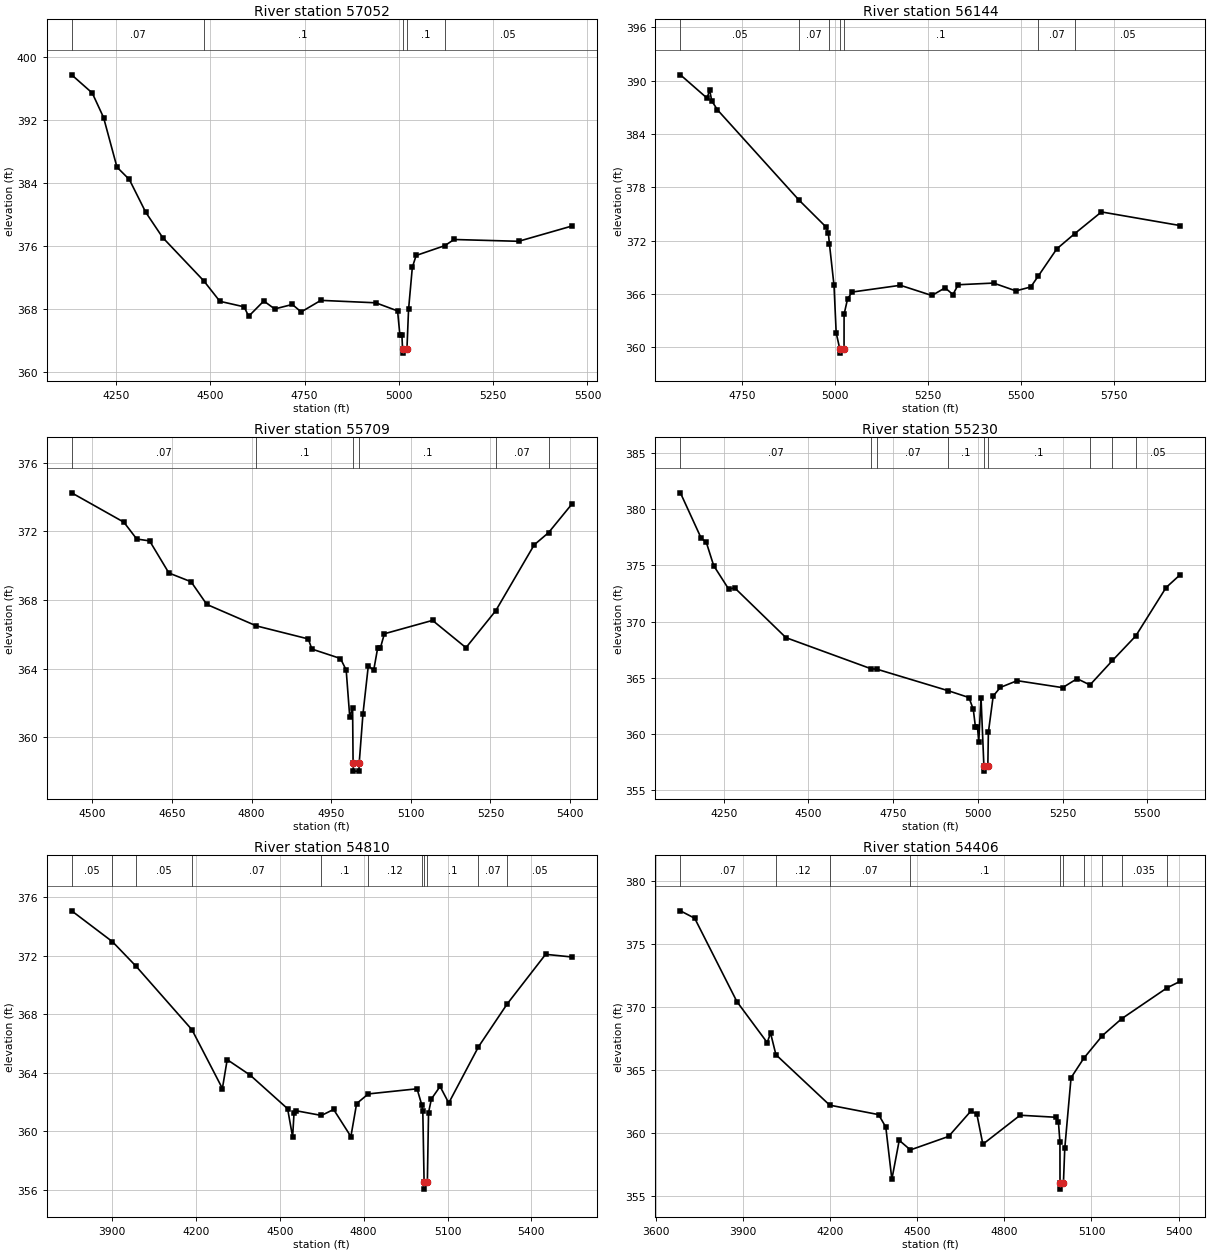
Type RM Length L Ch R = 1 ,57052   ,908,908,908
BEGIN DESCRIPTION:
MOUND CREEK 78.0
END DESCRIPTION:
XS GIS Cut Line= 3
      2394224.96     13603874.98        2395025.       13604225.
      2395474.97       13604175.
#Sta/Elev= 30
  4132.2  397.75  4186.8  395.44  4216.8  392.33  4252.3  386.03  4285.1  384.46
  4328.7  380.29  4373.5  377.09  4482.7  371.58  4525.2  368.99  4589.5  368.29
  4601.6  367.09  4641.7  369.03  4670.6  368.02  4717.4  368.59  4740.8  367.64
    4793  369.11  4938.8   368.8  4996.5  367.77  5002.7  364.65    5008  364.65
  5009.7  362.91  5010.2  362.41  5021.3  362.91  5025.6  367.96  5035.6   373.3
  5045.7  374.81  5121.8  376.06  5146.3  376.84  5317.4  376.61  5458.2  378.54
#Mann= 5 ,-1 , 0
  4132.2     .07       0  4482.7      .1       0  5009.7     .05       0
  5021.3      .1       0  5121.8     .05       0
Bank Sta=5009.7,5021.3
XS Rating Curve= 0 ,0
Exp/Cntr=0.3,0.1

Type RM Length L Ch R = 1 ,56144   ,435,435,435
BEGIN DESCRIPTION:
B19644
END DESCRIPTION:
XS GIS Cut Line= 4
      2394024.25     13604117.72      2394459.54      13604391.8
      2394642.27     13604569.15      2395217.31     13604563.77
#Sta/Elev= 30
  4584.5  390.66  4656.3  388.03    4663  388.96  4668.9  387.72  4684.2  386.71
  4902.7  376.58  4975.4  373.55  4982.1   372.9    4985  371.66  4997.4  366.96
  5003.3   361.6  5012.8  359.82  5013.3  359.32  5024.4  359.82  5024.5   363.7
  5033.9  365.43  5046.3   366.2  5175.8  366.96  5260.5  365.81    5296  366.67
  5317.1  365.92  5331.2  367.02  5426.3  367.21  5486.3  366.33  5526.3  366.77
  5546.5     368  5596.3  371.06  5644.9  372.79  5716.3  375.22  5928.6  373.68
#Mann= 7 ,-1 , 0
  4584.5     .05       0  4902.7     .07       0    4985      .1       0
  5012.8     .05       0  5024.4      .1       0  5546.5     .07       0
  5644.9     .05       0
Bank Sta=5012.8,5024.4
XS Rating Curve= 0 ,0
Exp/Cntr=0.3,0.1

Type RM Length L Ch R = 1 ,55709   ,479,479,479
BEGIN DESCRIPTION:
MOUND CREEK 77.0
END DESCRIPTION:
XS GIS Cut Line= 3
      2394074.98     13604474.99        2394575.       13604675.
      2394975.05     13604624.99
#Sta/Elev= 30
  4461.3  374.25  4559.6  372.54  4583.8  371.56  4608.1  371.45  4644.4  369.58
  4686.2  369.07  4715.8  367.75  4809.1   366.5  4906.9  365.74  4913.7  365.15
  4967.5   364.6  4978.3  363.93    4985   361.2  4990.4  361.71  4991.3  358.54
  4991.8  358.04  5002.4  358.04  5002.9  358.54  5009.9  361.37    5020  364.18
  5030.1  363.91  5037.6  365.21  5042.7  365.21  5050.2  366.04  5140.9  366.82
  5203.9  365.23  5259.9  367.38  5332.4  371.22  5359.4  371.93    5403  373.58
#Mann= 6 ,-1 , 0
  4461.3     .07       0  4809.1      .1       0  4991.3     .05       0
  5002.9      .1       0  5259.9     .07       0  5359.4     .05       0
Bank Sta=4991.3,5002.9
XS Rating Curve= 0 ,0
Exp/Cntr=0.3,0.1

Type RM Length L Ch R = 1 ,55230   ,420,420,420
BEGIN DESCRIPTION:
MOUND CREEK 76.0
END DESCRIPTION:
XS GIS Cut Line= 3
      2393775.02     13604775.01        2394575.       13605125.
      2395025.02     13604724.98
#Sta/Elev= 30
  4122.4  381.46  4183.6  377.43  4198.8  377.06  4220.6  374.98  4264.7   372.9
  4282.6     373  4433.8  368.57  4685.1   365.8  4702.5  365.76  4913.3  363.84
  4973.8  363.24  4986.6  362.18  4992.9  360.62  4998.9  360.62  5002.7  359.31
  5009.4  363.24  5017.8  357.19  5018.3  356.69  5029.5  357.19  5031.1  360.14
  5045.3  363.37  5066.3  364.14    5116  364.74  5250.2  364.12  5292.9  364.92
  5330.8  364.36  5397.3  366.54  5465.9  368.72  5555.4  373.03  5597.7  374.19
#Mann= 9 ,-1 , 0
  4122.4     .07       0  4685.1      .1       0  4702.5     .07       0
  4913.3      .1       0  5017.8     .05       0  5029.5      .1       0
  5330.8     .05       0  5397.3     .07       0  5465.9     .05       0
Bank Sta=5017.8,5029.5
XS Rating Curve= 0 ,0
Exp/Cntr=0.3,0.1

Type RM Length L Ch R = 1 ,54810   ,404,404,404
BEGIN DESCRIPTION:
B19643
END DESCRIPTION:
XS GIS Cut Line= 3
      2393594.24     13605746.13      2394862.62     13605439.78
      2395330.11     13605316.19
#Sta/Elev= 30
  3755.6  375.05  3901.6  372.94  3986.7  371.25  4185.9  366.93  4294.7  362.92
  4311.9  364.89  4394.2  363.83  4527.9  361.54  4545.9  359.61    4551  361.28
  4558.8   361.4    4649  361.08  4692.5  361.49  4754.3  359.64  4774.8  361.89
  4816.6  362.55  4990.9   362.9  5008.3  361.77  5011.5  361.38  5016.1  356.55
  5016.6  356.05  5027.8  356.55    5032  361.27  5042.3  362.21  5073.3  363.06
  5104.3  361.93  5210.7  365.77  5313.2  368.69  5450.8  372.08    5544   371.9
#Mann= 11 ,-1 , 0
  3755.6     .05       0  3901.6     .07       0  3986.7     .05       0
  4185.9     .07       0    4649      .1       0  4816.6     .12       0
  5008.3      .1       0  5016.1     .05       0  5027.8      .1       0
  5210.7     .07       0  5313.2     .05       0
Bank Sta=5016.1,5027.8
XS Rating Curve= 0 ,0
Exp/Cntr=0.3,0.1

Type RM Length L Ch R = 1 ,54406   ,399,399,399
BEGIN DESCRIPTION:
B19642
END DESCRIPTION:
XS GIS Cut Line= 3
      2393787.78     13606127.69      2395104.46       13605730.
      2395330.07     13605466.79
#Sta/Elev= 30
  3684.2  377.62  3733.5  377.03  3879.1  370.41  3983.2  367.17  3994.7  367.93
  4013.2  366.21  4198.4  362.21  4366.7  361.46  4391.6  360.47  4412.5  356.33
  4437.9  359.42  4476.4  358.66  4607.9  359.73  4684.3  361.73    4705  361.52
  4725.9  359.11  4854.3  361.41  4976.6  361.25  4986.2  360.85  4991.4  359.28
  4991.6  356.05  4992.1  355.55  5003.4  356.05    5008  358.78  5029.6  364.38
  5073.2  365.92  5137.8  367.73  5203.8  369.06  5360.2  371.51  5406.3  372.04
#Mann= 10 ,-1 , 0
  3684.2     .07       0  4013.2     .12       0  4198.4     .07       0
  4476.4      .1       0  4991.6     .05       0  5003.4      .1       0
  5073.2     .07       0  5137.8      .1       0  5203.8    .035       0
  5360.2     .07       0
Bank Sta=4991.6,5003.4
XS Rating Curve= 0 ,0
Exp/Cntr=0.3,0.1

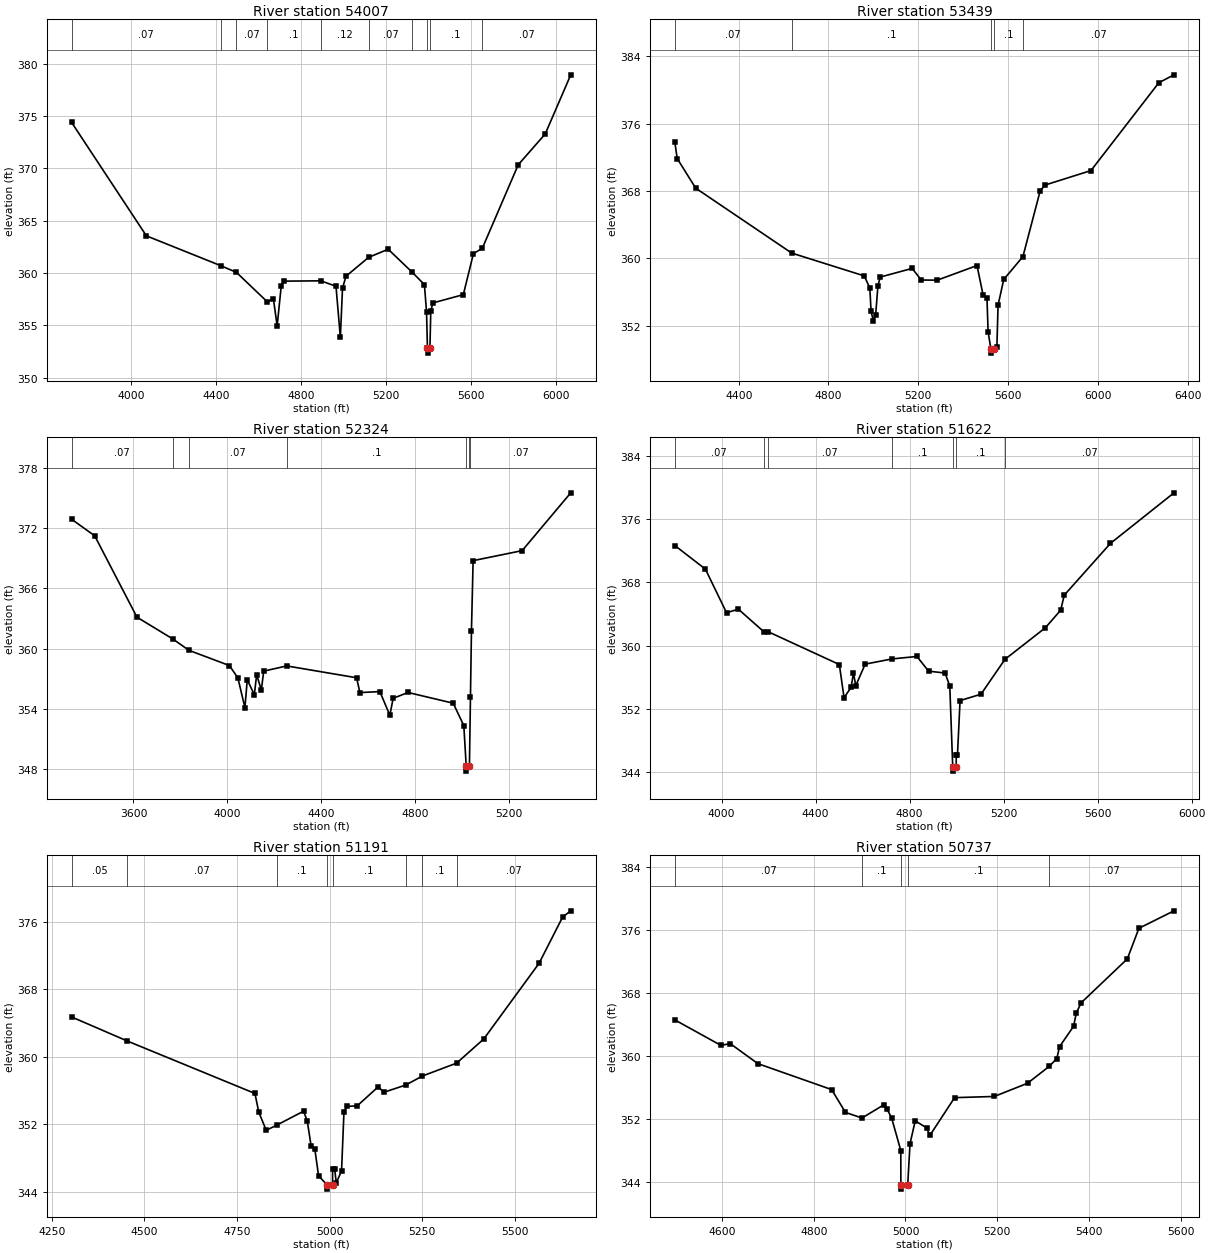
Type RM Length L Ch R = 1 ,54007   ,568,568,568
BEGIN DESCRIPTION:
MOUND CREEK 75.0
END DESCRIPTION:
XS GIS Cut Line= 3
       2393922.1     13606369.54       2395346.3     13606030.96
      2396231.52     13606122.16
#Sta/Elev= 30
  3718.1  374.39  4070.6  363.55  4422.4  360.69  4495.2  360.06  4641.5  357.23
  4669.6  357.54  4687.3  354.94  4706.6  358.76  4718.1  359.22  4893.7  359.25
  4964.8  358.73  4985.4  353.85  4995.6  358.55  5012.1  359.69  5118.3  361.49
  5210.8  362.27  5323.8  360.08  5381.7  358.89  5391.8  356.29    5396  352.84
  5396.5  352.34  5407.8  352.84  5411.9  356.39    5422  357.14  5565.3  357.93
    5613  361.86  5654.6  362.35  5824.1  370.34  5951.5  373.29  6071.9  378.94
#Mann= 10 ,-1 , 0
  3718.1     .07       0  4422.4      .1       0  4495.2     .07       0
  4641.5      .1       0  4893.7     .12       0  5118.3     .07       0
  5323.8      .1       0    5396     .05       0  5407.8      .1       0
  5654.6     .07       0
Bank Sta=5396,5407.8
XS Rating Curve= 0 ,0
Exp/Cntr=0.3,0.1

Type RM Length L Ch R = 1 ,53439   ,1115,1115,1115
BEGIN DESCRIPTION:
MOUND CREEK 74.0
END DESCRIPTION:
XS GIS Cut Line= 3
      2394104.81     13606606.01      2395281.81     13606391.04
      2396286.81     13606176.06
#Sta/Elev= 30
  4115.5  373.81  4125.9  371.86  4208.4  368.34  4636.4  360.62  4959.4  357.91
  4984.3  356.48  4989.9  353.69  5000.1  352.56  5010.2  353.25  5020.4  356.72
  5030.6  357.77  5172.9   358.8  5213.6  357.42  5284.7   357.4  5461.9  359.14
  5489.1  355.64  5506.3  355.28  5511.4  351.27  5523.8  349.23  5524.3  348.73
  5536.2  349.23  5550.4  349.41  5555.8  354.43  5581.1  357.49  5666.5   360.2
  5743.4  368.01  5765.2  368.71  5969.7  370.43  6272.2  380.87  6339.7  381.81
#Mann= 5 ,-1 , 0
  4115.5     .07       0  4636.4      .1       0  5523.8     .05       0
  5536.2      .1       0  5666.5     .07       0
Bank Sta=5523.8,5536.2
XS Rating Curve= 0 ,0
Exp/Cntr=0.3,0.1

Type RM Length L Ch R = 1 ,52324   ,702,702,702
BEGIN DESCRIPTION:
B19641
END DESCRIPTION:
XS GIS Cut Line= 4
      2394146.73     13606783.36      2395232.37     13606794.11
      2395587.07      13606460.9      2396085.89     13606219.54
#Sta/Elev= 30
  3336.7   372.9    3435  371.25    3615  363.13  3767.9  360.95  3836.4  359.82
  4008.7   358.3    4045  357.07    4075  354.09    4085  356.89    4115  355.38
    4125  357.37    4145  355.86    4155  357.74  4253.1  358.26  4550.8  357.08
  4564.9   355.6  4649.9   355.7  4692.4  353.34  4706.6  355.03  4770.1  355.61
  4962.4  354.54  5007.6   352.3  5017.8  348.26  5018.3  347.76  5031.5  348.26
  5035.9  355.15  5040.1  361.73  5047.2  368.77  5256.1  369.77  5463.2  375.54
#Mann= 7 ,-1 , 0
  3336.7     .07       0  3767.9      .1       0  3836.4     .07       0
  4253.1      .1       0  5017.8     .05       0  5031.5      .1       0
  5035.9     .07       0
Bank Sta=5017.8,5031.5
XS Rating Curve= 0 ,0
Exp/Cntr=0.3,0.1

Type RM Length L Ch R = 1 ,51622   ,431,431,431
BEGIN DESCRIPTION:
MOUND CREEK 73.0
END DESCRIPTION:
XS GIS Cut Line= 3
      2394175.01       13606825.        2395375.       13606825.
      2396183.59      13607272.4
#Sta/Elev= 30
  3800.7  372.68  3930.7  369.69  4020.7  364.16  4070.7  364.62  4178.8  361.77
  4197.4  361.76  4500.7   357.6  4520.7   353.4  4550.7   354.7  4560.7  356.52
  4570.7  354.92  4610.7  357.65    4725  358.31  4830.7  358.62  4880.7  356.76
  4950.7  356.52  4970.7  354.86  4983.3  344.59  4983.8  344.09    4998  344.59
  4998.2  346.18  5003.5  346.18  5014.4  353.03  5103.5  353.84  5205.6  358.26
  5377.5  362.26  5442.7  364.49  5457.8  366.39  5654.6  372.96  5924.8  379.36
#Mann= 7 ,-1 , 0
  3800.7     .07       0  4178.8      .1       0  4197.4     .07       0
    4725      .1       0  4983.3     .05       0    4998      .1       0
  5205.6     .07       0
Bank Sta=4983.3,4998
XS Rating Curve= 0 ,0
Exp/Cntr=0.3,0.1

Type RM Length L Ch R = 1 ,51191   ,454,454,454
BEGIN DESCRIPTION:
MOUND CREEK 72.0
END DESCRIPTION:
XS GIS Cut Line= 3
      2394474.97       13607075.        2395175.       13607175.
      2395575.03     13607675.04
#Sta/Elev= 30
  4303.7   364.7  4453.9  361.85  4798.7  355.63  4808.8  353.44    4829  351.26
  4857.2  351.87    4930  353.53  4940.1  352.32  4950.2  349.41  4960.3  349.02
  4970.4  345.87  4993.4  344.79  4993.9  344.29  5008.1  344.79  5008.3  346.66
    5014  346.66    5018  345.04  5032.4  346.44  5038.9   353.4  5046.9  354.09
  5074.9  354.17  5131.7  356.43  5146.1  355.76  5205.7  356.63  5250.8   357.7
  5343.2  359.23  5416.6   362.1  5565.5  371.05  5629.5  376.56  5651.2  377.28
#Mann= 8 ,-1 , 0
  4303.7     .05       0  4453.9     .07       0  4857.2      .1       0
  4993.4     .05       0  5008.1      .1       0  5205.7     .07       0
  5250.8      .1       0  5343.2     .07       0
Bank Sta=4993.4,5008.1
XS Rating Curve= 0 ,0
Exp/Cntr=0.3,0.1

Type RM Length L Ch R = 1 ,50737   ,454,454,454
BEGIN DESCRIPTION:
MOUND CREEK 71.0
END DESCRIPTION:
XS GIS Cut Line= 3
        2394525.       13607475.        2395025.       13607525.
      2395574.97     13607724.99
#Sta/Elev= 30
  4497.4  364.57  4597.9  361.34    4618  361.57  4678.3  359.03  4839.1  355.74
  4869.2  352.85  4905.2  352.14  4952.2  353.79  4959.7  353.27  4969.7  352.17
  4989.8  348.01  4989.9  343.63  4990.4  343.13  5004.8  343.63  5009.9  348.89
  5021.2  351.78  5045.8   350.9  5053.1  349.93    5107  354.72  5193.4  354.87
  5265.9  356.54  5312.9  358.67  5329.8  359.67  5335.7  361.18  5366.3  363.76
  5372.3  365.46    5383  366.75  5483.4   372.3  5508.7  376.18  5585.1  378.39
#Mann= 5 ,-1 , 0
  4497.4     .07       0  4905.2      .1       0  4989.9     .05       0
  5004.8      .1       0  5312.9     .07       0
Bank Sta=4989.9,5004.8
XS Rating Curve= 0 ,0
Exp/Cntr=0.3,0.1

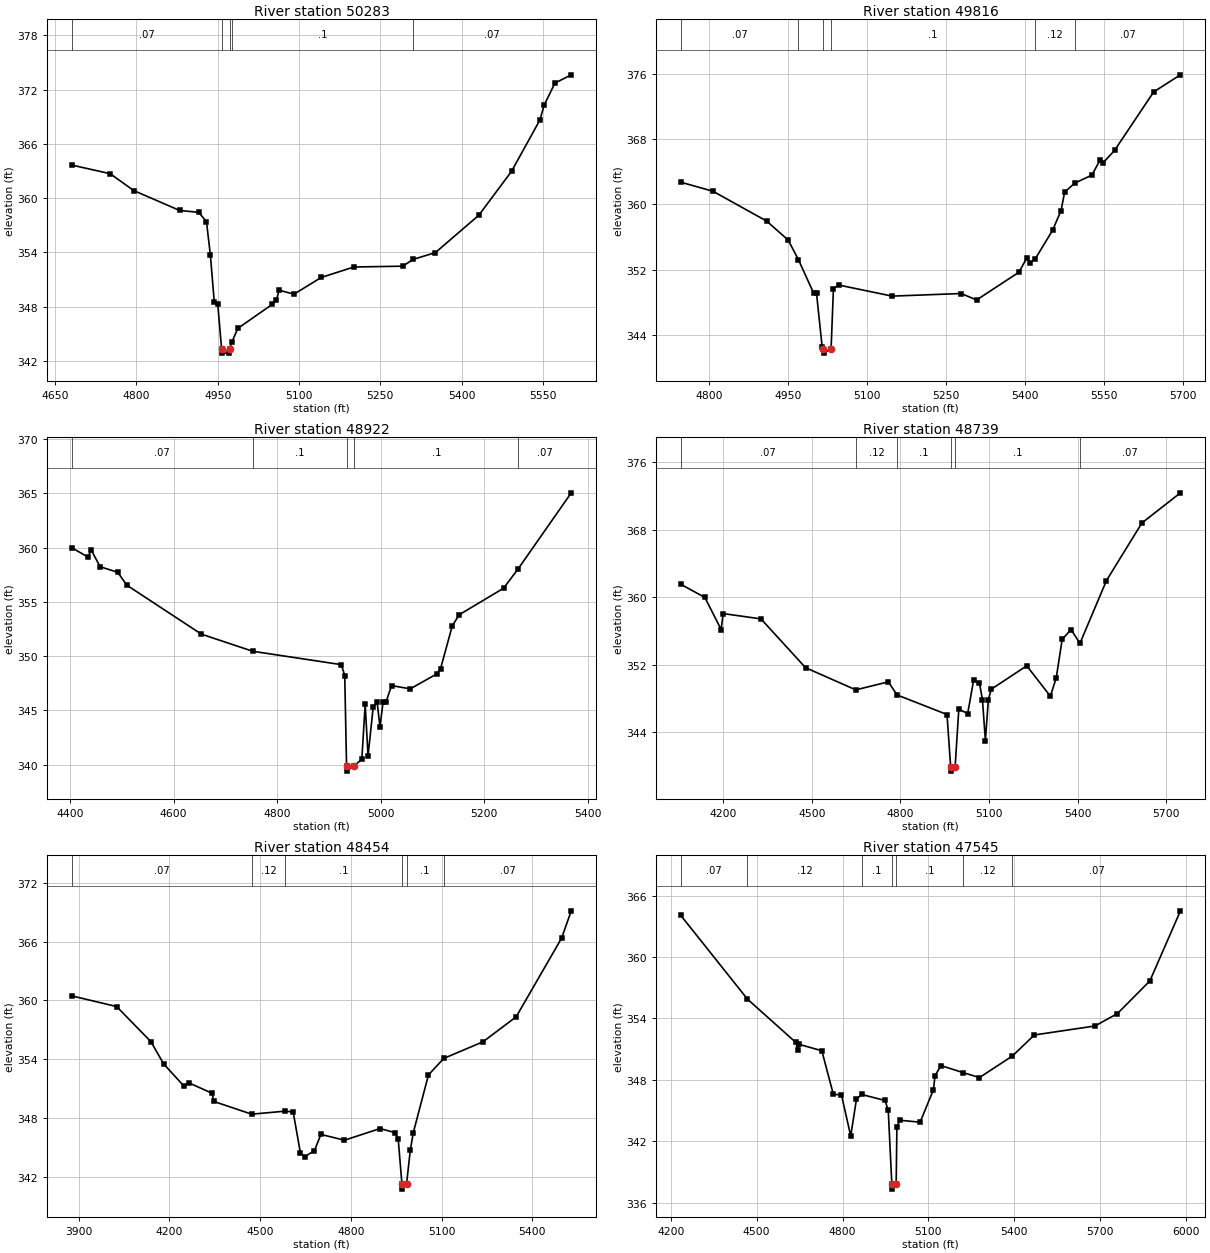
Type RM Length L Ch R = 1 ,50283   ,467,467,467
BEGIN DESCRIPTION:
MOUND CREEK 70.0
END DESCRIPTION:
XS GIS Cut Line= 3
        2394575.       13608075.        2394825.       13607875.
      2395424.96       13607925.
#Sta/Elev= 30
  4680.4  363.66  4751.6   362.7  4794.9  360.84  4879.7  358.64  4914.9  358.43
  4929.3   357.4  4936.5  353.69  4943.7  348.48  4950.1  348.31  4957.1  343.37
  4957.6  342.87  4971.5  342.87    4972  343.37    4976  344.06    4987   345.6
  5050.7  348.26  5058.3  348.73  5063.3  349.82  5090.9  349.39    5141  351.23
  5201.3  352.39  5291.6  352.48  5310.7  353.23  5351.8  353.98  5432.1  358.12
  5492.3  362.96  5544.9  368.66  5552.5  370.28  5572.5  372.72  5602.6  373.63
#Mann= 5 ,-1 , 0
  4680.4     .07       0  4957.1     .05       0    4972     .07       0
    4976      .1       0  5310.7     .07       0
Bank Sta=4957.1,4972
XS Rating Curve= 0 ,0
Exp/Cntr=0.3,0.1

Type RM Length L Ch R = 1 ,49816   ,894,894,894
BEGIN DESCRIPTION:
MOUND CREEK 69.0
END DESCRIPTION:
XS GIS Cut Line= 3
      2394624.96     13608274.99        2394875.       13608325.
      2395474.99       13607975.
#Sta/Elev= 30
  4745.9  362.72  4807.1  361.61  4909.1  357.95  4949.9  355.63  4969.4  353.23
  4998.3  349.12  5003.8  349.12  5014.5  342.53  5016.6  342.26  5017.1  341.76
  5031.5  342.26    5036  349.68    5046  350.11  5147.7  348.75  5278.7  349.07
  5308.1  348.28  5388.3  351.67    5404  353.48  5409.8   352.8  5419.1  353.27
  5452.8  356.86  5468.5  359.24  5475.5  361.52    5495  362.62  5527.2  363.59
  5542.9  365.46  5548.7  365.12  5570.2  366.61  5644.7   373.8  5695.5  375.89
#Mann= 6 ,-1 , 0
  4745.9     .07       0  4969.4      .1       0  5016.6     .05       0
  5031.5      .1       0  5419.1     .12       0    5495     .07       0
Bank Sta=5016.6,5031.5
XS Rating Curve= 0 ,0
Exp/Cntr=0.3,0.1

Type RM Length L Ch R = 1 ,48922   ,183,183,183
BEGIN DESCRIPTION:
MOUND CREEK 68.0
END DESCRIPTION:
XS GIS Cut Line= 3
      2394674.96     13608424.98        2395225.       13608675.
      2395524.96     13608475.03
#Sta/Elev= 30
  4403.2  359.99  4435.1  359.11  4440.6  359.81  4458.2  358.23  4492.2  357.72
  4509.8  356.53  4653.7  352.02  4753.1  350.44  4923.9  349.21  4930.5  348.21
    4934   339.9  4934.5   339.4    4949   339.9  4963.5   340.5    4970  345.55
  4975.5  340.79  4985.4  345.28  4993.1  345.75  4998.6  343.47  5004.6   345.8
  5010.4   345.8  5020.9  347.28    5057  346.98    5108  348.35  5115.6  348.85
  5138.1  352.78  5151.6  353.81  5237.2  356.25  5265.7  358.06  5367.9  365.04
#Mann= 5 ,-1 , 0
  4403.2     .07       0  4753.1      .1       0    4934     .05       0
    4949      .1       0  5265.7     .07       0
Bank Sta=4934,4949
XS Rating Curve= 0 ,0
Exp/Cntr=0.3,0.1

Type RM Length L Ch R = 1 ,48739   ,285,285,285
BEGIN DESCRIPTION:
B19640
END DESCRIPTION:
XS GIS Cut Line= 3
      2394420.86     13608562.26      2395103.39     13608820.22
      2396065.43     13608814.84
#Sta/Elev= 30
  4056.5  361.51    4138  359.95    4193  356.15  4199.9  358.04  4327.9  357.41
  4478.8  351.63  4648.9     349  4759.2  349.95  4788.5   348.4  4957.8  346.08
  4970.2  339.87  4970.7  339.37  4985.3  339.87  4997.8  346.73  5027.8  346.18
  5047.8  350.12  5067.8  349.79  5077.8  347.85  5087.8  342.97  5097.8  347.85
  5107.8  349.08  5227.8  351.85  5307.8  348.25  5327.8  350.44  5347.8  354.99
  5377.8  356.15  5407.9  354.51  5497.8  361.96  5617.8  368.78  5748.2  372.35
#Mann= 6 ,-1 , 0
  4056.5     .07       0  4648.9     .12       0  4788.5      .1       0
  4970.2     .05       0  4985.3      .1       0  5407.9     .07       0
Bank Sta=4970.2,4985.3
XS Rating Curve= 0 ,0
Exp/Cntr=0.3,0.1

Type RM Length L Ch R = 1 ,48454   ,909,909,909
BEGIN DESCRIPTION:
B19639
END DESCRIPTION:
XS GIS Cut Line= 3
       2394361.7     13608734.22      2395194.75     13609072.81
       2395947.1     13609067.44
#Sta/Elev= 30
  3877.1  360.47  4025.8  359.38  4139.7  355.77  4181.1  353.52  4247.7  351.27
  4264.1  351.59  4341.7  350.51  4347.1  349.68  4472.1  348.38    4584  348.69
  4609.4   348.6  4633.5  344.39  4647.1  344.04  4679.5  344.64    4701  346.31
    4779  345.72  4896.6  346.91  4946.6  346.49  4956.6  345.85    4969  341.22
  4969.5  340.72  4984.1  341.22  4996.6   344.7  5006.6   346.5  5056.6  352.39
  5107.3  354.08  5236.6  355.77  5346.6  358.33  5496.6  366.36  5528.7  369.16
#Mann= 6 ,-1 , 0
  3877.1     .07       0  4472.1     .12       0    4584      .1       0
    4969     .05       0  4984.1      .1       0  5107.3     .07       0
Bank Sta=4969,4984.1
XS Rating Curve= 0 ,0
Exp/Cntr=0.3,0.1

Type RM Length L Ch R = 1 ,47545   ,334,334,334
BEGIN DESCRIPTION:
B19638
END DESCRIPTION:
XS GIS Cut Line= 4
      2394216.62     13609196.42      2395033.52      13609303.9
      2395221.62     13609357.65      2395940.89     13609261.03
#Sta/Elev= 30
  4235.1  364.06    4468  355.88  4636.9  351.65  4643.9  350.87  4648.9  351.46
  4727.7  350.84    4768  346.57  4796.2  346.54  4828.6  342.51  4848.7  346.11
  4866.6  346.57  4948.5  345.98  4959.7  345.01  4972.2  337.82  4972.7  337.32
  4987.4  337.82  4989.9  343.38    5000  344.05    5071  343.86  5117.7  347.04
    5123   348.4  5143.8  349.39  5220.6  348.71  5278.3  348.22  5393.6  350.33
    5470  352.38  5681.9  353.26  5760.2  354.47  5873.6  357.66  5980.4  364.51
#Mann= 7 ,-1 , 0
  4235.1     .07       0    4468     .12       0  4866.6      .1       0
  4972.2     .05       0  4987.4      .1       0  5220.6     .12       0
  5393.6     .07       0
Bank Sta=4972.2,4987.4
XS Rating Curve= 0 ,0
Exp/Cntr=0.3,0.1

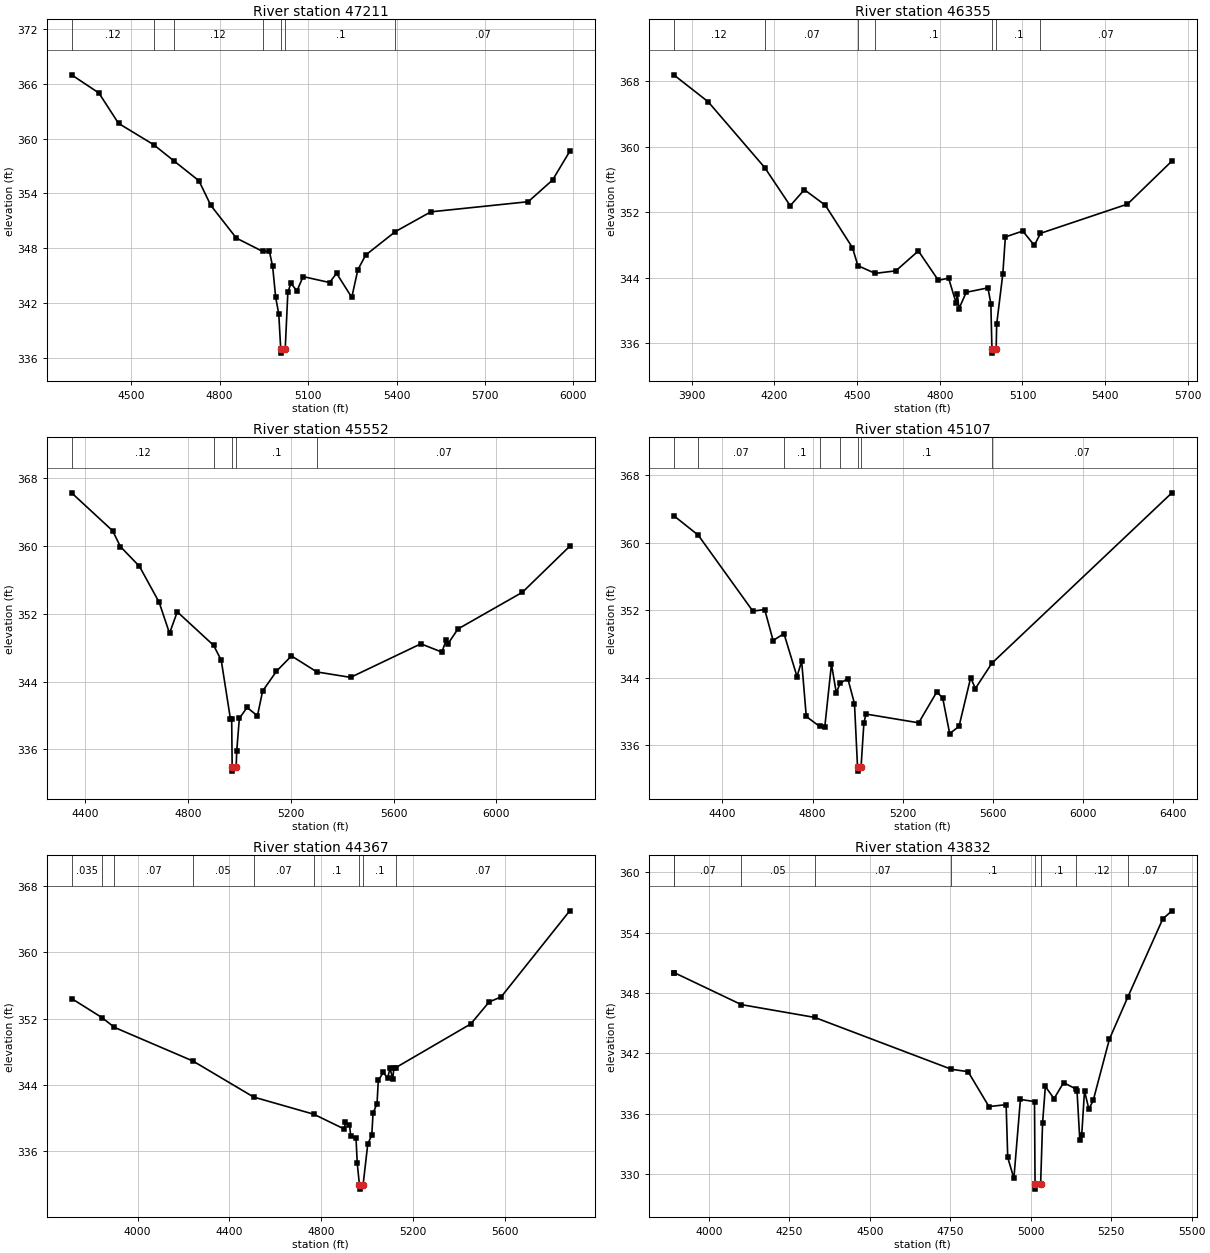
Type RM Length L Ch R = 1 ,47211   ,856,856,856
BEGIN DESCRIPTION:
B19637
END DESCRIPTION:
XS GIS Cut Line= 3
      2394270.36     13609862.83      2394705.69     13609669.36
      2395881.38     13609368.72
#Sta/Elev= 30
  4297.7     367  4390.3  365.01  4456.9  361.68  4575.7  359.35  4645.1  357.56
  4729.6  355.39  4770.2  352.68  4856.7   349.1  4945.4  347.65  4968.8  347.64
  4979.8  345.99  4990.1  342.59  5000.5  340.81  5007.1  336.99  5007.6  336.49
  5022.5  336.99  5031.4  343.18  5041.7  344.13  5062.4  343.32    5083  344.88
  5172.9  344.23  5196.6  345.24  5248.2   342.6  5268.8  345.63  5295.4  347.24
    5396  349.81  5516.5  351.98  5846.8  353.09  5929.4  355.47  5987.6  358.61
#Mann= 7 ,-1 , 0
  4297.7     .12       0  4575.7     .07       0  4645.1     .12       0
  4945.4      .1       0  5007.1     .05       0  5022.5      .1       0
    5396     .07       0
Bank Sta=5007.1,5022.5
XS Rating Curve= 0 ,0
Exp/Cntr=0.3,0.1

Type RM Length L Ch R = 1 ,46355   ,803,803,803
BEGIN DESCRIPTION:
B19636
END DESCRIPTION:
XS GIS Cut Line= 3
      2394313.41     13610083.17      2395060.39      13609911.2
      2396049.22     13609588.75
#Sta/Elev= 30
  3835.4  368.78  3960.2  365.49  4165.4  357.45  4257.8  352.79  4309.1  354.75
  4385.2  352.85  4483.5  347.67  4503.3  345.47  4565.9  344.53  4640.8  344.84
  4722.5  347.27  4795.1  343.68  4832.2  343.95  4858.9  340.97  4864.2  341.96
  4869.7  340.21  4896.1  342.22  4974.9  342.76  4985.4  340.84  4989.3  335.29
  4989.8  334.79  5004.7  335.29  5006.5  338.31  5028.9  344.49    5038  348.98
  5101.1   349.7  5143.2  347.95  5165.3  349.42  5480.9  352.99    5642  358.25
#Mann= 7 ,-1 , 0
  3835.4     .12       0  4165.4     .07       0  4503.3     .12       0
  4565.9      .1       0  4989.3     .05       0  5004.7      .1       0
  5165.3     .07       0
Bank Sta=4989.3,5004.7
XS Rating Curve= 0 ,0
Exp/Cntr=0.3,0.1

Type RM Length L Ch R = 1 ,45552   ,445,445,445
BEGIN DESCRIPTION:
B19635
END DESCRIPTION:
XS GIS Cut Line= 3
      2394426.24     13610319.64      2395232.37     13610228.28
      2396311.29     13609900.85
#Sta/Elev= 30
  4347.1  366.26  4506.9  361.78  4537.1  359.92  4611.4  357.58    4688  353.34
  4728.3  349.69  4758.5  352.22  4900.1  348.26  4929.6  346.51  4965.2  339.61
  4970.2  339.63  4972.1  333.93  4972.6  333.43  4987.6  333.93  4989.9   335.8
    5000  339.65  5030.2  340.94  5070.5  339.95  5090.6  342.88  5144.5  345.21
  5202.9  347.02  5301.9  345.13    5433  344.49  5706.6  348.45  5788.2  347.47
  5805.3  348.91  5810.5  348.39  5850.9   350.2  6101.7  354.53  6285.9  359.96
#Mann= 5 ,-1 , 0
  4347.1     .12       0  4900.1      .1       0  4972.1     .05       0
  4987.6      .1       0  5301.9     .07       0
Bank Sta=4972.1,4987.6
XS Rating Curve= 0 ,0
Exp/Cntr=0.3,0.1

Type RM Length L Ch R = 1 ,45107   ,740,740,740
BEGIN DESCRIPTION:
B19634
END DESCRIPTION:
XS GIS Cut Line= 4
      2394523.01     13610448.64       2395162.5     13610599.11
      2395511.83     13610529.24      2396667.31     13610222.91
#Sta/Elev= 30
  4184.7   363.2  4293.3  360.89  4535.4  351.88  4588.1  352.06  4625.3  348.39
  4673.4  349.21  4731.2  344.12  4751.8  345.95  4772.3  339.38  4831.7   338.2
  4854.4  338.15    4884   345.6  4905.4  342.18    4922  343.31  4956.4  343.88
    4986  340.91  4999.5   333.4    5000   332.9  5015.2   333.4  5027.8  338.63
    5037  339.67  5270.7  338.63  5351.1   342.3  5377.1  341.58  5408.1  337.35
  5449.5  338.21  5501.2  343.99  5521.9   342.7  5595.2   345.7  6393.3  365.91
#Mann= 8 ,-1 , 0
  4184.7     .12       0  4293.3     .07       0  4673.4      .1       0
  4831.7     .12       0    4922      .1       0  4999.5     .05       0
  5015.2      .1       0  5595.2     .07       0
Bank Sta=4999.5,5015.2
XS Rating Curve= 0 ,0
Exp/Cntr=0.3,0.1

Type RM Length L Ch R = 1 ,44367   ,535,535,535
BEGIN DESCRIPTION:
B19633
END DESCRIPTION:
XS GIS Cut Line= 4
      2394716.45     13610900.07      2395699.93     13610857.08
      2396070.76      13610685.1      2396737.13     13610287.42
#Sta/Elev= 30
  3712.4  354.43  3845.1  352.12  3899.3  350.94  4240.9  346.88  4505.2  342.53
  4767.7  340.45  4899.6  338.67  4905.1  339.47  4922.5  339.15    4928  337.85
  4950.9   337.6  4956.4  334.51  4965.9  331.91  4966.4  331.41  4981.7  331.91
  5002.2  336.87  5019.6  337.92  5025.1  340.58  5042.5  341.75    5048  344.55
  5070.2  345.51  5088.2   344.8  5099.3  346.02  5110.6  344.68  5115.9  346.02
  5123.9  346.08  5450.7  351.36  5530.5  354.01    5583  354.63  5881.6  365.02
#Mann= 9 ,-1 , 0
  3712.4    .035       0  3845.1     .05       0  3899.3     .07       0
  4240.9     .05       0  4505.2     .07       0  4767.7      .1       0
  4965.9     .05       0  4981.7      .1       0  5123.9     .07       0
Bank Sta=4965.9,4981.7
XS Rating Curve= 0 ,0
Exp/Cntr=0.3,0.1

Type RM Length L Ch R = 1 ,43832   ,466,466,466
BEGIN DESCRIPTION:
MOUND CREEK 63.0
END DESCRIPTION:
XS GIS Cut Line= 3
      2394974.95     13610924.99        2396075.       13611125.
        2396425.       13611375.
#Sta/Elev= 30
  3890.4  350.01    3892  350.01  4100.5  346.83  4328.2  345.56  4753.3   340.4
  4805.2  340.16    4870  336.69  4923.4  336.88  4928.4  331.63  4947.5  329.55
  4967.8   337.4  5011.6  337.19  5013.3  328.98  5013.8  328.48  5030.6  328.98
  5036.7  335.07  5045.3  338.69  5072.4  337.48  5101.9  339.07  5140.6  338.44
  5143.7  338.26  5152.3  333.39  5158.4   333.9    5167  338.26  5180.5  336.44
    5194   337.3  5244.4   343.4  5301.1  347.55  5410.3  355.36  5438.6  356.16
#Mann= 9 ,-1 , 0
  3890.4     .05       0    3892     .07       0  4100.5     .05       0
  4328.2     .07       0  4753.3      .1       0  5013.3     .05       0
  5030.6      .1       0  5140.6     .12       0  5301.1     .07       0
Bank Sta=5013.3,5030.6
XS Rating Curve= 0 ,0
Exp/Cntr=0.3,0.1

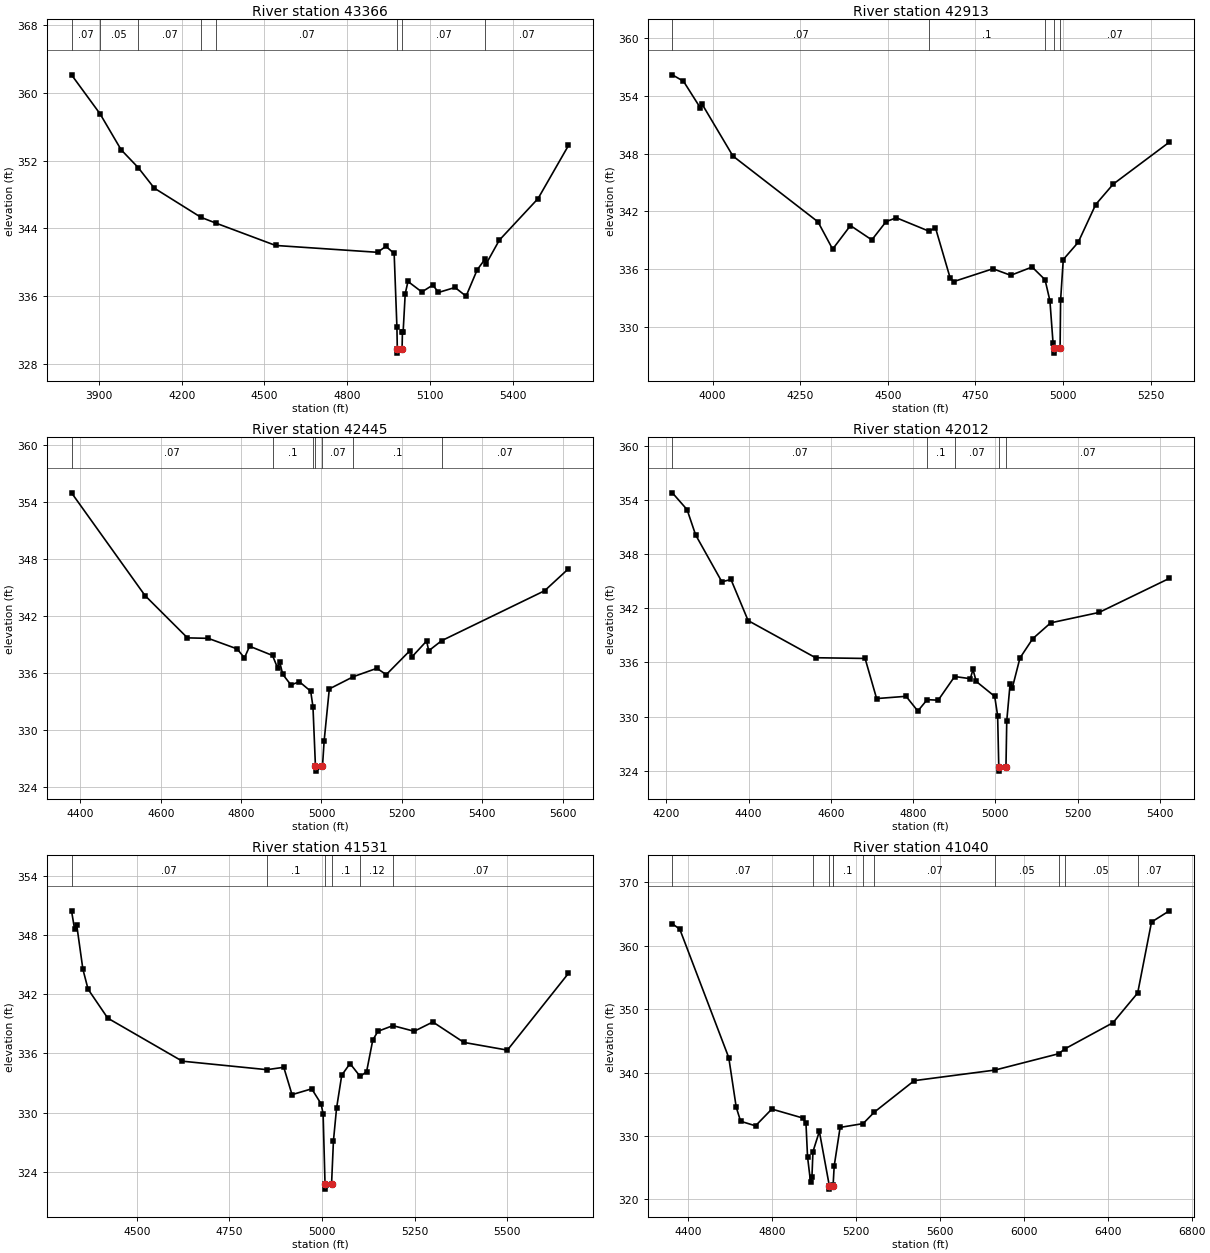
Type RM Length L Ch R = 1 ,43366   ,453,453,453
BEGIN DESCRIPTION:
MOUND CREEK 62.0
END DESCRIPTION:
XS GIS Cut Line= 3
      2394574.98       13611425.        2395775.       13611425.
        2396375.       13611475.
#Sta/Elev= 30
  3800.5  362.13  3903.9  357.53  3980.5  353.28  4042.3  351.18  4100.5  348.76
  4269.9  345.31  4325.4  344.61  4540.5  341.99  4910.5  341.18  4940.5  341.89
  4970.5  341.04  4980.5  332.35  4981.9  329.78  4982.4  329.28  4999.2  329.78
  5000.5  331.77    5003  331.77  5010.6  336.29  5020.6  337.74  5070.8   336.5
  5110.9  337.32    5131  336.44  5191.2  337.03  5231.3     336  5271.5  339.11
  5299.3  340.34  5304.1  339.82  5351.7  342.61  5492.2  347.52  5602.6  353.79
#Mann= 8 ,-1 , 0
  3800.5     .07       0  3903.9     .05       0  4042.3     .07       0
  4269.9     .05       0  4325.4     .07       0  4981.9     .05       0
  4999.2     .07       0  5299.3     .07       0
Bank Sta=4981.9,4999.2
XS Rating Curve= 0 ,0
Exp/Cntr=0.3,0.1

Type RM Length L Ch R = 1 ,42913   ,468,468,468
BEGIN DESCRIPTION:
MOUND CREEK 61.0
END DESCRIPTION:
XS GIS Cut Line= 3
      2394824.98       13611625.        2395925.       13611825.
      2396225.04       13611825.
#Sta/Elev= 30
  3885.4  356.18  3917.2  355.51  3965.5  352.73  3970.5  353.12  4058.2  347.74
  4300.9   340.9  4342.8  338.06  4393.6  340.51  4454.6  339.02  4495.3  340.92
  4524.5  341.32  4617.5  339.93  4636.3  340.27  4678.2  335.05  4688.4  334.69
  4800.2  336.02    4851  335.34    4912   336.2  4948.9  334.88  4962.8  332.69
  4971.7  328.32  4974.4  327.75  4974.9  327.25  4991.8  327.75  4993.3  332.76
  5000.9  336.98  5043.5  338.77  5093.5   342.7  5143.5  344.82  5303.5  349.18
#Mann= 5 ,-1 , 0
  3885.4     .07       0  4617.5      .1       0  4948.9     .07       0
  4974.4     .05       0  4991.8     .07       0
Bank Sta=4974.4,4991.8
XS Rating Curve= 0 ,0
Exp/Cntr=0.3,0.1

Type RM Length L Ch R = 1 ,42445   ,433,433,433
BEGIN DESCRIPTION:
MOUND CREEK 60.0
END DESCRIPTION:
XS GIS Cut Line= 3
      2394924.97     13611774.99        2395525.       13611925.
      2396125.03     13612075.01
#Sta/Elev= 30
  4377.8  354.98  4560.8  344.17  4666.4  339.72    4718  339.67  4790.1  338.56
  4808.2  337.61  4821.1  338.84  4878.1  337.87  4890.6  336.57  4895.8  337.21
  4903.5  335.89  4924.1  334.76  4944.8  335.11  4973.1  334.11  4978.8  332.48
    4985   326.2  4985.5   325.7  5002.5   326.2  5006.6  328.87  5019.5  334.35
  5079.5  335.64    5138  336.52  5161.2  335.85  5220.5  338.39  5225.6  337.74
  5261.7  339.39  5266.9  338.36    5299  339.42  5555.5  344.68  5614.8  346.99
#Mann= 7 ,-1 , 0
  4377.8     .07       0  4878.1      .1       0  4978.8     .07       0
    4985     .05       0  5002.5     .07       0  5079.5      .1       0
    5299     .07       0
Bank Sta=4985,5002.5
XS Rating Curve= 0 ,0
Exp/Cntr=0.3,0.1

Type RM Length L Ch R = 1 ,42012   ,481,481,481
BEGIN DESCRIPTION:
MOUND CREEK 59.0
END DESCRIPTION:
XS GIS Cut Line= 3
      2394925.03     13611825.02        2395525.       13612325.
      2395925.01       13612475.
#Sta/Elev= 30
  4214.8  354.77  4250.6  352.91  4271.4  350.11  4335.2  344.92  4357.3  345.18
    4399  340.63    4563  336.52  4683.4  336.44  4711.4     332    4783  332.25
  4811.6  330.62  4834.3  331.88  4861.1  331.82  4901.1  334.44  4939.2   334.2
  4945.7  335.22  4953.5   333.9  4998.5  332.24  5005.6  330.12  5008.4  324.47
  5008.9  323.97  5025.9  324.47  5027.8  329.54  5035.8  333.56  5041.2  333.16
  5059.9  336.49    5091  338.63  5134.6  340.38  5252.1  341.53    5423   345.3
#Mann= 5 ,-1 , 0
  4214.8     .07       0  4834.3      .1       0  4901.1     .07       0
  5008.4     .05       0  5025.9     .07       0
Bank Sta=5008.4,5025.9
XS Rating Curve= 0 ,0
Exp/Cntr=0.3,0.1

Type RM Length L Ch R = 1 ,41531   ,491,491,491
BEGIN DESCRIPTION:
MOUND CREEK 58.0
END DESCRIPTION:
XS GIS Cut Line= 3
      2394875.01     13611925.02        2395175.       13612525.
      2395774.99     13612824.99
#Sta/Elev= 30
  4323.5  350.44  4331.9  348.56  4337.4  349.04  4354.2  344.53  4368.2   342.5
  4421.3  339.57  4622.5  335.21    4851  334.35  4896.5  334.59  4918.8  331.82
  4971.9  332.41  4997.1   330.9  5002.7  329.89  5007.9  322.75  5008.4  322.25
  5025.5  322.75  5030.6  327.14    5039  330.44    5053  333.79  5075.4  334.97
  5102.8  333.66  5120.1  334.15  5136.8  337.35  5150.8  338.24  5191.1  338.81
  5248.6  338.24    5299  339.18  5382.8  337.11  5500.2  336.33  5665.1  344.11
#Mann= 6 ,-1 , 0
  4323.5     .07       0    4851      .1       0  5007.9     .05       0
  5025.5      .1       0  5102.8     .12       0  5191.1     .07       0
Bank Sta=5007.9,5025.5
XS Rating Curve= 0 ,0
Exp/Cntr=0.3,0.1

Type RM Length L Ch R = 1 ,41040   ,456,456,456
BEGIN DESCRIPTION:
MOUND CREEK 57.0
END DESCRIPTION:
XS GIS Cut Line= 3
      2394224.98     13612174.98        2394725.       13612625.
      2395925.03     13613825.03
#Sta/Elev= 30
  4323.6  363.45  4359.1  362.59  4592.7  342.34  4628.2  334.53  4649.1  332.32
  4720.1   331.6  4797.9  334.24  4946.6  332.82  4960.8     332  4968.3   326.7
  4982.5  322.78  4989.2  323.48    4994  327.52  5024.6  330.72  5072.3  322.12
  5072.8  321.62    5090  322.12  5090.3   322.3  5095.3  325.26  5123.6  331.35
  5233.2  331.95  5286.8  333.76  5477.1  338.72  5862.2  340.39  6165.4  342.96
  6195.1  343.72  6424.7  347.85  6542.6  352.54  6608.5  363.72  6693.4  365.49
#Mann= 11 ,-1 , 0
  4323.6     .07       0    4994     .12       0  5072.3     .05       0
    5090     .12       0  5090.3      .1       0  5233.2     .12       0
  5286.8     .07       0  5862.2     .05       0  6165.4     .07       0
  6195.1     .05       0  6542.6     .07       0
Bank Sta=5072.3,5090
XS Rating Curve= 0 ,0
Exp/Cntr=0.3,0.1