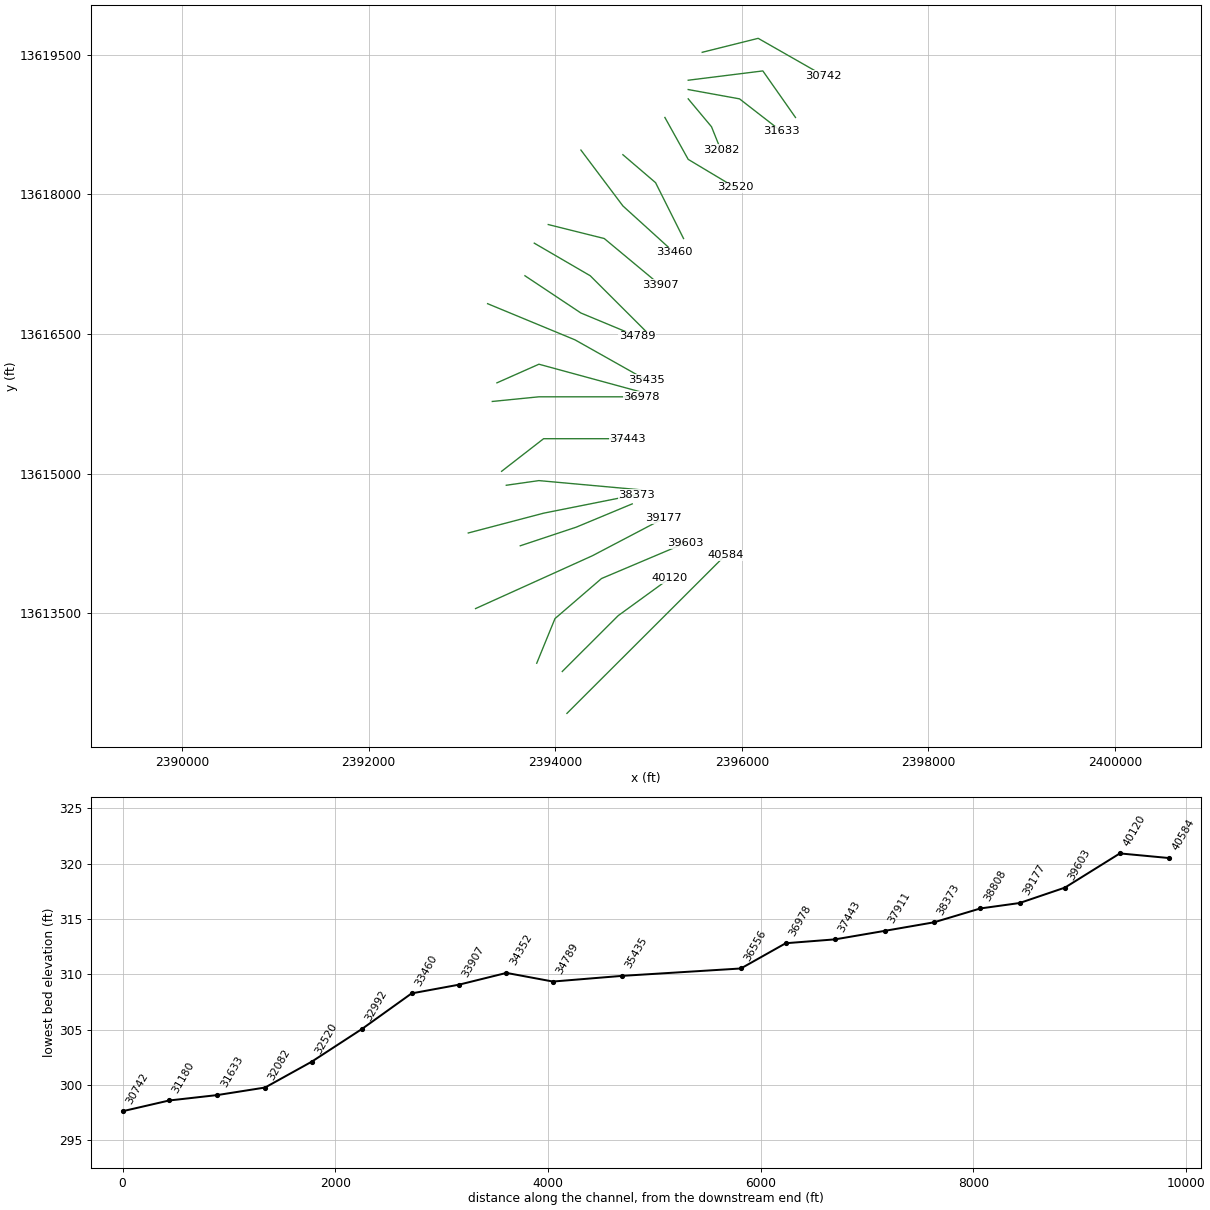
HEC-RAS study MOUND CREEK.prj: MOUND CREEK Base Level Engineering

--- MOUND CREEK.g01 (geometry) --- (continued)

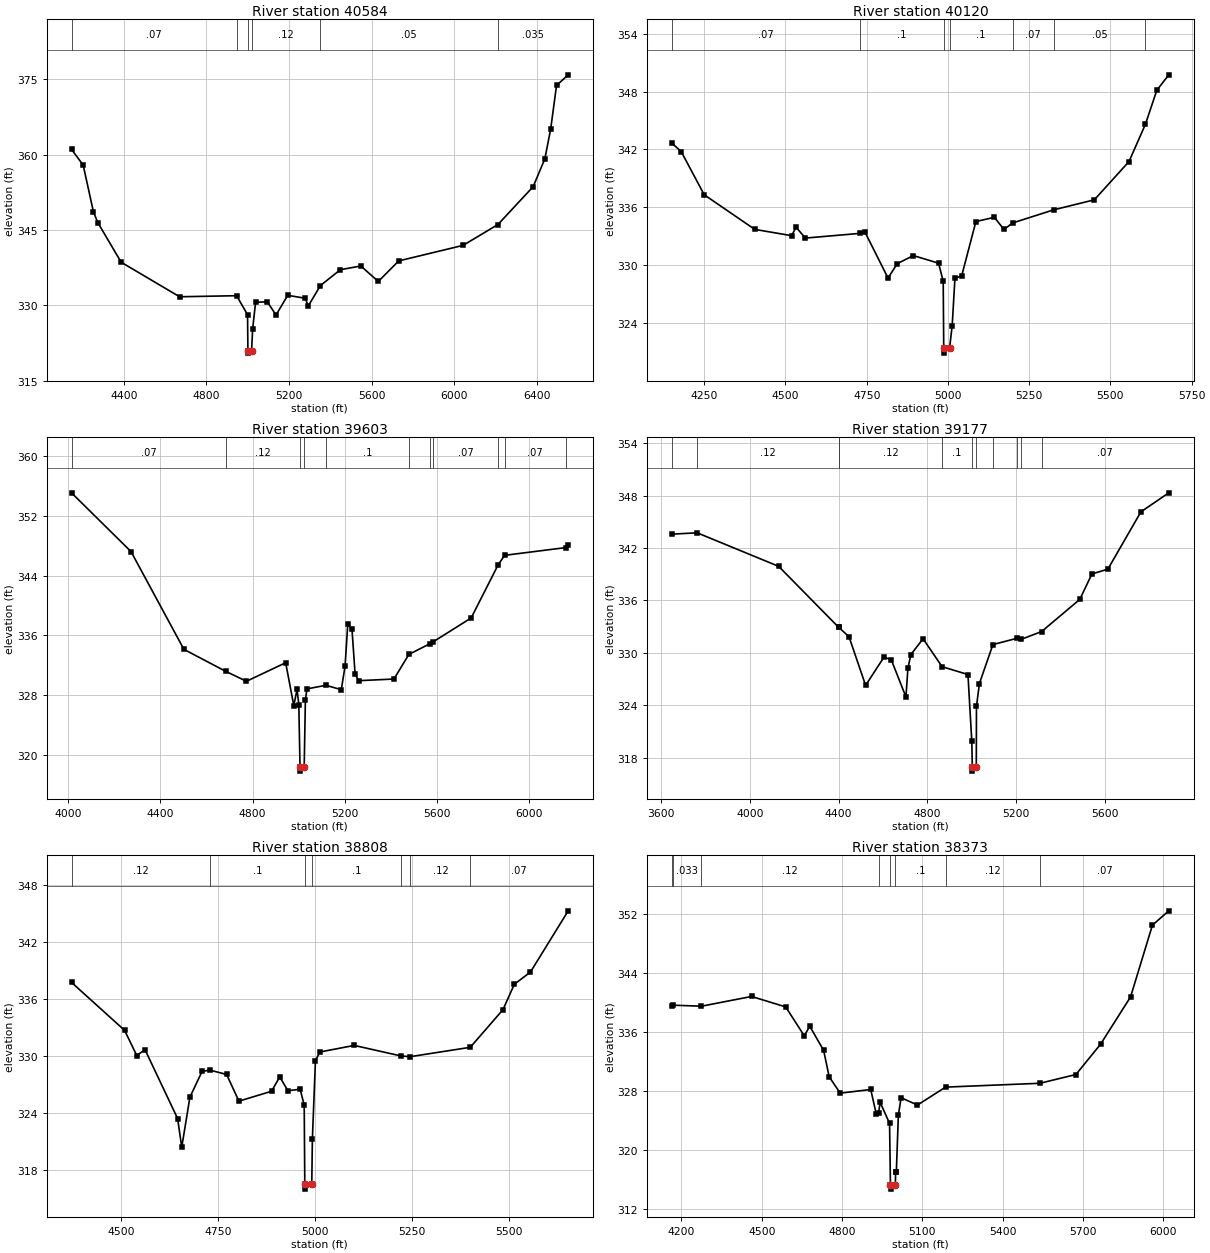
Type RM Length L Ch R = 1 ,40584   ,464,464,464
BEGIN DESCRIPTION:
MOUND CREEK 56.0
END DESCRIPTION:
XS GIS Cut Line= 3
      2394124.97     13612424.97        2394725.       13613025.
        2395825.       13614125.
#Sta/Elev= 30
  4146.7  361.07  4203.3  357.92  4252.8  348.63    4274  346.48  4387.2  338.59
    4670  331.72  4945.8  331.93  4998.8  328.15  5000.5     321    5001   320.5
  5018.3     321  5023.6  325.37  5037.7  330.63  5094.3  330.71  5136.7  328.09
  5193.3  332.01  5278.1  331.42  5292.3  329.86  5351.5  333.95  5447.8   337.1
  5546.8  337.85  5631.7  334.77  5730.7  338.86  6041.8  341.95  6210.7   346.1
  6381.2  353.64  6437.8  359.18  6466.1  365.13  6494.3  373.78  6550.9   375.9
#Mann= 6 ,-1 , 0
  4146.7     .07       0  4945.8     .12       0  5000.5     .05       0
  5018.3     .12       0  5351.5     .05       0  6210.7    .035       0
Bank Sta=5000.5,5018.3
XS Rating Curve= 0 ,0
Exp/Cntr=0.3,0.1

Type RM Length L Ch R = 1 ,40120   ,517,517,517
BEGIN DESCRIPTION:
MOUND CREEK 55.0
END DESCRIPTION:
XS GIS Cut Line= 3
      2394075.02     13612875.02        2394675.       13613475.
      2395225.03     13613875.02
#Sta/Elev= 30
    4151  342.64  4179.2  341.78    4250  337.31  4405.5  333.73  4518.7  333.08
  4532.8  333.95  4561.1  332.83  4730.4  333.32  4744.9  333.43  4815.6  328.69
  4843.9  330.18  4893.4  331.02  4971.2  330.23  4985.4  328.35    4987  321.42
  4987.5  320.92  5004.9  321.42    5013  323.76  5021.5  328.66  5042.4  328.94
    5086  334.54  5142.8  334.98  5172.2  333.73  5199.5   334.4  5324.9  335.75
  5450.4  336.79  5557.1  340.75  5607.4  344.59  5642.9  348.14  5679.6  349.73
#Mann= 7 ,-1 , 0
    4151     .07       0  4730.4      .1       0    4987     .05       0
  5004.9      .1       0  5199.5     .07       0  5324.9     .05       0
  5607.4    .035       0
Bank Sta=4987,5004.9
XS Rating Curve= 0 ,0
Exp/Cntr=0.3,0.1

Type RM Length L Ch R = 1 ,39603   ,426,426,426
BEGIN DESCRIPTION:
B19632
END DESCRIPTION:
XS GIS Cut Line= 4
      2393801.39     13612963.62      2393997.03     13613442.96
      2394495.94     13613873.38      2395395.97     13614254.92
#Sta/Elev= 30
  4014.9  355.06    4273   347.2  4502.4  334.12  4683.6  331.18  4773.7  329.85
  4943.7  332.33    4979  326.59  4993.1  328.77  5000.7  326.72    5006  318.33
  5006.5  317.83    5024  318.33  5029.2  327.28  5035.8  328.83  5118.1  329.31
    5185  328.73  5201.4  331.91  5213.1  337.54  5231.3  336.82  5244.8  330.82
  5260.4  329.93  5413.3  330.15    5478  333.44  5567.7  334.85  5580.9  335.08
  5748.2  338.32  5865.9  345.47  5893.6   346.7  6157.6  347.73  6169.1  348.03
#Mann= 11 ,-1 , 0
  4014.9     .07       0  4683.6     .12       0    5006     .05       0
    5024     .12       0  5118.1      .1       0    5478     .07       0
  5567.7    .035       0  5580.9     .07       0  5865.9     .12       0
  5893.6     .07       0  6157.6     .12       0
Bank Sta=5006,5024
XS Rating Curve= 0 ,0
Exp/Cntr=0.3,0.1

Type RM Length L Ch R = 1 ,39177   ,369,369,369
BEGIN DESCRIPTION:
MOUND CREEK 54.0
END DESCRIPTION:
XS GIS Cut Line= 3
      2393145.96     13613550.56      2394398.11     13614117.94
      2395160.59     13614518.73
#Sta/Elev= 30
  3650.2  343.58  3763.2  343.73  4130.1  339.89  4399.6  332.92  4401.1   332.9
  4446.8  331.82  4521.5  326.26  4604.3   329.5    4637  329.19  4703.1  324.93
  4711.8   328.2  4725.1  329.78    4780   331.6  4865.8   328.4  4982.2   327.5
  4999.5  319.84  5001.8  316.94  5002.3  316.44  5019.8  316.94  5020.5  323.85
  5033.8  326.47  5094.5  330.93    5204  331.66  5221.5  331.53  5313.5  332.42
  5485.5   336.1  5540.3  339.02  5612.1  339.57  5760.7  346.13  5886.3  348.31
#Mann= 11 ,-1 , 0
  3650.2     .07       0  3763.2     .12       0  4399.6     .07       0
  4401.1     .12       0  4865.8      .1       0  5001.8     .05       0
  5019.8      .1       0  5094.5     .12       0    5204     .07       0
  5221.5     .12       0  5313.5     .07       0
Bank Sta=5001.8,5019.8
XS Rating Curve= 0 ,0
Exp/Cntr=0.3,0.1

Type RM Length L Ch R = 1 ,38808   ,435,435,435
BEGIN DESCRIPTION:
MOUND CREEK 53.0
END DESCRIPTION:
XS GIS Cut Line= 3
      2393625.03     13614225.01        2394225.       13614425.
      2394824.97     13614674.99
#Sta/Elev= 30
  4371.7  337.73  4508.7  332.68  4540.3  330.02  4561.4  330.65  4645.7  323.38
  4656.3  320.36  4677.4  325.64    4709  328.37  4729.8  328.48  4772.2  328.03
  4803.9  325.22  4888.2  326.26  4909.3  327.78  4930.3  326.32    4962  326.47
  4972.5   324.8    4974  316.45  4974.5  315.95    4992  316.45  4993.6  321.23
  5001.5   329.5  5013.3   330.4  5101.6  331.09  5223.5  329.97  5246.9  329.91
  5401.2  330.89  5485.7  334.86  5514.9  337.53  5556.6  338.82  5654.1  345.27
#Mann= 7 ,-1 , 0
  4371.7     .12       0  4729.8      .1       0    4974     .05       0
    4992      .1       0  5223.5     .07       0  5246.9     .12       0
  5401.2     .07       0
Bank Sta=4974,4992
XS Rating Curve= 0 ,0
Exp/Cntr=0.3,0.1

Type RM Length L Ch R = 1 ,38373   ,462,462,462
BEGIN DESCRIPTION:
MOUND CREEK 52.0
END DESCRIPTION:
XS GIS Cut Line= 3
      2393067.75     13614362.52        2393875.       13614575.
      2394874.95     13614774.99
#Sta/Elev= 30
  4165.3  339.57  4166.9  339.64    4275   339.5  4462.3  340.82  4589.6   339.4
  4658.8  335.49  4679.5  336.77  4731.2  333.51  4751.9  329.92  4793.2  327.71
    4907  328.21  4927.7  324.88  4936.5  325.08  4942.1  326.47  4977.3  323.62
  4980.6   315.2  4981.1   314.7  4998.8   315.2    5000  317.05  5002.6  317.05
  5010.2  324.74  5020.4  327.09  5081.6   326.1  5186.3  328.53  5538.5  329.05
  5673.1  330.24  5764.9  334.34  5877.1  340.76  5958.7  350.49  6019.8  352.43
#Mann= 8 ,-1 , 0
  4165.3     .12       0  4166.9    .033       0    4275     .12       0
  4936.5      .1       0  4980.6     .05       0  4998.8      .1       0
  5186.3     .12       0  5538.5     .07       0
Bank Sta=4980.6,4998.8
XS Rating Curve= 0 ,0
Exp/Cntr=0.3,0.1

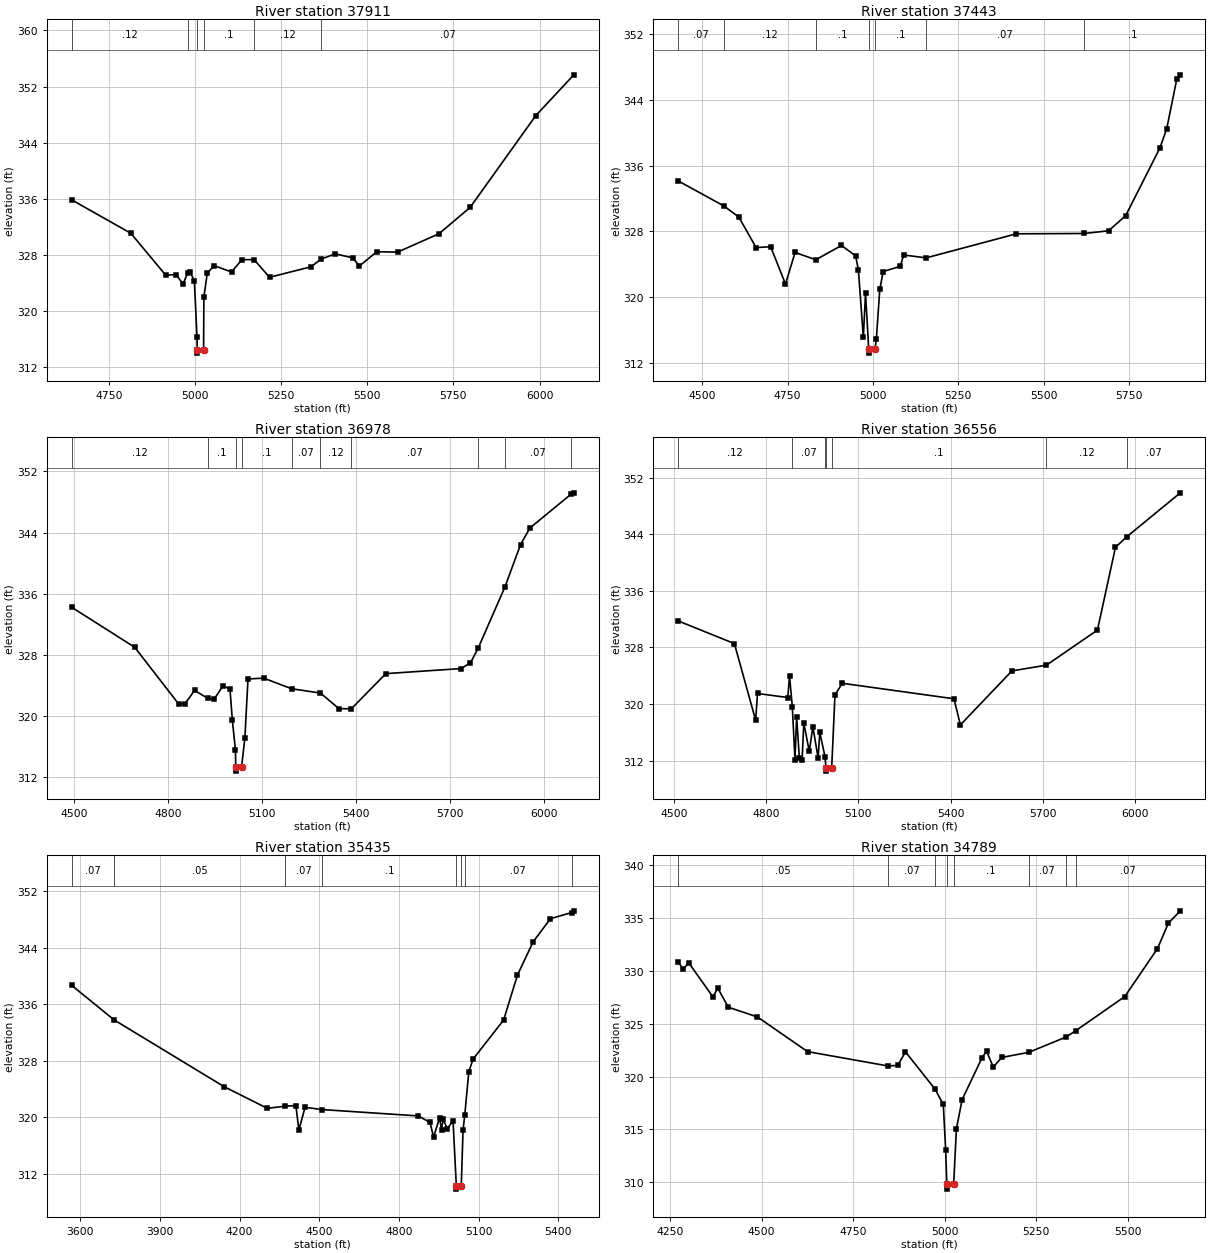
Type RM Length L Ch R = 1 ,37911   ,468,468,468
BEGIN DESCRIPTION:
MOUND CREEK 51.0
END DESCRIPTION:
XS GIS Cut Line= 3
      2393474.99       13614875.        2393825.       13614925.
        2394925.       13614825.
#Sta/Elev= 30
  4641.6  335.81  4813.3  331.04  4914.4  325.06  4944.7  325.15  4964.9  323.79
  4978.1  325.39  4985.1  325.58  4997.7   324.2  5005.2  316.28  5006.1  314.43
  5006.6  313.93  5024.4  314.43  5025.3  321.98  5035.3   325.4  5055.4  326.41
  5105.6  325.52  5135.7  327.28    5171  327.28  5216.1  324.76  5336.6  326.26
  5365.9  327.37  5406.9   328.1  5457.1  327.55  5477.1  326.37  5527.3  328.41
  5587.6  328.35  5708.1  330.98  5798.5  334.74  5989.2  347.85  6099.7  353.67
#Mann= 6 ,-1 , 0
  4641.6     .12       0  4978.1      .1       0  5006.1     .05       0
  5024.4      .1       0    5171     .12       0  5365.9     .07       0
Bank Sta=5006.1,5024.4
XS Rating Curve= 0 ,0
Exp/Cntr=0.3,0.1

Type RM Length L Ch R = 1 ,37443   ,465,465,465
BEGIN DESCRIPTION:
MOUND CREEK 50.0
END DESCRIPTION:
XS GIS Cut Line= 3
        2393425.       13615025.        2393875.       13615375.
      2394775.01       13615375.
#Sta/Elev= 30
  4429.9  334.13    4564  331.07  4607.3  329.73  4657.9  326.01  4700.5  326.12
  4743.9  321.57    4772  325.42  4832.7  324.53  4907.7  326.27  4949.3  325.01
  4957.5  323.25  4971.9  315.07  4978.3  320.49  4987.6  313.66  4988.1  313.16
  5006.1  313.66    5010  314.89    5020  320.91    5030   323.1    5080  323.73
    5090  325.11  5155.8  324.76    5420  327.69  5618.7  327.73    5690  328.06
    5740   329.9    5840  338.12    5860  340.45    5890  346.59    5900  347.05
#Mann= 7 ,-1 , 0
  4429.9     .07       0    4564     .12       0  4832.7      .1       0
  4987.6     .05       0  5006.1      .1       0  5155.8     .07       0
  5618.7      .1       0
Bank Sta=4987.6,5006.1
XS Rating Curve= 0 ,0
Exp/Cntr=0.3,0.1

Type RM Length L Ch R = 1 ,36978   ,422,422,422
BEGIN DESCRIPTION:
MOUND CREEK 49.0
END DESCRIPTION:
XS GIS Cut Line= 3
      2393324.95       13615775.        2393825.       13615825.
      2394924.96       13615825.
#Sta/Elev= 30
  4492.8  334.23  4693.8     329  4834.5  321.56  4854.6  321.65  4884.8  323.36
  4927.4  322.31  4947.6  322.23  4975.2  323.96  4997.8  323.55  5005.3  319.48
  5015.3  315.53  5016.1  313.31  5016.6  312.81  5034.6  313.31  5045.3  317.15
  5055.3  324.86  5105.3  324.97  5194.6  323.58  5286.5  323.02  5345.3  320.99
  5384.9  320.95  5495.3  325.56  5735.3  326.22  5765.3  326.97  5789.8  328.88
  5875.1  336.87  5925.3  342.44  5955.3  344.61  6087.5  349.06  6095.3   349.2
#Mann= 10 ,-1 , 0
  4492.8     .12       0  4927.4      .1       0  5016.1     .05       0
  5034.6      .1       0  5194.6     .07       0  5286.5     .12       0
  5384.9     .07       0  5789.8     .12       0  5875.1     .07       0
  6087.5     .05       0
Bank Sta=5016.1,5034.6
XS Rating Curve= 0 ,0
Exp/Cntr=0.3,0.1

Type RM Length L Ch R = 1 ,36556   ,1121,1121,1121
BEGIN DESCRIPTION:
MOUND CREEK 48.0
END DESCRIPTION:
XS GIS Cut Line= 3
      2393375.01     13615975.01        2393825.       13616175.
        2394925.       13615875.
#Sta/Elev= 30
  4514.3  331.75  4696.9  328.55    4766  317.72  4772.1   321.5  4870.6  320.93
  4876.1     324  4885.2  319.65  4893.9  312.16  4899.3  318.13  4908.2   312.4
  4917.1  312.12  4922.6  317.35  4940.4  313.31    4952  316.81  4969.1   312.4
  4974.6  316.01  4991.5  312.57  4994.6  311.03  4995.1  310.53  5013.3  311.03
    5024  321.34  5048.2  322.94    5411  320.75  5431.7  317.06  5599.3  324.69
  5711.5   325.5  5877.4  330.46  5936.1  342.16  5972.4  343.63  6146.9  349.85
#Mann= 7 ,-1 , 0
  4514.3     .12       0  4885.2     .07       0  4991.5      .1       0
  4994.6     .05       0  5013.3      .1       0  5711.5     .12       0
  5972.4     .07       0
Bank Sta=4994.6,5013.3
XS Rating Curve= 0 ,0
Exp/Cntr=0.3,0.1

Type RM Length L Ch R = 1 ,35435   ,646,646,646
BEGIN DESCRIPTION:
MOUND CREEK 47.0
END DESCRIPTION:
XS GIS Cut Line= 3
      2393274.96     13616825.02      2394212.25     13616436.38
      2394975.25     13616005.97
#Sta/Elev= 30
  3567.9  338.69  3727.4  333.81  4141.7  324.36  4304.1   321.3  4370.7  321.59
  4411.7  321.69  4423.2  318.22  4446.4  321.44  4511.2  321.12  4872.8  320.22
  4917.1  319.31  4930.2  317.22  4953.1  319.96  4960.4  318.17  4966.1  319.78
  4982.1  318.41  5003.7  319.53    5016  310.36  5016.5  309.86  5034.7  310.36
  5041.3  318.18  5047.9  320.37  5062.9  326.45  5078.9  328.25  5194.2   333.8
  5246.4  340.17  5305.6  344.88  5370.6  348.14  5450.6  349.01  5458.6  349.25
#Mann= 8 ,-1 , 0
  3567.9     .07       0  3727.4     .05       0  4370.7     .07       0
  4511.2      .1       0    5016     .05       0  5034.7      .1       0
  5047.9     .07       0  5450.6     .05       0
Bank Sta=5016,5034.7
XS Rating Curve= 0 ,0
Exp/Cntr=0.3,0.1

Type RM Length L Ch R = 1 ,34789   ,437,437,437
BEGIN DESCRIPTION:
MOUND CREEK 46.0
END DESCRIPTION:
XS GIS Cut Line= 3
      2393674.99       13617125.        2394275.       13616725.
      2394874.98     13616475.01
#Sta/Elev= 30
  4272.6  330.85  4286.1  330.15  4301.2  330.77  4367.3  327.54  4380.8  328.35
  4409.3  326.56  4488.9  325.64  4625.7  322.36  4844.4  321.01    4872  321.05
  4893.1  322.34  4973.9  318.81  4996.4  317.36  5002.9  313.07    5006  309.85
  5006.5  309.35  5024.8  309.85  5032.2  315.04  5047.9  317.82  5102.1  321.77
  5114.5  322.41  5132.9   320.9  5156.2  321.81  5229.6  322.29  5330.4  323.72
  5357.9  324.33  5492.1  327.57  5581.4  332.11  5611.2  334.52  5643.7  335.68
#Mann= 8 ,-1 , 0
  4272.6     .05       0  4844.4     .07       0  4973.9      .1       0
    5006     .05       0  5024.8      .1       0  5229.6     .07       0
  5330.4      .1       0  5357.9     .07       0
Bank Sta=5006,5024.8
XS Rating Curve= 0 ,0
Exp/Cntr=0.3,0.1

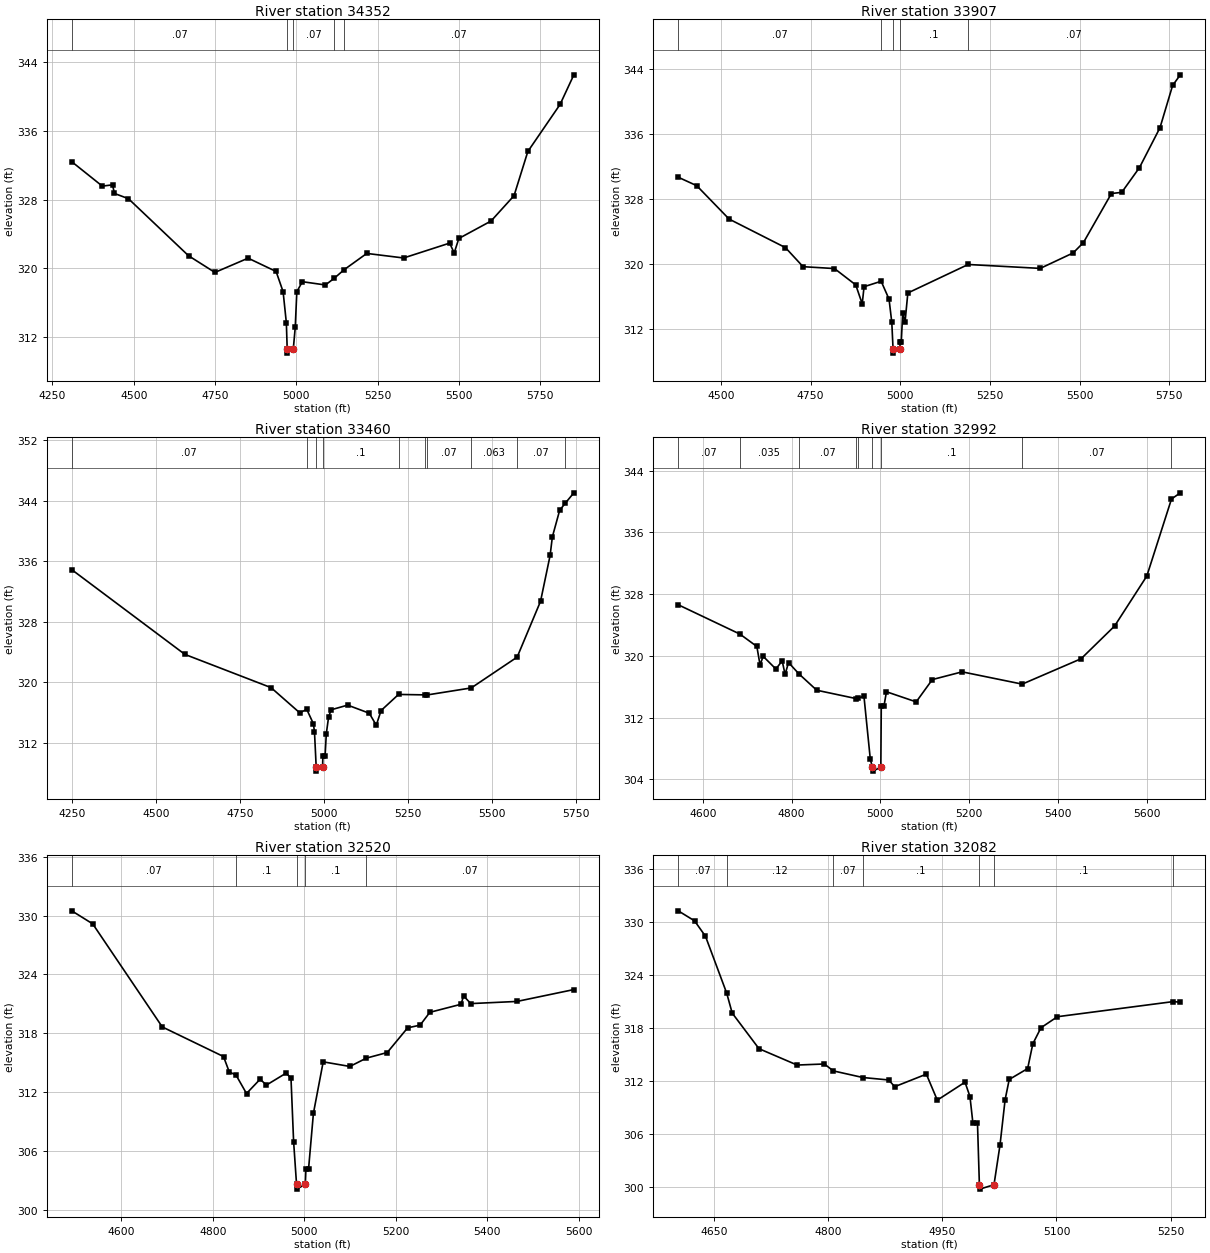
Type RM Length L Ch R = 1 ,34352   ,445,445,445
BEGIN DESCRIPTION:
MOUND CREEK 45.0
END DESCRIPTION:
XS GIS Cut Line= 3
        2393775.       13617475.        2394375.       13617125.
      2394974.97     13616525.03
#Sta/Elev= 30
  4309.6   332.4  4403.5  329.56  4434.9  329.71  4440.7  328.71  4483.7   328.1
  4668.5  321.46  4749.5  319.52  4851.6  321.18  4937.6  319.63  4959.1  317.28
  4969.1  313.66  4971.7  310.63  4972.2  310.13  4990.5  310.63  4996.4  313.12
  5001.3  317.28  5018.4  318.44  5089.1  318.06    5116  318.83  5146.5  319.83
  5216.3  321.73  5329.5   321.2  5470.9  322.93    5485  321.79  5499.2  323.47
  5598.2   325.5  5668.9  328.45  5711.3  333.59  5810.3  339.06  5852.7  342.51
#Mann= 5 ,-1 , 0
  4309.6     .07       0  4971.7     .05       0  4990.5     .07       0
    5116      .1       0  5146.5     .07       0
Bank Sta=4971.7,4990.5
XS Rating Curve= 0 ,0
Exp/Cntr=0.3,0.1

Type RM Length L Ch R = 1 ,33907   ,447,447,447
BEGIN DESCRIPTION:
MOUND CREEK 44.0
END DESCRIPTION:
XS GIS Cut Line= 3
      2393924.98     13617675.01        2394525.       13617525.
      2395124.99     13617025.01
#Sta/Elev= 30
  4381.1  330.68  4432.7  329.64  4522.9  325.54    4680  322.03    4729  319.69
  4816.6  319.46  4875.9  317.45  4893.9  315.13  4899.1  317.23  4946.7   317.9
  4968.7   315.7  4976.4  312.84  4979.9  309.57  4980.4  309.07  4998.7  309.57
  4999.6  310.47  5002.8  310.47  5006.8  314.01  5013.3  312.88  5021.1  316.46
  5189.2  319.96  5390.1  319.48  5481.9  321.38  5510.5  322.65  5588.6  328.68
  5617.3  328.82  5666.7  331.86    5724  336.77  5759.1  341.95  5780.6  343.26
#Mann= 5 ,-1 , 0
  4381.1     .07       0  4946.7      .1       0  4979.9     .05       0
  4998.7      .1       0  5189.2     .07       0
Bank Sta=4979.9,4998.7
XS Rating Curve= 0 ,0
Exp/Cntr=0.3,0.1

Type RM Length L Ch R = 1 ,33460   ,468,468,468
BEGIN DESCRIPTION:
MOUND CREEK 43.0
END DESCRIPTION:
XS GIS Cut Line= 3
      2394275.01     13618474.99        2394725.       13617875.
      2395275.01     13617374.99
#Sta/Elev= 30
  4249.6  334.89    4586   323.7  4842.3  319.31  4927.7  315.98  4948.5  316.44
  4968.3  314.53  4971.5  313.47  4976.6  308.78  4977.1  308.28  4995.5  308.78
  4996.5   310.3    5003   310.3  5006.7  313.24  5013.4  315.41  5020.9  316.38
  5070.2     317  5134.4  315.93  5155.3  314.34  5169.5  316.28  5221.5  318.41
  5301.2  318.35  5306.2  318.34  5437.8  319.27  5574.3  323.34  5643.9  330.72
  5672.3  336.77    5679  339.22  5700.7  342.73  5717.8  343.69  5742.9  345.04
#Mann= 10 ,-1 , 0
  4249.6     .07       0  4948.5      .1       0  4976.6     .05       0
  4995.5      .1       0  5221.5     .07       0  5301.2    .035       0
  5306.2     .07       0  5437.8    .063       0  5574.3     .07       0
  5717.8     .12       0
Bank Sta=4976.6,4995.5
XS Rating Curve= 0 ,0
Exp/Cntr=0.3,0.1

Type RM Length L Ch R = 1 ,32992   ,472,472,472
BEGIN DESCRIPTION:
MOUND CREEK 42.0
END DESCRIPTION:
XS GIS Cut Line= 3
      2394725.01     13618424.99        2395075.       13618125.
      2395375.01     13617524.99
#Sta/Elev= 30
  4544.3  326.61  4683.4  322.81  4721.5  321.21  4728.7  318.83  4735.8  319.93
  4764.4  318.29  4778.6  319.34  4785.2  317.58  4792.9  319.13  4816.3  317.66
  4856.5  315.54  4945.9  314.45  4949.2  314.54    4963  314.73  4977.3  306.59
    4982  305.56  4982.5  305.06    5001  305.56    5002  313.51  5008.1  313.51
  5013.7  315.34  5080.7  314.03  5117.1  316.92  5184.2  317.92  5319.7  316.33
  5452.5  319.62  5527.9  323.85  5600.6  330.33  5656.2  340.31  5676.1  341.11
#Mann= 9 ,-1 , 0
  4544.3     .07       0  4683.4    .035       0  4816.3     .07       0
  4945.9    .035       0  4949.2      .1       0    4982     .05       0
    5001      .1       0  5319.7     .07       0  5656.2     .12       0
Bank Sta=4982,5001
XS Rating Curve= 0 ,0
Exp/Cntr=0.3,0.1

Type RM Length L Ch R = 1 ,32520   ,438,438,438
BEGIN DESCRIPTION:
MOUND CREEK 41.0
END DESCRIPTION:
XS GIS Cut Line= 3
      2395174.98     13618825.04        2395425.       13618375.
      2395924.98     13618075.01
#Sta/Elev= 30
  4491.3  330.49  4537.1  329.16  4689.2  318.65  4823.1  315.63  4835.7  314.06
  4850.5  313.74  4873.4  311.86  4903.2  313.32  4916.9  312.72  4960.4  313.95
  4970.7   313.4  4976.4  306.96  4982.8  302.61  4983.3  302.11    5002  302.61
  5003.3  304.12    5009  304.12  5019.7  309.84  5041.1  315.09  5099.4  314.62
  5135.6  315.47  5181.1  316.04  5225.8  318.56    5253  318.83  5274.3  320.14
  5342.4  320.96  5348.2  321.81  5363.8  321.03  5464.8  321.25  5589.2  322.46
#Mann= 5 ,-1 , 0
  4491.3     .07       0  4850.5      .1       0  4982.8     .05       0
    5002      .1       0  5135.6     .07       0
Bank Sta=4982.8,5002
XS Rating Curve= 0 ,0
Exp/Cntr=0.3,0.1

Type RM Length L Ch R = 1 ,32082   ,449,449,449
BEGIN DESCRIPTION:
MOUND CREEK 40.0
END DESCRIPTION:
XS GIS Cut Line= 3
      2395425.02     13619024.98        2395675.       13618725.
      2395774.99     13618475.04
#Sta/Elev= 30
    4603  331.27  4624.4  330.14  4638.8  328.39  4666.7  321.95  4673.9   319.7
  4709.1  315.67  4759.2  313.82    4795  313.94  4806.7  313.16  4845.5  312.41
  4879.6  312.13  4887.4  311.37    4929  312.79  4943.4  309.85  4979.8  311.88
  4986.3  310.26  4990.2  307.23  4996.2  307.23  4998.7  300.28  4999.2  299.78
  5017.9  300.28  5025.8  304.78  5032.5   309.9  5037.9  312.19  5062.1  313.42
  5068.9  316.22  5079.6  318.04  5101.2  319.29  5253.4     321  5262.7  320.93
#Mann= 7 ,-1 , 0
    4603     .07       0  4666.7     .12       0  4806.7     .07       0
  4845.5      .1       0  4998.7     .05       0  5017.9      .1       0
  5253.4     .07       0
Bank Sta=4998.7,5017.9
XS Rating Curve= 0 ,0
Exp/Cntr=0.3,0.1

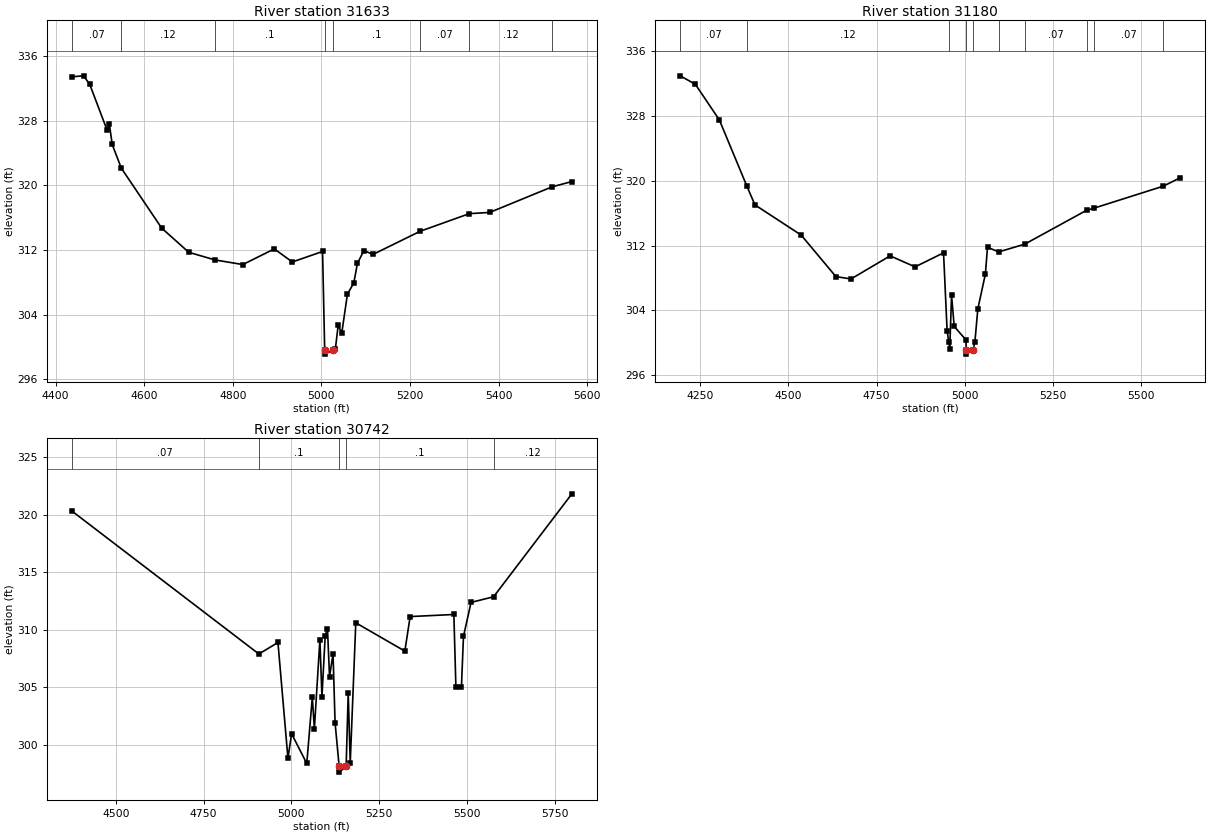
Type RM Length L Ch R = 1 ,31633   ,453,453,453
BEGIN DESCRIPTION:
MOUND CREEK 39.0
END DESCRIPTION:
XS GIS Cut Line= 3
        2395425.       13619125.        2395975.       13619025.
        2396425.       13618675.
#Sta/Elev= 30
  4436.3  333.47    4463  333.59    4477  332.54  4516.3  326.85  4521.4   327.6
  4527.8  325.08  4548.3  322.15  4639.6  314.71  4700.6  311.72  4759.3  310.78
  4822.5   310.2  4893.7  312.14  4934.3  310.52  5002.6  311.82  5007.4   299.6
  5007.9   299.1  5026.7   299.6  5031.5  299.72  5037.8  302.67    5046  301.73
  5058.7  306.52  5073.1  307.93  5081.3  310.34  5095.8  311.93  5116.6  311.46
  5223.1  314.33  5333.9  316.51  5379.9  316.66  5520.5  319.83  5565.4  320.49
#Mann= 8 ,-1 , 0
  4436.3     .07       0  4548.3     .12       0  4759.3      .1       0
  5007.4     .05       0  5026.7      .1       0  5223.1     .07       0
  5333.9     .12       0  5520.5     .07       0
Bank Sta=5007.4,5026.7
XS Rating Curve= 0 ,0
Exp/Cntr=0.3,0.1

Type RM Length L Ch R = 1 ,31180   ,438,438,438
BEGIN DESCRIPTION:
MOUND CREEK 38.0
END DESCRIPTION:
XS GIS Cut Line= 3
      2395424.98       13619225.        2396225.       13619325.
      2396575.02     13618824.98
#Sta/Elev= 30
  4193.8  332.96  4236.7  331.92  4304.7  327.52  4382.6  319.35  4405.5  317.03
  4536.5   313.3  4634.7  308.18  4677.6  307.89  4788.4  310.74    4859  309.38
  4939.6  311.11  4949.7  301.52  4954.3  300.15  4957.2  299.28  4962.3  305.86
  4969.8  302.03  5003.1  300.37  5003.9  299.11  5004.4  298.61  5023.2  299.11
  5028.4  300.12  5036.7  304.19    5058  308.47  5064.1  311.79    5096  311.23
  5169.4  312.18  5344.6  316.36  5364.5  316.61  5561.9  319.34  5610.4  320.39
#Mann= 10 ,-1 , 0
  4193.8     .07       0  4382.6     .12       0  4954.3      .1       0
  5003.9     .05       0  5023.2      .1       0    5096     .12       0
  5169.4     .07       0  5344.6     .12       0  5364.5     .07       0
  5561.9     .12       0
Bank Sta=5003.9,5023.2
XS Rating Curve= 0 ,0
Exp/Cntr=0.3,0.1

Type RM Length L Ch R = 1 ,30742   ,435,435,435
BEGIN DESCRIPTION:
MOUND CREEK 37.0
END DESCRIPTION:
XS GIS Cut Line= 3
        2395575.       13619525.        2396175.       13619675.
      2396875.01       13619275.
#Sta/Elev= 30
  4374.5  320.33  4907.7   307.9    4962   308.9  4990.4  298.85  5000.9  300.97
  5044.1  298.39  5059.9  304.15  5065.7  301.39  5081.5  309.13  5087.3  304.19
  5096.6   309.5  5103.1  310.08  5108.9  305.94  5118.9  307.91  5124.7  301.93
  5136.3  298.14  5136.8  297.64  5156.2  298.14  5162.1  304.48  5167.9  298.47
  5183.7  310.61  5323.4  308.15  5338.5  311.15    5463  311.33  5468.8  305.05
  5484.6  305.05  5490.4  309.43    5512  312.38  5576.2  312.87  5799.2  321.81
#Mann= 5 ,-1 , 0
  4374.5     .07       0  4907.7      .1       0  5136.3     .05       0
  5156.2      .1       0  5576.2     .12       0
Bank Sta=5136.3,5156.2
XS Rating Curve= 0 ,0
Exp/Cntr=0.3,0.1