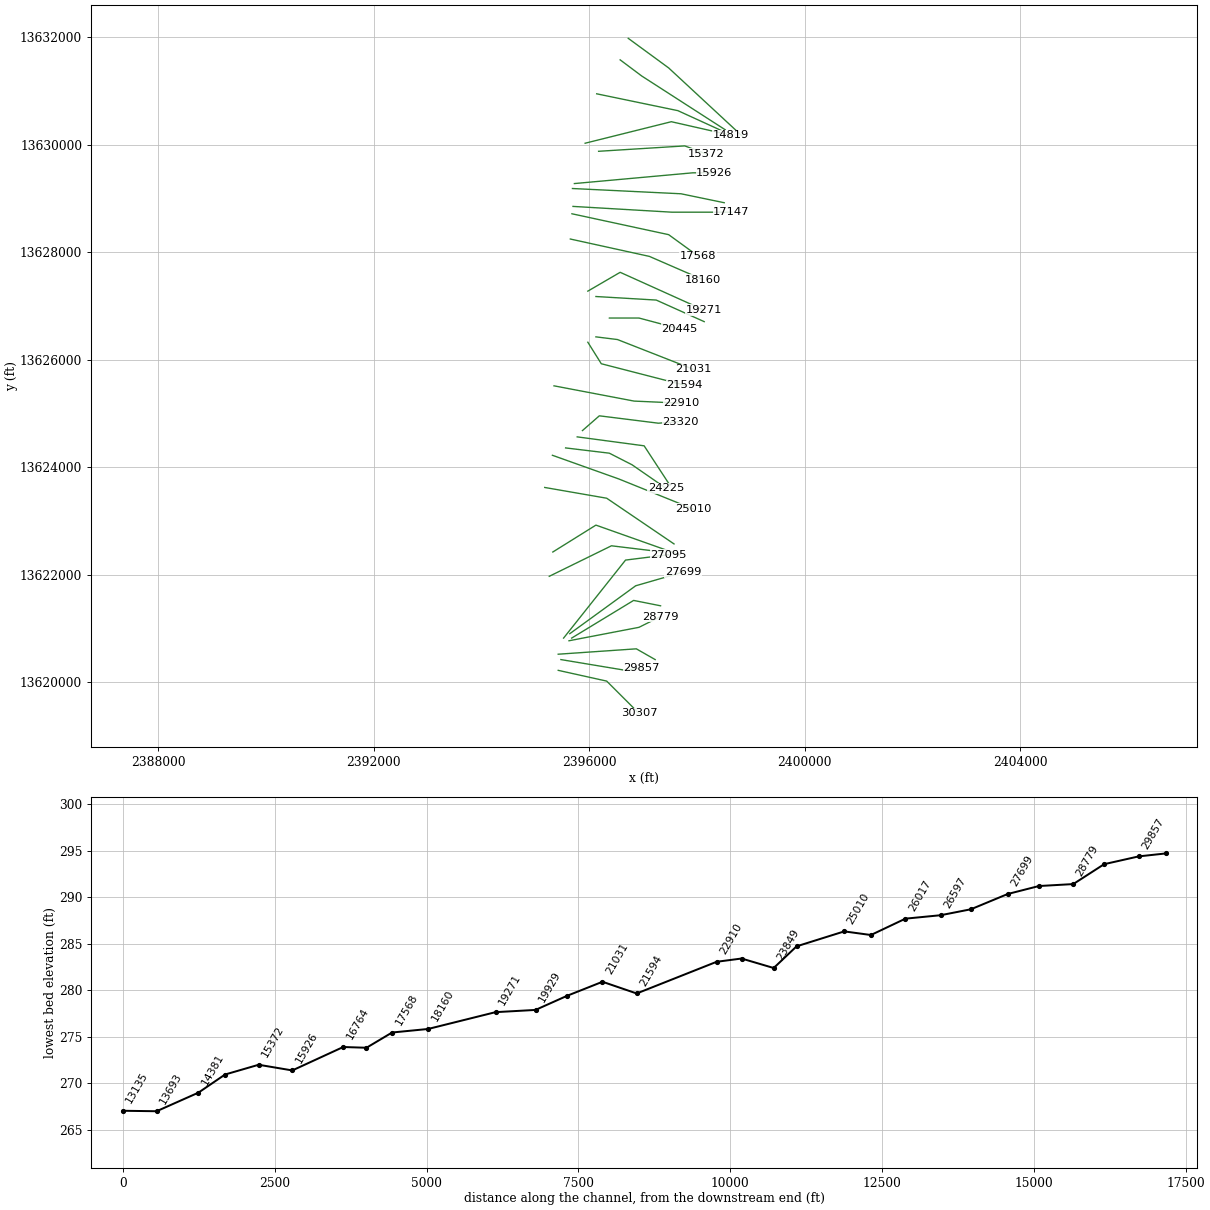
HEC-RAS study MOUND CREEK.prj: MOUND CREEK Base Level Engineering

--- MOUND CREEK.g01 (geometry) --- (continued)

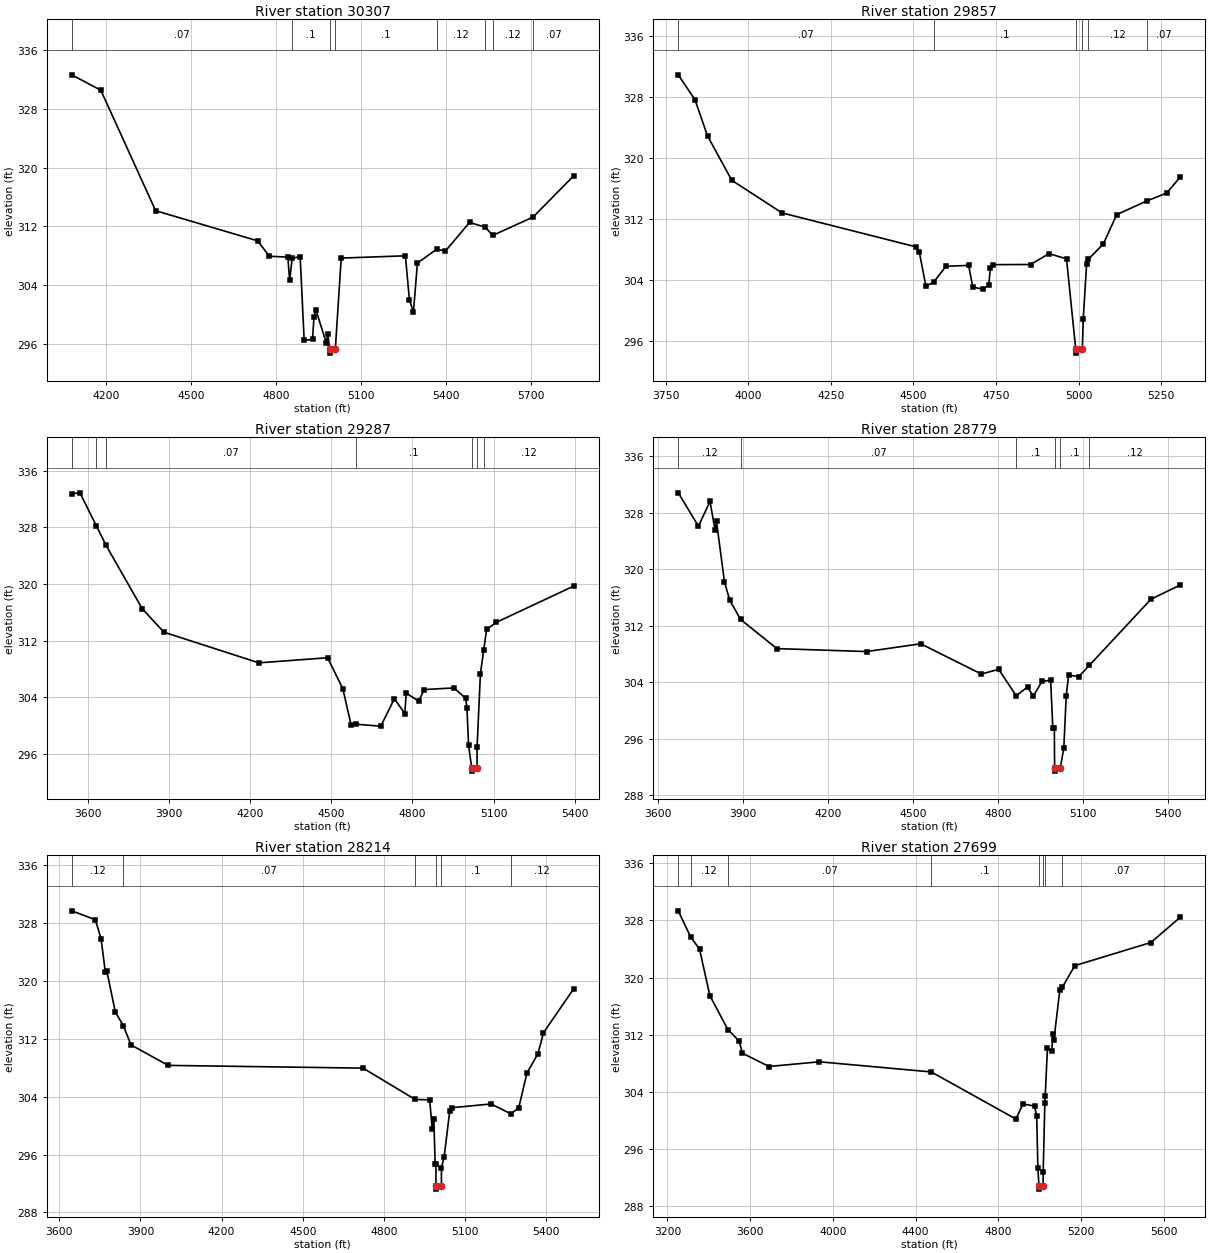
Type RM Length L Ch R = 1 ,30307   ,450,450,450
BEGIN DESCRIPTION:
MOUND CREEK 36.0
END DESCRIPTION:
XS GIS Cut Line= 3
      2395425.02       13620225.        2396325.       13620025.
      2396925.03     13619424.97
#Sta/Elev= 30
  4080.2  332.68  4182.6  330.58    4376  314.15  4735.8  310.04  4776.8  307.94
  4842.1  307.82  4848.5  304.64  4857.3  307.65  4885.6   307.9  4899.7  296.47
  4929.1  296.59  4934.3  299.64  4940.7  300.67  4977.8  296.12  4982.9  297.31
  4989.6  295.23  4990.1  294.73  5009.5  295.23  5030.4  307.69  5256.7     308
  5270.8     302    5285  300.34  5299.1  307.01  5367.2   308.9  5398.1  308.66
    5483  312.55  5538.3  311.91  5564.6  310.78  5707.1  313.29  5850.7  318.93
#Mann= 8 ,-1 , 0
  4080.2     .07       0  4857.3      .1       0  4989.6     .05       0
  5009.5      .1       0  5367.2     .12       0  5538.3      .1       0
  5564.6     .12       0  5707.1     .07       0
Bank Sta=4989.6,5009.5
XS Rating Curve= 0 ,0
Exp/Cntr=0.3,0.1

Type RM Length L Ch R = 1 ,29857   ,570,570,570
BEGIN DESCRIPTION:
MOUND CREEK 35.0
END DESCRIPTION:
XS GIS Cut Line= 3
      2395474.97       13620425.        2396675.       13620225.
      2396974.98       13620275.
#Sta/Elev= 30
  3787.6  330.93  3838.3  327.66  3876.3  322.91  3949.8  317.09  4101.9  312.81
  4507.4  308.36  4517.6   307.7  4537.8  303.18  4561.5  303.74  4598.7  305.81
  4667.1  305.92  4679.8  303.07  4710.2  302.82  4727.9  303.31    4733  305.52
  4740.6  306.02  4854.6  306.04  4910.4  307.46  4963.6  306.79  4991.6  294.91
  4992.1  294.41  5011.6  294.91  5014.3  298.89  5024.5  306.06  5030.2  306.76
  5075.1  308.73  5115.7  312.59  5206.6  314.37  5267.8  315.44  5308.3  317.54
#Mann= 6 ,-1 , 0
  3787.6     .07       0  4561.5      .1       0  4991.6     .05       0
  5011.6      .1       0  5030.2     .12       0  5206.6     .07       0
Bank Sta=4991.6,5011.6
XS Rating Curve= 0 ,0
Exp/Cntr=0.3,0.1

Type RM Length L Ch R = 1 ,29287   ,508,508,508
BEGIN DESCRIPTION:
MOUND CREEK 34.0
END DESCRIPTION:
XS GIS Cut Line= 3
      2395424.97       13620525.        2396875.       13620625.
      2397225.01     13620424.99
#Sta/Elev= 30
  3540.4  332.75  3570.5  332.87  3630.9  328.25  3667.2  325.45    3801   316.5
  3881.2  313.19  4232.1  308.86  4486.4  309.58  4542.8   305.2  4572.9  300.15
  4591.1   300.2  4683.1  299.91  4733.3   303.8  4772.1  301.69  4777.1  304.59
  4823.5  303.44  4843.5  305.09  4953.8  305.32  4996.8  303.85  5001.8  302.43
  5007.6  297.26  5019.1  294.07  5019.6  293.57  5039.1  294.07  5039.2  296.99
  5051.5  307.32  5063.6  310.67  5074.5  313.57  5109.8  314.57    5397  319.71
#Mann= 7 ,-1 , 0
  3540.4     .07       0  3630.9     .12       0  3667.2     .07       0
  4591.1      .1       0  5019.1     .05       0  5039.1      .1       0
  5063.6     .12       0
Bank Sta=5019.1,5039.1
XS Rating Curve= 0 ,0
Exp/Cntr=0.3,0.1

Type RM Length L Ch R = 1 ,28779   ,565,565,565
BEGIN DESCRIPTION:
MOUND CREEK 33.0
END DESCRIPTION:
XS GIS Cut Line= 3
      2395624.95     13620774.99        2396925.       13621025.
      2397325.02     13621225.01
#Sta/Elev= 30
  3671.9  330.79  3743.2  326.08    3784  329.58  3801.8  325.51  3806.9  326.75
  3834.9  318.19  3853.7  315.59    3892  312.88  4019.7  308.76  4336.4  308.34
  4527.3  309.44  4741.2  305.16  4802.3  305.83    4864  302.09  4904.1  303.32
  4924.5  302.03    4955  304.12  4985.6   304.3  4993.2  297.49  4998.6  297.49
  4999.6  291.93  5000.1  291.43  5019.8  291.93  5032.1   294.7  5040.5  302.06
  5048.9  304.99  5085.2  304.81  5122.6  306.41  5339.6  315.75    5443  317.76
#Mann= 6 ,-1 , 0
  3671.9     .12       0    3892     .07       0    4864      .1       0
  4999.6     .05       0  5019.8      .1       0  5122.6     .12       0
Bank Sta=4999.6,5019.8
XS Rating Curve= 0 ,0
Exp/Cntr=0.3,0.1

Type RM Length L Ch R = 1 ,28214   ,515,515,515
BEGIN DESCRIPTION:
MOUND CREEK 32.0
END DESCRIPTION:
XS GIS Cut Line= 3
      2395674.98     13620824.99        2396825.       13621525.
      2397324.98       13621425.
#Sta/Elev= 30
    3646  329.68  3733.2  328.45  3754.5  325.79    3770  321.21  3775.8  321.32
  3806.8  315.72  3836.9  313.79  3864.9  311.15  4002.5  308.32  4723.1  307.94
  4915.6  303.61  4969.1  303.56  4978.7  299.48  4984.6  300.95  4989.4  294.68
  4992.3  294.68  4992.4  291.72  4992.9  291.22  5012.6  291.72  5012.7  294.16
  5022.9  295.72  5043.3     302  5053.5  302.48  5196.3  302.99  5269.1  301.63
  5298.3  302.44  5328.9  307.26  5369.6  309.95    5390  312.84  5502.2  318.94
#Mann= 6 ,-1 , 0
    3646     .12       0  3836.9     .07       0  4915.6      .1       0
  4992.4     .05       0  5012.6      .1       0  5269.1     .12       0
Bank Sta=4992.4,5012.6
XS Rating Curve= 0 ,0
Exp/Cntr=0.3,0.1

Type RM Length L Ch R = 1 ,27699   ,604,604,604
BEGIN DESCRIPTION:
B19631
END DESCRIPTION:
XS GIS Cut Line= 3
      2395640.44     13620906.92      2396863.29     13621797.15
      2397741.89     13622050.97
#Sta/Elev= 30
  3252.5  329.35  3312.9  325.66  3355.3     324  3405.5  317.46  3492.4  312.72
  3547.7  311.08  3562.4  309.41  3691.1  307.54  3934.8   308.2  4475.4  306.78
    4885  300.18  4918.6  302.29    4975     302  4985.4  300.55  4991.1  293.31
  4996.2  290.86  4996.7  290.36  5016.4  290.86  5016.7  292.69  5024.7  302.49
  5026.3  303.34  5037.5  310.13  5058.3  309.65  5063.5  312.12  5068.7  311.32
  5097.2  318.26    5110  318.68  5169.6  321.67  5537.1  324.91  5679.6  328.45
#Mann= 8 ,-1 , 0
  3252.5     .07       0  3312.9     .12       0  3492.4     .07       0
  4475.4      .1       0  4996.2     .05       0  5016.4      .1       0
  5026.3     .12       0    5110     .07       0
Bank Sta=4996.2,5016.4
XS Rating Curve= 0 ,0
Exp/Cntr=0.3,0.1

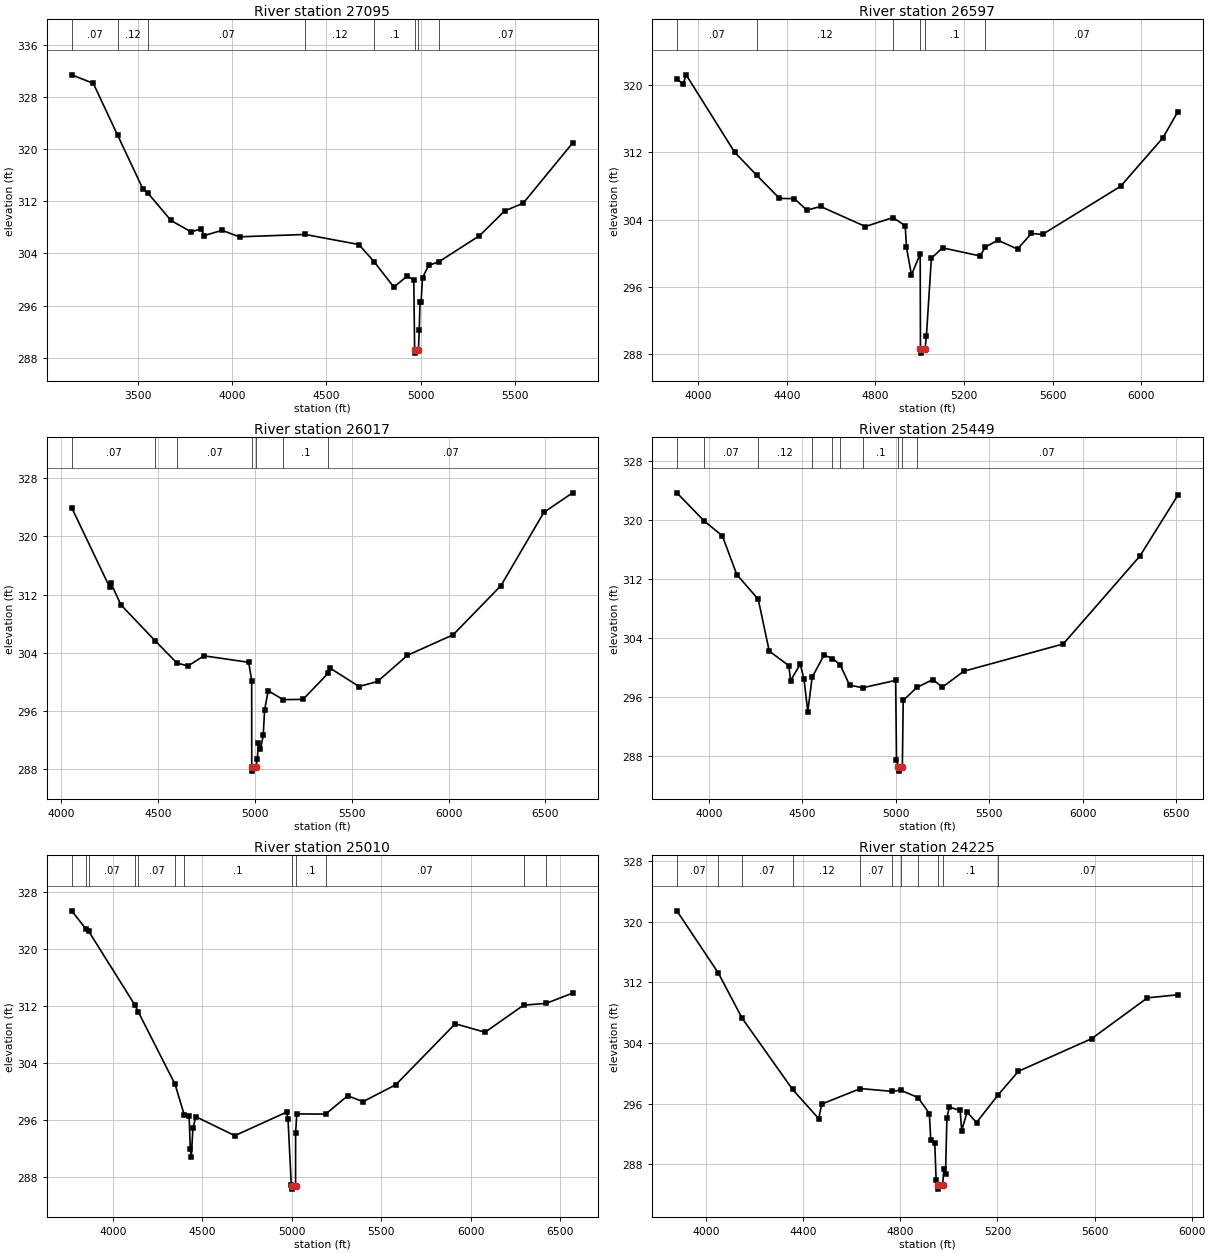
Type RM Length L Ch R = 1 ,27095   ,498,498,498
BEGIN DESCRIPTION:
MOUND CREEK 31.0
END DESCRIPTION:
XS GIS Cut Line= 3
      2395524.99     13620824.98        2396675.       13622275.
      2397474.98       13622375.
#Sta/Elev= 30
    3149  331.38  3263.6  330.07  3392.6  322.12  3526.4   313.9  3552.1  313.29
  3675.4  309.06  3782.7   307.3  3832.4  307.76  3853.2  306.75  3946.2  307.54
  4039.1  306.55    4387  306.91    4672  305.37  4752.9  302.74  4857.9  298.83
  4928.4  300.53  4963.6  299.92    4968  289.22  4968.5  288.72  4988.2  289.22
  4992.5  292.23  4996.5   296.5  5002.2   296.5  5009.8  300.27  5042.5  302.16
    5097  302.73  5312.1  306.72  5445.6  310.52  5543.9   311.7  5805.9  320.92
#Mann= 8 ,-1 , 0
    3149     .07       0  3392.6     .12       0  3552.1     .07       0
    4387     .12       0  4752.9      .1       0    4968     .05       0
  4988.2      .1       0    5097     .07       0
Bank Sta=4968,4988.2
XS Rating Curve= 0 ,0
Exp/Cntr=0.3,0.1

Type RM Length L Ch R = 1 ,26597   ,580,580,580
BEGIN DESCRIPTION:
B19630
END DESCRIPTION:
XS GIS Cut Line= 3
      2395259.01     13621973.25      2396413.29     13622540.61
      2397380.83     13622423.34
#Sta/Elev= 30
    3904  320.71    3933  320.18  3945.8  321.25    4165  312.02  4265.3  309.26
  4367.3  306.52  4434.4  306.49  4490.8  305.12  4552.7  305.56    4755  303.17
  4879.7  304.24  4934.8  303.26  4940.4   300.7  4962.9  297.41  5002.3  299.89
  5003.5  288.58    5004  288.08    5024  288.58  5030.3  290.07  5052.8  299.39
  5103.3  300.63  5272.5  299.66  5296.7  300.73  5353.1  301.54  5441.6  300.48
  5504.2  302.34  5554.5  302.23  5907.1  307.97  6098.5  313.76  6164.8  316.84
#Mann= 6 ,-1 , 0
    3904     .07       0  4265.3     .12       0  4879.7      .1       0
  5003.5     .05       0    5024      .1       0  5296.7     .07       0
Bank Sta=5003.5,5024
XS Rating Curve= 0 ,0
Exp/Cntr=0.3,0.1

Type RM Length L Ch R = 1 ,26017   ,568,568,568
BEGIN DESCRIPTION:
MOUND CREEK 30.0
END DESCRIPTION:
XS GIS Cut Line= 3
      2395324.97     13622424.98        2396125.       13622925.
      2397674.98     13622375.01
#Sta/Elev= 30
    4053  323.95  4249.4  312.99  4255.3   313.6  4307.2  310.58    4483  305.67
    4597  302.57  4654.4  302.18  4736.4  303.57  4967.5  302.68  4982.9  300.16
  4983.2  288.21  4983.7  287.71  5003.8  288.21  5011.9  289.31  5017.7  291.62
  5028.3  290.72  5042.7  292.64  5049.5  296.11  5068.3  298.77  5145.4  297.54
  5248.2  297.58  5377.8  301.16    5389  301.86  5537.6  299.35  5633.1  300.04
  5787.9  303.64  6024.2  306.47  6271.2  313.23  6492.6   323.3  6641.1  325.99
#Mann= 7 ,-1 , 0
    4053     .07       0    4483     .12       0    4597     .07       0
  4983.2     .05       0  5003.8     .07       0  5145.4      .1       0
  5377.8     .07       0
Bank Sta=4983.2,5003.8
XS Rating Curve= 0 ,0
Exp/Cntr=0.3,0.1

Type RM Length L Ch R = 1 ,25449   ,439,439,439
BEGIN DESCRIPTION:
MOUND CREEK 29.0
END DESCRIPTION:
XS GIS Cut Line= 3
      2395175.05     13623624.99        2396325.       13623425.
      2397574.97     13622575.02
#Sta/Elev= 30
  3828.5  323.67  3973.3  319.89  4072.1  317.83  4148.8   312.6  4263.8  309.24
  4322.6  302.22  4427.3  300.25  4436.8  298.21  4488.2  300.46  4508.5  298.41
  4528.8  294.01    4552  298.66  4615.7  301.69  4660.1  301.21  4701.3   300.4
  4752.1  297.61  4822.3  297.25  4998.7  298.25  5003.2  287.47  5013.9  286.45
  5014.4  285.95  5034.5  286.45  5039.1  295.53  5112.1  297.29  5197.7  298.36
  5248.6  297.33  5362.4  299.48  5895.2  303.19  6305.3  315.11  6507.3  323.32
#Mann= 10 ,-1 , 0
  3828.5    .035       0  3973.3     .07       0  4263.8     .12       0
    4552     .07       0  4660.1     .12       0  4701.3     .07       0
  4822.3      .1       0  5013.9     .05       0  5034.5      .1       0
  5112.1     .07       0
Bank Sta=5013.9,5034.5
XS Rating Curve= 0 ,0
Exp/Cntr=0.3,0.1

Type RM Length L Ch R = 1 ,25010   ,785,785,785
BEGIN DESCRIPTION:
MOUND CREEK 28.0
END DESCRIPTION:
XS GIS Cut Line= 3
      2395317.66     13624223.19      2396550.25     13623782.98
      2397929.57     13623225.38
#Sta/Elev= 30
    3771  325.37  3851.1  322.81  3866.2  322.49  4124.8  312.12  4141.6  311.25
  4347.9  301.05  4398.8   296.8  4426.5  296.55  4433.2  291.94  4438.5  290.89
  4447.8  294.86    4464   296.5  4681.4  293.84  4971.6  297.15  4978.7  296.14
  4997.1  286.89  5000.3  286.84  5000.8  286.34  5020.9  286.84  5021.2  294.28
  5027.9  296.89  5188.8  296.86  5311.5  299.43  5397.8  298.61  5581.1  300.99
  5912.5  309.53  6078.8  308.34  6294.1  312.14  6419.7  312.39  6567.6  313.83
#Mann= 12 ,-1 , 0
    3771     .07       0  3851.1     .12       0  3866.2     .07       0
  4124.8     .12       0  4141.6     .07       0  4347.9     .12       0
  4398.8      .1       0  5000.3     .05       0  5020.9      .1       0
  5188.8     .07       0  6294.1    .035       0  6419.7     .07       0
Bank Sta=5000.3,5020.9
XS Rating Curve= 0 ,0
Exp/Cntr=0.3,0.1

Type RM Length L Ch R = 1 ,24225   ,376,376,376
BEGIN DESCRIPTION:
B19629
END DESCRIPTION:
XS GIS Cut Line= 4
      2395562.18     13624360.15      2396374.16     13624262.32
      2396794.81     13624047.11      2397430.32     13623607.14
#Sta/Elev= 30
  3879.4  321.45    4050  313.26  4147.9   307.3  4356.1  297.88  4463.6  294.04
  4476.5  295.96  4635.8     298  4765.2  297.63  4801.3  297.79  4873.3   296.8
  4919.6   294.7  4925.2  291.25  4941.8  290.87  4947.4  285.93  4953.4  285.23
  4953.9  284.73  4974.6  285.23    4979  287.34  4986.2  286.78  4991.8  294.09
  5001.5  295.56  5046.4  295.11  5052.8  292.46    5075   294.9  5113.8  293.52
    5204  297.21  5286.6  300.28    5588  304.58  5817.7  309.97  5942.7  310.37
#Mann= 11 ,-1 , 0
  3879.4     .07       0    4050     .12       0  4147.9     .07       0
  4356.1     .12       0  4635.8     .07       0  4765.2     .12       0
  4801.3     .07       0  4873.3      .1       0  4953.4     .05       0
  4974.6      .1       0    5204     .07       0
Bank Sta=4953.4,4974.6
XS Rating Curve= 0 ,0
Exp/Cntr=0.3,0.1

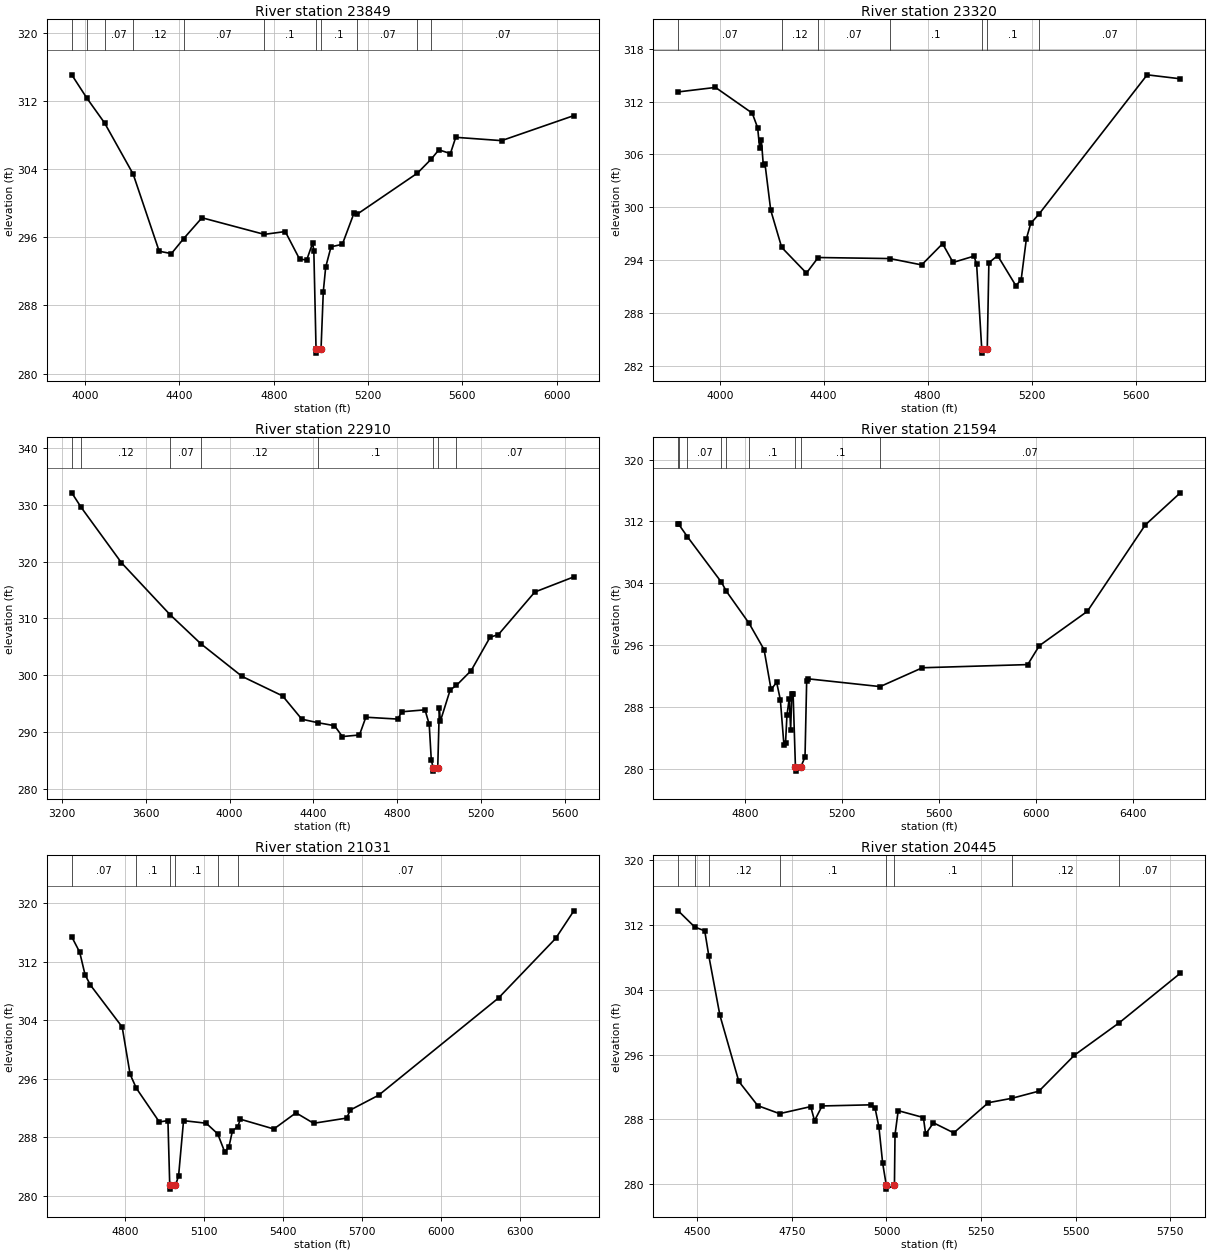
Type RM Length L Ch R = 1 ,23849   ,529,529,529
BEGIN DESCRIPTION:
B19628
END DESCRIPTION:
XS GIS Cut Line= 3
      2395777.44     13624565.57       2397019.8     13624399.27
      2397499.13     13623665.62
#Sta/Elev= 30
  3943.1  315.09    4007  312.36  4082.2  309.44  4203.5  303.43  4313.9  294.37
  4365.7  294.09  4417.7  295.85  4495.5   298.3  4759.8  296.35  4848.7  296.68
  4909.2  293.46  4939.5  293.33  4964.8  295.32  4969.9  294.45  4979.3   282.9
  4979.8   282.4  5000.5   282.9  5010.1  289.63  5020.2   292.5  5042.9  294.89
  5090.8  295.18  5141.2  298.91  5154.9  298.74  5409.2  303.54  5467.9  305.19
  5500.3  306.28  5549.2  305.84  5571.9  307.75  5766.4  307.36  6072.9   310.3
#Mann= 11 ,-1 , 0
  3943.1     .07       0    4007     .12       0  4082.2     .07       0
  4203.5     .12       0  4417.7     .07       0  4759.8      .1       0
  4979.3     .05       0  5000.5      .1       0  5154.9     .07       0
  5409.2     .12       0  5467.9     .07       0
Bank Sta=4979.3,5000.5
XS Rating Curve= 0 ,0
Exp/Cntr=0.3,0.1

Type RM Length L Ch R = 1 ,23320   ,410,410,410
BEGIN DESCRIPTION:
B19627
END DESCRIPTION:
XS GIS Cut Line= 4
      2395875.23     13624682.94       2396188.3     13624956.87
      2397283.93     13624819.92      2397694.83     13624849.27
#Sta/Elev= 30
  3840.3  313.09  3983.6   313.6    4125  310.68  4145.9  309.02  4153.5  306.72
  4160.1  307.66  4167.7  304.77  4174.4  304.86  4196.2  299.66  4238.4  295.43
  4333.6  292.51  4378.9  294.28  4655.1  294.16    4777  293.44  4857.6  295.85
  4897.9  293.72  4978.6  294.44  4988.6  293.49  5008.2  283.92  5008.7  283.42
  5029.5  283.92  5035.7  293.68  5069.3   294.5  5139.8  291.07    5160  291.77
  5180.1  296.42  5196.9  298.16  5228.6  299.21  5644.8  315.03  5772.4  314.58
#Mann= 7 ,-1 , 0
  3840.3     .07       0  4238.4     .12       0  4378.9     .07       0
  4655.1      .1       0  5008.2     .05       0  5029.5      .1       0
  5228.6     .07       0
Bank Sta=5008.2,5029.5
XS Rating Curve= 0 ,0
Exp/Cntr=0.3,0.1

Type RM Length L Ch R = 1 ,22910   ,1316,1316,1316
BEGIN DESCRIPTION:
B19626
END DESCRIPTION:
XS GIS Cut Line= 3
      2395347.01     13625514.47      2396833.94     13625230.78
      2397714.32     13625191.65
#Sta/Elev= 30
  3247.2  332.11  3291.8  329.56  3484.4  319.78  3715.5  310.66  3862.8  305.52
  4059.6  299.76    4253  296.32  4344.6  292.22  4421.5   291.6  4500.4  291.08
  4538.1  289.16  4619.5  289.44    4650  292.57    4802  292.24  4822.1  293.53
  4932.2  293.87  4952.2  291.34  4962.2  285.03  4971.6  283.57  4972.1  283.07
  4992.9  283.57  5000.5  294.13  5005.5  291.88  5052.3  297.38  5081.9  298.17
  5152.4  300.79  5242.5  306.66  5282.5  307.14    5456  314.63  5642.2   317.3
#Mann= 8 ,-1 , 0
  3247.2     .07       0  3291.8     .12       0  3715.5     .07       0
  3862.8     .12       0  4421.5      .1       0  4971.6     .05       0
  4992.9      .1       0  5081.9     .07       0
Bank Sta=4971.6,4992.9
XS Rating Curve= 0 ,0
Exp/Cntr=0.3,0.1

Type RM Length L Ch R = 1 ,21594   ,563,563,563
BEGIN DESCRIPTION:
MOUND CREEK 26.0
END DESCRIPTION:
XS GIS Cut Line= 3
      2395975.02     13626324.97        2396225.       13625925.
      2397774.96     13625525.01
#Sta/Elev= 30
  4524.2  311.65  4525.7  311.65  4561.9  310.03  4702.5  304.13  4722.8  302.96
  4816.6  298.81  4878.5   295.4  4907.4  290.24  4930.4  291.16  4945.7   288.9
  4960.5  283.03    4967  283.26  4972.9  286.88  4982.3  289.06  4988.2     285
  4992.9  289.63  4998.4  289.63    5008  280.16  5008.5  279.66  5029.5  280.16
  5047.5  281.49  5054.3  291.33  5059.4  291.62  5357.6  290.61  5531.9  293.05
  5966.7  293.46  6014.7  295.91  6212.9  300.36  6451.7  311.54  6596.6  315.71
#Mann= 9 ,-1 , 0
  4524.2     .07       0  4525.7     .12       0  4561.9     .07       0
  4702.5     .12       0  4722.8     .07       0  4816.6      .1       0
    5008     .05       0  5029.5      .1       0  5357.6     .07       0
Bank Sta=5008,5029.5
XS Rating Curve= 0 ,0
Exp/Cntr=0.3,0.1

Type RM Length L Ch R = 1 ,21031   ,586,586,586
BEGIN DESCRIPTION:
MOUND CREEK 25.0
END DESCRIPTION:
XS GIS Cut Line= 3
        2396125.       13626425.        2396525.       13626375.
      2397925.02     13625824.99
#Sta/Elev= 30
  4596.9   315.4  4627.1   313.3  4647.3  310.23  4667.4  308.83  4788.4  303.08
  4818.6  296.61  4842.4   294.7  4929.5   290.1  4962.2  290.29  4969.1  281.42
  4969.6  280.92  4990.7  281.42  5002.7  282.74  5021.5  290.28  5107.5  289.93
  5151.4  288.47  5177.5  286.04  5193.4  286.62  5207.3  288.89    5228  289.48
  5237.1  290.48  5364.6  289.14  5448.6  291.35  5515.7  289.92    5641  290.63
  5655.4  291.74  5762.8  293.76  6218.2  307.05  6435.1  315.19  6504.2  318.96
#Mann= 6 ,-1 , 0
  4596.9     .07       0  4842.4      .1       0  4969.1     .05       0
  4990.7      .1       0  5151.4     .12       0    5228     .07       0
Bank Sta=4969.1,4990.7
XS Rating Curve= 0 ,0
Exp/Cntr=0.3,0.1

Type RM Length L Ch R = 1 ,20445   ,516,516,516
BEGIN DESCRIPTION:
MOUND CREEK 24.0
END DESCRIPTION:
XS GIS Cut Line= 3
      2396375.04       13626775.        2396925.       13626775.
      2397675.03     13626574.99
#Sta/Elev= 30
    4450  313.73  4493.6  311.73    4520  311.26  4530.9  308.14    4560  300.86
    4610  292.69    4660   289.7  4717.6  288.71    4800  289.58    4810  287.84
    4830  289.66    4960   289.8    4970  289.38    4980  287.09    4990  282.59
  4999.5   279.9    5000   279.4  5021.1   279.9  5022.6  286.11    5031  289.08
  5097.6  288.23  5103.5  286.19  5124.2  287.58  5177.8  286.34    5269  290.06
  5331.7  290.61  5402.9  291.49  5496.7  295.93  5615.1  299.93  5776.2  306.03
#Mann= 8 ,-1 , 0
    4450     .12       0  4493.6     .07       0  4530.9     .12       0
  4717.6      .1       0  4999.5     .05       0  5021.1      .1       0
  5331.7     .12       0  5615.1     .07       0
Bank Sta=4999.5,5021.1
XS Rating Curve= 0 ,0
Exp/Cntr=0.3,0.1

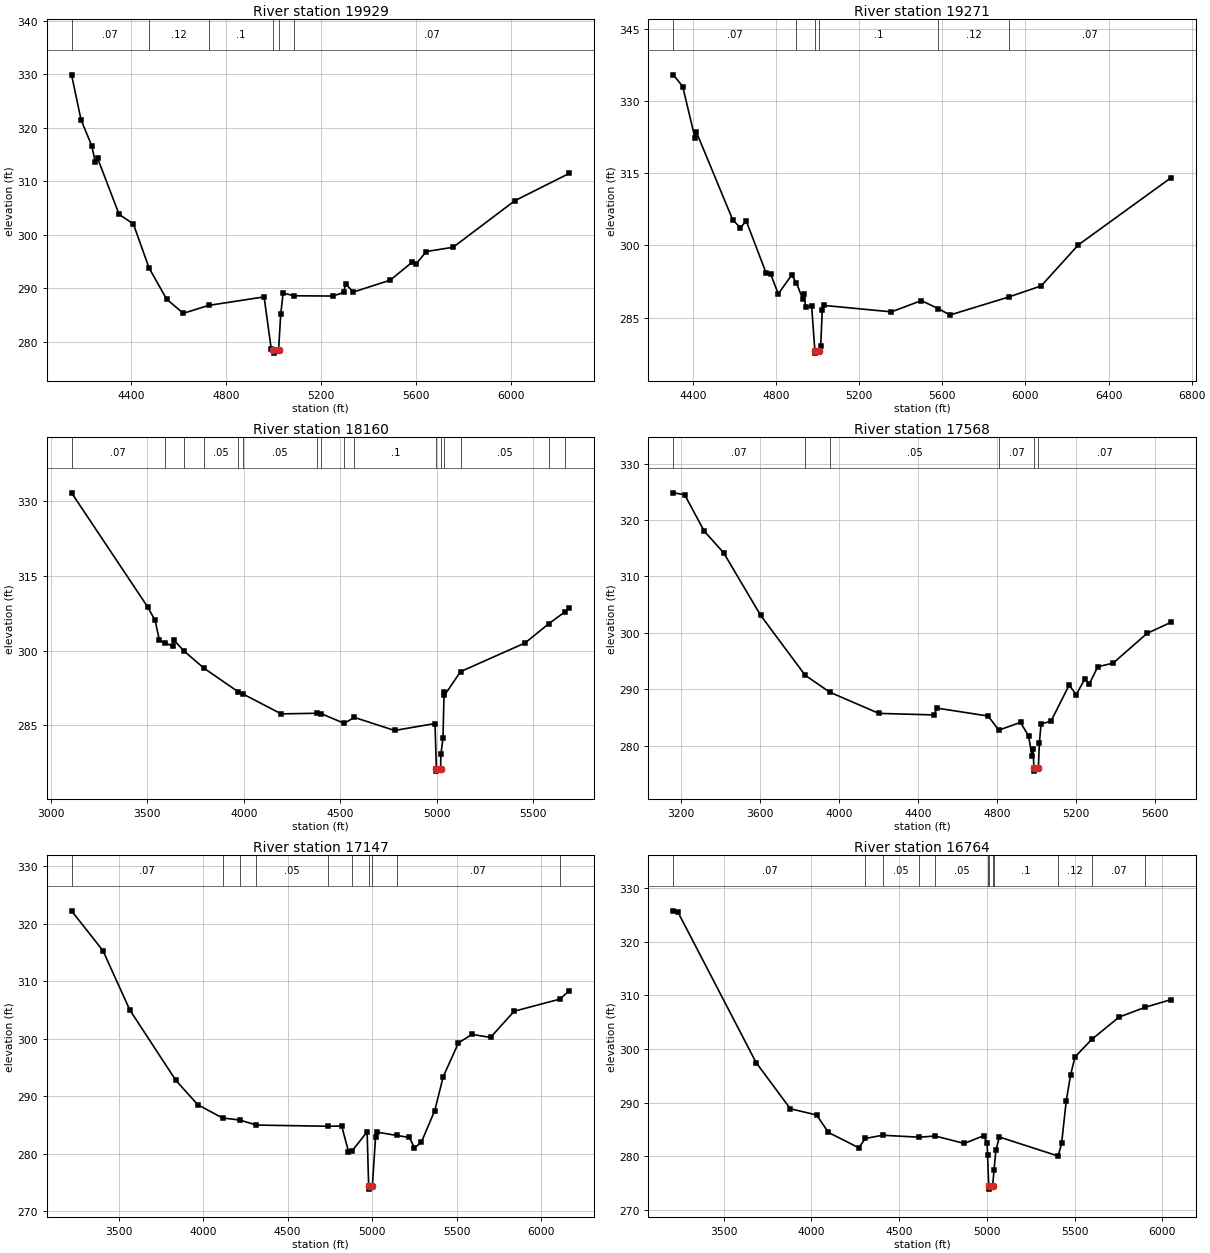
Type RM Length L Ch R = 1 ,19929   ,658,658,658
BEGIN DESCRIPTION:
MOUND CREEK 23.0
END DESCRIPTION:
XS GIS Cut Line= 3
      2396125.05       13627175.       2397244.8     13627109.01
      2398135.02     13626707.92
#Sta/Elev= 30
  4148.8  329.91  4188.8  321.49  4233.8  316.66  4248.9  313.62  4258.9  314.28
  4349.1  303.83  4409.2  302.04  4475.2  293.83  4549.4  287.98  4619.6  285.33
  4726.3  286.81  4960.2   288.4  4990.2   278.7  4999.4  278.39  4999.9  277.89
  5021.1  278.39  5030.3  285.16  5040.3   289.1    5088  288.61  5249.6  288.56
  5295.3  289.23  5303.6  290.84  5336.1  289.31  5491.4  291.52  5583.9  294.88
  5599.8  294.49  5643.6  296.88  5756.9  297.68  6016.5  306.37  6246.9   311.5
#Mann= 6 ,-1 , 0
  4148.8     .07       0  4475.2     .12       0  4726.3      .1       0
  4999.4     .05       0  5021.1      .1       0    5088     .07       0
Bank Sta=4999.4,5021.1
XS Rating Curve= 0 ,0
Exp/Cntr=0.3,0.1

Type RM Length L Ch R = 1 ,19271   ,1111,1111,1111
BEGIN DESCRIPTION:
MOUND CREEK 22.0
END DESCRIPTION:
XS GIS Cut Line= 3
      2395975.04     13627275.02        2396575.       13627625.
      2398124.99     13626925.01
#Sta/Elev= 30
  4306.4  335.44  4351.4     333  4410.1  322.34  4415.9  323.67  4592.1  305.31
  4629.3  303.67  4656.6  305.13  4752.5   294.3    4774  294.11  4811.2  289.94
  4875.7  293.89  4898.5  292.21  4928.6  288.89  4934.4   289.9  4943.1  287.16
  4971.6  287.45  4987.2  278.15  4987.7  277.65    5009  278.15  5015.3  279.18
  5022.9   286.7  5032.9  287.55  5355.4  286.22  5499.6  288.56  5581.8  286.86
  5637.4  285.57  5919.5   289.3  6076.3  291.62  6254.8  300.13  6701.7   314.1
#Mann= 6 ,-1 , 0
  4306.4     .07       0  4898.5      .1       0  4987.2     .05       0
    5009      .1       0  5581.8     .12       0  5919.5     .07       0
Bank Sta=4987.2,5009
XS Rating Curve= 0 ,0
Exp/Cntr=0.3,0.1

Type RM Length L Ch R = 1 ,18160   ,592,592,592
BEGIN DESCRIPTION:
B19625
END DESCRIPTION:
XS GIS Cut Line= 3
      2395650.26     13628243.77      2397117.63     13627920.95
      2398105.69     13627490.51
#Sta/Elev= 30
  3107.2  331.64  3501.7  308.76  3540.3  306.05  3562.6  302.04  3589.5  301.61
  3632.9  300.84    3638  302.08  3690.9  299.89  3792.3  296.51  3972.2  291.71
  3995.1  291.32  4193.7  287.32  4377.3  287.44  4400.6  287.37  4520.3  285.42
  4572.8  286.61  4781.3  283.99  4990.8  285.38  4997.9  276.34  4998.4  275.84
  5019.7  276.34  5021.3  279.21  5032.2  282.43  5037.7  291.62  5039.8  291.03
  5123.2  295.79  5457.6  301.54  5581.2  305.42    5665  307.79  5687.4  308.57
#Mann= 16 ,-1 , 0
  3107.2     .07       0  3589.5    .035       0  3690.9     .07       0
  3792.3     .05       0  3972.2     .07       0  3995.1     .05       0
  4377.3     .07       0  4400.6     .05       0  4520.3     .07       0
  4572.8      .1       0  4997.9     .05       0  5019.7      .1       0
  5039.8     .07       0  5123.2     .05       0  5581.2     .07       0
    5665     .05       0
Bank Sta=4997.9,5019.7
XS Rating Curve= 0 ,0
Exp/Cntr=0.3,0.1

Type RM Length L Ch R = 1 ,17568   ,421,421,421
BEGIN DESCRIPTION:
MOUND CREEK 21.0
END DESCRIPTION:
XS GIS Cut Line= 3
      2395679.63     13628713.32        2397475.       13628325.
      2398025.03     13627924.98
#Sta/Elev= 30
  3163.1  324.81  3219.8  324.49  3318.8  318.03  3417.3  314.17    3604   303.1
  3829.4  292.46  3954.3  289.45  4201.9   285.7  4478.2  285.43  4498.4  286.62
  4754.4  285.23  4808.1  282.73  4918.1   284.1  4959.1  281.68  4975.4   278.2
  4980.5  279.46  4986.5  275.96    4987  275.46  5008.3  275.96  5013.5  280.46
    5022  283.84  5072.2  284.31  5164.2  290.73  5199.8     289  5243.8  291.86
  5264.7  290.83  5308.7  293.98    5386   294.6  5557.6  299.88  5680.1  301.87
#Mann= 6 ,-1 , 0
  3163.1     .07       0  3829.4    .035       0  3954.3     .05       0
  4808.1     .07       0  4986.5     .05       0  5008.3     .07       0
Bank Sta=4986.5,5008.3
XS Rating Curve= 0 ,0
Exp/Cntr=0.3,0.1

Type RM Length L Ch R = 1 ,17147   ,383,383,383
BEGIN DESCRIPTION:
MOUND CREEK 20.0
END DESCRIPTION:
XS GIS Cut Line= 3
      2395699.15     13628850.28      2397538.27     13628742.67
      2398641.81     13628742.67
#Sta/Elev= 30
  3221.3  322.27  3407.5  315.31  3565.6  305.03  3838.2  292.76  3968.4  288.51
  4115.2   286.2  4216.7  285.85  4315.4  284.97  4736.1  284.77  4819.9   284.8
  4859.9  280.35  4882.4  280.52  4970.1  283.79  4979.3  274.32  4979.8  273.82
  5001.1  274.32  5020.2  282.91  5030.2  283.74  5145.8  283.16  5220.3  282.82
  5250.3  281.03  5290.3  281.94  5370.3  287.49  5420.3  293.38  5510.3  299.27
  5590.3  300.76  5700.3  300.23  5840.3  304.79  6109.6  306.89  6167.1  308.37
#Mann= 10 ,-1 , 0
  3221.3     .07       0  4115.2    .035       0  4216.7    .063       0
  4315.4     .05       0  4736.1     .07       0  4882.4      .1       0
  4979.3     .05       0  5001.1      .1       0  5145.8     .07       0
  6109.6     .12       0
Bank Sta=4979.3,5001.1
XS Rating Curve= 0 ,0
Exp/Cntr=0.3,0.1

Type RM Length L Ch R = 1 ,16764   ,838,838,838
BEGIN DESCRIPTION:
MOUND CREEK 19.0
END DESCRIPTION:
XS GIS Cut Line= 3
      2395689.37     13629182.88      2397704.57     13629085.06
      2398506.74     13628918.75
#Sta/Elev= 30
    3213  325.77  3238.7  325.54  3684.6  297.48  3879.4  288.88  4029.6  287.71
    4096  284.48  4269.9   281.6  4306.4  283.34    4405  283.94  4613.6  283.58
  4704.7   283.8  4870.6  282.41  4980.7  283.86  5000.7  282.57  5003.2  280.33
  5009.8   274.4  5010.3   273.9  5031.7   274.4  5040.2  277.48  5050.8  281.19
  5070.8  283.61  5405.3  280.07  5425.1  282.41  5451.6  290.36  5476.1  295.15
  5501.7  298.56  5597.6  301.83  5752.5  305.96  5900.9  307.79  6049.8  309.23
#Mann= 12 ,-1 , 0
    3213     .07       0  4306.4    .063       0    4405     .05       0
  4613.6     .07       0  4704.7     .05       0  5003.2     .07       0
  5009.8     .05       0  5031.7     .07       0  5040.2      .1       0
  5405.3     .12       0  5597.6     .07       0  5900.9     .12       0
Bank Sta=5009.8,5031.7
XS Rating Curve= 0 ,0
Exp/Cntr=0.3,0.1

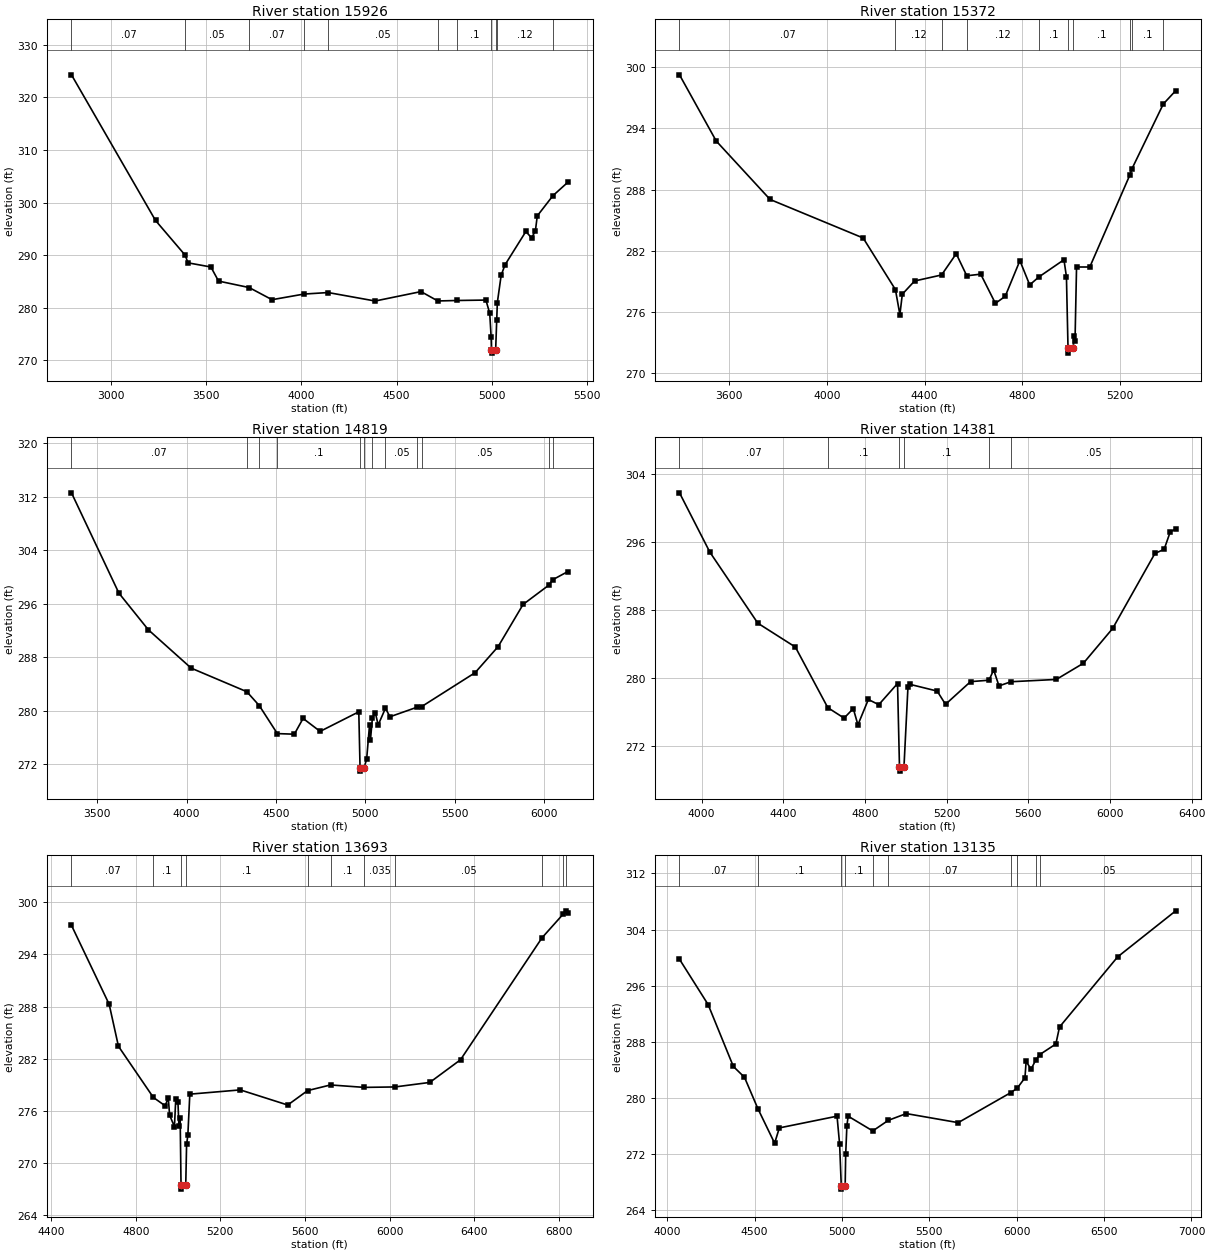
Type RM Length L Ch R = 1 ,15926   ,554,554,554
BEGIN DESCRIPTION:
MOUND CREEK 18.0
END DESCRIPTION:
XS GIS Cut Line= 3
      2395724.98       13629275.        2397925.       13629475.
      2398325.01       13629475.
#Sta/Elev= 30
  2790.9   324.3  3232.7  296.61  3388.7     290  3403.4  288.55  3523.9  287.76
  3564.1  285.08  3725.1  283.85  3845.3  281.54    4013  282.61  4140.4   282.9
  4387.5  281.29  4628.5  283.08  4717.1   281.3  4819.7  281.39  4969.9  281.47
    4990  278.94  4997.5  274.36    4999  271.88  4999.5  271.38    5021  271.88
  5026.7  277.66    5030     281    5050  286.16    5070  288.15    5180  294.51
    5210  293.29    5230  294.62    5240  297.48  5322.3  301.32    5400  303.85
#Mann= 11 ,-1 , 0
  2790.9     .07       0  3388.7     .05       0  3725.1     .07       0
    4013    .063       0  4140.4     .05       0  4717.1     .07       0
  4819.7      .1       0    4999     .05       0    5021      .1       0
  5026.7     .12       0  5322.3     .07       0
Bank Sta=4999,5021
XS Rating Curve= 0 ,0
Exp/Cntr=0.3,0.1

Type RM Length L Ch R = 1 ,15372   ,553,553,553
BEGIN DESCRIPTION:
MOUND CREEK 17.0
END DESCRIPTION:
XS GIS Cut Line= 3
      2396175.03       13629875.        2397775.       13629975.
        2398175.       13629825.
#Sta/Elev= 30
  3396.9  299.23  3547.2  292.75  3767.6  287.03  4148.3  283.26  4280.3  278.21
  4298.6  275.76  4308.6  277.76  4358.7  279.05  4469.1  279.64  4529.1  281.72
  4572.3  279.56  4629.3  279.72  4689.4  276.86  4729.5  277.55  4789.6  281.04
  4829.7  278.67  4867.5  279.45  4969.9  281.13    4980  279.47  4986.5  272.49
    4987  271.99  5008.5  272.49  5009.8  273.68  5015.1  273.17  5021.4  280.42
  5075.6  280.42  5239.6  289.43  5248.2  290.04  5376.5  296.38  5427.2  297.68
#Mann= 10 ,-1 , 0
  3396.9     .07       0  4280.3     .12       0  4469.1    .035       0
  4572.3     .12       0  4867.5      .1       0  4986.5     .05       0
  5008.5      .1       0  5239.6     .07       0  5248.2      .1       0
  5376.5     .07       0
Bank Sta=4986.5,5008.5
XS Rating Curve= 0 ,0
Exp/Cntr=0.3,0.1

Type RM Length L Ch R = 1 ,14819   ,438,438,438
BEGIN DESCRIPTION:
MOUND CREEK 16.0
END DESCRIPTION:
XS GIS Cut Line= 3
      2395925.05     13630025.01        2397525.       13630425.
      2398624.96     13630175.01
#Sta/Elev= 30
  3355.3  312.61  3620.7  297.59  3785.6   292.1  4025.3  286.36  4336.7  282.83
  4406.6  280.74  4507.3  276.56  4602.5  276.47  4651.5  278.83  4746.8  276.89
  4963.3  279.82  4970.3  271.44  4970.8  270.94  4992.3  271.44  5007.1   272.7
  5023.5  277.89  5028.6  275.61  5039.4  278.92  5055.8  279.69  5071.7  277.85
  5112.4  280.35  5137.8  279.08  5290.3  280.52  5315.5  280.61  5614.2  285.68
  5742.9  289.58  5882.8   295.9  6026.5  298.78  6047.4  299.58  6132.5  300.81
#Mann= 12 ,-1 , 0
  3355.3     .07       0  4336.7     .12       0  4406.6     .07       0
  4507.3      .1       0  4970.3     .05       0  4992.3      .1       0
  5039.4    .035       0  5112.4     .05       0  5290.3     .07       0
  5315.5     .05       0  6026.5     .07       0  6047.4     .05       0
Bank Sta=4970.3,4992.3
XS Rating Curve= 0 ,0
Exp/Cntr=0.3,0.1

Type RM Length L Ch R = 1 ,14381   ,688,688,688
BEGIN DESCRIPTION:
B19624
END DESCRIPTION:
XS GIS Cut Line= 3
       2396139.4     13630943.71      2397645.88     13630630.68
      2398456.68     13630259.47
#Sta/Elev= 30
  3891.7  301.74  4040.4  294.76  4275.3   286.4  4459.2  283.59    4618  276.46
  4697.8  275.23  4742.8  276.35  4765.6  274.44  4816.6  277.42  4867.7  276.81
  4959.6   279.3  4969.1  269.49  4969.6  268.99  4991.1  269.49  5010.7  278.92
  5020.9   279.2  5153.7  278.41  5194.5  276.85  5317.1  279.52  5407.5  279.69
  5430.4   280.9  5456.5  279.02  5515.2  279.51  5737.3  279.78  5869.6  281.68
  6013.2  285.78  6220.2  294.61  6265.3  295.09  6294.8  297.12  6322.1  297.51
#Mann= 6 ,-1 , 0
  3891.7     .07       0    4618      .1       0  4969.1     .05       0
  4991.1      .1       0  5407.5    .035       0  5515.2     .05       0
Bank Sta=4969.1,4991.1
XS Rating Curve= 0 ,0
Exp/Cntr=0.3,0.1

Type RM Length L Ch R = 1 ,13693   ,558,558,558
BEGIN DESCRIPTION:
MOUND CREEK 15.0
END DESCRIPTION:
XS GIS Cut Line= 3
      2396574.99     13631575.01        2396975.       13631275.
        2398525.       13630275.
#Sta/Elev= 30
  4496.6  297.35  4674.7  288.26  4718.5  283.43  4883.5  277.54  4939.3  276.58
  4953.9  277.51  4960.2  275.51  4983.1  274.18  4989.3  277.39  4999.6  277.03
  5004.2  274.27  5010.1  275.14  5014.2  267.49  5014.7  266.99  5036.5  267.49
  5040.5  272.14  5046.4  273.18  5055.7  277.92  5294.1  278.41  5518.3  276.67
  5612.2  278.33  5720.5  278.98  5879.9   278.7  6024.7  278.75  6189.5  279.27
  6334.7  281.88  6720.2  295.93    6819  298.62  6834.4  299.02  6841.2  298.82
#Mann= 11 ,-1 , 0
  4496.6     .07       0  4883.5      .1       0  5014.2     .05       0
  5036.5      .1       0  5612.2     .07       0  5720.5      .1       0
  5879.9    .035       0  6024.7     .05       0  6720.2     .07       0
    6819     .05       0  6834.4     .07       0
Bank Sta=5014.2,5036.5
XS Rating Curve= 0 ,0
Exp/Cntr=0.3,0.1

Type RM Length L Ch R = 1 ,13135   ,535,535,535
BEGIN DESCRIPTION:
MOUND CREEK 14.0
END DESCRIPTION:
XS GIS Cut Line= 3
      2396725.03     13631974.98        2397475.       13631425.
      2398874.99     13630125.01
#Sta/Elev= 30
  4069.7  299.78  4233.7  293.32    4378  284.51  4441.7  282.97  4518.4   278.5
  4614.2  273.58  4641.2  275.76  4971.5  277.43  4986.2  273.43  4995.7  267.54
  4996.2  267.04    5018  267.54    5021  271.99  5027.8  276.06  5035.1  277.43
  5175.9  275.33  5265.1  276.84  5367.9   277.8    5665  276.51  5967.1   280.8
  6003.7  281.44  6047.1   282.9  6053.9  285.24  6082.2  284.11  6107.5  285.37
  6132.2  286.21    6224  287.71  6244.9  290.13  6577.7  300.12  6910.2  306.68
#Mann= 10 ,-1 , 0
  4069.7     .07       0  4518.4      .1       0  4995.7     .05       0
    5018      .1       0  5175.9     .12       0  5265.1     .07       0
  5967.1    .035       0  6003.7     .07       0  6107.5    .035       0
  6132.2     .05       0
Bank Sta=4995.7,5018
XS Rating Curve= 0 ,0
Exp/Cntr=0.3,0.1