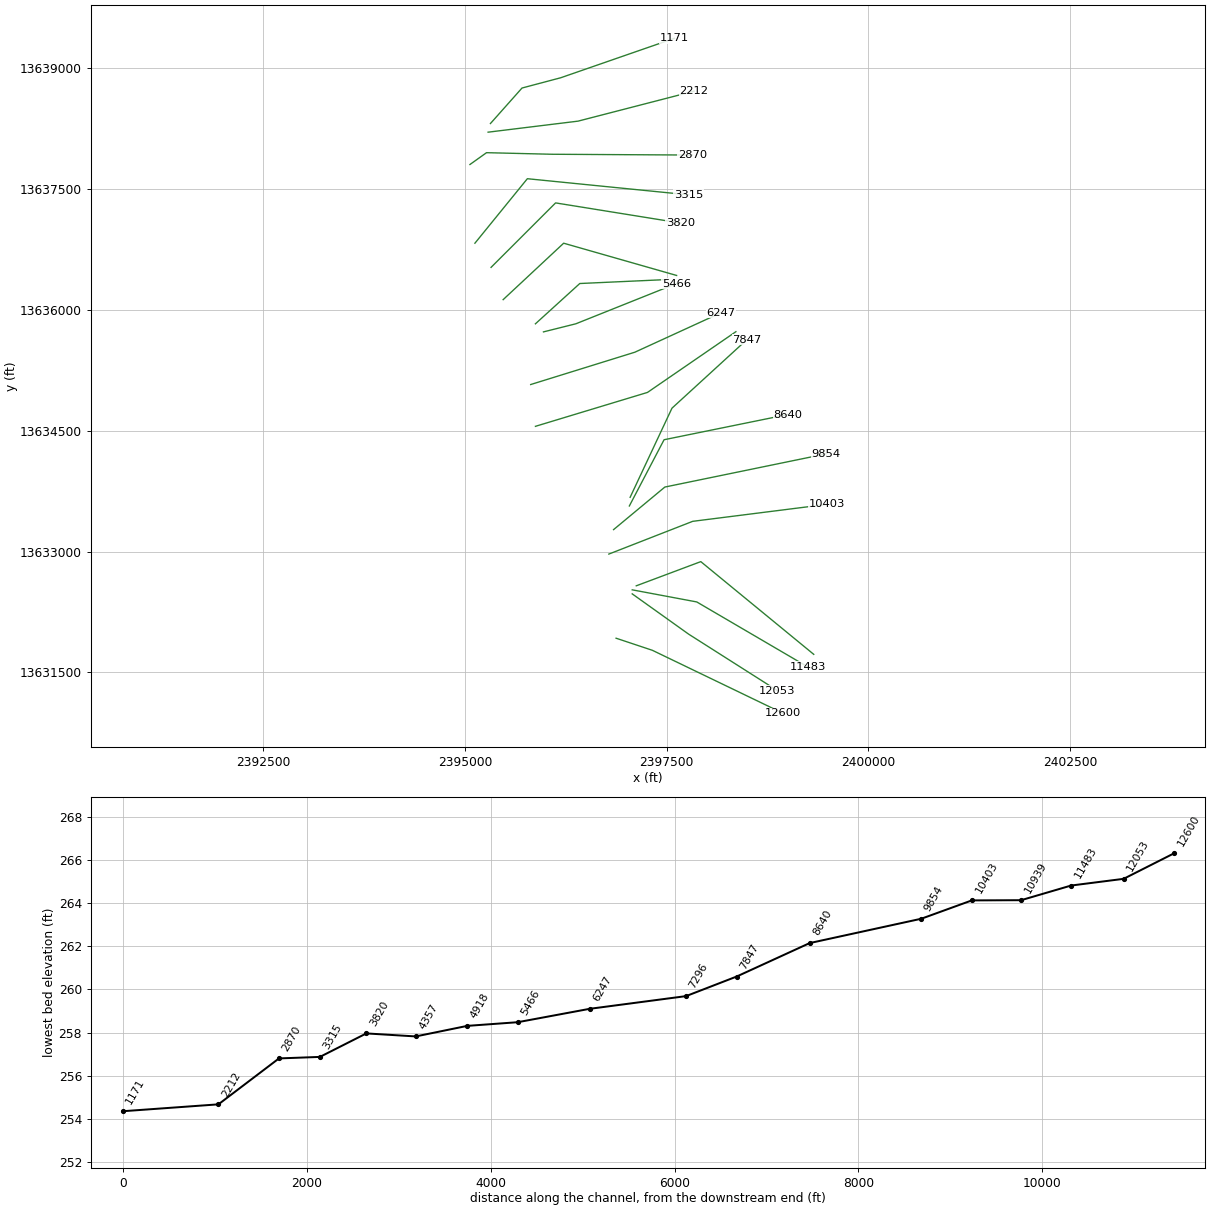
HEC-RAS study MOUND CREEK.prj: MOUND CREEK Base Level Engineering

--- MOUND CREEK.g01 (geometry) --- (continued)

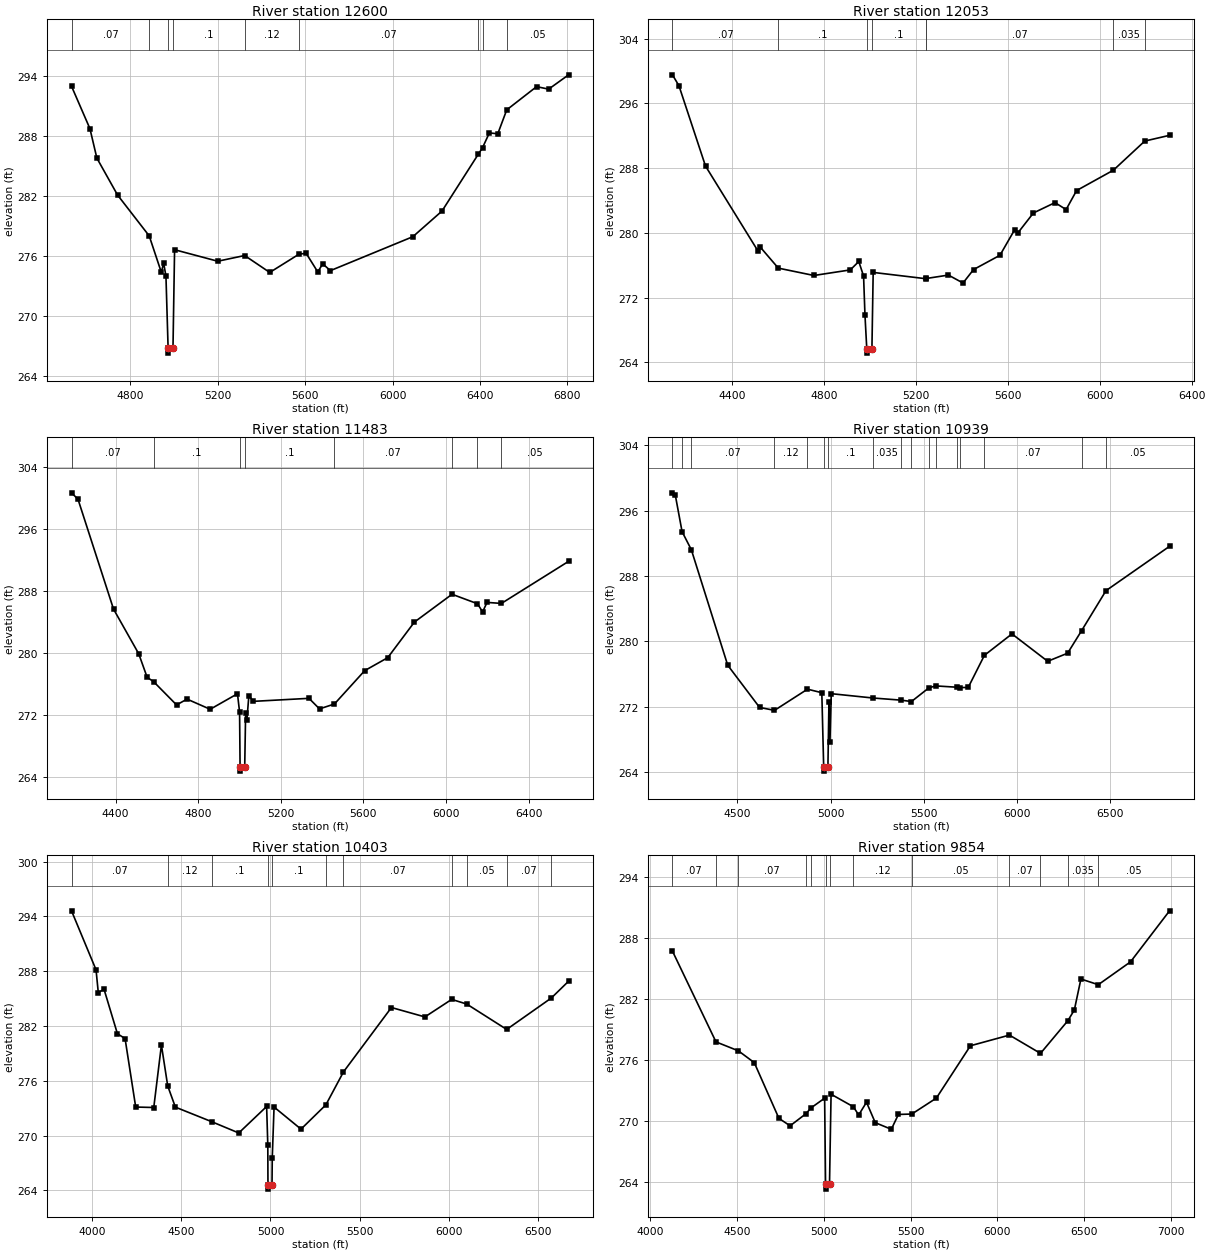
Type RM Length L Ch R = 1 ,12600   ,547,547,547
BEGIN DESCRIPTION:
MOUND CREEK 13.0
END DESCRIPTION:
XS GIS Cut Line= 3
      2396874.99       13631925.        2397325.       13631775.
      2398946.92     13630992.64
#Sta/Elev= 30
  4530.3  292.97  4614.6  288.73  4646.3  285.79  4741.1   282.1  4885.9  278.02
  4941.4  274.38  4951.9  275.32  4962.5     274  4972.4  266.81  4972.9  266.31
  4994.7  266.81    5002  276.64  5199.6  275.49  5322.8  276.06  5437.6  274.37
  5571.9   276.2  5604.2  276.28  5657.4  274.42    5680  275.23  5715.2  274.55
  6092.6  277.94  6225.9   280.5  6392.4  286.19  6411.5  286.83  6442.8  288.31
  6481.3  288.22  6522.3  290.61  6658.9  292.93  6714.2  292.68  6805.4  294.11
#Mann= 9 ,-1 , 0
  4530.3     .07       0  4885.9      .1       0  4972.4     .05       0
  4994.7      .1       0  5322.8     .12       0  5571.9     .07       0
  6392.4    .035       0  6411.5     .07       0  6522.3     .05       0
Bank Sta=4972.4,4994.7
XS Rating Curve= 0 ,0
Exp/Cntr=0.3,0.1

Type RM Length L Ch R = 1 ,12053   ,570,570,570
BEGIN DESCRIPTION:
MOUND CREEK 12.0
END DESCRIPTION:
XS GIS Cut Line= 3
      2397074.99       13632475.        2397775.       13631975.
      2398875.02     13631274.99
#Sta/Elev= 30
  4139.6  299.54  4167.9  298.18  4283.4  288.26    4512  277.75  4520.6  278.28
  4600.4  275.64  4755.3  274.73  4913.8  275.42  4950.7  276.46  4971.6  274.66
  4977.7   269.8  4985.6  265.63  4986.1  265.13  5007.9  265.63  5013.4  275.11
    5243  274.33  5244.7  274.36    5341  274.78  5404.5   273.8  5450.3  275.46
  5565.4  277.23  5628.9  280.37  5644.1  280.02    5711  282.46    5805  283.74
  5853.3  282.88    5899  285.23  6059.3  287.75  6195.8  291.35  6303.7  292.06
#Mann= 8 ,-1 , 0
  4139.6     .07       0  4600.4      .1       0  4985.6     .05       0
  5007.9      .1       0    5243     .12       0  5244.7     .07       0
  6059.3    .035       0  6195.8     .05       0
Bank Sta=4985.6,5007.9
XS Rating Curve= 0 ,0
Exp/Cntr=0.3,0.1

Type RM Length L Ch R = 1 ,11483   ,544,544,544
BEGIN DESCRIPTION:
MOUND CREEK 11.0
END DESCRIPTION:
XS GIS Cut Line= 3
      2397075.03     13632524.99        2397875.       13632375.
      2399249.94     13631569.94
#Sta/Elev= 30
  4186.5  300.68  4217.8  299.86  4389.9   285.7    4512  279.94  4552.7  276.91
  4584.4  276.34  4695.2  273.35    4746   274.1    4858  272.79  4990.2  274.79
  5000.4  272.43  5002.8  265.32  5003.3  264.82  5025.2  265.32  5029.7  272.37
  5035.5  271.35  5045.4  274.55  5066.9  273.81  5336.5   274.2  5387.5  272.84
  5459.7  273.47  5606.4  277.77  5717.9  279.44  5846.8  284.02  6029.3  287.61
  6152.4  286.39  6177.3  285.34  6198.8  286.56  6268.4  286.43  6593.7  291.85
#Mann= 8 ,-1 , 0
  4186.5     .07       0  4584.4      .1       0  5002.8     .05       0
  5025.2      .1       0  5459.7     .07       0  6029.3     .12       0
  6152.4    .035       0  6268.4     .05       0
Bank Sta=5002.8,5025.2
XS Rating Curve= 0 ,0
Exp/Cntr=0.3,0.1

Type RM Length L Ch R = 1 ,10939   ,536,536,536
BEGIN DESCRIPTION:
MOUND CREEK 10.0
END DESCRIPTION:
XS GIS Cut Line= 3
      2397125.04     13632575.01        2397925.       13632875.
      2399324.98     13631725.02
#Sta/Elev= 30
  4151.6  298.17  4166.7   297.9  4203.1  293.42  4252.8  291.21  4447.9  277.09
  4618.8  271.93  4698.8  271.57  4875.7  274.16  4952.6  273.73  4962.6  264.64
  4963.1  264.14  4985.3  264.64  4990.8  272.55  4996.2   267.7  5003.3  273.61
  5227.4  273.08  5377.3  272.82  5433.4  272.65  5527.2  274.33  5563.9  274.56
  5677.2   274.4  5694.3  274.36  5737.8  274.37  5824.7   278.3  5972.5  280.92
  6164.1  277.57    6271  278.56  6346.4  281.33  6476.9  286.21  6817.7  291.63
#Mann= 17 ,-1 , 0
  4151.6     .07       0  4203.1    .035       0  4252.8     .07       0
  4698.8     .12       0  4875.7      .1       0  4962.6     .05       0
  4985.3      .1       0  5227.4    .035       0  5377.3      .1       0
  5433.4     .07       0  5527.2      .1       0  5563.9     .12       0
  5677.2      .1       0  5694.3     .12       0  5824.7     .07       0
  6346.4    .035       0  6476.9     .05       0
Bank Sta=4962.6,4985.3
XS Rating Curve= 0 ,0
Exp/Cntr=0.3,0.1

Type RM Length L Ch R = 1 ,10403   ,549,549,549
BEGIN DESCRIPTION:
MOUND CREEK 9.0
END DESCRIPTION:
XS GIS Cut Line= 3
      2396785.06     13632968.69        2397825.       13633375.
      2399484.98     13633584.97
#Sta/Elev= 30
  3883.5  294.61  4021.1  288.15  4033.7  285.66    4066  286.02  4141.1  281.15
    4184  280.62  4243.7  273.12  4345.1  273.07    4388  279.91  4423.4  275.43
  4466.4  273.11  4669.7  271.52  4822.1  270.28  4978.5  273.18  4985.1  268.97
    4986  264.63  4986.5  264.13  5008.7  264.63  5010.1  267.57  5020.2  273.12
  5171.4   270.7    5311  273.36  5409.8  276.97  5678.9  284.02  5866.8  282.99
  6017.2  284.91  6101.5   284.4  6325.8  281.62  6576.2  285.06  6673.2   286.9
#Mann= 11 ,-1 , 0
  3883.5     .07       0  4423.4     .12       0  4669.7      .1       0
    4986     .05       0  5008.7      .1       0    5311    .035       0
  5409.8     .07       0  6017.2    .035       0  6101.5     .05       0
  6325.8     .07       0  6576.2     .05       0
Bank Sta=4986,5008.7
XS Rating Curve= 0 ,0
Exp/Cntr=0.3,0.1

Type RM Length L Ch R = 1 ,9854    ,1214,1214,1214
BEGIN DESCRIPTION:
B19623
END DESCRIPTION:
XS GIS Cut Line= 3
      2396843.75     13633271.96      2397479.58     13633800.19
       2399475.2     13634211.05
#Sta/Elev= 30
  4127.5   286.7  4378.2  277.77  4507.3  276.89  4598.8  275.73  4740.7  270.25
  4805.2  269.51  4895.7  270.69  4926.2  271.28  5004.2  272.23  5009.6  263.78
  5010.1  263.28  5032.3  263.78  5041.3  272.62  5169.4  271.39  5200.4  270.58
  5245.5  271.83  5295.9  269.82  5388.5  269.17  5429.3  270.63  5506.6  270.67
  5648.1  272.24  5844.3  277.39  6069.1  278.44    6248  276.64  6405.4  279.85
    6443  280.91  6480.9  283.96    6581   283.4  6766.8  285.65  6991.6  290.67
#Mann= 13 ,-1 , 0
  4127.5     .07       0  4378.2     .12       0  4507.3     .07       0
  4895.7     .12       0  4926.2      .1       0  5009.6     .05       0
  5032.3      .1       0  5169.4     .12       0  5506.6     .05       0
  6069.1     .07       0    6248     .05       0  6405.4    .035       0
    6581     .05       0
Bank Sta=5009.6,5032.3
XS Rating Curve= 0 ,0
Exp/Cntr=0.3,0.1

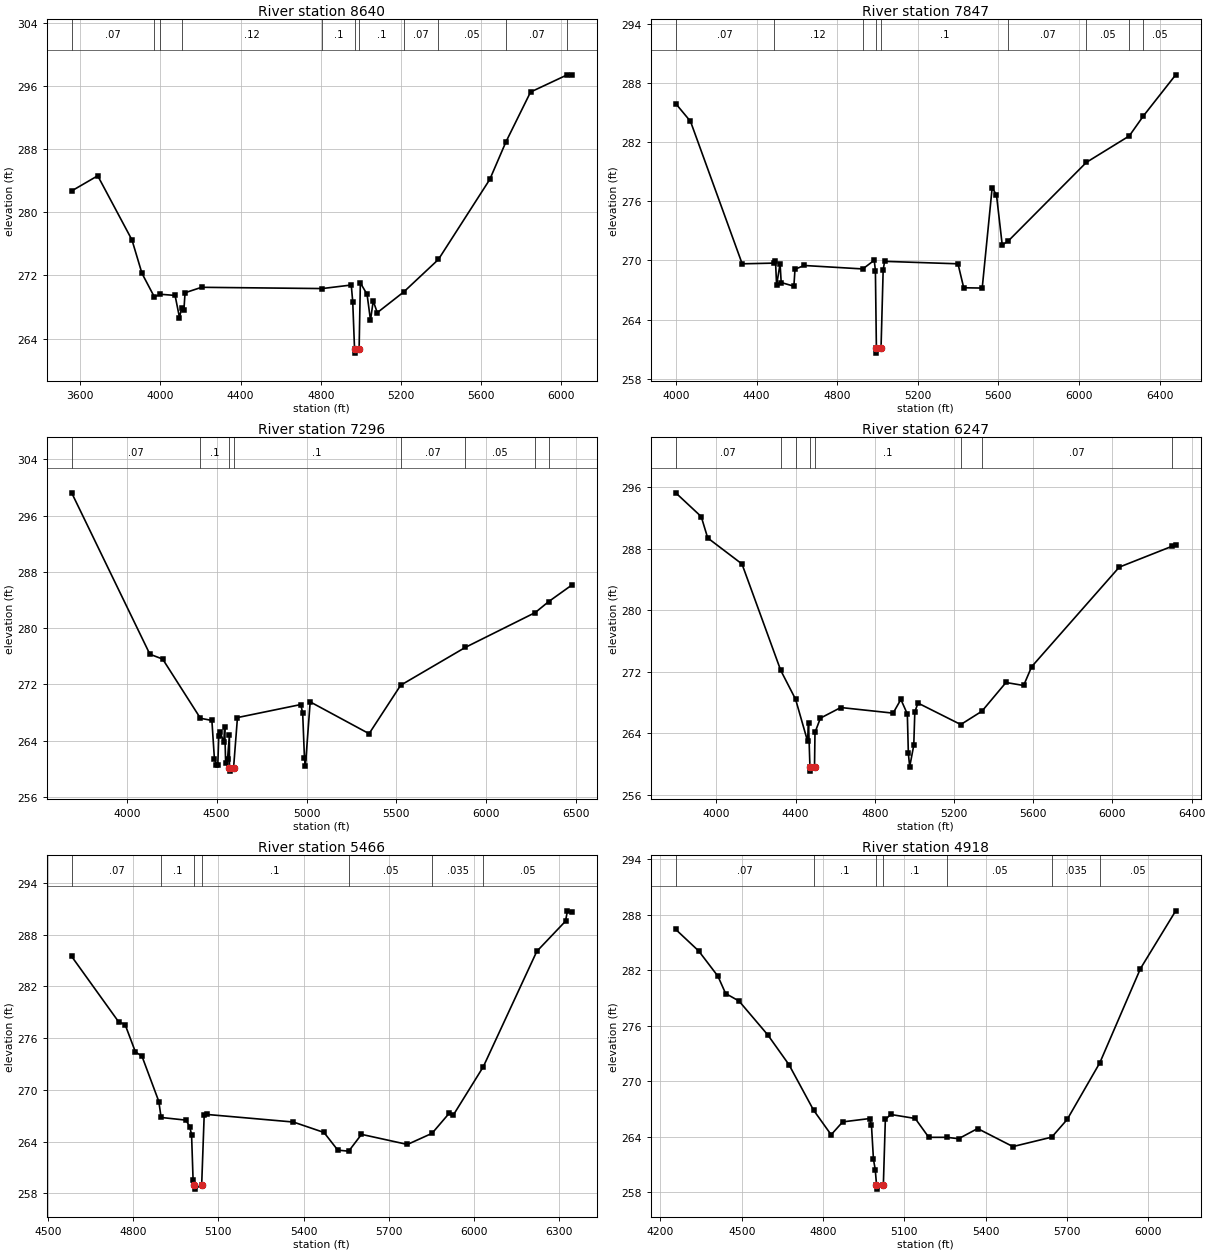
Type RM Length L Ch R = 1 ,8640    ,793,793,793
BEGIN DESCRIPTION:
B19622
END DESCRIPTION:
XS GIS Cut Line= 3
      2397039.35     13633565.38       2397469.8     13634387.13
      2399005.26     13634700.09
#Sta/Elev= 30
  3556.9   282.7  3686.9  284.62  3857.8  276.49  3907.6  272.26  3969.5  269.27
  3998.7  269.61  4072.8  269.46  4094.9  266.66  4105.7  267.89    4117  267.63
  4122.6   269.8  4205.2  270.49  4806.9  270.33  4951.9  270.78  4959.3  268.66
  4968.3  262.65  4968.8  262.15  4991.1  262.65  4997.3  271.05  5030.8   269.6
  5047.9  266.31  5061.4  268.76  5081.8  267.28  5213.7   269.9  5386.8  274.02
  5643.1  284.16  5723.8  288.92  5846.5  295.23  6027.9  297.39  6051.6  297.41
#Mann= 11 ,-1 , 0
  3556.9     .07       0  3969.5     .12       0  3998.7     .07       0
  4105.7     .12       0  4806.9      .1       0  4968.3     .05       0
  4991.1      .1       0  5213.7     .07       0  5386.8     .05       0
  5723.8     .07       0  6027.9    .035       0
Bank Sta=4968.3,4991.1
XS Rating Curve= 0 ,0
Exp/Cntr=0.3,0.1

Type RM Length L Ch R = 1 ,7847    ,551,551,551
BEGIN DESCRIPTION:
B19621
END DESCRIPTION:
XS GIS Cut Line= 3
      2397049.17     13633673.04      2397567.62     13634778.43
      2398496.97     13635629.51
#Sta/Elev= 30
  3998.7  285.91    4072  284.11  4328.5  269.66  4485.7  269.73  4493.8  269.96
  4499.3   267.5  4516.6  269.67  4522.1  267.76  4585.1  267.39  4590.6  269.11
  4636.2  269.49    4927  269.14  4983.9  270.02  4989.6  268.96  4994.5   261.1
    4995   260.6  5017.5   261.1  5028.1  269.02  5035.2  269.91  5399.4  269.66
  5427.8  267.23  5519.6   267.2    5569  277.38  5590.5  276.64  5618.9  271.57
  5649.1  271.98  6036.5  279.95  6249.3  282.63  6319.1  284.65  6479.8  288.83
#Mann= 9 ,-1 , 0
  3998.7     .07       0  4485.7     .12       0    4927      .1       0
  4994.5     .05       0  5017.5      .1       0  5649.1     .07       0
  6036.5     .05       0  6249.3    .035       0  6319.1     .05       0
Bank Sta=4994.5,5017.5
XS Rating Curve= 0 ,0
Exp/Cntr=0.3,0.1

Type RM Length L Ch R = 1 ,7296    ,1049,1049,1049
BEGIN DESCRIPTION:
MOUND CREEK 8.0
END DESCRIPTION:
XS GIS Cut Line= 3
      2395875.29     13634553.44      2397264.37     13634974.08
      2398359.96      13635727.3
#Sta/Elev= 30
  3693.8  299.23  4128.8   276.3  4199.9  275.61  4409.9   267.2  4473.7  266.89
  4487.6  261.48    4498  260.58  4506.6  260.59  4511.9  264.67  4518.9   265.3
  4539.6   263.8  4544.8  265.92  4550.3   260.8  4560.7  261.39  4571.2  264.85
  4571.4  260.19  4571.9  259.69  4594.4  260.19  4615.9   267.3  4968.2  269.15
  4978.7   267.9  4988.5  261.55  4993.7  260.37  5020.4  269.53    5348  265.01
  5523.6  271.89  5883.4  277.27  6272.2  282.22  6346.6  283.77  6474.7  286.11
#Mann= 8 ,-1 , 0
  3693.8     .07       0  4409.9      .1       0  4571.4     .05       0
  4594.4      .1       0  5523.6     .07       0  5883.4     .05       0
  6272.2     .07       0  6346.6     .05       0
Bank Sta=4571.4,4594.4
XS Rating Curve= 0 ,0
Exp/Cntr=0.3,0.1

Type RM Length L Ch R = 1 ,6247    ,781,781,781
BEGIN DESCRIPTION:
MOUND CREEK 7.0
END DESCRIPTION:
XS GIS Cut Line= 3
      2395816.52     13635071.89      2397107.85     13635472.98
      2398174.13      13635962.1
#Sta/Elev= 30
  3794.2  295.24  3923.1  292.15  3955.7  289.38  4128.9     286  4324.6  272.18
  4399.6  268.43  4459.8  263.02    4465  265.29  4472.2   259.6  4472.7   259.1
  4495.2   259.6  4497.6  264.12  4524.9  265.98  4627.9  267.36  4892.1  266.63
  4931.4  268.41    4964  266.52  4969.2   261.4  4975.9  259.66  4996.5  262.46
  5001.8  266.79  5017.7  267.94  5233.9  265.15  5340.7  266.88  5462.3  270.61
  5551.4  270.22  5591.9  272.66  6034.4  285.59    6301   288.3  6319.5   288.5
#Mann= 8 ,-1 , 0
  3794.2     .07       0  4324.6     .12       0  4399.6      .1       0
  4472.2     .05       0  4495.2      .1       0  5233.9     .05       0
  5340.7     .07       0    6301     .05       0
Bank Sta=4472.2,4495.2
XS Rating Curve= 0 ,0
Exp/Cntr=0.3,0.1

Type RM Length L Ch R = 1 ,5466    ,548,548,548
BEGIN DESCRIPTION:
MOUND CREEK 6.0
END DESCRIPTION:
XS GIS Cut Line= 3
      2395975.04     13635725.01        2396375.       13635825.
      2397625.04     13636325.02
#Sta/Elev= 30
  4584.2  285.46  4749.1  277.89  4772.3  277.55  4808.4  274.39  4831.5  273.89
  4890.8  268.64  4898.7  266.79  4986.2  266.48  4999.2  265.74  5005.9  264.81
  5011.3   259.5  5016.1  258.98  5016.6  258.48  5041.5  258.98  5050.3  267.06
  5059.7  267.14    5364  266.26  5471.7  265.05  5520.2     263  5558.6  262.88
  5603.6  264.83  5765.2  263.66  5851.7  264.95  5911.9  267.27  5926.8  267.08
    6032  272.67  6220.2  286.05  6321.2  289.55  6327.9  290.75  6342.8  290.56
#Mann= 7 ,-1 , 0
  4584.2     .07       0  4898.7      .1       0  5016.1     .05       0
  5041.5      .1       0  5558.6     .05       0  5851.7    .035       0
    6032     .05       0
Bank Sta=5016.1,5041.5
XS Rating Curve= 0 ,0
Exp/Cntr=0.3,0.1

Type RM Length L Ch R = 1 ,4918    ,561,561,561
BEGIN DESCRIPTION:
MOUND CREEK 5.0
END DESCRIPTION:
XS GIS Cut Line= 3
      2395875.03     13635825.02        2396425.       13636325.
        2397525.       13636375.
#Sta/Elev= 30
  4256.4  286.39  4341.2  284.06  4412.1  281.33  4440.5  279.46  4489.8  278.65
  4595.9  274.99  4674.3  271.76  4764.7  266.86  4829.7  264.19  4872.3  265.58
  4971.6  265.94  4978.4  265.26  4985.8  261.54  4992.6  260.39    4997  258.81
  4997.5  258.31  5022.4  258.81  5029.7  265.84  5049.7  266.38  5139.8  265.95
  5189.9  263.91  5257.2  263.91    5300  263.76  5370.1  264.86  5500.2  262.91
  5643.5  263.93  5700.4  265.84  5820.7  271.96  5970.7  282.15  6100.8   288.4
#Mann= 7 ,-1 , 0
  4256.4     .07       0  4764.7      .1       0    4997     .05       0
  5022.4      .1       0  5257.2     .05       0  5643.5    .035       0
  5820.7     .05       0
Bank Sta=4997,5022.4
XS Rating Curve= 0 ,0
Exp/Cntr=0.3,0.1

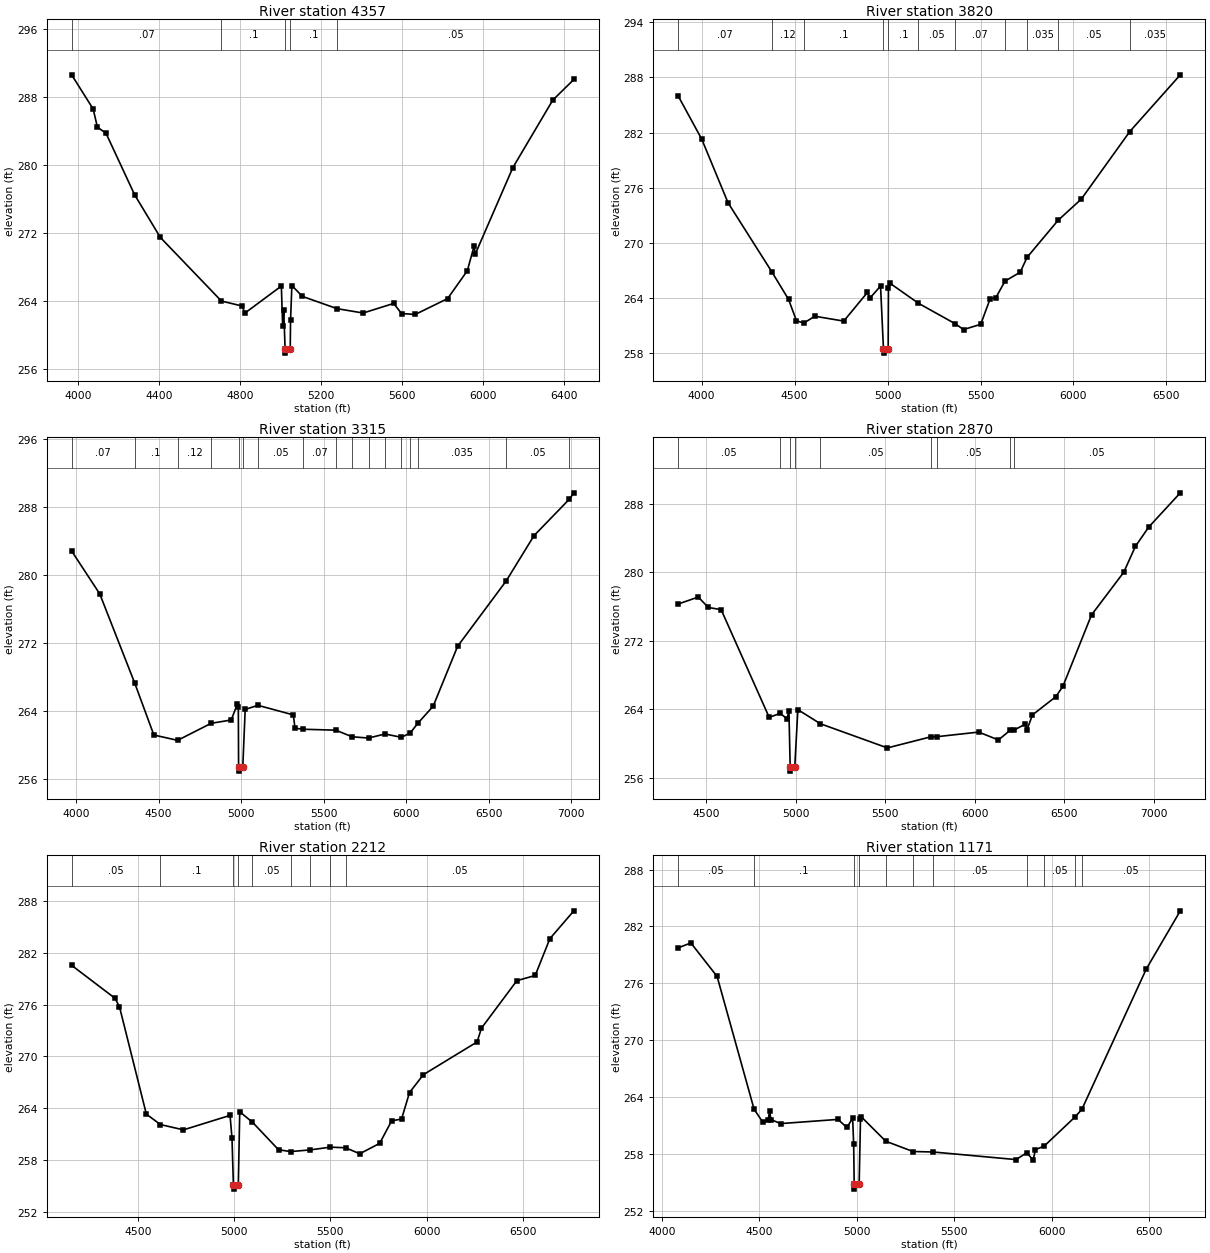
Type RM Length L Ch R = 1 ,4357    ,537,537,537
BEGIN DESCRIPTION:
MOUND CREEK 4.0
END DESCRIPTION:
XS GIS Cut Line= 3
      2395474.97     13636124.97        2396225.       13636825.
      2397625.02     13636424.99
#Sta/Elev= 30
  3968.5  290.64  4074.8  286.61  4095.8  284.47  4138.3  283.75    4280  276.48
    4407  271.46  4708.8  263.96  4810.5  263.38  4824.7  262.54  5004.9  265.73
  5011.4     261  5016.6  262.91  5023.4  258.32  5023.9  257.82  5048.8  258.32
  5050.4  261.69  5056.9  265.79  5108.9  264.51  5280.8  263.06  5409.2  262.55
    5560  263.68    5599  262.49  5666.6  262.38  5826.5  264.25    5924  267.53
  5957.8  270.47    5963  269.48  6148.9  279.69  6346.5  287.66  6450.5  290.09
#Mann= 5 ,-1 , 0
  3968.5     .07       0  4708.8      .1       0  5023.4     .05       0
  5048.8      .1       0  5280.8     .05       0
Bank Sta=5023.4,5048.8
XS Rating Curve= 0 ,0
Exp/Cntr=0.3,0.1

Type RM Length L Ch R = 1 ,3820    ,505,505,505
BEGIN DESCRIPTION:
MOUND CREEK 3.0
END DESCRIPTION:
XS GIS Cut Line= 3
        2395325.       13636525.        2396125.       13637325.
      2397674.99       13637075.
#Sta/Elev= 30
  3873.3     286  4000.6  281.27    4142  274.34  4377.4  266.82  4467.3  263.82
  4509.7   261.5  4548.7  261.23  4608.7  261.98  4764.3  261.45  4891.5  264.57
  4905.7  263.97  4962.2  265.27  4977.8  258.46  4978.3  257.96  5003.2  258.46
  5004.7  265.01  5014.8  265.55  5166.3  263.39  5363.1  261.17  5408.8  260.53
    5501   261.1  5551.7  263.88    5582  263.99  5631.9  265.81  5713.7  266.78
  5750.1  268.39  5917.5  272.44  6041.9  274.74    6303  282.11  6574.7  288.29
#Mann= 11 ,-1 , 0
  3873.3     .07       0  4377.4     .12       0  4548.7      .1       0
  4977.8     .05       0  5003.2      .1       0  5166.3     .05       0
  5363.1     .07       0  5631.9     .05       0  5750.1    .035       0
  5917.5     .05       0    6303    .035       0
Bank Sta=4977.8,5003.2
XS Rating Curve= 0 ,0
Exp/Cntr=0.3,0.1

Type RM Length L Ch R = 1 ,3315    ,445,445,445
BEGIN DESCRIPTION:
MOUND CREEK 2.0
END DESCRIPTION:
XS GIS Cut Line= 3
      2395125.03     13636825.04        2395775.       13637625.
        2397775.       13637425.
#Sta/Elev= 30
  3974.1  282.83  4144.3  277.77  4356.8  267.21  4471.8  261.13  4615.7   260.5
  4818.8  262.51  4940.4   262.9  4976.8  264.76  4983.3  264.46  4984.9  257.37
  4985.4  256.87  5010.3  257.37  5024.9  264.15  5102.1  264.63  5316.4   263.5
  5326.4  261.93    5375  261.81  5573.4   261.7  5672.5  260.92  5771.7  260.77
  5870.9  261.25  5970.1  260.86  6023.4  261.35  6069.2  262.49  6163.1  264.53
  6311.3   271.6  6605.6  279.31  6773.6  284.64  6987.6  288.94  7014.8  289.69
#Mann= 17 ,-1 , 0
  3974.1     .07       0  4356.8      .1       0  4615.7     .12       0
  4818.8      .1       0  4984.9     .05       0  5010.3      .1       0
  5102.1     .05       0    5375     .07       0  5573.4     .05       0
  5672.5     .12       0  5771.7     .07       0  5870.9     .05       0
  5970.1    .035       0  6023.4     .07       0  6069.2    .035       0
  6605.6     .05       0  6987.6    .035       0
Bank Sta=4984.9,5010.3
XS Rating Curve= 0 ,0
Exp/Cntr=0.3,0.1

Type RM Length L Ch R = 1 ,2870    ,658,658,658
BEGIN DESCRIPTION:
B19620
END DESCRIPTION:
XS GIS Cut Line= 4
      2395063.36     13637801.22      2395268.75     13637947.93
      2396080.69     13637928.37      2397820.98     13637918.59
#Sta/Elev= 30
  4342.5  276.31  4454.9  277.13  4511.4  275.91  4582.7  275.66  4851.2  263.08
  4912.4  263.54  4951.3  262.91  4961.3  263.88  4968.5   257.3    4969   256.8
    4994   257.3  5011.3  263.98  5137.5  262.33  5511.4  259.51  5752.7   260.8
  5787.4  260.82  6021.4  261.36  6131.4  260.44  6195.9  261.55  6218.7  261.59
  6281.4  262.29  6291.4  261.64  6321.4  263.36  6451.4  265.48  6491.4  266.69
  6651.4  275.04  6831.4  280.02  6896.7  283.05  6971.4  285.31  7147.4   289.3
#Mann= 9 ,-1 , 0
  4342.5     .05       0  4912.4      .1       0  4968.5     .05       0
    4994      .1       0  5137.5     .05       0  5752.7     .12       0
  5787.4     .05       0  6195.9    .035       0  6218.7     .05       0
Bank Sta=4968.5,4994
XS Rating Curve= 0 ,0
Exp/Cntr=0.3,0.1

Type RM Length L Ch R = 1 ,2212    ,1041,1041,1041
BEGIN DESCRIPTION:
B19619
END DESCRIPTION:
XS GIS Cut Line= 3
      2395288.35     13638202.28      2396403.51     13638339.23
       2397841.5     13638710.96
#Sta/Elev= 30
  4156.6  280.53    4382  276.72  4405.1  275.74  4544.6  263.34  4617.9  262.13
  4737.6  261.52  4979.4  263.19  4989.5  260.58  4996.9  255.17  4997.4  254.67
  5022.4  255.17  5029.8  263.61    5096   262.4  5231.3  259.22  5293.8  259.01
  5394.7   259.2  5500.5  259.52  5579.3  259.45  5653.5  258.76  5756.8  259.96
  5818.8  262.56  5870.4  262.77  5911.7  265.83    5984   267.9  6262.9  271.68
  6285.4  273.27  6469.5  278.76  6564.7  279.36  6640.8  283.61  6765.4  286.83
#Mann= 9 ,-1 , 0
  4156.6     .05       0  4617.9      .1       0  4996.9     .05       0
  5022.4      .1       0    5096     .05       0  5293.8      .1       0
  5394.7     .05       0  5500.5     .07       0  5579.3     .05       0
Bank Sta=4996.9,5022.4
XS Rating Curve= 0 ,0
Exp/Cntr=0.3,0.1

Type RM Length L Ch R = 1 ,1171    ,893,893,893
BEGIN DESCRIPTION:
B19618
END DESCRIPTION:
XS GIS Cut Line= 4
      2395317.66     13638309.89      2395708.96     13638750.09
       2396188.3     13638877.27      2397596.99      13639366.4
#Sta/Elev= 30
  4083.2  279.75  4148.6  280.27  4283.2  276.74  4473.1  262.75  4517.4  261.41
    4545  261.58  4552.5  262.59  4559.2  261.67  4609.3  261.25  4903.3  261.69
  4948.7  260.84  4978.5   261.8  4983.7  259.09  4986.4  254.85  4986.9  254.35
  5011.9  254.85  5018.7  261.74  5023.9  261.94  5148.6  259.39  5288.2  258.31
  5391.3  258.26  5816.1  257.46  5872.7  258.19  5904.2  257.39  5916.2  258.51
  5961.1  258.88  6120.9  261.98  6154.8  262.77  6484.9  277.53  6659.3  283.65
#Mann= 11 ,-1 , 0
  4083.2     .05       0  4473.1      .1       0  4986.4     .05       0
  5011.9      .1       0  5148.6     .05       0  5288.2     .07       0
  5391.3     .05       0  5872.7     .07       0  5961.1     .05       0
  6120.9     .07       0  6154.8     .05       0
Bank Sta=4986.4,5011.9
XS Rating Curve= 0 ,0
Exp/Cntr=0.3,0.1