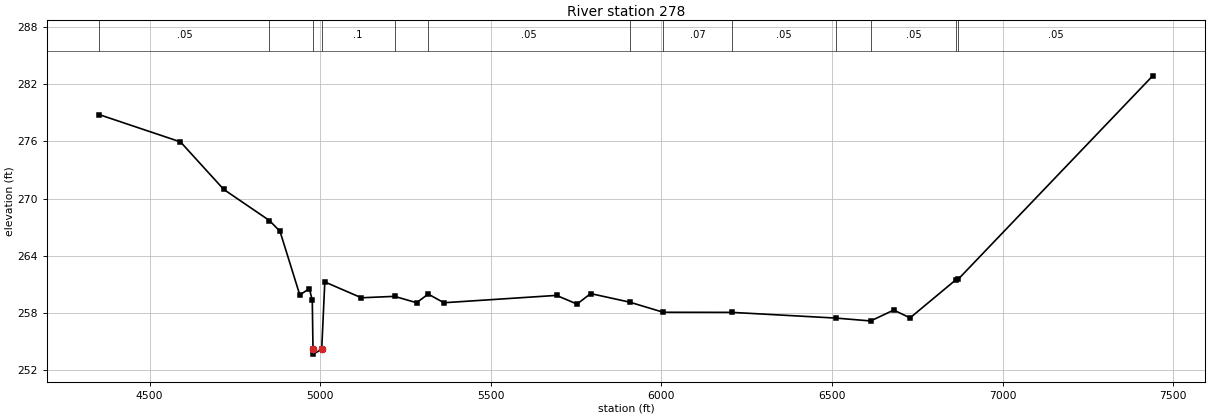
HEC-RAS study MOUND CREEK.prj: MOUND CREEK Base Level Engineering

--- MOUND CREEK.g01 (geometry) --- (continued)

Type RM Length L Ch R = 1 ,278     ,0,0,0
BEGIN DESCRIPTION:
B19617
END DESCRIPTION:
XS GIS Cut Line= 5
      2395268.75     13638349.01      2395200.27      13638857.7
      2395356.79     13639112.04      2396276.34     13639102.26
      2397577.43     13639483.78
#Sta/Elev= 30
  4352.3   278.8  4590.4  275.94  4717.1  270.96  4851.2  267.69  4882.1  266.56
  4940.1  259.89  4968.1  260.55  4976.7  259.32  4978.8  254.18  4979.3  253.68
  5004.3  254.18  5013.4  261.25  5120.7  259.59    5218  259.74  5282.4  259.07
  5316.4  259.98  5362.4  259.07  5692.5  259.84  5752.5  258.93  5792.5  260.03
    5907  259.13  6005.4  258.07  6206.2  258.06  6511.2  257.46  6612.9  257.16
  6680.8   258.3  6728.5  257.48  6863.2  261.49  6870.3  261.56  7439.7  282.87
#Mann= 13 ,-1 , 0
  4352.3     .05       0  4851.2      .1       0  4978.8     .05       0
  5004.3      .1       0    5218     .07       0  5316.4     .05       0
    5907      .1       0  6005.4     .07       0  6206.2     .05       0
  6511.2      .1       0  6612.9     .05       0  6863.2     .07       0
  6870.3     .05       0
Bank Sta=4978.8,5004.3
XS Rating Curve= 0 ,0
Exp/Cntr=0.3,0.1

Chan Stop Cuts=-1
Use User Specified Reach Order=0
Composite Channel Slope=5