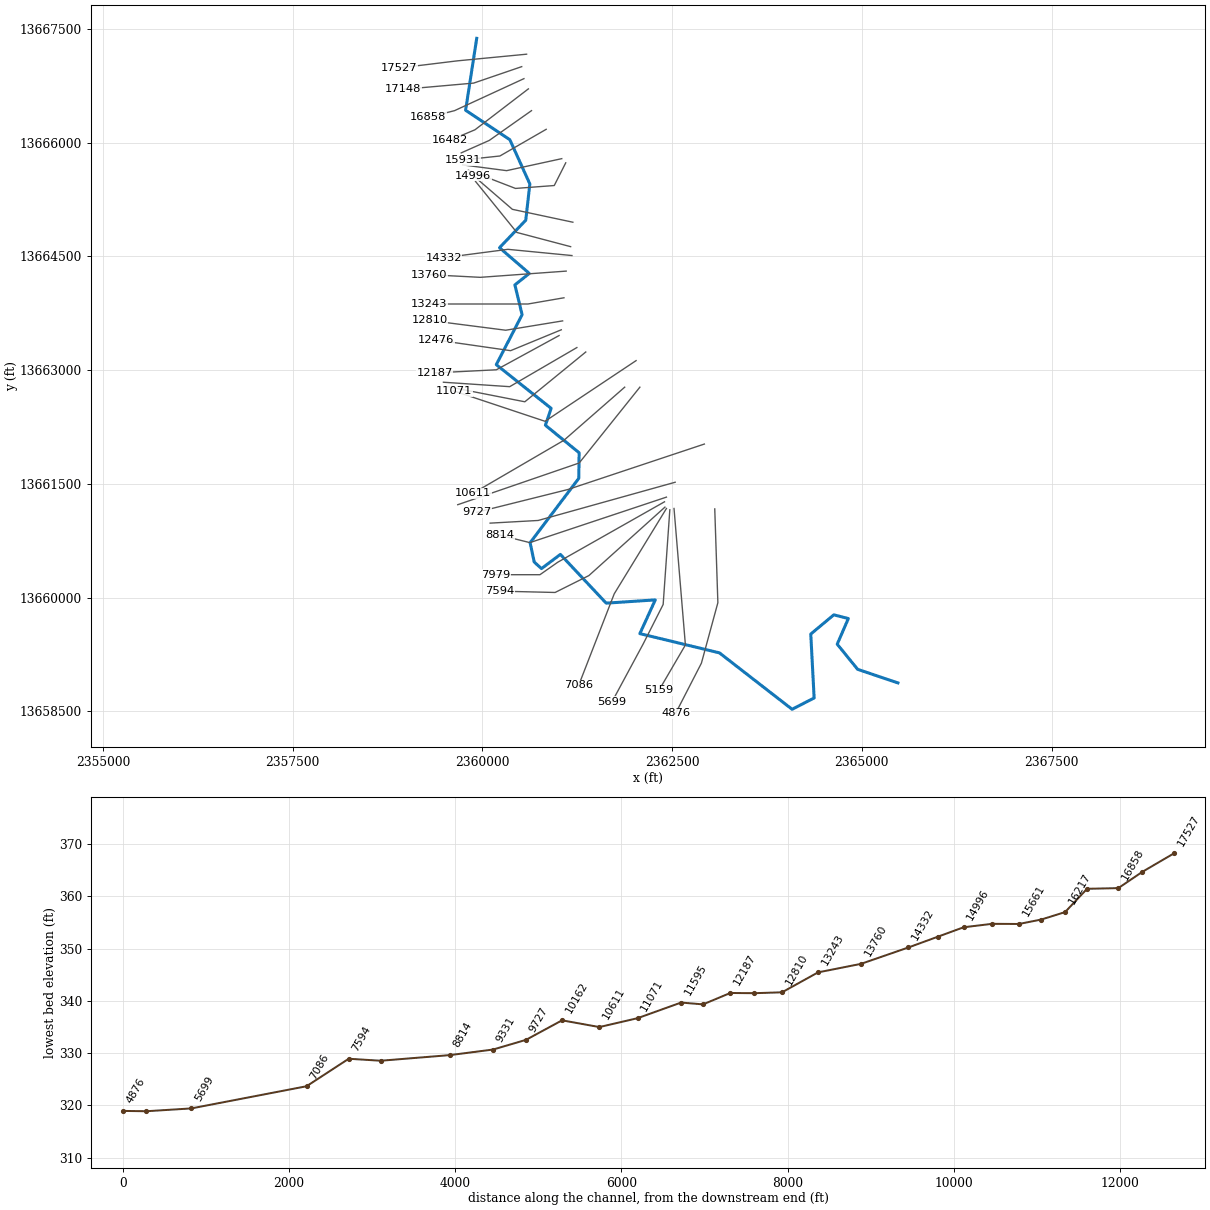
--- MURRAY BRANCH.prj (project) ---

Proj Title=MURRAY BRANCH Base Level Engineering
Current Plan=p01
Default Exp/Contr=0.3,0.1
English Units
Geom File=g01
Flow File=f01
Plan File=p01
Y Axis Title=Elevation
X Axis Title(PF)=Main Channel Distance
X Axis Title(XS)=Station
BEGIN DESCRIPTION:
MURRAY BRANCH
END DESCRIPTION:
DSS Export Rating Curves= 0
DSS Export Rating Curve Sorted= 0
DSS Export Volume Flow Curves= 0
DXF OffsetX= 0
DXF OffsetY= 0
DXF ScaleX= 1
DXF ScaleY= 10

--- MURRAY BRANCH.p01 (plan) ---

Plan Title=Multiple Run
Short Identifier=Multiple
Geom File=g01
Flow File=f01
Subcritical Flow
K Sum by GR= 0
Std Step Tol= 0.01
Critical Tol= 0.01
Num of Std Step Trials= 20
Max Error Tol= 0.3
Flow Tol Ratio= 0.001
Split Flow NTrial= 30
Split Flow Tol= 0.02
Split Flow Ratio= 0.02
Log Output Level= 0
Friction Slope Method= 1
Unsteady Friction Slope Method= 2
Unsteady Bridges Friction Slope Method= 1
Parabolic Critical Depth
Global Vel Dist=  1 , 1 , 1
Global Log Level= 0
CheckData=True
Encroach Param= -1, 0, 0, 0
BEGIN DESCRIPTION:
Multiple Run
END DESCRIPTION:

--- MURRAY BRANCH.f01 (steady flow) ---

Flow Title=Multiple
Number of Profiles=7
Profile Names=10-year,25-year,50-year,1pct_min,100-year,1pct_plu,500-year
River Rch & RM= MURRAY BRANCH,Reach-1,17527
     720    1177    1594    1045    2085    4161    3539
River Rch & RM= MURRAY BRANCH,Reach-1,17148
     798    1310    1780    1170    2334    4656    3979
River Rch & RM= MURRAY BRANCH,Reach-1,14332
    1486    2515    3487    2333    4655    9289    8237
River Rch & RM= MURRAY BRANCH,Reach-1,7086
    2648    4560    6393    4317    8614   17187   15522
Boundary for River Rch & Prof#=MURRAY BRANCH,Reach-1,1
Up Type=0
Dn Type=3
Dn Slope=0.005
Boundary for River Rch & Prof#=MURRAY BRANCH,Reach-1,2
Up Type=0
Dn Type=3
Dn Slope=0.005
Boundary for River Rch & Prof#=MURRAY BRANCH,Reach-1,3
Up Type=0
Dn Type=3
Dn Slope=0.005
Boundary for River Rch & Prof#=MURRAY BRANCH,Reach-1,4
Up Type=0
Dn Type=3
Dn Slope=0.005
Boundary for River Rch & Prof#=MURRAY BRANCH,Reach-1,5
Up Type=0
Dn Type=3
Dn Slope=0.005
Boundary for River Rch & Prof#=MURRAY BRANCH,Reach-1,6
Up Type=0
Dn Type=3
Dn Slope=0.005
Boundary for River Rch & Prof#=MURRAY BRANCH,Reach-1,7
Up Type=0
Dn Type=3
Dn Slope=0.005

--- MURRAY BRANCH.g01 (geometry) ---

Geom Title=Existing Conditions
Program Version=4.10

River Reach=MURRAY BRANCH   ,Reach-1
Reach XY= 30
        2359925.       13667375.      2359778.54     13666426.46
      2360361.63     13666038.32      2360625.06     13665455.01
      2360571.25     13664976.55      2360225.53     13664614.31
      2360618.01     13664274.78      2360428.12     13664123.38
      2360523.11     13663730.71      2360182.79     13663071.57
      2360905.74     13662495.47      2360830.06      13662272.7
      2361274.69     13661909.98      2361269.91      13661572.7
      2360628.67     13660723.42      2360682.86     13660468.79
      2360778.34     13660382.58      2361027.42     13660569.59
      2361630.89     13659926.96      2362277.99     13659969.61
        2362075.       13659525.      2363123.45     13659271.25
      2364080.96     13658527.14      2364371.47     13658676.45
      2364326.89     13659519.29      2364630.86     13659772.95
      2364821.97     13659723.61      2364675.55     13659385.64
      2364944.41     13659054.33        2365475.       13658875.

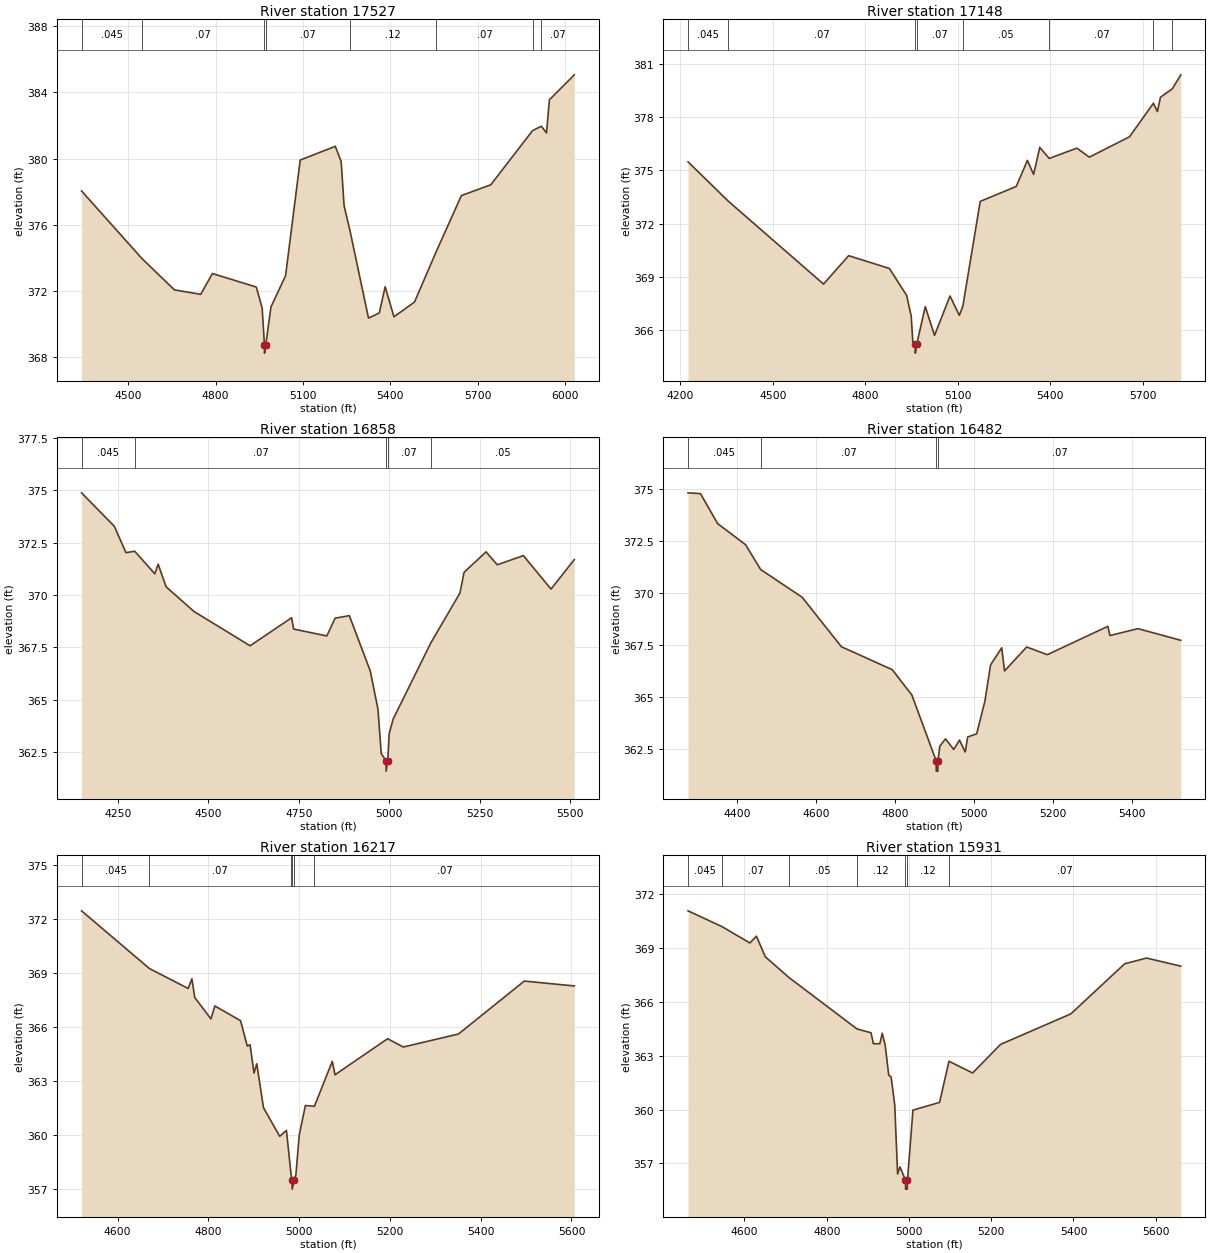
Type RM Length L Ch R = 1 ,17527   ,379,379,379
BEGIN DESCRIPTION:
B19728
END DESCRIPTION:
XS GIS Cut Line= 3
      2360582.45     13667165.81      2359668.04     13667077.89
      2358900.17      13666984.1
#Sta/Elev= 30
  4339.7  378.04  4546.9  373.95  4658.6  372.05    4749  371.78  4789.2  373.04
  4939.9  372.22    4960  370.94  4967.8  368.72  4968.1  368.22  4972.3  368.72
  4990.1  371.01  5040.4  372.91  5090.6  379.91  5211.1  380.74  5231.2  379.82
  5241.3  377.14  5261.7  375.62  5325.1  370.34  5362.1  370.65  5382.3  372.24
  5412.5  370.42    5483  371.31  5558.1  374.38  5644.2  377.76    5745  378.41
  5888.4  381.69  5918.6  381.96  5936.4  381.55  5946.4  383.56  6031.9  385.07
#Mann= 8 ,-1 , 0
  4339.7    .045       0  4546.9     .07       0  4967.8     .05       0
  4972.3     .07       0  5261.7     .12       0  5558.1     .07       0
  5888.4    .035       0  5918.6     .07       0
Bank Sta=4967.8,4972.3
XS Rating Curve= 0 ,0
Exp/Cntr=0.3,0.1

Type RM Length L Ch R = 1 ,17148   ,290,290,290
BEGIN DESCRIPTION:
B19727
END DESCRIPTION:
XS GIS Cut Line= 3
      2360517.97      13667001.7      2359884.91     13666784.82
      2358959.42     13666702.81
#Sta/Elev= 30
    4225  375.48  4355.1  373.27  4664.5  368.59  4746.1  370.19  4878.2  369.47
  4934.2  367.95    4949  366.78  4954.3   365.3    4962   365.2  4962.3   364.7
  4966.8   365.2  4994.5  367.32  5024.6   365.7  5074.8  367.92  5104.9  366.83
  5116.3  367.33  5172.8  373.25  5289.7  374.09  5325.8  375.56  5345.9  374.77
  5365.9  376.29  5396.5  375.67  5486.4  376.25  5526.6  375.74  5657.1  376.89
  5734.6  378.78  5747.4  378.31  5757.5  379.12  5795.9  379.59  5823.3  380.38
#Mann= 8 ,-1 , 0
    4225    .045       0  4355.1     .07       0    4962     .05       0
  4966.8     .07       0  5116.3     .05       0  5396.5     .07       0
  5734.6    .035       0  5795.9     .07       0
Bank Sta=4962,4966.8
XS Rating Curve= 0 ,0
Exp/Cntr=0.3,0.1

Type RM Length L Ch R = 1 ,16858   ,376,376,376
BEGIN DESCRIPTION:
B19726
END DESCRIPTION:
XS GIS Cut Line= 3
      2360547.23     13666843.42      2359632.87     13666421.41
      2359288.57     13666333.88
#Sta/Elev= 30
  4149.1  374.88  4239.7  373.28  4271.9  372.02    4296  372.09  4351.7  371.01
  4360.8  371.47  4382.8  370.39  4459.9  369.21  4615.1  367.57  4729.9  368.91
  4735.4  368.37  4827.2  368.04  4850.1  368.89  4889.5  369.01  4947.4  366.36
  4968.6  364.54  4977.6  362.42  4990.9  362.08  4991.2  361.58  4995.7  362.08
  4999.6  363.37  5010.6  364.07  5114.5   367.7  5195.2  370.09  5206.6  371.08
  5267.4  372.06  5298.4  371.44  5370.6  371.88    5447  370.28  5511.4  371.69
#Mann= 5 ,-1 , 0
  4149.1    .045       0    4296     .07       0  4990.9     .05       0
  4995.7     .07       0  5114.5     .05       0
Bank Sta=4990.9,4995.7
XS Rating Curve= 0 ,0
Exp/Cntr=0.3,0.1

Type RM Length L Ch R = 1 ,16482   ,265,265,265
BEGIN DESCRIPTION:
B19725
END DESCRIPTION:
XS GIS Cut Line= 3
      2360605.89     13666708.64       2359902.5     13666169.37
      2359568.43     13666028.71
#Sta/Elev= 30
  4274.7  374.81  4306.3  374.77  4349.9  373.33  4420.6  372.32  4458.7  371.13
  4563.8   369.8  4663.5  367.42  4792.3  366.32  4842.1   365.1  4903.5  361.95
  4903.8  361.45  4907.9  361.45  4908.3  361.95  4912.8  362.65  4927.3     363
  4948.1  362.49  4962.7  362.94  4977.2  362.37  4983.5  363.09  5006.2  363.24
    5027   364.8  5041.5  366.55  5069.7  367.37  5076.9  366.26    5133  367.41
  5185.3  367.04  5338.6   368.4    5344  367.96  5415.2  368.29  5523.5  367.73
#Mann= 4 ,-1 , 0
  4274.7    .045       0  4458.7     .07       0  4903.5     .05       0
  4908.3     .07       0
Bank Sta=4903.5,4908.3
XS Rating Curve= 0 ,0
Exp/Cntr=0.3,0.1

Type RM Length L Ch R = 1 ,16217   ,286,286,286
BEGIN DESCRIPTION:
B19724
END DESCRIPTION:
XS GIS Cut Line= 3
       2360646.9     13666421.41      2360090.06     13666028.69
      2359720.78     13665864.57
#Sta/Elev= 30
  4520.8  372.44  4670.1  369.24  4755.6  368.13  4763.9  368.67  4770.1  367.63
  4805.8  366.44  4814.4  367.16  4871.1  366.34  4885.9  364.93    4892  365.01
  4900.7  363.43  4906.8  363.95  4921.6  361.51  4957.3  359.92  4972.1  360.25
  4982.3  357.82  4984.4  357.49  4984.8  356.99  4989.3  357.49    4993  357.79
  5000.4     360  5013.9  361.63  5033.8  361.59  5073.1  364.08  5079.2  363.34
    5195  365.34  5229.6  364.88  5351.1   365.6  5496.1  368.54  5606.3  368.27
#Mann= 6 ,-1 , 0
  4520.8    .045       0  4670.1     .07       0  4982.3     .12       0
  4984.4     .05       0  4989.3     .12       0  5033.8     .07       0
Bank Sta=4984.4,4989.3
XS Rating Curve= 0 ,0
Exp/Cntr=0.3,0.1

Type RM Length L Ch R = 1 ,15931   ,270,270,270
BEGIN DESCRIPTION:
B19723
END DESCRIPTION:
XS GIS Cut Line= 3
      2360840.35     13666175.24      2360230.73     13665823.54
      2359739.23     13665770.88
#Sta/Elev= 30
  4462.8  371.07  4545.5  370.19  4613.3  369.28  4629.1  369.66  4650.7  368.51
    4708  367.36  4873.8  364.49  4907.7  364.28  4913.5  363.67  4929.3  363.67
    4935  364.25  4942.3  363.57  4950.8  361.92  4956.6  361.82  4965.4  360.27
  4972.4  356.41  4978.1  356.81  4991.5  356.07  4991.8  355.57    4996  355.57
  4996.4  356.07  5009.7  359.97  5074.4   360.4  5097.3  362.69  5154.8  362.04
  5222.6  363.63  5393.6  365.33  5524.4  368.12  5577.5  368.44  5660.9  367.99
#Mann= 7 ,-1 , 0
  4462.8    .045       0  4545.5     .07       0    4708     .05       0
  4873.8     .12       0  4991.5     .05       0  4996.4     .12       0
  5097.3     .07       0
Bank Sta=4991.5,4996.4
XS Rating Curve= 0 ,0
Exp/Cntr=0.3,0.1

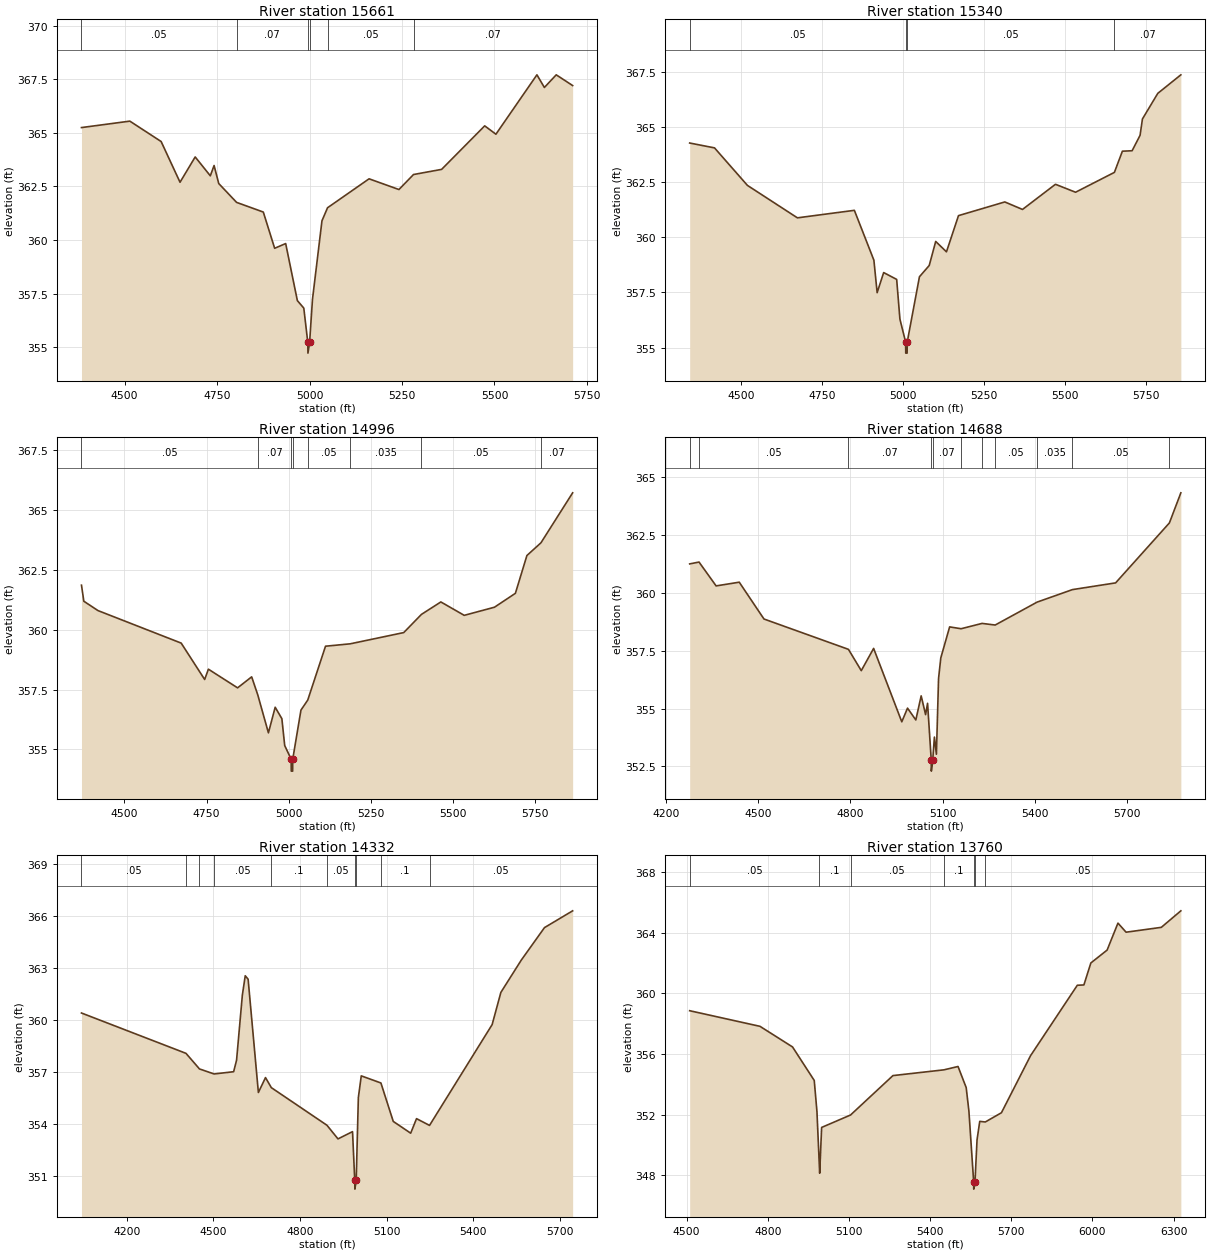
Type RM Length L Ch R = 1 ,15661   ,321,321,321
BEGIN DESCRIPTION:
B19722
END DESCRIPTION:
XS GIS Cut Line= 3
      2361045.43     13665788.37      2360318.66     13665630.12
      2359739.23      13665706.2
#Sta/Elev= 30
  4383.2  365.24    4514  365.54  4598.6  364.59  4649.7  362.69  4690.7  363.87
  4731.6  362.99  4741.8  363.47  4754.4  362.63  4802.7  361.75  4874.9   361.3
  4905.6  359.61  4935.4  359.83    4967  357.17  4984.4  356.82  4995.2  355.22
  4995.6  354.72  5000.1  355.22  5007.9  357.23  5033.5  360.89  5048.6   361.5
  5160.9  362.85  5241.6  362.35  5281.1  363.05  5357.1  363.29  5473.6  365.32
  5503.9  364.93  5614.8   367.7    5635  367.11    5667   367.7  5711.4   367.2
#Mann= 6 ,-1 , 0
  4383.2     .05       0  4802.7     .07       0  4995.2     .05       0
  5000.1     .07       0  5048.6     .05       0  5281.1     .07       0
Bank Sta=4995.2,5000.1
XS Rating Curve= 0 ,0
Exp/Cntr=0.3,0.1

Type RM Length L Ch R = 1 ,15340   ,344,344,344
BEGIN DESCRIPTION:
B19721
END DESCRIPTION:
XS GIS Cut Line= 4
      2361098.03     13665733.31      2360946.76     13665433.98
      2360435.88     13665395.66      2359814.53     13665635.99
#Sta/Elev= 30
  4342.4  364.27  4418.9  364.05  4520.4  362.35  4674.4  360.88    4850  361.22
  4910.2  358.96  4920.2  357.49  4940.3   358.4  4980.4  358.09  4990.4  356.29
    5008  355.25  5008.4  354.75  5012.6  354.75  5012.9  355.25  5050.6  358.21
  5080.7  358.72  5100.7  359.81  5133.9  359.34  5170.9  360.98  5313.7   361.6
  5368.2  361.26  5469.8   362.4  5531.8  362.04  5651.5  362.94  5676.1   363.9
  5706.1  363.92  5730.6  364.62  5737.9  365.36  5785.2  366.52  5856.3  367.36
#Mann= 4 ,-1 , 0
  4342.4     .05       0    5008     .05       0  5012.9     .05       0
  5651.5     .07       0
Bank Sta=5008,5012.9
XS Rating Curve= 0 ,0
Exp/Cntr=0.3,0.1

Type RM Length L Ch R = 1 ,14996   ,308,308,308
BEGIN DESCRIPTION:
B19720
END DESCRIPTION:
XS GIS Cut Line= 3
      2361191.99      13664950.2      2360394.85     13665120.17
       2359879.5     13665565.25
#Sta/Elev= 30
  4369.2  361.86  4376.4  361.19  4419.3   360.8  4672.9  359.44  4744.4  357.92
  4755.8  358.35  4844.7  357.57  4887.6  358.03  4906.1  357.28  4938.6  355.69
  4959.2  356.76  4979.6  356.28  4988.2  355.16  5007.8  354.59  5008.2  354.09
  5012.4  354.09  5012.7  354.59  5037.7  356.64  5058.4  357.06  5112.5  359.31
  5187.7  359.41  5350.8  359.88  5404.7  360.64  5463.8  361.16    5535   360.6
  5627.2  360.94  5690.8  361.52  5725.9   363.1  5768.6  363.63  5865.2  365.72
#Mann= 8 ,-1 , 0
  4369.2     .05       0  4906.1     .07       0  5007.8     .05       0
  5012.7     .07       0  5058.4     .05       0  5187.7    .035       0
  5404.7     .05       0  5768.6     .07       0
Bank Sta=5007.8,5012.7
XS Rating Curve= 0 ,0
Exp/Cntr=0.3,0.1

Type RM Length L Ch R = 1 ,14688   ,356,356,356
BEGIN DESCRIPTION:
B19719
END DESCRIPTION:
XS GIS Cut Line= 3
      2361162.66     13664627.82      2360453.47     13664815.38
      2359909.16     13665488.45
#Sta/Elev= 30
  4276.7  361.25  4307.1  361.33  4362.8   360.3  4438.1  360.46  4518.6  358.87
  4793.6  357.56  4835.4  356.64  4875.6   357.6  4967.3  354.43    4986  355.02
    5013  354.51  5030.4  355.55  5044.8  354.74  5051.2  355.23  5063.1   352.8
  5063.5   352.3  5068.1   352.8  5073.5  353.77    5080  353.03    5087   356.3
  5094.3  357.19  5123.1  358.53  5160.4  358.45  5228.6  358.68  5271.4  358.61
  5407.9   359.6  5522.9  360.14  5663.5  360.43  5838.6  363.02  5875.9  364.32
#Mann= 11 ,-1 , 0
  4276.7    .035       0  4307.1     .05       0  4793.6     .07       0
  5063.1     .05       0  5068.1     .07       0  5160.4     .05       0
  5228.6    .035       0  5271.4     .05       0  5407.9    .035       0
  5522.9     .05       0  5838.6     .07       0
Bank Sta=5063.1,5068.1
XS Rating Curve= 0 ,0
Exp/Cntr=0.3,0.1

Type RM Length L Ch R = 1 ,14332   ,572,572,572
BEGIN DESCRIPTION:
MURRAY BRANCH 14.0
END DESCRIPTION:
XS GIS Cut Line= 3
      2361180.24     13664510.59      2360336.24     13664592.65
      2359488.17     13664481.52
#Sta/Elev= 30
  4042.2   360.4  4404.7  358.07  4451.4  357.17  4502.2  356.88  4569.9  357.01
    4580  357.67  4600.1  361.43  4610.1  362.55  4620.1  362.35  4655.7  355.81
  4680.4  356.67  4700.6  356.09  4893.4  353.92  4931.8  353.13  4982.2  353.55
  4989.9  350.73  4990.3  350.23  4994.9  350.73  5002.4  355.52  5012.5  356.77
  5080.6  356.36  5123.4  354.14  5183.9  353.46  5204.1   354.3  5249.2  353.91
  5466.3  359.73  5496.6  361.59  5567.2  363.45  5647.8  365.33  5745.5   366.3
#Mann= 10 ,-1 , 0
  4042.2     .05       0  4404.7      .1       0  4451.4     .07       0
  4502.2     .05       0  4700.6      .1       0  4893.4     .05       0
  4989.9     .05       0  4994.9     .05       0  5080.6      .1       0
  5249.2     .05       0
Bank Sta=4989.9,4994.9
XS Rating Curve= 0 ,0
Exp/Cntr=0.3,0.1

Type RM Length L Ch R = 1 ,13760   ,517,517,517
BEGIN DESCRIPTION:
MURRAY BRANCH 13.0
END DESCRIPTION:
XS GIS Cut Line= 3
       2361104.1     13664305.44      2359972.83     13664223.38
      2359292.88     13664258.55
#Sta/Elev= 30
  4511.6  358.86  4771.4  357.83  4891.7  356.47  4971.9  354.26  4981.9  352.21
  4990.7  348.66    4992  348.14  4999.2  351.16  5106.1  351.98  5262.7  354.58
  5451.5  354.96  5503.3  355.18  5533.4  353.79  5543.4  352.25    5561  347.59
  5561.3  347.09    5566  347.59  5573.5  350.34  5583.5  351.56  5604.1  351.52
  5663.7  352.13  5771.5   355.9  5944.1  360.54  5968.4  360.56  5994.1  362.01
  6054.2  362.86  6094.3  364.64  6124.3  364.04  6254.5  364.36  6326.7  365.45
#Mann= 7 ,-1 , 0
  4511.6     .05       0  4990.7      .1       0  5106.1     .05       0
  5451.5      .1       0    5561     .05       0    5566      .1       0
  5604.1     .05       0
Bank Sta=5561,5566
XS Rating Curve= 0 ,0
Exp/Cntr=0.3,0.1

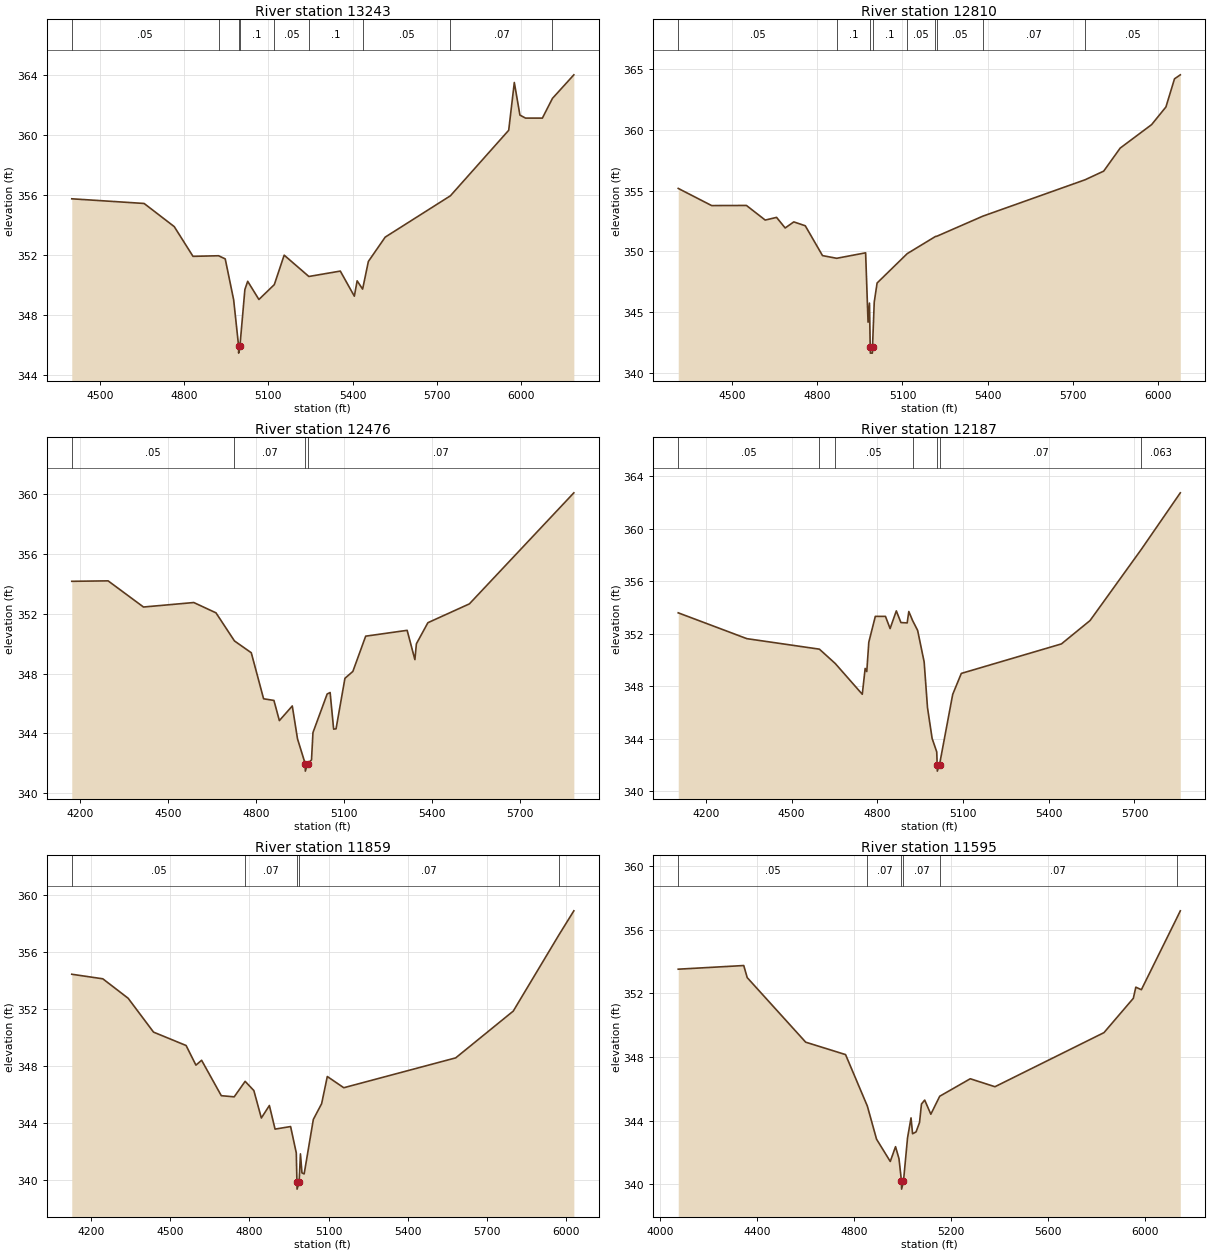
Type RM Length L Ch R = 1 ,13243   ,433,433,433
BEGIN DESCRIPTION:
MURRAY BRANCH 12.0
END DESCRIPTION:
XS GIS Cut Line= 3
      2361074.75     13663953.75        2360600.     13663871.69
      2359292.88     13663871.69
#Sta/Elev= 30
  4399.6  355.73  4657.3  355.42  4764.7  353.88  4831.6   351.9  4922.7  351.94
  4946.4  351.73  4976.4  349.01  4993.9  345.96  4994.2  345.46  4998.9  345.96
  5016.4  349.69  5026.4  350.24  5066.4  349.03  5121.3  350.02  5156.4  351.98
  5244.4  350.56  5356.4  350.92  5406.4  349.25  5416.4  350.27  5435.9  349.72
  5456.4  351.56  5516.4  353.18  5748.7  355.93  5956.4  360.29  5976.4  363.47
  5996.4   361.3  6016.4   361.1  6076.4   361.1  6112.2  362.41  6188.5  363.98
#Mann= 9 ,-1 , 0
  4399.6     .05       0  4922.7      .1       0  4993.9     .05       0
  4998.9      .1       0  5121.3     .05       0  5244.4      .1       0
  5435.9     .05       0  5748.7     .07       0  6112.2     .05       0
Bank Sta=4993.9,4998.9
XS Rating Curve= 0 ,0
Exp/Cntr=0.3,0.1

Type RM Length L Ch R = 1 ,12810   ,334,334,334
BEGIN DESCRIPTION:
B19718
END DESCRIPTION:
XS GIS Cut Line= 3
      2361057.18     13663648.96      2360306.93     13663525.87
      2359304.67     13663654.81
#Sta/Elev= 30
  4309.2  355.18  4427.1  353.77  4549.7  353.78    4616  352.58    4656   352.8
  4686.4  351.93  4716.8  352.43  4757.3  352.11  4818.1  349.66  4868.1  349.44
  4970.1  349.89  4978.7  344.19  4983.7  345.76  4986.3  342.15  4986.8  341.65
  4993.9  341.65  4994.4  342.15  5000.5  345.84  5010.6  347.41  5116.7  349.82
  5216.3  351.23  5221.2  351.25  5383.5   352.9  5744.2  355.89  5809.8   356.6
  5867.9  358.49  5978.8  360.42  6029.3  361.87  6059.5  364.18    6080  364.51
#Mann= 9 ,-1 , 0
  4309.2     .05       0  4868.1      .1       0  4986.3     .05       0
  4994.4      .1       0  5116.7     .05       0  5216.3     .07       0
  5221.2     .05       0  5383.5     .07       0  5744.2     .05       0
Bank Sta=4986.3,4994.4
XS Rating Curve= 0 ,0
Exp/Cntr=0.3,0.1

Type RM Length L Ch R = 1 ,12476   ,289,289,289
BEGIN DESCRIPTION:
B19717
END DESCRIPTION:
XS GIS Cut Line= 3
      2361039.59     13663531.72      2360371.41     13663256.24
       2359392.5     13663396.92
#Sta/Elev= 30
  4171.3  354.18  4295.2  354.21  4415.8  352.46  4587.3  352.76    4663  352.07
    4726  350.19  4783.3   349.4  4825.3  346.32  4860.5  346.21  4879.1  344.86
  4923.1  345.84  4940.9  343.64  4967.1  341.98  4967.6  341.48  4975.3  341.98
  4988.6  342.23  4993.6  344.06    5042  346.64  5052.1  346.74  5064.1  344.29
  5072.3  344.31  5102.6  347.69  5129.6  348.15  5173.3  350.51  5314.7   350.9
  5341.1  348.94  5346.2     350  5385.4  351.41  5526.9  352.67    5883   360.1
#Mann= 4 ,-1 , 0
  4171.3     .05       0    4726     .07       0  4967.1     .05       0
  4975.3     .07       0
Bank Sta=4967.1,4975.3
XS Rating Curve= 0 ,0
Exp/Cntr=0.3,0.1

Type RM Length L Ch R = 1 ,12187   ,328,328,328
BEGIN DESCRIPTION:
B19716
END DESCRIPTION:
XS GIS Cut Line= 3
      2361010.31     13663455.53      2360183.84      13663004.2
      2359369.55     13662963.19
#Sta/Elev= 30
  4103.4  353.59  4343.7  351.62  4597.4  350.82  4652.7  349.73  4747.5  347.38
  4757.5  349.35  4763.2  349.11  4770.3  351.35  4793.1  353.32  4828.6  353.32
  4844.8  352.39  4866.6  353.74  4882.7  352.85  4904.6  352.82  4910.3  353.69
  4923.6     353  4941.2  352.25    4964  349.84  4975.7  346.36  4991.9  344.01
    5008  342.99  5009.6  342.02  5010.1  341.52  5017.8  342.02  5063.9  347.37
    5094  348.97  5444.4  351.22  5544.5     353  5724.3  358.44  5860.4  362.74
#Mann= 7 ,-1 , 0
  4103.4     .05       0  4597.4     .07       0  4652.7     .05       0
  4923.6     .07       0  5009.6     .05       0  5017.8     .07       0
  5724.3    .063       0
Bank Sta=5009.6,5017.8
XS Rating Curve= 0 ,0
Exp/Cntr=0.3,0.1

Type RM Length L Ch R = 1 ,11859   ,264,264,264
BEGIN DESCRIPTION:
B19715
END DESCRIPTION:
XS GIS Cut Line= 3
      2361244.73     13663297.25      2360359.69     13662781.47
      2359486.32     13662840.08
#Sta/Elev= 30
  4128.4  354.45  4245.9  354.13  4341.8  352.76  4437.8  350.38    4561  349.44
  4598.2  348.06  4619.7   348.4  4694.2  345.91    4743  345.83  4784.4  346.92
  4817.4  346.27  4845.7  344.34  4876.1  345.22  4897.6  343.56  4956.4  343.74
  4977.9  341.89  4980.4  339.84  4980.9  339.34  4988.7  339.84  4993.6  341.82
  4999.4  340.48  5007.7  340.41  5042.4  344.24  5073.8  345.35  5095.3  347.26
  5157.6  346.47  5581.1  348.57  5798.9  351.86  5971.4  357.21  6028.1  358.91
#Mann= 5 ,-1 , 0
  4128.4     .05       0  4784.4     .07       0  4980.4     .05       0
  4988.7     .07       0  5971.4    .063       0
Bank Sta=4980.4,4988.7
XS Rating Curve= 0 ,0
Exp/Cntr=0.3,0.1

Type RM Length L Ch R = 1 ,11595   ,524,524,524
BEGIN DESCRIPTION:
B19714
END DESCRIPTION:
XS GIS Cut Line= 3
      2361362.02     13663238.68      2360558.97     13662582.18
      2359544.92     13662781.47
#Sta/Elev= 30
  4075.2  353.52  4345.4  353.75  4359.7  352.99  4600.9  348.93  4765.3  348.15
  4855.2  344.91  4893.1  342.83  4949.7  341.43  4971.4  342.36  4985.7   341.6
  4995.9  340.19  4996.4  339.69  5004.2  340.19  5020.9  342.91  5035.3  344.17
  5041.7  343.17  5056.1  343.29  5070.4  343.88  5078.3  345.04  5091.7  345.29
    5117   344.4  5153.6  345.53  5279.6  346.63  5381.5  346.13    5831  349.53
  5952.2  351.69  5962.4  352.39  5985.3  352.23  6131.6  356.74  6145.9  357.19
#Mann= 6 ,-1 , 0
  4075.2     .05       0  4855.2     .07       0  4995.9     .05       0
  5004.2     .07       0  5153.6     .07       0  6131.6    .063       0
Bank Sta=4995.9,5004.2
XS Rating Curve= 0 ,0
Exp/Cntr=0.3,0.1

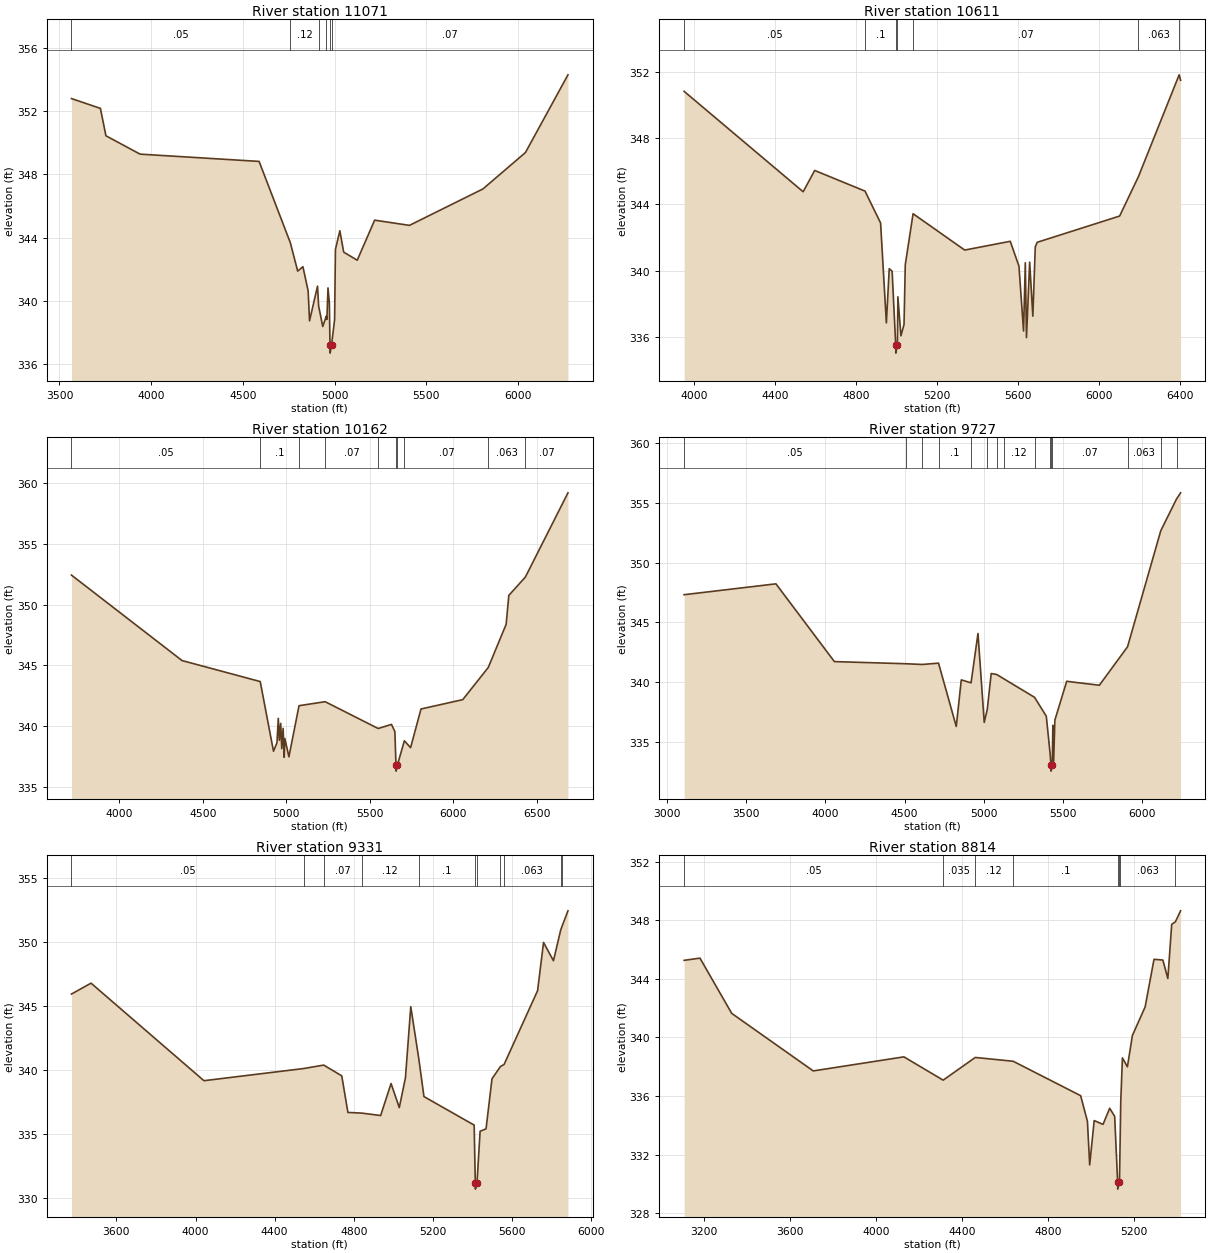
Type RM Length L Ch R = 1 ,11071   ,460,460,460
BEGIN DESCRIPTION:
MURRAY BRANCH 11.0
END DESCRIPTION:
XS GIS Cut Line= 3
      2362024.97     13663124.98        2360825.       13662325.
      2359624.99       13662725.
#Sta/Elev= 30
  3565.4  352.78  3723.1  352.16  3753.2  350.43  3939.4  349.27  4588.4  348.81
  4758.8  343.67  4798.8  341.88  4827.3  342.16  4855.8  340.63  4863.4  338.74
  4906.9  340.93  4913.1  339.67  4935.5  338.38  4954.7  339.03    4958  338.83
    4964  340.82  4971.5  339.85  4974.9   337.2  4975.4   336.7  4983.2   337.2
  5000.1  338.81  5004.6  343.25  5028.7  344.43  5049.7  343.08  5123.5  342.57
  5218.4   345.1  5408.1  344.77  5808.7  347.07  6040.6  349.37  6272.5  354.28
#Mann= 6 ,-1 , 0
  3565.4     .05       0  4758.8     .12       0  4913.1      .1       0
  4954.7     .07       0  4974.9     .05       0  4983.2     .07       0
Bank Sta=4974.9,4983.2
XS Rating Curve= 0 ,0
Exp/Cntr=0.3,0.1

Type RM Length L Ch R = 1 ,10611   ,449,449,449
BEGIN DESCRIPTION:
MURRAY BRANCH 10.0
END DESCRIPTION:
XS GIS Cut Line= 3
      2361875.02     13662775.02        2361075.       13662075.
      2359874.99     13661374.99
#Sta/Elev= 30
  3951.1  350.85  4539.1  344.77  4596.1  346.06  4844.6  344.81  4921.6  342.88
  4950.1  336.83  4964.3  340.11  4978.6  339.96  4996.2   335.5  4996.7     335
  5004.6   335.5    5007  338.41    5022  336.05  5037.3  336.73  5043.5  340.35
    5082  343.44  5337.1  341.24    5562  341.77    5605  340.27  5627.7  336.34
  5636.4  340.47  5642.2  335.94  5657.9  340.51  5673.6  337.24  5685.6  341.43
  5695.1  341.71  6102.4   343.3  6194.9  345.68  6396.3  351.85  6403.4  351.52
#Mann= 7 ,-1 , 0
  3951.1     .05       0  4844.6      .1       0  4996.2     .05       0
  5004.6      .1       0    5082     .07       0  6194.9    .063       0
  6396.3     .07       0
Bank Sta=4996.2,5004.6
XS Rating Curve= 0 ,0
Exp/Cntr=0.3,0.1

Type RM Length L Ch R = 1 ,10162   ,435,435,435
BEGIN DESCRIPTION:
MURRAY BRANCH 9.0
END DESCRIPTION:
XS GIS Cut Line= 3
        2362075.       13662775.        2361275.       13661775.
      2359675.02     13661225.01
#Sta/Elev= 30
  3713.5  352.44  4375.4   345.4  4843.5  343.67  4922.9  337.93  4943.7  338.62
  4951.7  340.64  4958.1  338.83  4966.1  340.23  4972.5  338.14  4980.5  339.81
  4986.9  337.43  4990.9  338.98  5015.3  337.47  5075.8  341.68  5232.3  342.01
  5549.9   339.8  5629.3  340.14  5649.7  339.55  5656.3  336.79  5656.8  336.29
  5664.8  336.79  5706.5  338.79  5743.7  338.22  5806.2  341.41  6056.1  342.18
  6208.9  344.83  6315.9  348.39    6332  350.77  6431.1  352.28    6686  359.22
#Mann= 10 ,-1 , 0
  3713.5     .05       0  4843.5      .1       0  5075.8     .12       0
  5232.3     .07       0  5549.9      .1       0  5656.3     .05       0
  5664.8      .1       0  5706.5     .07       0  6208.9    .063       0
  6431.1     .07       0
Bank Sta=5656.3,5664.8
XS Rating Curve= 0 ,0
Exp/Cntr=0.3,0.1

Type RM Length L Ch R = 1 ,9727    ,396,396,396
BEGIN DESCRIPTION:
MURRAY BRANCH 8.0
END DESCRIPTION:
XS GIS Cut Line= 3
      2362924.97     13662024.99        2361125.       13661425.
      2359924.97     13661124.99
#Sta/Elev= 30
  3108.6  347.32  3688.3  348.23  4057.3  341.72  4509.2  341.54  4611.9  341.48
  4714.7  341.59  4826.7  336.29  4858.4  340.19  4920.1  339.94  4963.8  344.07
  5003.3  336.63  5022.5  337.72  5047.2  340.72  5082.3  340.64  5125.6  340.29
  5320.9  338.73  5395.1  337.15  5419.9  333.92  5424.3  333.05  5424.8  332.55
  5432.9  333.05  5436.3  336.38  5441.4  333.35  5449.2  336.82  5523.9  340.07
  5730.1  339.74    5908  342.96  6117.9  352.68  6217.5  355.34  6242.9  355.85
#Mann= 15 ,-1 , 0
  3108.6     .05       0  4509.2    .035       0  4611.9     .12       0
  4714.7      .1       0  4920.1     .07       0  5022.5     .12       0
  5082.3     .07       0  5125.6     .12       0  5320.9      .1       0
  5419.9     .07       0  5424.3     .05       0  5432.9     .07       0
    5908    .063       0  6117.9    .035       0  6217.5     .07       0
Bank Sta=5424.3,5432.9
XS Rating Curve= 0 ,0
Exp/Cntr=0.3,0.1

Type RM Length L Ch R = 1 ,9331    ,517,517,517
BEGIN DESCRIPTION:
B19713
END DESCRIPTION:
XS GIS Cut Line= 3
      2362540.15     13661521.27      2360734.82     13661017.18
      2360101.79     13660982.01
#Sta/Elev= 30
  3373.4  345.94  3472.2  346.79  4042.7  339.17  4546.4  340.12  4647.7  340.39
  4738.9  339.55    4770  336.69  4839.3  336.64  4935.4  336.45    4988  338.95
  5029.6  337.07  5060.7   339.4  5087.6  344.95  5128.4  340.86  5154.2  337.93
  5407.9   335.7  5413.6   331.2  5414.1   330.7  5422.2   331.2  5437.9  335.22
  5467.9  335.41    5498  339.32  5540.8  340.28  5559.1  340.44  5728.3   346.2
  5758.4  349.97  5808.5  348.54  5844.9  350.93  5849.9  351.15  5881.8  352.44
#Mann= 11 ,-1 , 0
  3373.4     .05       0  4546.4    .035       0  4647.7     .07       0
  4839.3     .12       0  5128.4      .1       0  5413.6     .05       0
  5422.2      .1       0  5540.8     .07       0  5559.1    .063       0
  5844.9     .07       0  5849.9    .035       0
Bank Sta=5413.6,5422.2
XS Rating Curve= 0 ,0
Exp/Cntr=0.3,0.1

Type RM Length L Ch R = 1 ,8814    ,835,835,835
BEGIN DESCRIPTION:
MURRAY BRANCH 7.0
END DESCRIPTION:
XS GIS Cut Line= 3
        2362425.       13661325.        2360625.       13660725.
      2360224.98     13660825.01
#Sta/Elev= 30
  3108.3  345.26  3182.1  345.41  3329.7  341.64  3709.1  337.71  4130.8  338.67
  4313.5  337.08  4462.8  338.63  4639.2  338.37    4953  336.02  4984.6  334.27
  4995.1  331.29    5016  334.32  5057.2  334.06  5088.1  335.16  5111.3  334.61
  5125.1  330.14  5125.6  329.64  5133.7  330.14  5135.2  331.52  5139.7  335.64
  5147.4   338.6  5170.6  337.99  5193.8  340.13  5253.1  342.08  5294.3  345.33
  5335.5  345.28  5358.7  344.02  5376.7  347.72  5393.7  347.89    5418  348.64
#Mann= 8 ,-1 , 0
  3108.3     .05       0  4313.5    .035       0  4462.8     .12       0
  4639.2      .1       0  5125.1     .05       0  5133.7      .1       0
  5135.2    .063       0  5393.7     .07       0
Bank Sta=5125.1,5133.7
XS Rating Curve= 0 ,0
Exp/Cntr=0.3,0.1

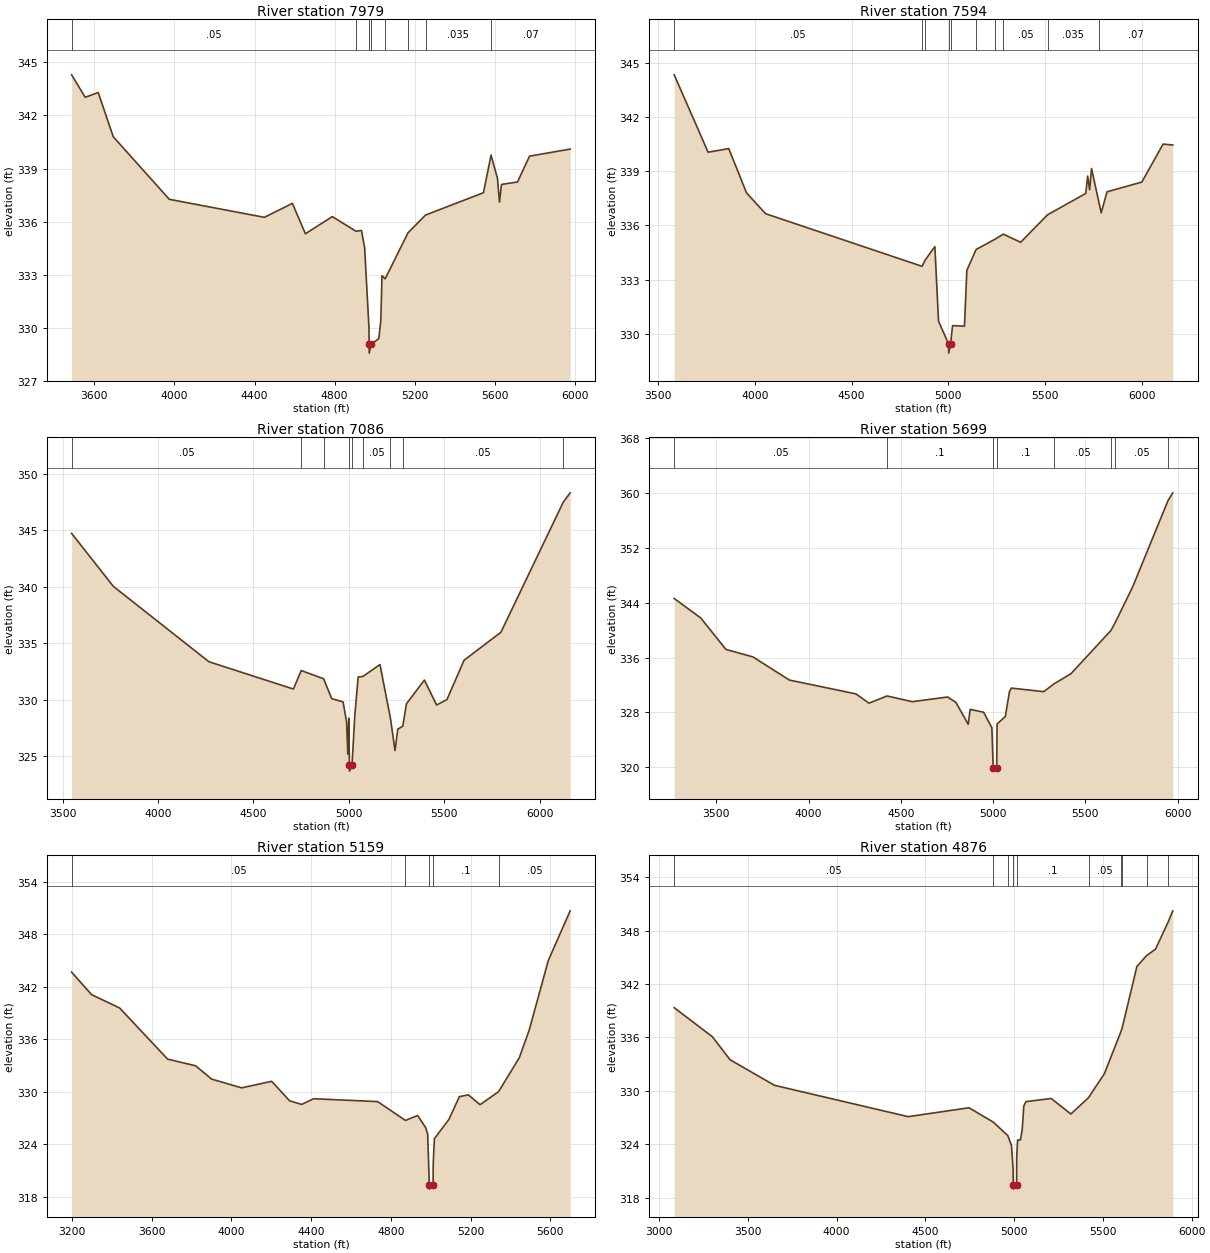
Type RM Length L Ch R = 1 ,7979    ,385,385,385
BEGIN DESCRIPTION:
B19712
END DESCRIPTION:
XS GIS Cut Line= 4
      2362399.44     13661263.35      2360992.72     13660466.21
      2360758.26     13660302.09      2360172.13     13660302.09
#Sta/Elev= 30
  3486.5   344.3  3554.5  343.03  3619.4   343.3  3694.4   340.8  3974.3  337.26
    4449  336.24  4588.9  337.03  4653.8  335.31  4788.1  336.28    4907  335.45
  4933.8   335.5  4949.6  334.52  4971.3  329.98    4972  329.06  4972.5  328.56
    4982  329.06  5020.3  329.38  5030.4   330.4  5036.2  332.94  5051.8  332.76
  5166.6  335.37  5253.8  336.37  5542.8  337.63  5580.8  339.76  5612.8  338.44
  5622.8   337.1  5632.8   338.1  5712.8  338.24  5772.8   339.7  5975.7   340.1
#Mann= 8 ,-1 , 0
  3486.5     .05       0    4907      .1       0    4972     .05       0
    4982      .1       0  5051.8    .035       0  5166.6      .1       0
  5253.8    .035       0  5580.8     .07       0
Bank Sta=4972,4982
XS Rating Curve= 0 ,0
Exp/Cntr=0.3,0.1

Type RM Length L Ch R = 1 ,7594    ,508,508,508
BEGIN DESCRIPTION:
B19711
END DESCRIPTION:
XS GIS Cut Line= 4
      2362405.29     13661192.99      2361403.02     13660290.36
      2360957.55     13660067.63      2360224.91     13660085.21
#Sta/Elev= 30
  3581.7  344.33  3757.2  340.05    3864  340.25    3956   337.8  4054.6  336.65
  4864.2  333.74  4879.4  334.07  4930.5  334.83  4949.4  330.71  5001.6  329.44
  5002.1  328.94  5011.6  329.44    5022  330.46  5083.5  330.43    5096  333.52
  5143.8  334.67  5241.7  335.24  5284.7  335.52  5374.2  335.07  5513.4  336.59
  5711.2  337.77  5721.2  338.73  5731.2  337.97  5741.2  339.15    5778  337.34
  5791.2   336.7  5821.2  337.86  6001.3   338.4  6111.3   340.5  6161.4  340.45
#Mann= 10 ,-1 , 0
  3581.7     .05       0  4864.2     .07       0  4879.4      .1       0
  5001.6     .05       0  5011.6      .1       0  5143.8     .05       0
  5241.7      .1       0  5284.7     .05       0  5513.4    .035       0
    5778     .07       0
Bank Sta=5001.6,5011.6
XS Rating Curve= 0 ,0
Exp/Cntr=0.3,0.1

Type RM Length L Ch R = 1 ,7086    ,1387,1387,1387
BEGIN DESCRIPTION:
MURRAY BRANCH 6.0
END DESCRIPTION:
XS GIS Cut Line= 3
        2362425.       13661175.      2361737.12     13660050.05
      2361268.21      13658842.6
#Sta/Elev= 30
  3546.4  344.74    3765  340.05  4266.2  333.37  4709.4  330.95  4750.4  332.59
  4867.7  331.86  4910.1   330.1  4969.9  329.81  4988.4     328  4994.5  325.18
  4999.8  328.37  5003.3  324.18  5003.8  323.68  5016.5  324.18  5031.3  328.63
  5048.9  332.02  5073.3  332.06  5163.2  333.12  5218.1  328.36  5242.1  325.51
  5256.6  327.39  5282.9  327.67  5301.9  329.64  5396.1  331.75  5459.9  329.54
  5514.1  330.01  5604.1   333.5  5797.3  335.98  6123.8  347.49  6160.3  348.33
#Mann= 9 ,-1 , 0
  3546.4     .05       0  4750.4     .07       0  4867.7     .12       0
  5003.3     .05       0  5016.5     .12       0  5073.3     .05       0
  5218.1      .1       0  5282.9     .05       0  6123.8    .063       0
Bank Sta=5003.3,5016.5
XS Rating Curve= 0 ,0
Exp/Cntr=0.3,0.1

Type RM Length L Ch R = 1 ,5699    ,540,540,540
BEGIN DESCRIPTION:
B19710
END DESCRIPTION:
XS GIS Cut Line= 4
       2362469.8     13661157.86      2362381.88     13659909.37
      2362118.11      13659387.7       2361707.8     13658625.69
#Sta/Elev= 30
  3272.1  344.62    3416  341.78  3552.3  337.19  3698.6   336.1  3896.5  332.72
  4257.4   330.7  4327.6  329.35  4425.4   330.4  4562.2  329.57  4753.9  330.25
  4798.5  329.47  4865.3  326.28    4876  328.45  4948.9  328.03  4993.4  325.77
  5000.7  319.94  5001.2  319.44  5019.6  319.94  5021.6  326.31  5066.4  327.41
  5088.9  331.04  5099.3  331.55  5274.5  331.03  5329.8  332.16  5422.1  333.65
  5638.6  339.95  5661.1  341.07  5755.6  346.26  5947.7  358.88  5973.7  360.03
#Mann= 8 ,-1 , 0
  3272.1     .05       0  4425.4      .1       0  5000.7     .05       0
  5019.6      .1       0  5329.8     .05       0  5638.6    .035       0
  5661.1     .05       0  5947.7    .035       0
Bank Sta=5000.7,5019.6
XS Rating Curve= 0 ,0
Exp/Cntr=0.3,0.1

Type RM Length L Ch R = 1 ,5159    ,283,283,283
BEGIN DESCRIPTION:
MURRAY BRANCH 5.0
END DESCRIPTION:
XS GIS Cut Line= 3
        2362525.     13661175.04        2362675.       13659375.
        2362325.       13658775.
#Sta/Elev= 30
    3199  343.67  3299.4   341.1  3439.9  339.58  3680.7  333.74  3821.2  332.98
  3901.5  331.46    4052  330.46  4202.5  331.21  4292.8  328.98    4353  328.57
  4413.2  329.22  4734.3  328.89  4873.7  326.74    4935  327.31  4975.2  325.92
  4985.2   325.2  4993.3   319.4  4993.8   318.9  5012.2   319.4  5013.1  321.92
  5018.9  324.66  5092.1  326.87  5144.2  329.46  5189.3  329.66    5248  328.54
    5341  330.03  5445.2  333.92  5494.4  337.05  5590.3     345  5699.9  350.67
#Mann= 5 ,-1 , 0
    3199     .05       0  4873.7      .1       0  4993.3     .05       0
  5012.2      .1       0    5341     .05       0
Bank Sta=4993.3,5012.2
XS Rating Curve= 0 ,0
Exp/Cntr=0.3,0.1

Type RM Length L Ch R = 1 ,4876    ,440,440,440
BEGIN DESCRIPTION:
B19709
END DESCRIPTION:
XS GIS Cut Line= 4
       2363061.8     13661169.59      2363102.83     13659932.82
      2362885.96     13659135.66      2362545.99      13658473.3
#Sta/Elev= 30
  3085.5  339.34  3300.2  336.08  3400.3  333.49  3650.4  330.62  4403.6   327.1
  4745.6   328.1  4881.8   326.5  4964.6  324.97  4985.2  323.85  4994.3  321.21
  4995.2  319.46  4995.7  318.96  5014.2  319.46  5014.6  322.59  5019.8  324.48
  5035.8  324.49  5046.1  325.73  5054.4  328.29  5066.9  328.79  5208.8  329.14
  5319.7   327.4  5419.1  329.23  5508.2  331.92  5599.9  336.56  5608.2  337.03
  5691.4  343.96    5746  345.19  5796.7  345.92  5868.6  349.01  5893.6  350.22
#Mann= 10 ,-1 , 0
  3085.5     .05       0  4881.8    .035       0  4964.6      .1       0
  4995.2     .05       0  5014.2      .1       0  5419.1     .05       0
  5599.9    .035       0  5608.2     .05       0    5746    .035       0
  5868.6     .05       0
Bank Sta=4995.2,5014.2
XS Rating Curve= 0 ,0
Exp/Cntr=0.3,0.1