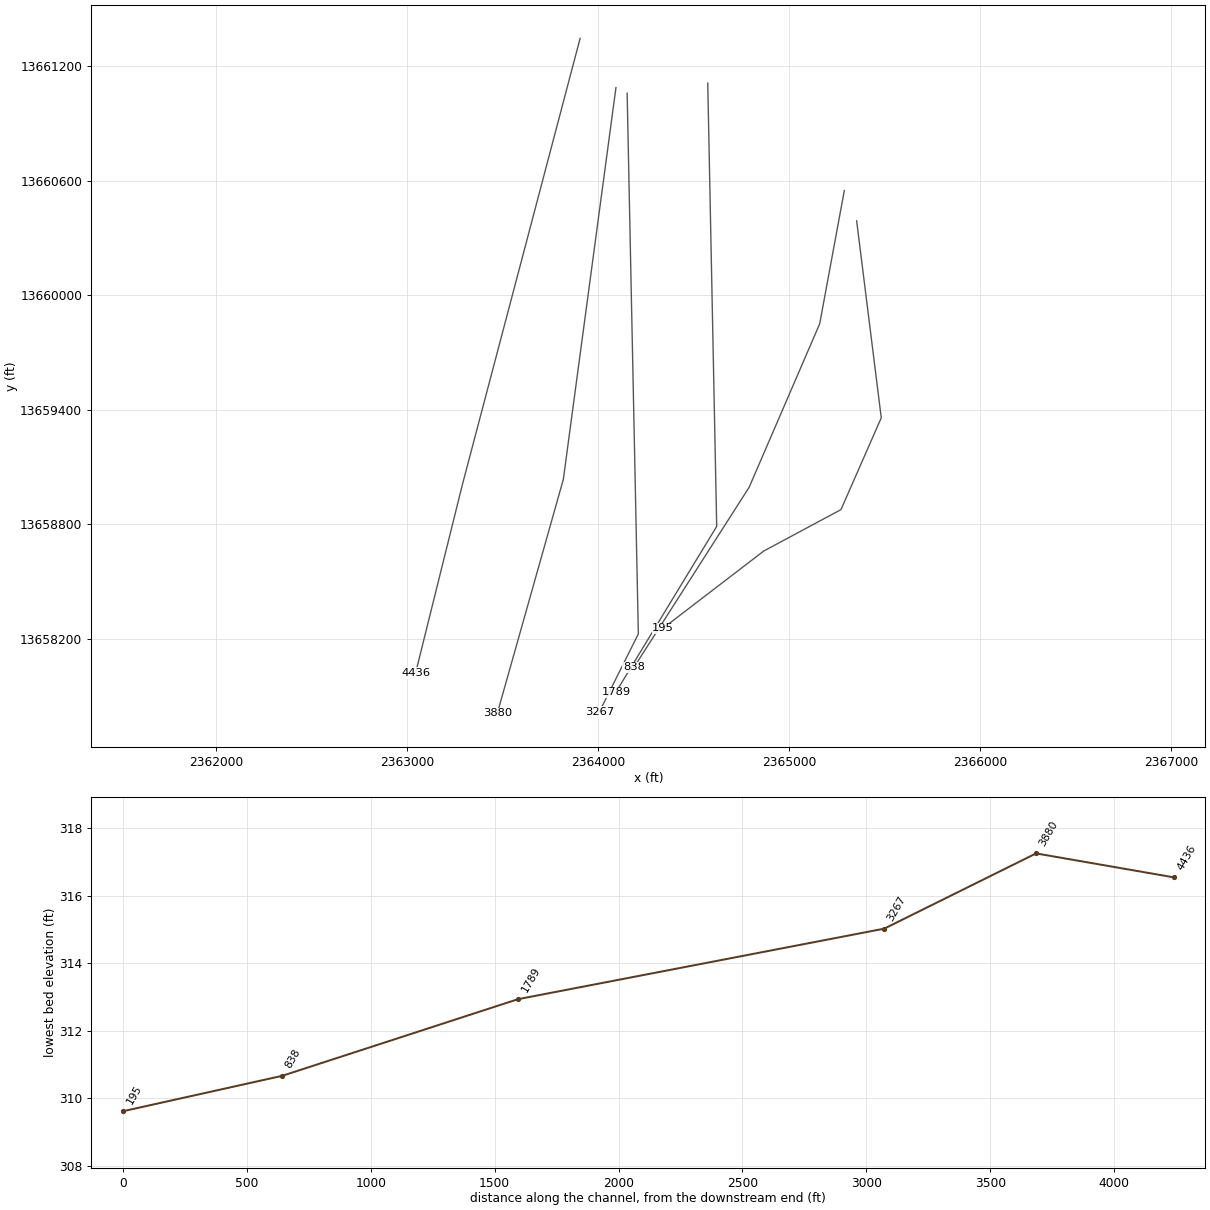
HEC-RAS study MURRAY BRANCH.prj: MURRAY BRANCH Base Level Engineering

--- MURRAY BRANCH.g01 (geometry) --- (continued)

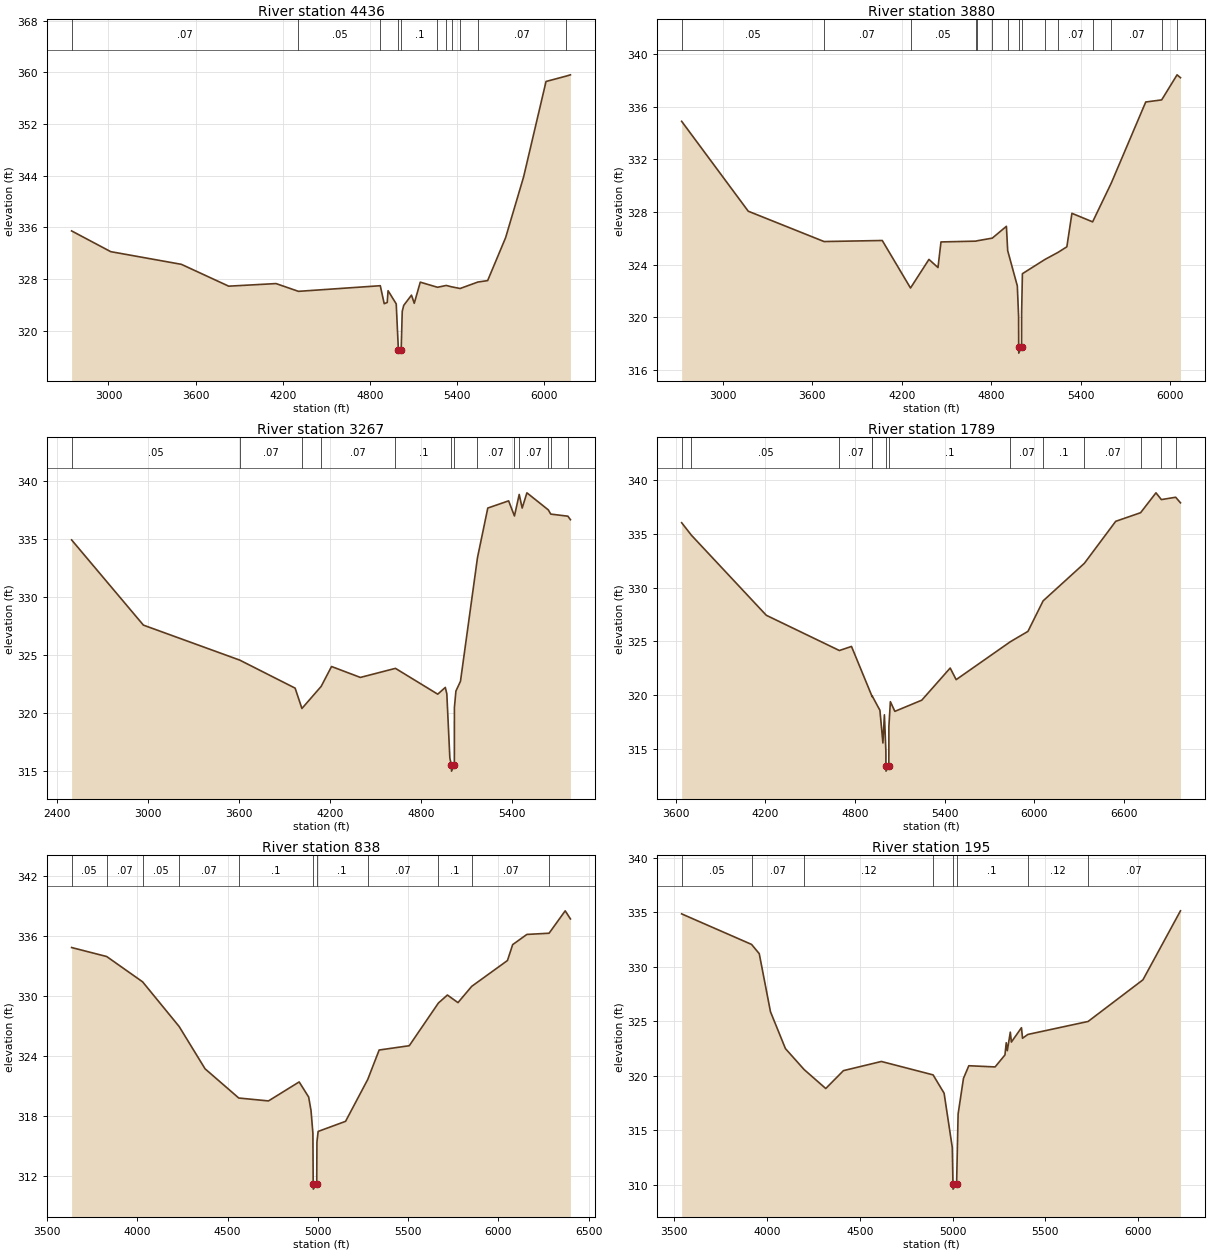
Type RM Length L Ch R = 1 ,4436    ,556,556,556
BEGIN DESCRIPTION:
B19708
END DESCRIPTION:
XS GIS Cut Line= 3
      2363905.83     13661345.37       2363290.4     13659012.57
      2363044.22     13658022.02
#Sta/Elev= 30
  2746.6  335.45  3015.9  332.24    3502  330.28  3827.8   326.9  4153.5   327.3
    4308   326.1  4871.2  326.97  4898.2  324.19  4918.8  324.37  4924.8   326.2
  4980.9  324.16  4995.8  317.04  4996.3  316.54  5014.9  317.04  5022.3  323.01
  5032.6  323.93  5085.9  325.51    5105  324.25  5146.4  327.52  5264.8  326.73
  5325.3  327.01  5361.9   326.8  5420.8  326.54  5542.9  327.54  5610.1  327.76
  5733.7   334.4  5857.4  343.79    6012  358.57  6151.8  359.41  6179.9   359.6
#Mann= 11 ,-1 , 0
  2746.6     .07       0    4308     .05       0  4871.2      .1       0
  4995.8     .05       0  5014.9      .1       0  5264.8     .07       0
  5325.3     .12       0  5361.9     .07       0  5420.8     .12       0
  5542.9     .07       0  6151.8    .035       0
Bank Sta=4995.8,5014.9
XS Rating Curve= 0 ,0
Exp/Cntr=0.3,0.1

Type RM Length L Ch R = 1 ,3880    ,613,613,613
BEGIN DESCRIPTION:
B19707
END DESCRIPTION:
XS GIS Cut Line= 3
       2364093.4     13661087.47      2363817.92     13659036.02
      2363472.09     13657810.96
#Sta/Elev= 30
  2724.2  334.91  3170.6  328.06  3678.6  325.75  4068.6  325.83  4257.9  322.21
  4381.4  324.39    4442  323.77  4462.1  325.72  4695.4  325.78  4705.7  325.81
  4805.9  326.01  4900.5  326.91  4909.1  325.06  4973.7  322.37  4982.2  320.04
  4982.9  317.75  4983.4  317.25  5002.1  317.75  5002.5  320.31  5007.7   323.3
  5159.4  324.39  5247.3  324.93  5305.6  325.35  5339.6   327.9  5478.3  327.25
  5603.1   330.2  5834.2  336.38    5941  336.54  6044.2  338.45    6067  338.23
#Mann= 15 ,-1 , 0
  2724.2     .05       0  3678.6     .07       0  4257.9     .05       0
  4695.4     .07       0  4705.7     .05       0  4805.9     .07       0
  4909.1      .1       0  4982.9     .05       0  5002.1      .1       0
  5159.4     .12       0  5247.3     .07       0  5478.3     .12       0
  5603.1     .07       0    5941    .035       0  6044.2     .07       0
Bank Sta=4982.9,5002.1
XS Rating Curve= 0 ,0
Exp/Cntr=0.3,0.1

Type RM Length L Ch R = 1 ,3267    ,1478,1478,1478
BEGIN DESCRIPTION:
B19706
END DESCRIPTION:
XS GIS Cut Line= 3
      2364152.03     13661058.18      2364210.64     13658227.14
      2364006.28     13657818.43
#Sta/Elev= 30
  2494.8  334.91  2968.1  327.58  3603.3  324.57  3968.3  322.16  4013.3  320.41
  4140.1  322.31  4208.4  324.02  4398.4  323.08  4629.7  323.86  4908.5  321.64
  4958.5  322.22  4968.5  321.67  4988.5  316.15  4998.9  315.52  4999.4  315.02
  5018.2  315.52  5018.5  320.49  5028.5  321.91  5058.5  322.75  5170.7  333.39
  5238.6  337.65  5375.9  338.27  5414.3  336.97  5445.7  338.82  5465.3  337.65
  5496.5  338.96  5637.8  337.49  5653.6  337.13  5766.6  336.95  5783.4  336.65
#Mann= 13 ,-1 , 0
  2494.8     .05       0  3603.3     .07       0  4013.3     .05       0
  4140.1     .07       0  4629.7      .1       0  4998.9     .05       0
  5018.2      .1       0  5170.7     .07       0  5414.3     .12       0
  5445.7     .07       0  5637.8     .12       0  5653.6     .07       0
  5766.6     .12       0
Bank Sta=4998.9,5018.2
XS Rating Curve= 0 ,0
Exp/Cntr=0.3,0.1

Type RM Length L Ch R = 1 ,1789    ,951,951,951
BEGIN DESCRIPTION:
B19705
END DESCRIPTION:
XS GIS Cut Line= 3
      2364574.05     13661110.99      2364620.94     13658789.84
      2364093.42     13657922.37
#Sta/Elev= 30
  3640.9  336.04    3706  334.88    4207  327.43  4696.1  324.15  4777.1  324.53
  4915.9  319.84  4916.8  319.89  4967.2  318.59  4987.2  315.55  4997.2  318.17
  5007.2   314.8  5007.4  313.43  5007.9  312.93  5026.9  313.43  5027.2  317.07
  5037.2  319.39  5067.2  318.49  5247.2  319.53  5437.3  322.52  5477.3  321.44
    5840  324.97  5957.4  325.93    6059  328.77  6334.8  332.26  6544.6  336.17
    6711  336.97  6813.9  338.82  6849.9  338.19  6945.7  338.41  6977.8  337.89
#Mann= 13 ,-1 , 0
  3640.9     .07       0    3706     .05       0  4696.1     .07       0
  4915.9     .12       0  4916.8      .1       0  5007.4     .05       0
  5026.9      .1       0    5840     .07       0    6059      .1       0
  6334.8     .07       0    6711     .12       0  6849.9     .07       0
  6945.7     .12       0
Bank Sta=5007.4,5026.9
XS Rating Curve= 0 ,0
Exp/Cntr=0.3,0.1

Type RM Length L Ch R = 1 ,838     ,643,643,643
BEGIN DESCRIPTION:
B19704
END DESCRIPTION:
XS GIS Cut Line= 4
      2365289.14     13660548.29      2365160.19     13659850.76
      2364790.92     13658994.99      2364187.18     13658051.28
#Sta/Elev= 30
  3636.8  334.82  3831.1  333.92  4029.9  331.39  4232.3  326.92  4375.8  322.69
  4562.3  319.77  4726.7  319.48  4896.7  321.38  4949.2  319.87  4962.3  318.52
  4972.7  316.25  4974.4  311.16  4974.9  310.66  4993.9  311.16    4995  315.36
  5001.7  316.43  5153.6  317.44  5276.4  321.63  5339.5  324.57  5506.1     325
  5667.5  329.27  5717.4  330.07  5775.9  329.31  5852.1  330.94  6049.8  333.52
  6078.7  335.11  6157.3  336.13  6280.3  336.25  6369.6  338.49  6398.5  337.68
#Mann= 11 ,-1 , 0
  3636.8     .05       0  3831.1     .07       0  4029.9     .05       0
  4232.3     .07       0  4562.3      .1       0  4974.4     .05       0
  4993.9      .1       0  5276.4     .07       0  5667.5      .1       0
  5852.1     .07       0  6280.3     .12       0
Bank Sta=4974.4,4993.9
XS Rating Curve= 0 ,0
Exp/Cntr=0.3,0.1

Type RM Length L Ch R = 1 ,195     ,0,0,0
BEGIN DESCRIPTION:
B19703
END DESCRIPTION:
XS GIS Cut Line= 5
      2365353.62     13660390.02      2365482.57      13659358.4
      2365271.56     13658877.76      2364867.12     13658660.89
      2364339.83     13658256.64
#Sta/Elev= 30
  3539.9  334.86  3916.6  332.06  3958.1  331.21  4018.6  325.88  4099.2   322.5
  4199.8  320.58  4316.4  318.84  4411.7  320.48  4616.2  321.32  4894.8  320.09
  4954.1  318.41  4998.3  313.43  5001.9  310.11  5002.4  309.61  5021.5  310.11
  5029.6   316.5  5058.5  319.77  5087.3  320.93  5228.9  320.82  5282.1  321.92
    5289  323.04  5294.7  322.31  5310.9  324.01  5316.6   323.1    5371  324.42
  5376.7  323.45  5405.3   323.8  5729.9  324.99  6025.5  328.81  6227.8  335.14
#Mann= 8 ,-1 , 0
  3539.9     .05       0  3916.6     .07       0  4199.8     .12       0
  4894.8      .1       0  5001.9     .05       0  5021.5      .1       0
  5405.3     .12       0  5729.9     .07       0
Bank Sta=5001.9,5021.5
XS Rating Curve= 0 ,0
Exp/Cntr=0.3,0.1

Chan Stop Cuts=-1
Use User Specified Reach Order=0
Composite Channel Slope=5