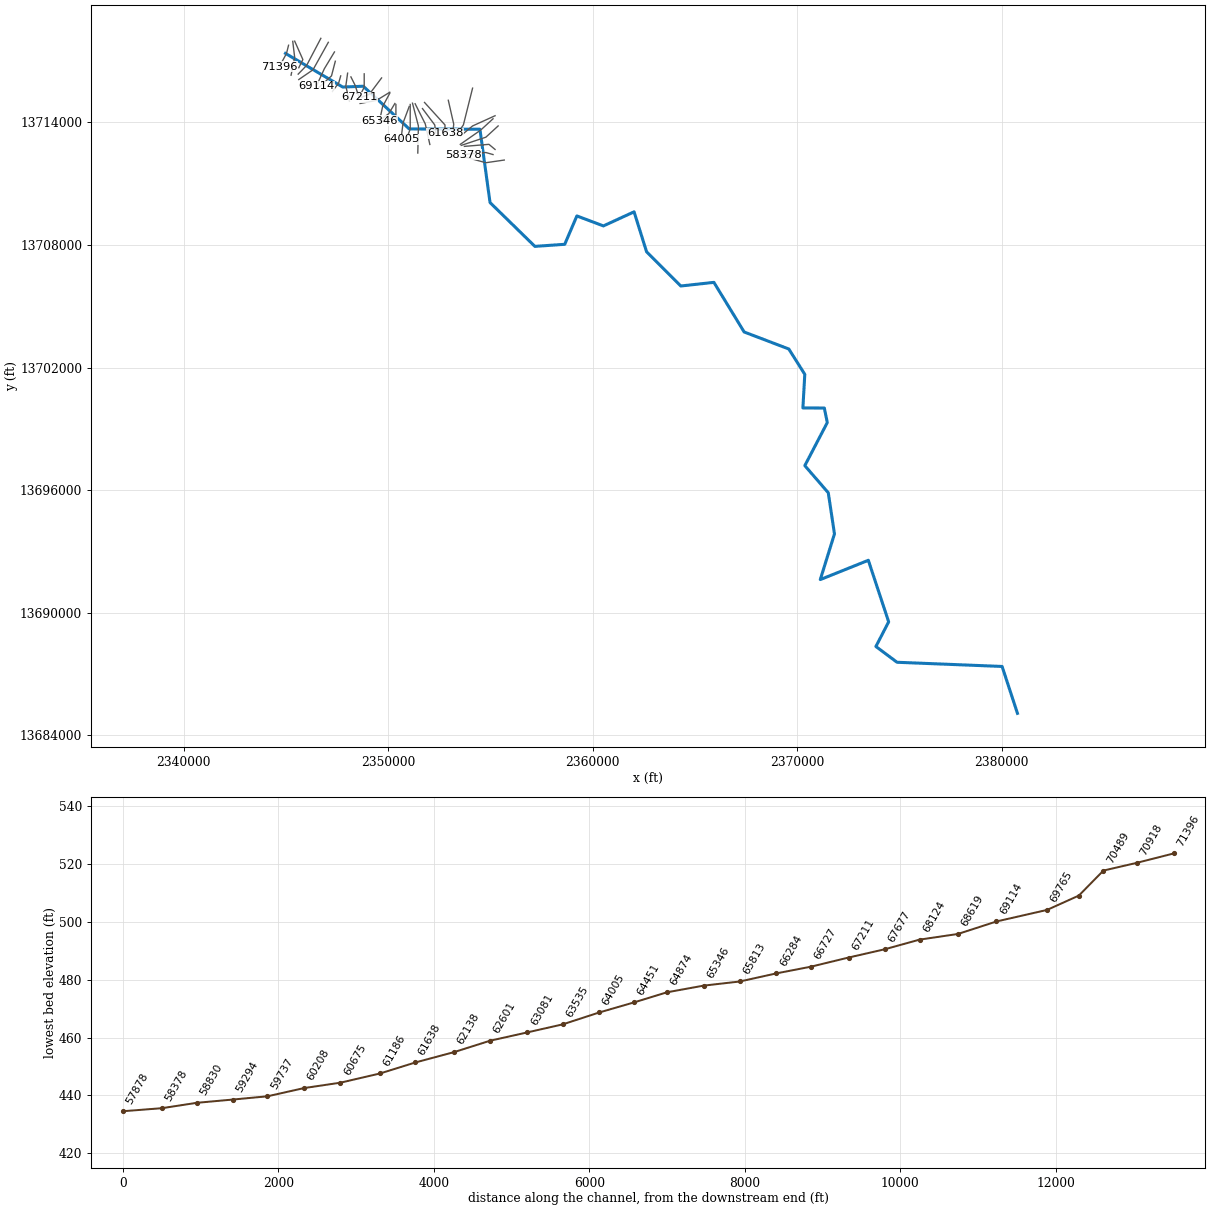
--- ONEIL CREEK.prj (project) ---

Proj Title=ONEIL CREEK Base Level Engineering
Current Plan=p01
Default Exp/Contr=0.3,0.1
English Units
Geom File=g01
Flow File=f01
Plan File=p01
Y Axis Title=Elevation
X Axis Title(PF)=Main Channel Distance
X Axis Title(XS)=Station
BEGIN DESCRIPTION:
ONEIL CREEK
END DESCRIPTION:
DSS Export Rating Curves= 0
DSS Export Rating Curve Sorted= 0
DSS Export Volume Flow Curves= 0
DXF OffsetX= 0
DXF OffsetY= 0
DXF ScaleX= 1
DXF ScaleY= 10

--- ONEIL CREEK.p01 (plan) ---

Plan Title=Multiple Run
Program Version=4.10
Short Identifier=Multiple
Geom File=g01
Flow File=f01
Subcritical Flow
K Sum by GR= 0
Std Step Tol= 0.01
Critical Tol= 0.01
Num of Std Step Trials= 20
Max Error Tol= 0.3
Flow Tol Ratio= 0.001
Split Flow NTrial= 30
Split Flow Tol= 0.02
Split Flow Ratio= 0.02
Log Output Level= 0
Friction Slope Method= 1
Unsteady Friction Slope Method= 2
Unsteady Bridges Friction Slope Method= 1
Parabolic Critical Depth
Global Vel Dist= 1 , 1 , 1
Global Log Level= 0
CheckData=True
Encroach Param=-1 ,0,0, 0
BEGIN DESCRIPTION:
Multiple Run
END DESCRIPTION:
Computation Interval=1HOUR
Output Interval=1HOUR
Run HTab= 0
Run UNet= 0
Run PostProcess= 0
Run WQNet= 0
UNET Theta= 1
UNET Theta Warmup= 1
UNET ZTol= 0.02
UNET ZSATol= 0.05
UNET MxIter= 20
UNET MaxInSteps= 0
UNET DtIC= 0
UNET DtMin= 0
UNET MaxCRTS= 20
UNET WFStab= 2
UNET SFStab= 1
UNET WFX= 1
UNET SFX= 1
UNET DSS MLevel= 4
UNET DZMax Abort= 100
UNET Convert EG Bridges= 0
UNET Use Existing IB Tables=-1
UNET Froude Reduction=False
UNET Froude Limit= 1
UNET Froude Power= 10
UNET Time Slicing=0,0, 5
UNET Junction Losses=0
Instantaneous Interval=1HOUR
Write IC File= 0
Write IC File at Sim End=0
Echo Input=False
Echo Parameters=False
Echo Output=False
Write Detailed= 0
WQ AD Non Conservative
WQ ULTIMATE=-1
WQ Max Comp Step=1HOUR
WQ Output Interval=15MIN
WQ Output Selected Increments= 0
WQ Output face flow=0
WQ Output face velocity=0
WQ Output face area=0
WQ Output face dispersion=0
WQ Output cell volume=0
WQ Output cell surface area=0
WQ Output cell continuity=0
WQ Output cumulative cell continuity=0
WQ Output face conc=0
WQ Output face dconc_dx=0
WQ Output face courant=0
WQ Output face peclet=0
WQ Output face adv mass=0
WQ Output face disp mass=0
WQ Output cell mass=0
WQ Output cell source sink temp=0
WQ Output cell source sink nsm=0
WQ Output MaxMinRange=-1
WQ Daily Max Min Mean=-1
WQ Daily Range=0
WQ Daily Time=0
WQ Create Restart=0
WQ Fixed Restart=0
WQ System Summary=0
WQ Use Fixed Temperature=0
Sorting and Armoring Iterations= 10
XS Update Threshold= 0.02
Hydraulics Update Threshold= 0.02
Energy Slope Method= 1
Volume Change Method= 0
XS Weighting Method= 0
Number of US Weighted Cross Sections= 1
Number of DS Weighted Cross Sections= 1
Upstream XS Weight=0.25
Main XS Weight=0.5
Downstream XS Weight=0.25
Number of DS XS's Weighted with US Boundary= 1
Upstream Boundary Weight= 1
Weight of XSs Associated with US Boundary= 0
Number of US XS's Weighted with DS Boundary= 1
Downstream Boundary Weight= 0.5
Weight of XSs Associated with DS Boundary= 0.5
Sediment Output Level= 4
Mass or Volume Output= 0
Output Increment Type= 1
Profile and TS Output Increment= 10
XS Output Flag= 0
XS Output Increment= 10
Disregard all LS=0
Disregard all Conn=0
Disregard all Breaches=0
Disregard all Pumps=0

--- ONEIL CREEK.f01 (steady flow) ---

Flow Title=Multiple
Number of Profiles=7
Profile Names=10-year,25-year,50-year,1pct_min,100-year,1pct_plu,500-year
River Rch & RM= ONEIL CREEK,Reach-1,71396
     676    1098    1482     969    1933    3857    3257
River Rch & RM= ONEIL CREEK,Reach-1,69114
    1115    1865    2565    1706    3404    6792    5945
River Rch & RM= ONEIL CREEK,Reach-1,68619
    1499    2546    3539    2377    4742    9463    8446
River Rch & RM= ONEIL CREEK,Reach-1,62601
    1624    2769    3859    2598    5183   10341    9273
River Rch & RM= ONEIL CREEK,Reach-1,61186
    2007    3459    4855    3289    6562   13094   11897
River Rch & RM= ONEIL CREEK,Reach-1,60675
    2599    4515    6372    4336    8652   17264   15827
River Rch & RM= ONEIL CREEK,Reach-1,49918
    2864    4994    7067    4820    9618   19190   17675
River Rch & RM= ONEIL CREEK,Reach-1,48310
    3085    5395    7647    5225   10424   20799   19219
River Rch & RM= ONEIL CREEK,Reach-1,45585
    3571    6280    8937    6127   12226   24393   22699
River Rch & RM= ONEIL CREEK,Reach-1,44438
    4365    7724   11039    7596   15157   30242   28348
River Rch & RM= ONEIL CREEK,Reach-1,39404
    4318    7629   10889    7484   14933   29795   27858
River Rch & RM= ONEIL CREEK,Reach-1,37872
    5172    9185   13160    9074   18105   36124   33993
River Rch & RM= ONEIL CREEK,Reach-1,34626
    5335    9482   13590    9374   18703   37318   35140
River Rch & RM= ONEIL CREEK,Reach-1,33516
    5359    9515   13628    9392   18740   37390   35149
River Rch & RM= ONEIL CREEK,Reach-1,31326
    5986   10637   15245   10510   20970   41840   39350
River Rch & RM= ONEIL CREEK,Reach-1,24526
    6015   10690   15322   10563   21076   42053   39556
River Rch & RM= ONEIL CREEK,Reach-1,23657
    6131   10894   15612   10761   21471   42840   40276
River Rch & RM= ONEIL CREEK,Reach-1,22510
    6950   12371   17750   12245   24432   48749   45903
River Rch & RM= ONEIL CREEK,Reach-1,16572
    6761   11986   17152   11799   23542   46972   43979
River Rch & RM= ONEIL CREEK,Reach-1,11930
    6926   12253   17508   12024   23990   47867   44665
River Rch & RM= ONEIL CREEK,Reach-1,2645
    6887   12165   17364   11911   23766   47419   44147
Boundary for River Rch & Prof#=ONEIL CREEK,Reach-1,1
Up Type=0
Dn Type=3
Dn Slope=0.0003
Boundary for River Rch & Prof#=ONEIL CREEK,Reach-1,2
Up Type=0
Dn Type=3
Dn Slope=0.0003
Boundary for River Rch & Prof#=ONEIL CREEK,Reach-1,3
Up Type=0
Dn Type=3
Dn Slope=0.0003
Boundary for River Rch & Prof#=ONEIL CREEK,Reach-1,4
Up Type=0
Dn Type=3
Dn Slope=0.0003
Boundary for River Rch & Prof#=ONEIL CREEK,Reach-1,5
Up Type=0
Dn Type=3
Dn Slope=0.0003
Boundary for River Rch & Prof#=ONEIL CREEK,Reach-1,6
Up Type=0
Dn Type=3
Dn Slope=0.0003
Boundary for River Rch & Prof#=ONEIL CREEK,Reach-1,7
Up Type=0
Dn Type=3
Dn Slope=0.0003

--- ONEIL CREEK.g01 (geometry) ---

Geom Title=Existing Conditions
Program Version=4.10

River Reach=ONEIL CREEK     ,Reach-1
Reach XY= 30
        2344975.       13717375.       2347776.5     13715728.46
      2348777.45     13715769.53       2351026.5     13713678.46
      2354484.68     13713664.22      2354978.45     13710076.25
      2357172.71     13707930.81      2358631.17     13708032.86
      2359226.46     13709421.46       2360524.9     13708932.33
      2362023.75     13709621.64       2362636.1     13707664.92
      2364308.21     13705991.44      2365927.55     13706169.94
      2367407.47     13703741.22      2369591.75      13702908.6
      2370373.04     13701669.12      2370280.69     13700022.61
      2371327.74     13700019.66      2371474.49     13699309.79
       2370374.8     13697200.08      2371521.66     13695873.28
      2371824.63     13693859.73      2371130.46     13691622.55
      2373481.07     13692567.53      2374474.98     13689554.99
      2373851.14     13688348.06      2374885.43     13687576.05
       2380023.5     13687371.39        2380775.       13685075.

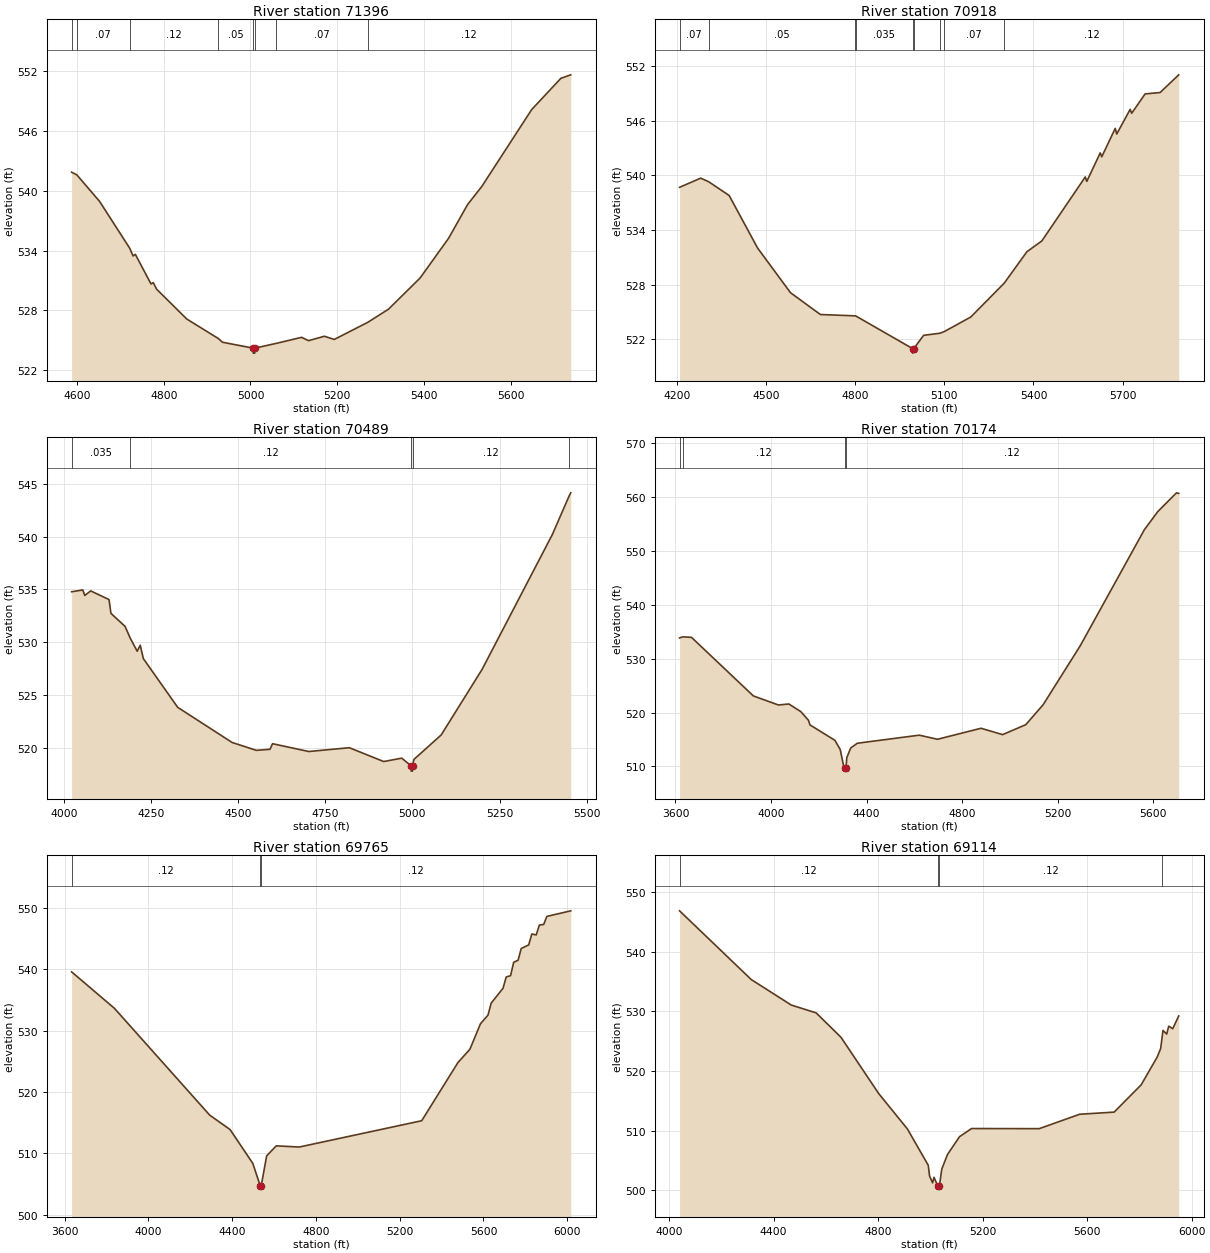
Type RM Length L Ch R = 1 ,71396   ,478,478,478
BEGIN DESCRIPTION:
ONEIL CREEK 7519
END DESCRIPTION:
XS GIS Cut Line= 3
        2345125.     13717775.01        2345025.       13717375.
      2344674.98     13716724.96
#Sta/Elev= 30
  4587.7  541.85  4599.6  541.59  4652.1  538.93  4721.5  534.24  4729.4  533.46
  4734.6  533.62  4770.7  530.65  4775.8  530.79  4783.6  530.13  4853.1  527.14
    4926  525.18  4935.6  524.81  5006.1  524.22  5006.4  523.72  5009.9  523.72
  5010.1  524.22  5059.7   524.7  5117.6   525.3  5133.9  524.97  5170.4  525.41
  5193.1  525.09  5270.5  526.81    5318  528.12    5391  531.25  5456.8  535.24
  5500.6  538.62    5533  540.41  5648.2  548.13  5715.5  551.26  5738.3  551.61
#Mann= 8 ,-1 , 0
  4587.7     .12       0  4599.6     .07       0  4721.5     .12       0
    4926     .05       0  5006.1     .05       0  5010.1     .05       0
  5059.7     .07       0  5270.5     .12       0
Bank Sta=5006.1,5010.1
XS Rating Curve= 0 ,0
Exp/Cntr=0.3,0.1

Type RM Length L Ch R = 1 ,70918   ,429,429,429
BEGIN DESCRIPTION:
ONEIL CREEK 7518
END DESCRIPTION:
XS GIS Cut Line= 3
      2345329.68     13717965.73        2345425.       13717175.
      2345247.27     13716309.21
#Sta/Elev= 30
  4208.6   538.7  4279.8  539.71  4306.7  539.31  4375.5   537.8  4471.2  532.02
    4582   527.1  4682.7   524.7  4800.8  524.55  4801.3  524.55  4992.9  520.95
  4993.2  520.45    4997  520.95  5030.2  522.41  5085.4  522.64  5099.5  522.82
  5188.8  524.42  5301.7  528.16  5377.8  531.61  5428.2   532.8  5574.3  539.84
  5579.4  539.35  5624.7  542.49  5629.8  542.06  5675.1  545.18  5680.2  544.56
  5725.4  547.28  5730.5  546.85  5775.8  548.98  5826.2  549.13  5888.9  551.08
#Mann= 9 ,-1 , 0
  4208.6     .07       0  4306.7     .05       0  4800.8     .12       0
  4801.3    .035       0  4992.9    .035       0    4997    .035       0
  5085.4     .05       0  5099.5     .07       0  5301.7     .12       0
Bank Sta=4992.9,4997
XS Rating Curve= 0 ,0
Exp/Cntr=0.3,0.1

Type RM Length L Ch R = 1 ,70489   ,315,315,315
BEGIN DESCRIPTION:
ONEIL CREEK 7517
END DESCRIPTION:
XS GIS Cut Line= 3
      2345425.01     13717974.97        2345825.       13717075.
      2345624.99     13716674.97
#Sta/Elev= 30
  4022.4  534.78  4054.5  534.95    4060  534.43  4077.1  534.86  4129.7  534.04
  4135.2  532.73  4175.6   531.5  4190.9  530.36  4210.5  529.14  4219.3  529.71
  4228.2  528.44  4326.7  523.82  4482.7  520.49  4552.4  519.74  4591.4  519.84
  4598.9  520.37  4702.9  519.63  4819.2  519.99  4917.7  518.68  4969.6     519
  4996.3  518.27  4996.6  517.77  5000.2  517.77  5000.4  518.27  5004.5  518.88
  5082.7   521.2  5200.1  527.42  5401.4  540.19  5450.1  543.89  5454.5  544.16
#Mann= 5 ,-1 , 0
  4022.4    .035       0  4190.9     .12       0  4996.3     .05       0
  5000.4     .12       0  5450.1     .07       0
Bank Sta=4996.3,5000.4
XS Rating Curve= 0 ,0
Exp/Cntr=0.3,0.1

Type RM Length L Ch R = 1 ,70174   ,409,409,409
BEGIN DESCRIPTION:
B19903
END DESCRIPTION:
XS GIS Cut Line= 3
      2346703.83     13718113.13      2346007.92     13716786.18
      2345595.08     13716361.55
#Sta/Elev= 30
  3617.1  533.84  3631.6  534.04  3667.1  533.94  3926.1  523.08  4030.8   521.4
  4074.9  521.58  4124.7  520.18    4157  518.56  4163.1  517.71  4267.8  514.84
  4289.8  513.15  4303.8  510.18  4309.8  509.63  4310.1  509.13  4313.7  509.13
  4313.9  509.63  4317.5  511.63  4333.9  513.42  4361.6   514.3  4620.7   515.8
  4697.6  515.04  4879.7  517.08    4970   515.9    5067  517.74  5139.6  521.43
  5295.2  532.38  5563.8  553.91  5620.4  557.29  5698.3  560.75  5707.7  560.64
#Mann= 4 ,-1 , 0
  3617.1     .07       0  3631.6     .12       0  4309.8     .05       0
  4313.9     .12       0
Bank Sta=4309.8,4313.9
XS Rating Curve= 0 ,0
Exp/Cntr=0.3,0.1

Type RM Length L Ch R = 1 ,69765   ,651,651,651
BEGIN DESCRIPTION:
ONEIL CREEK 7516
END DESCRIPTION:
XS GIS Cut Line= 3
      2347069.51     13717918.55       2346320.5     13716573.87
      2345624.59     13716096.17
#Sta/Elev= 30
  3633.7  539.61  3838.1  533.66  4293.1  516.23  4390.3  513.88  4498.9  508.35
  4534.6  504.66  4534.8  504.16  4538.7  504.66  4564.9  509.59  4610.7  511.22
  4720.7  511.03  5305.2  515.32  5478.4  524.82  5535.3  526.98    5586  531.15
  5621.9  532.56  5636.8   534.5  5693.6  536.94  5708.5  538.77  5729.5  538.99
  5744.4  541.18  5765.4   541.5  5780.3  543.42  5816.1  544.01    5831  545.79
    5852  545.64  5866.9  547.24  5887.8  547.36  5902.7  548.66    6017  549.57
#Mann= 3 ,-1 , 0
  3633.7     .12       0  4534.6     .05       0  4538.7     .12       0
Bank Sta=4534.6,4538.7
XS Rating Curve= 0 ,0
Exp/Cntr=0.3,0.1

Type RM Length L Ch R = 1 ,69114   ,495,495,495
BEGIN DESCRIPTION:
ONEIL CREEK 7515
END DESCRIPTION:
XS GIS Cut Line= 3
       2347370.3     13717446.75        2346875.       13716625.
      2346479.87     13715760.27
#Sta/Elev= 30
  4040.5  546.88  4314.6  535.35    4468  531.06  4563.1  529.75  4658.3  525.65
  4801.9  516.24  4912.6  510.25  4992.2  504.16  4997.1  502.38  5008.7  501.22
  5014.2  502.15  5028.7  500.66  5029.2  500.16  5034.8  500.66    5044  503.54
  5065.9  505.98  5111.8  508.96  5157.9  510.33  5416.7  510.31  5571.7  512.73
  5703.6  513.09    5807  517.67  5868.5  522.35  5881.6  523.77  5886.5  525.44
  5890.5  526.81  5904.6  526.19  5912.5  527.52  5927.7  527.09  5950.7  529.23
#Mann= 4 ,-1 , 0
  4040.5     .12       0  5028.7     .05       0  5034.8     .12       0
  5886.5     .07       0
Bank Sta=5028.7,5034.8
XS Rating Curve= 0 ,0
Exp/Cntr=0.3,0.1

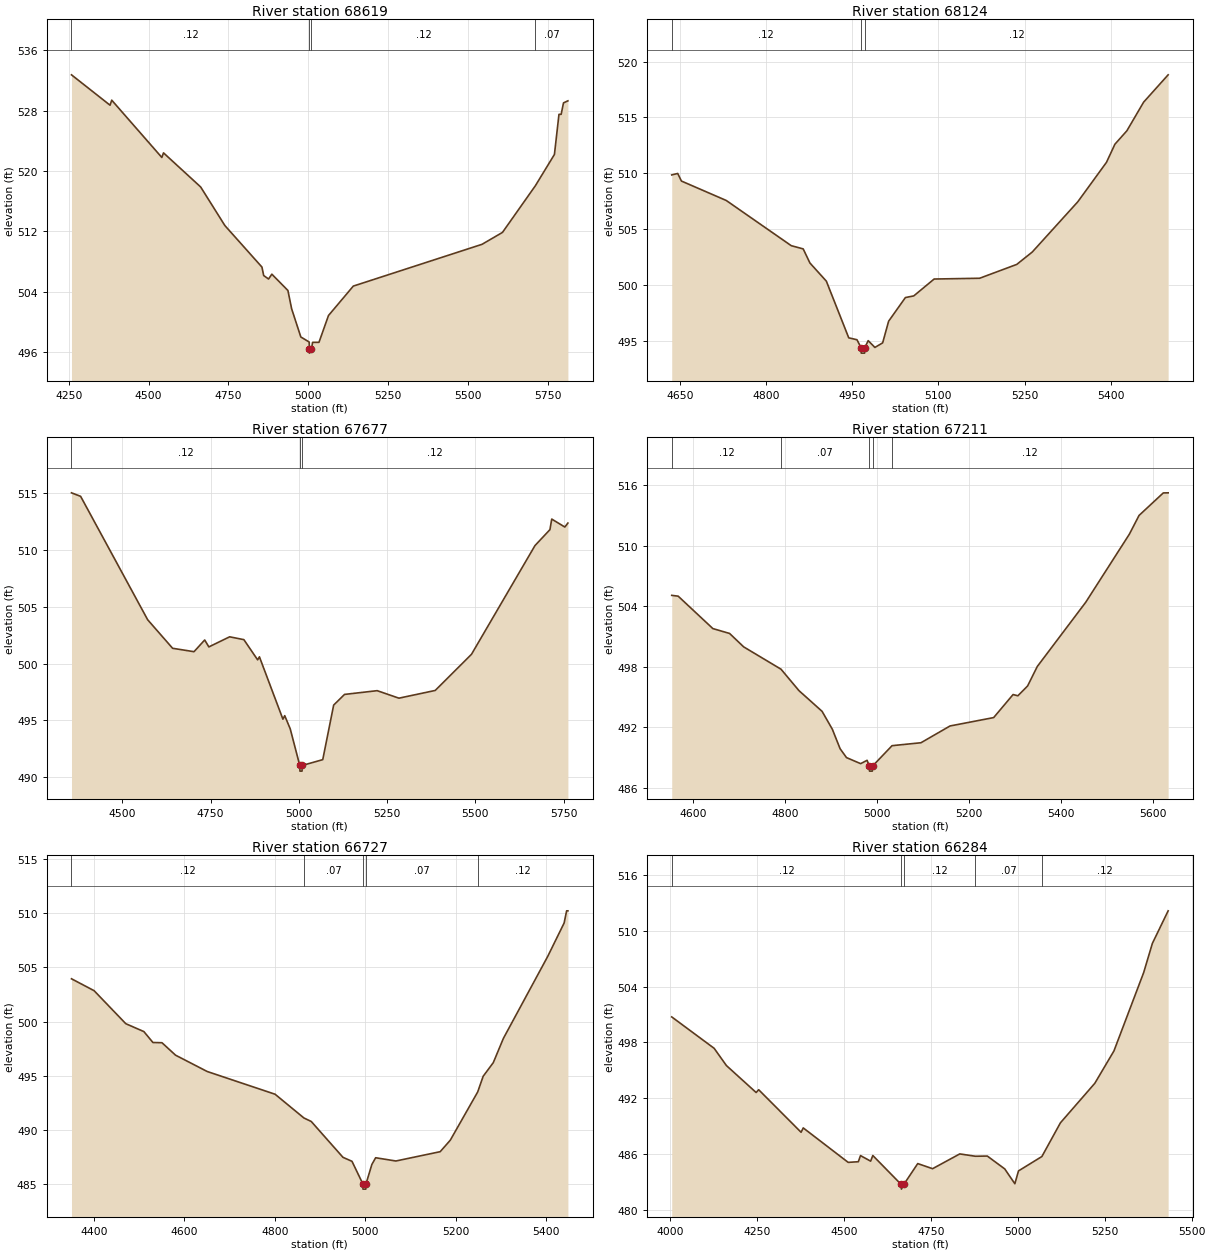
Type RM Length L Ch R = 1 ,68619   ,495,495,495
BEGIN DESCRIPTION:
ONEIL CREEK 7514
END DESCRIPTION:
XS GIS Cut Line= 3
      2347411.58     13716992.64        2347225.       13716275.
      2346625.03     13715725.02
#Sta/Elev= 30
  4258.5  532.75  4379.4  528.72  4384.6  529.39  4541.6  521.79  4546.8   522.4
  4663.2  517.88  4739.1  512.76  4855.3  507.25  4860.7  506.13    4876  505.67
  4886.3  506.31  4936.6  504.15  4948.3  501.72  4977.1  497.98  5003.4  497.31
  5003.7  496.34  5004.2  495.84  5010.4  496.34  5013.9  497.27  5033.9  497.27
  5063.8  500.83  5141.5  504.73  5544.8  510.27  5608.9  511.85  5711.8  518.03
  5771.7  522.19  5785.9  527.51  5792.7  527.51  5800.1  529.03  5813.9   529.3
#Mann= 4 ,-1 , 0
  4258.5     .12       0  5003.7     .05       0  5010.4     .12       0
  5711.8     .07       0
Bank Sta=5003.7,5010.4
XS Rating Curve= 0 ,0
Exp/Cntr=0.3,0.1

Type RM Length L Ch R = 1 ,68124   ,447,447,447
BEGIN DESCRIPTION:
ONEIL CREEK 7513
END DESCRIPTION:
XS GIS Cut Line= 3
        2347675.     13716274.99        2347575.       13715925.
        2347275.       13715525.
#Sta/Elev= 30
    4636  509.84  4646.4  509.97  4652.9  509.29  4730.9  507.55    4844   503.5
  4864.8  503.21  4876.5  501.95  4905.1  500.32  4944.1  495.24  4958.4  495.07
  4965.4  494.37  4965.9  493.87  4971.7  493.87  4972.2  494.37  4977.9  494.99
  4989.6  494.38  5003.1  494.79  5013.5  496.73  5042.7  498.85  5057.3     499
  5092.7  500.51  5171.9  500.58  5236.5  501.82  5263.5  502.93  5342.7  507.43
  5392.7  510.97  5407.3  512.59  5428.1  513.79  5457.3  516.36    5500  518.81
#Mann= 3 ,-1 , 0
    4636     .12       0  4965.4     .05       0  4972.2     .12       0
Bank Sta=4965.4,4972.2
XS Rating Curve= 0 ,0
Exp/Cntr=0.3,0.1

Type RM Length L Ch R = 1 ,67677   ,466,466,466
BEGIN DESCRIPTION:
ONEIL CREEK 7512
END DESCRIPTION:
XS GIS Cut Line= 3
      2348013.13     13716408.69        2347925.       13715775.
      2348101.46     13715029.29
#Sta/Elev= 30
    4356  515.03  4381.9  514.72  4571.8  503.86  4642.4  501.35    4703  501.05
  4733.3  502.08  4745.1  501.47    4804  502.36  4844.3  502.11  4883.3  500.33
  4888.3   500.6  4954.9  495.11    4960  495.42  4975.6  494.26  5002.6  491.04
  5003.1  490.54  5009.1  490.54  5009.6  491.04  5067.7  491.55  5098.6  496.35
  5129.4  497.29  5221.9  497.62  5283.5  496.96  5386.3  497.64    5489  500.82
  5668.9  510.39  5711.2  511.79  5716.3  512.72  5753.4  512.02  5762.1  512.37
#Mann= 3 ,-1 , 0
    4356     .12       0  5002.6     .05       0  5009.6     .12       0
Bank Sta=5002.6,5009.6
XS Rating Curve= 0 ,0
Exp/Cntr=0.3,0.1

Type RM Length L Ch R = 1 ,67211   ,484,484,484
BEGIN DESCRIPTION:
ONEIL CREEK 7511
END DESCRIPTION:
XS GIS Cut Line= 3
        2348175.     13716225.01        2348375.       13715825.
      2348575.01     13715224.98
#Sta/Elev= 30
  4552.8  505.07  4566.8  504.99  4642.3  501.78  4678.6   501.3  4709.3  499.97
  4790.5  497.76  4829.5  495.64  4879.8  493.59  4902.2  491.81    4919  489.89
  4932.9  489.01  4963.7  488.41  4977.7  488.74  4982.5  488.17    4983  487.67
  4989.1  487.67  4989.6  488.17    5032  490.19  5094.9  490.48  5158.1  492.14
    5253  492.97  5295.2  495.25  5305.7  495.13  5326.8   496.1  5347.9  498.03
  5453.3  504.39  5548.2  511.13  5569.2  512.98  5621.9  515.21  5632.5  515.22
#Mann= 5 ,-1 , 0
  4552.8     .12       0  4790.5     .07       0  4982.5     .05       0
  4989.6     .07       0    5032     .12       0
Bank Sta=4982.5,4989.6
XS Rating Curve= 0 ,0
Exp/Cntr=0.3,0.1

Type RM Length L Ch R = 1 ,66727   ,443,443,443
BEGIN DESCRIPTION:
ONEIL CREEK 7510
END DESCRIPTION:
XS GIS Cut Line= 3
        2348825.     13716374.97        2348825.       13715725.
      2348624.99     13715324.98
#Sta/Elev= 30
  4350.4  503.95  4400.4  502.85  4470.4   499.8  4510.4  499.07  4530.4  498.06
  4550.4  498.04  4580.4  496.89  4650.4  495.38  4800.4  493.28    4864  491.09
  4880.4  490.76  4950.4  487.45  4970.4  487.08  4994.2  485.01  4994.7  484.51
    5001  484.51  5001.5  485.01  5014.3  486.79  5022.7  487.41  5067.4  487.11
  5165.3  487.97  5187.6  489.03  5248.2  493.49  5260.3  494.94  5282.7   496.2
    5305  498.44  5402.9  506.01  5439.2   509.1  5444.8  510.23  5447.6  510.23
#Mann= 5 ,-1 , 0
  4350.4     .12       0    4864     .07       0  4994.2     .05       0
  5001.5     .07       0  5248.2     .12       0
Bank Sta=4994.2,5001.5
XS Rating Curve= 0 ,0
Exp/Cntr=0.3,0.1

Type RM Length L Ch R = 1 ,66284   ,471,471,471
BEGIN DESCRIPTION:
ONEIL CREEK 7509
END DESCRIPTION:
XS GIS Cut Line= 3
        2349675.       13716175.        2349075.       13715375.
        2348675.       13715225.
#Sta/Elev= 30
  4005.2  500.74  4127.1  497.36  4162.5   495.5  4247.9   492.6  4255.2   492.9
  4377.1  488.32  4383.3  488.79  4512.5  485.08  4541.7  485.15  4547.9  485.81
  4577.1  485.21  4583.3  485.82    4665   482.7  4665.5   482.2  4672.4   482.7
  4712.5  484.95  4755.2   484.4  4833.3  485.99    4878  485.74  4912.5  485.76
  4962.5  484.38  4991.7  482.78  5002.1  484.16  5069.4  485.71  5122.7  489.34
  5221.5  493.59  5276.6  497.08  5362.1  505.52    5387  508.65  5432.4  512.16
#Mann= 5 ,-1 , 0
  4005.2     .12       0    4665     .05       0  4672.4     .12       0
    4878     .07       0  5069.4     .12       0
Bank Sta=4665,4672.4
XS Rating Curve= 0 ,0
Exp/Cntr=0.3,0.1

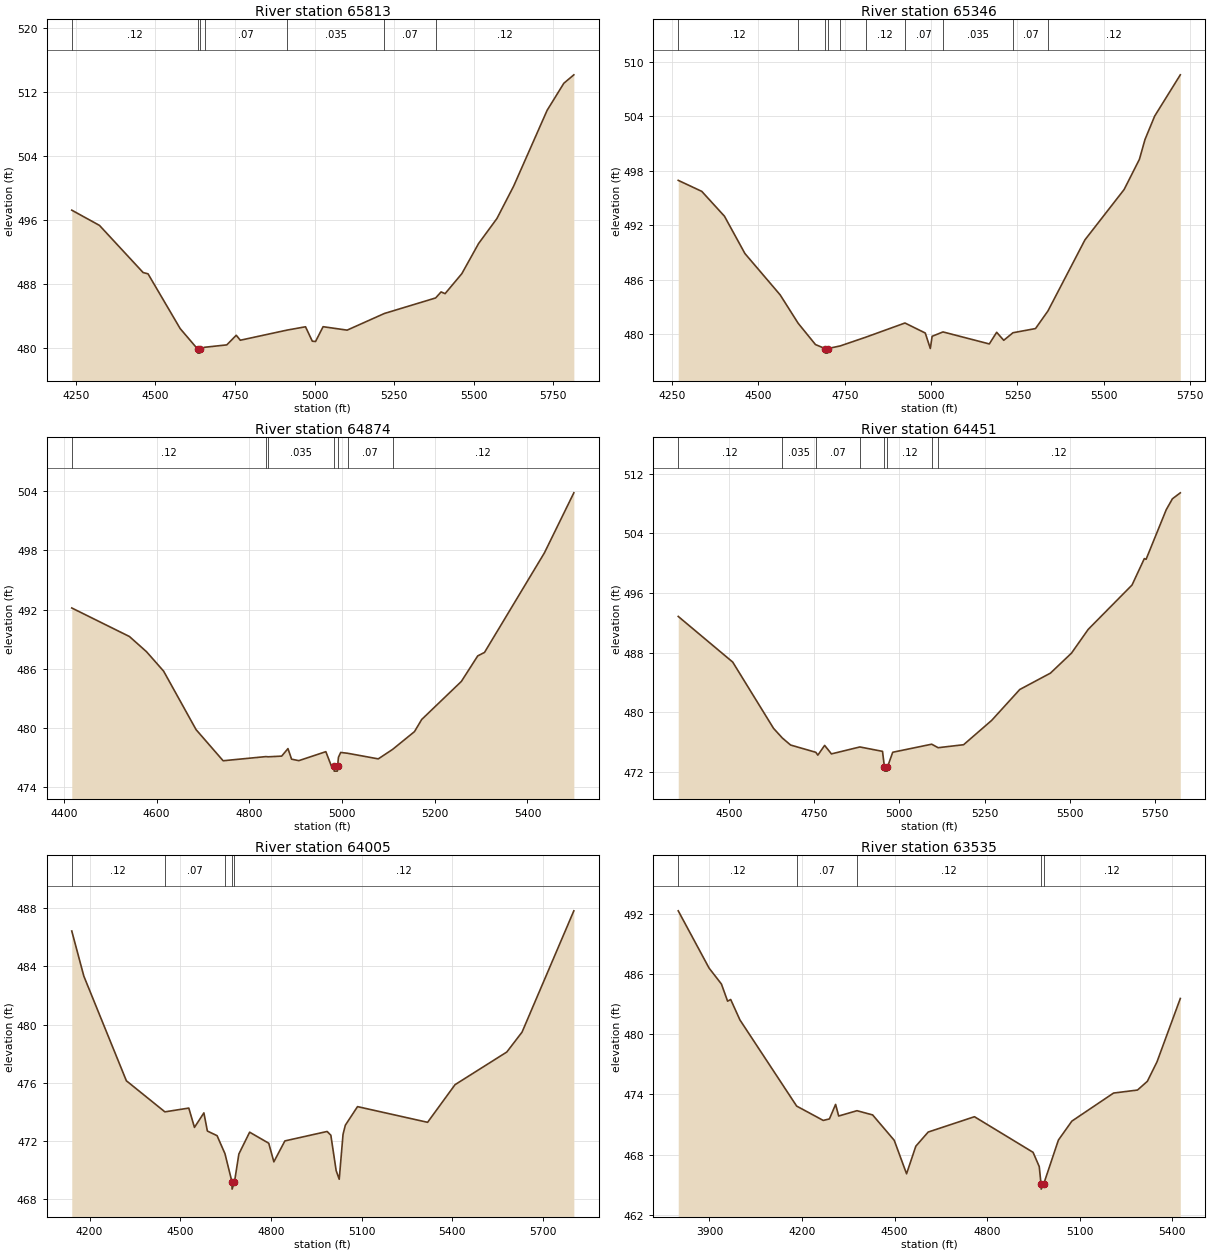
Type RM Length L Ch R = 1 ,65813   ,467,467,467
BEGIN DESCRIPTION:
ONEIL CREEK 7508
END DESCRIPTION:
XS GIS Cut Line= 3
      2350075.03     13715475.02        2349425.       13715075.
        2348625.       13714925.
#Sta/Elev= 30
    4237  497.24    4324  495.34  4461.2  489.45  4476.6  489.29  4577.6  482.45
  4632.6  479.89  4633.1  479.39  4639.5  479.39    4640  479.89  4654.3  480.12
    4724  480.42  4753.7  481.62  4766.5     481  4912.6  482.26  4971.3  482.68
  4992.6  480.88  5002.8  480.84  5026.5  482.69    5102  482.26    5219  484.34
  5380.1  486.28  5397.1  487.03  5409.8  486.82  5462.3  489.31  5514.9  493.07
  5572.6   496.2  5625.1  500.24  5730.3  509.71  5782.8  513.09  5814.2  514.14
#Mann= 7 ,-1 , 0
    4237     .12       0  4632.6    .035       0    4640     .12       0
  4654.3     .07       0  4912.6    .035       0    5219     .07       0
  5380.1     .12       0
Bank Sta=4632.6,4640
XS Rating Curve= 0 ,0
Exp/Cntr=0.3,0.1

Type RM Length L Ch R = 1 ,65346   ,472,472,472
BEGIN DESCRIPTION:
ONEIL CREEK 7507
END DESCRIPTION:
XS GIS Cut Line= 3
      2350075.01     13715425.02        2349725.       13714775.
      2349574.99     13714074.95
#Sta/Elev= 30
  4267.7  496.94  4335.9  495.73  4401.6     493  4460.8   488.9    4563  484.35
  4615.1  481.23  4665.2  478.89  4693.2  478.45  4693.7  477.95  4700.1  477.95
  4700.6  478.45  4736.7  478.74  4810.8   479.7  4924.4  481.26  4983.2  480.16
  4997.8  478.46  5003.1   479.8  5034.6  480.28  5168.7  478.96    5190  480.24
  5210.5  479.36  5237.2  480.19  5302.5  480.65  5338.6  482.59  5445.7   490.4
  5559.1  495.93  5603.4  499.25  5619.6  501.43  5647.7  504.01  5721.9  508.54
#Mann= 10 ,-1 , 0
  4267.7     .12       0  4615.1     .07       0  4693.2     .05       0
  4700.6     .07       0  4736.7    .035       0  4810.8     .12       0
  4924.4     .07       0  5034.6    .035       0  5237.2     .07       0
  5338.6     .12       0
Bank Sta=4693.2,4700.6
XS Rating Curve= 0 ,0
Exp/Cntr=0.3,0.1

Type RM Length L Ch R = 1 ,64874   ,423,423,423
BEGIN DESCRIPTION:
ONEIL CREEK 7506
END DESCRIPTION:
XS GIS Cut Line= 3
      2350324.98     13714924.97        2350025.       13714425.
      2349624.97     13714124.98
#Sta/Elev= 30
  4416.9  492.16  4541.3  489.27  4578.2  487.73  4615.1  485.76  4685.1  479.84
  4743.4  476.69  4835.4  477.11  4840.9  477.09  4869.7  477.16  4883.3  477.92
  4891.1  476.85  4906.7   476.7    4965  477.61  4976.6   476.2  4982.5  476.14
    4983  475.64  4989.8  475.64  4990.3  476.14  4992.2  477.04    4997  477.53
  5011.8  477.45  5078.1  476.88    5109  477.84  5156.2  479.64  5171.8  480.87
  5257.3  484.72  5292.7  487.31  5307.3  487.66  5436.4  497.73    5500  503.82
#Mann= 7 ,-1 , 0
  4416.9     .12       0  4835.4     .07       0  4840.9    .035       0
  4982.5    .035       0  4990.3    .035       0  5011.8     .07       0
    5109     .12       0
Bank Sta=4982.5,4990.3
XS Rating Curve= 0 ,0
Exp/Cntr=0.3,0.1

Type RM Length L Ch R = 1 ,64451   ,446,446,446
BEGIN DESCRIPTION:
ONEIL CREEK 7505
END DESCRIPTION:
XS GIS Cut Line= 3
        2350375.     13714875.05        2350375.       13714225.
      2349574.97     13714024.99
#Sta/Elev= 30
  4350.3  492.88  4510.3  486.76  4630.3  477.87  4656.1  476.58  4680.3  475.64
  4754.6  474.66  4760.3  474.28  4780.3  475.59  4800.3  474.45  4883.8  475.38
  4950.3  474.79  4956.1  472.64  4956.6  472.14    4964  472.14  4964.5  472.64
  4980.3  474.67  5094.8  475.75  5113.7  475.28  5188.5  475.68  5270.9  478.94
  5353.4  483.08  5443.6  485.28  5505.4  487.96  5554.4  491.14  5683.2  497.09
  5719.3  500.63  5724.5  500.54  5783.7  507.19  5801.8  508.65    5825  509.45
#Mann= 8 ,-1 , 0
  4350.3     .12       0  4656.1    .035       0  4754.6     .07       0
  4883.8     .12       0  4956.1     .05       0  4964.5     .12       0
  5094.8     .07       0  5113.7     .12       0
Bank Sta=4956.1,4964.5
XS Rating Curve= 0 ,0
Exp/Cntr=0.3,0.1

Type RM Length L Ch R = 1 ,64005   ,470,470,470
BEGIN DESCRIPTION:
ONEIL CREEK 7504
END DESCRIPTION:
XS GIS Cut Line= 3
      2351024.99     13714774.97        2350725.       13713975.
        2350625.       13713175.
#Sta/Elev= 30
  4141.1  486.44  4181.1  483.33  4321.7  476.13  4449.1  473.99  4528.2  474.25
  4546.9  472.92  4578.1  473.92  4589.6  472.67  4621.7  472.35  4647.8  471.11
  4670.9  469.17  4671.4  468.67  4679.3  469.17  4693.8  471.09  4729.4  472.59
  4792.6  471.83  4809.5  470.55    4846  471.99  4985.7  472.64    4998  472.38
  5015.6  469.94  5025.7  469.35  5038.3  472.44  5045.9  473.07  5086.2  474.35
    5318  473.27  5408.7  475.86    5580  478.11  5630.4  479.48  5801.7  487.83
#Mann= 5 ,-1 , 0
  4141.1     .12       0  4449.1     .07       0  4647.8     .12       0
  4670.9     .05       0  4679.3     .12       0
Bank Sta=4670.9,4679.3
XS Rating Curve= 0 ,0
Exp/Cntr=0.3,0.1

Type RM Length L Ch R = 1 ,63535   ,454,454,454
BEGIN DESCRIPTION:
ONEIL CREEK 7503
END DESCRIPTION:
XS GIS Cut Line= 3
        2351075.     13714875.01        2351075.       13713675.
        2350925.     13713275.01
#Sta/Elev= 30
  3799.1   492.3  3899.1  486.59  3939.1     485  3959.1  483.29  3969.1  483.46
  3999.1  481.42  4182.9  472.83  4269.1   471.4  4289.1  471.55  4309.1     473
  4319.1  471.84  4378.4  472.37  4429.1  471.95  4499.1  469.42  4539.1  466.08
  4569.1  468.83  4609.1  470.24  4759.1  471.77  4949.1  468.22  4969.1   466.8
  4974.9  465.05  4975.4  464.55  4983.4  465.05  5031.2  469.44  5074.8  471.33
    5210  474.13  5287.5  474.43  5319.5   475.3  5350.7  477.24  5426.3  483.56
#Mann= 5 ,-1 , 0
  3799.1     .12       0  4182.9     .07       0  4378.4     .12       0
  4974.9     .05       0  4983.4     .12       0
Bank Sta=4974.9,4983.4
XS Rating Curve= 0 ,0
Exp/Cntr=0.3,0.1

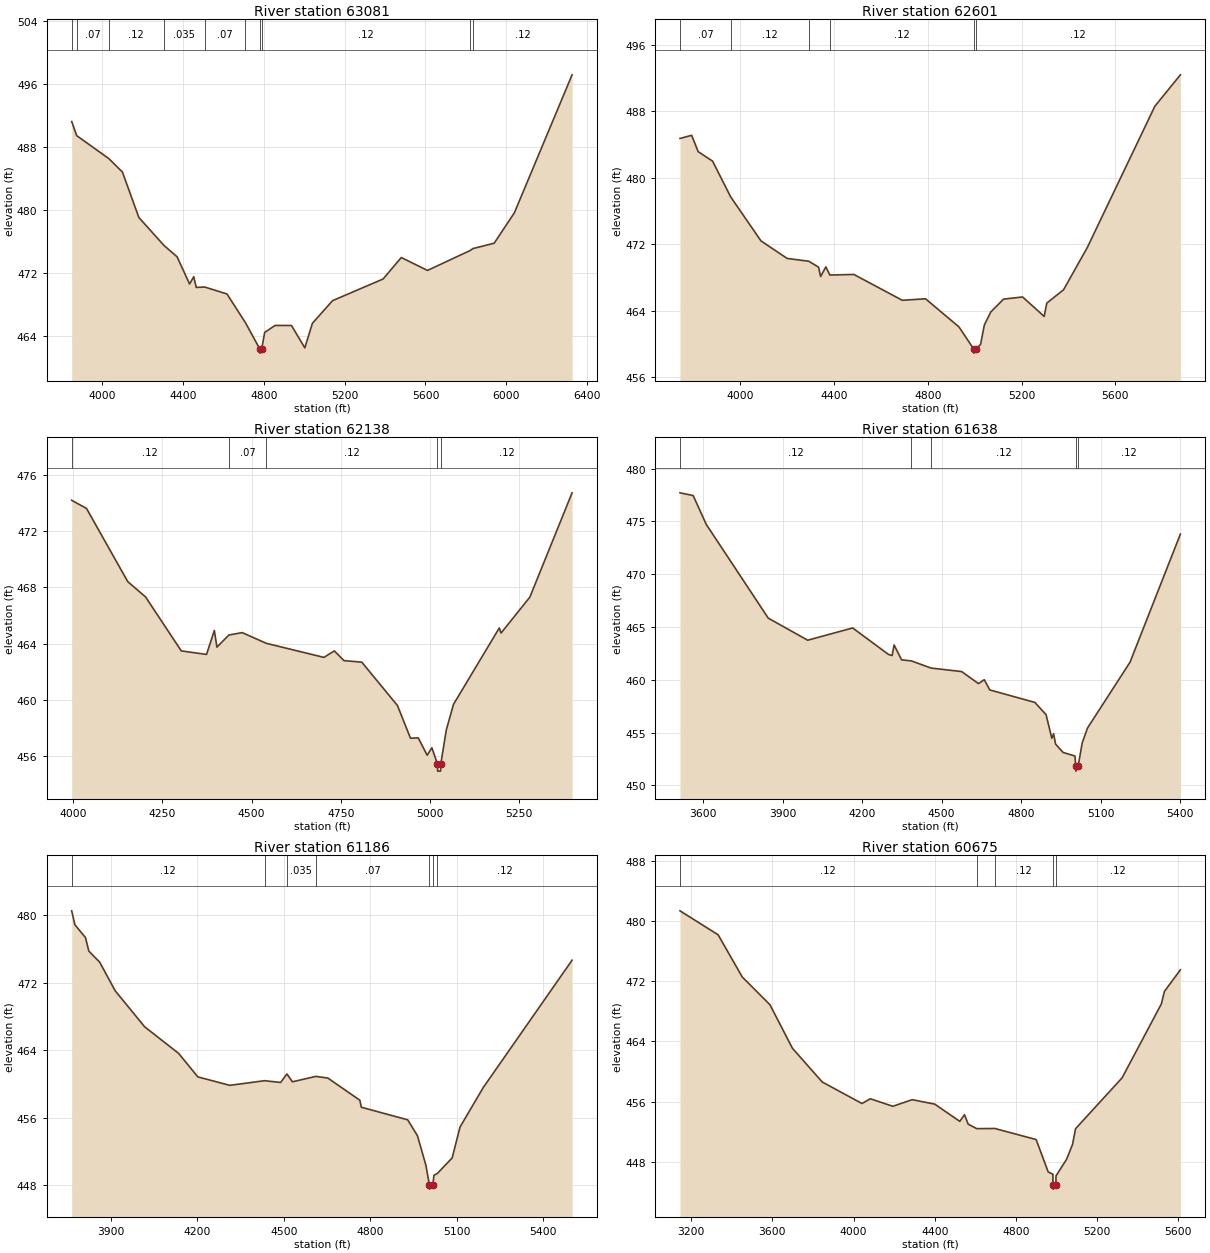
Type RM Length L Ch R = 1 ,63081   ,480,480,480
BEGIN DESCRIPTION:
ONEIL CREEK 7502
END DESCRIPTION:
XS GIS Cut Line= 3
      2351186.11     13714940.16        2351475.       13713825.
      2351445.62      13712499.3
#Sta/Elev= 30
    3848  491.22  3872.9  489.42  4031.7  486.51  4099.4  484.79  4180.6  479.02
  4304.9  475.47  4369.8  474.03  4431.8  470.57  4452.5  471.49  4464.8  470.13
  4506.8  470.18  4616.9   469.3  4708.7  465.64  4780.2  462.28  4780.7  461.78
  4788.7  462.28  4803.7  464.41  4855.3   465.3  4936.5  465.29  5002.5  462.45
    5040  465.57    5140  468.45  5390.1   471.2  5480.1  473.93  5610.1  472.29
  5821.2  474.82  5835.3  475.07  5940.2  475.75  6040.2  479.61    6326  497.15
#Mann= 10 ,-1 , 0
    3848     .12       0  3872.9     .07       0  4031.7     .12       0
  4304.9    .035       0  4506.8     .07       0  4708.7     .12       0
  4780.2     .05       0  4788.7     .12       0  5821.2     .07       0
  5835.3     .12       0
Bank Sta=4780.2,4788.7
XS Rating Curve= 0 ,0
Exp/Cntr=0.3,0.1

Type RM Length L Ch R = 1 ,62601   ,463,463,463
BEGIN DESCRIPTION:
ONEIL CREEK 7501
END DESCRIPTION:
XS GIS Cut Line= 3
      2351315.84     13714910.73      2351811.26      13713925.8
      2352035.06     13712918.68
#Sta/Elev= 30
  3743.1  484.73  3792.8  485.11  3820.7  483.14  3882.1     482  3959.2   477.7
  4088.5   472.4  4200.1  470.29  4292.4  469.95  4334.1  469.24  4342.8  468.11
  4365.2  469.27  4382.3  468.29  4484.7  468.36  4691.2  465.25  4790.5  465.43
  4932.8  462.05  4995.7  459.39  4996.2  458.89  5004.5  459.39  5024.9  459.92
  5041.1  462.27  5068.5  463.84    5123  465.39  5204.2  465.65  5296.4  463.31
  5307.4  464.91  5379.1  466.52  5480.8  471.63  5768.4  488.61  5877.3  492.39
#Mann= 6 ,-1 , 0
  3743.1     .07       0  3959.2     .12       0  4292.4     .07       0
  4382.3     .12       0  4995.7     .05       0  5004.5     .12       0
Bank Sta=4995.7,5004.5
XS Rating Curve= 0 ,0
Exp/Cntr=0.3,0.1

Type RM Length L Ch R = 1 ,62138   ,500,500,500
BEGIN DESCRIPTION:
ONEIL CREEK 7500
END DESCRIPTION:
XS GIS Cut Line= 3
      2351675.02     13714674.97        2352275.       13713875.
        2352325.     13713474.98
#Sta/Elev= 30
  3995.7  474.19  4037.3  473.61    4153  468.41    4203  467.32    4303  463.49
  4373.8  463.24  4395.7  464.94    4403  463.76  4436.6  464.62  4473.8  464.79
  4541.3  464.03    4703  463.03  4732.1  463.49  4759.2   462.8  4809.2  462.69
  4909.2  459.61  4945.7  457.29  4967.5  457.31  4992.5  456.08  5005.7  456.61
  5021.3  455.45  5021.8  454.95  5030.1  454.95  5030.6  455.45  5046.1  457.87
  5066.2  459.69  5194.7  465.12  5199.7  464.76  5280.4  467.31  5398.8  474.72
#Mann= 5 ,-1 , 0
  3995.7     .12       0  4436.6     .07       0  4541.3     .12       0
  5021.3     .05       0  5030.6     .12       0
Bank Sta=5021.3,5030.6
XS Rating Curve= 0 ,0
Exp/Cntr=0.3,0.1

Type RM Length L Ch R = 1 ,61638   ,452,452,452
BEGIN DESCRIPTION:
ONEIL CREEK 7499
END DESCRIPTION:
XS GIS Cut Line= 3
        2351775.       13714975.        2352775.       13713875.
        2352775.     13713475.01
#Sta/Elev= 30
  3513.4  477.71  3563.1  477.45  3612.4  474.72  3846.2  465.84  3994.9  463.75
  4164.5  464.91  4298.9  462.41  4313.1   462.3  4320.6   463.3  4348.9  461.89
  4385.7  461.79  4460.2  461.11  4575.3  460.78  4638.8  459.64  4660.5  460.01
  4681.4  459.04  4851.3  457.86  4893.6   456.7  4915.2  454.46    4922  454.89
  4929.4  453.91  4957.8  453.12  5002.5  452.78  5005.3  451.85  5005.8  451.35
  5014.7  451.85    5030  454.05    5050  455.44    5210  461.66    5400   473.8
#Mann= 5 ,-1 , 0
  3513.4     .12       0  4385.7     .07       0  4460.2     .12       0
  5005.3     .05       0  5014.7     .12       0
Bank Sta=5005.3,5014.7
XS Rating Curve= 0 ,0
Exp/Cntr=0.3,0.1

Type RM Length L Ch R = 1 ,61186   ,511,511,511
BEGIN DESCRIPTION:
ONEIL CREEK 7498
END DESCRIPTION:
XS GIS Cut Line= 3
      2352937.72     13715081.77      2353203.12       13713914.
      2353144.29     13713378.67
#Sta/Elev= 30
  3763.5  480.49  3774.7  478.84  3811.5  477.32  3822.9  475.73  3860.8  474.41
  3914.2  471.04  4016.6  466.77  4134.6  463.62  4201.2  460.84  4312.1  459.84
  4432.6  460.39  4488.3  460.18  4510.3  461.19  4529.3  460.26  4610.6   460.9
  4652.4   460.7  4763.3  458.08  4768.4  457.25  4929.3  455.76  4963.1  453.88
  4992.4  450.39  5004.5  448.06    5005  447.56  5016.2  448.06  5020.4   449.2
  5032.1  449.41  5083.5  451.25  5110.9  454.91  5191.4  459.58  5499.6  474.65
#Mann= 7 ,-1 , 0
  3763.5     .12       0  4432.6     .07       0  4510.3    .035       0
  4610.6     .07       0  5004.5     .05       0  5016.2     .07       0
  5032.1     .12       0
Bank Sta=5004.5,5016.2
XS Rating Curve= 0 ,0
Exp/Cntr=0.3,0.1

Type RM Length L Ch R = 1 ,60675   ,467,467,467
BEGIN DESCRIPTION:
ONEIL CREEK 7497
END DESCRIPTION:
XS GIS Cut Line= 3
        2354125.     13715675.01        2353675.       13713875.
      2353325.02     13713375.03
#Sta/Elev= 30
  3144.6  481.35  3332.7  478.16  3451.3  472.56  3587.8  468.87  3698.7  463.08
  3845.5   458.6  4041.4  455.74  4082.6  456.37  4193.4  455.37  4288.8  456.25
  4399.6  455.66  4523.3  453.37  4546.5  454.25  4564.5     453  4606.6   452.4
  4695.9  452.42  4899.5  450.95  4958.8  446.65    4982  446.34  4982.6  444.86
  4983.1  444.36  4996.8  444.86  4997.4  446.12  5049.3  448.31  5078.9  450.31
  5093.7  452.39    5323  459.15  5516.6  468.98  5531.4  470.63  5610.3  473.51
#Mann= 5 ,-1 , 0
  3144.6     .12       0  4606.6     .07       0  4695.9     .12       0
  4982.6     .05       0  4996.8     .12       0
Bank Sta=4982.6,4996.8
XS Rating Curve= 0 ,0
Exp/Cntr=0.3,0.1

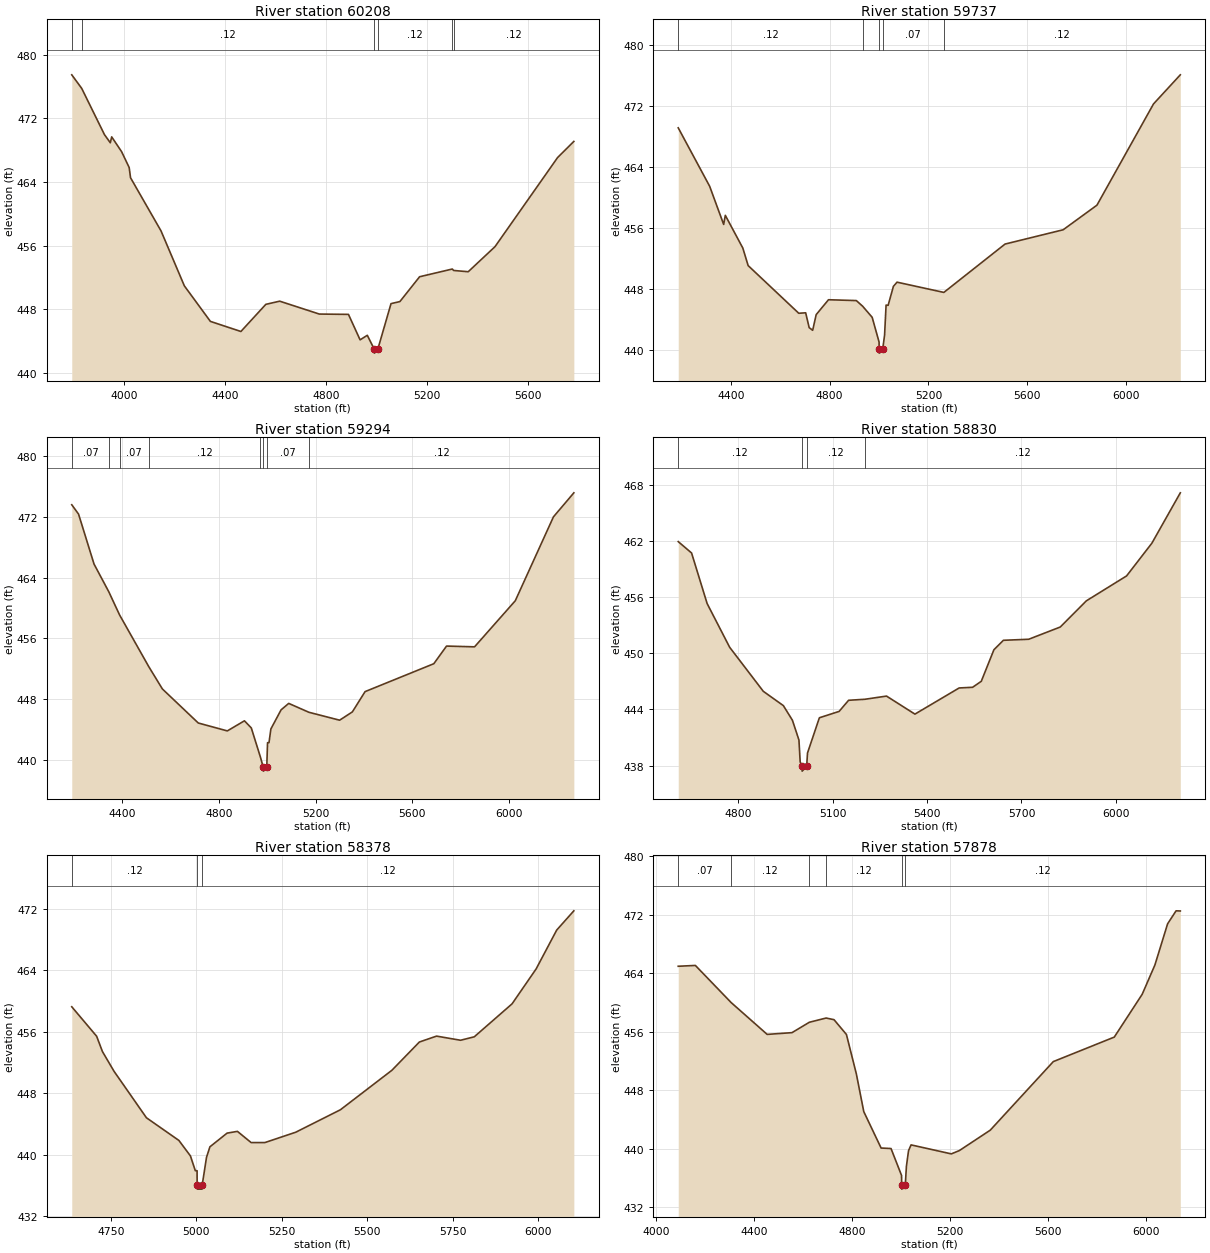
Type RM Length L Ch R = 1 ,60208   ,471,471,471
BEGIN DESCRIPTION:
ONEIL CREEK 7496
END DESCRIPTION:
XS GIS Cut Line= 3
        2355225.       13714325.        2354125.       13713825.
      2353525.03     13713325.02
#Sta/Elev= 30
  3792.5  477.48  3831.8  475.78  3922.1  469.96  3945.2  468.94  3950.7  469.68
  3990.2  467.81  4019.9  465.83  4025.4  464.54  4146.2  457.86  4238.5  450.96
  4341.7  446.49  4462.6  445.22  4561.4  448.63  4616.3  449.03  4773.4  447.41
  4888.8  447.37  4934.9  444.17  4963.5  444.74  4990.9     443  4991.4   442.5
  5005.2     443  5057.4  448.72  5092.6  448.98  5170.7   452.1  5300.2  453.07
  5305.5  452.89  5363.3  452.73  5469.4  455.88  5717.4  467.08  5781.8  469.11
#Mann= 6 ,-1 , 0
  3792.5     .07       0  3831.8     .12       0  4990.9     .05       0
  5005.2     .12       0  5300.2     .07       0  5305.5     .12       0
Bank Sta=4990.9,5005.2
XS Rating Curve= 0 ,0
Exp/Cntr=0.3,0.1

Type RM Length L Ch R = 1 ,59737   ,443,443,443
BEGIN DESCRIPTION:
ONEIL CREEK 7495
END DESCRIPTION:
XS GIS Cut Line= 3
      2355124.99     13714174.99        2354525.       13713625.
      2353524.99     13712924.99
#Sta/Elev= 30
  4186.3  469.15  4313.6   461.5  4370.4   456.5  4377.1  457.69    4448  453.41
  4469.6  451.11  4674.7  444.87  4702.7  444.93  4716.9  442.99  4731.1  442.64
  4745.3  444.69  4795.2  446.64    4908  446.53  4933.3   445.8  4972.2  444.34
  5000.2   441.1  5000.5  440.15    5001  439.65  5014.8  440.15  5022.5  442.01
  5028.6  445.94  5036.9  445.91  5058.2  448.39    5073  448.94  5262.7   447.6
  5510.7  453.93  5746.1   455.8    5883  459.02  6112.3  472.28  6220.9  476.09
#Mann= 5 ,-1 , 0
  4186.3     .12       0  4933.3     .07       0  5000.5     .05       0
  5014.8     .07       0  5262.7     .12       0
Bank Sta=5000.5,5014.8
XS Rating Curve= 0 ,0
Exp/Cntr=0.3,0.1

Type RM Length L Ch R = 1 ,59294   ,464,464,464
BEGIN DESCRIPTION:
ONEIL CREEK 7494
END DESCRIPTION:
XS GIS Cut Line= 3
      2355375.01     13713825.01        2354775.       13713275.
      2353574.97     13712874.99
#Sta/Elev= 30
  4190.6  473.57  4218.7  472.34  4282.8  465.77  4344.3   462.1  4388.5  459.08
  4509.9  452.25  4565.8  449.34  4714.4  444.86  4834.7  443.82  4905.6  445.15
    4934  444.21  4971.8  440.37  4983.4  439.03  4983.9  438.53    4998  439.03
  5001.2  442.27  5007.2  442.27  5015.1  444.08  5057.3  446.59  5088.9  447.44
  5172.6  446.27  5299.7  445.23  5352.4  446.32  5405.1  448.99  5689.7  452.66
  5742.4  454.98  5858.4  454.88    6027  460.94  6185.1  471.98  6269.5  475.14
#Mann= 8 ,-1 , 0
  4190.6     .07       0  4344.3     .12       0  4388.5     .07       0
  4509.9     .12       0  4971.8     .07       0  4983.4     .05       0
    4998     .07       0  5172.6     .12       0
Bank Sta=4983.4,4998
XS Rating Curve= 0 ,0
Exp/Cntr=0.3,0.1

Type RM Length L Ch R = 1 ,58830   ,452,452,452
BEGIN DESCRIPTION:
ONEIL CREEK 7493
END DESCRIPTION:
XS GIS Cut Line= 3
      2355225.04     13712674.97        2354925.       13712925.
      2353725.02       13712825.
#Sta/Elev= 30
  4609.9  461.96  4652.3  460.74  4701.7  455.33  4773.3  450.65  4880.1  445.94
  4943.8  444.41  4972.5  442.85  4993.3  440.73  4997.2  438.39  5003.1   437.9
  5003.6   437.4  5017.8   437.9  5020.5  439.34  5058.2  443.11  5120.9  443.79
    5151  444.98  5203.2  445.09  5271.4  445.43  5361.7   443.5  5502.2   446.3
  5544.8  446.37  5572.4  447.01  5612.6  450.39  5642.7   451.4    5723  451.51
  5823.3  452.82  5906.1  455.62    6034  458.29  6114.3  461.79  6204.6  467.18
#Mann= 4 ,-1 , 0
  4609.9     .12       0  5003.1     .05       0  5017.8     .12       0
  5203.2     .12       0
Bank Sta=5003.1,5017.8
XS Rating Curve= 0 ,0
Exp/Cntr=0.3,0.1

Type RM Length L Ch R = 1 ,58378   ,500,500,500
BEGIN DESCRIPTION:
ONEIL CREEK 7492
END DESCRIPTION:
XS GIS Cut Line= 3
      2355124.97     13712425.01        2354775.       13712525.
      2353675.01       13712425.
#Sta/Elev= 30
    4636  459.27  4708.8  455.43  4725.7  453.44  4759.5  450.88  4854.4  444.82
  4949.3  441.87  4983.1  439.85  4997.4  437.93  5002.5  437.93  5002.7  436.03
  5003.2  435.53  5016.9  435.53  5017.4  436.03  5030.1  439.67  5040.1  441.04
  5090.3  442.82  5120.5  443.05  5160.6  441.59  5200.8  441.59  5291.2  442.94
  5421.7  445.86  5572.3     451  5652.7  454.68  5702.9  455.45  5773.2  454.91
  5813.3  455.36  5923.8  459.65  5994.1  464.19  6054.3  469.25  6104.5  471.76
#Mann= 3 ,-1 , 0
    4636     .12       0  5002.7     .05       0  5017.4     .12       0
Bank Sta=5002.7,5017.4
XS Rating Curve= 0 ,0
Exp/Cntr=0.3,0.1

Type RM Length L Ch R = 1 ,57878   ,482,482,482
BEGIN DESCRIPTION:
ONEIL CREEK 7491
END DESCRIPTION:
XS GIS Cut Line= 3
      2355674.22     13712156.48        2354775.       13712025.
      2353674.96     13712325.01
#Sta/Elev= 30
  4090.8  464.96  4160.8  465.07  4306.9  459.99  4453.8  455.64  4555.1  455.88
  4625.9   457.3  4694.5  457.88  4726.7  457.65  4777.2  455.63  4817.7  450.24
    4848  445.08  4918.7   440.1  4959.2  440.03  5002.2  436.35  5002.6  434.98
  5003.1  434.48  5017.3  434.98    5022   437.6  5030.7  439.74    5041  440.53
  5205.2   439.3    5238  439.75  5364.1  442.54  5621.5  451.92  5870.3  455.27
  5984.3  461.13  6036.1  465.13  6087.9  470.76  6122.5  472.54  6139.8  472.52
#Mann= 6 ,-1 , 0
  4090.8     .07       0  4306.9     .12       0  4625.9     .07       0
  4694.5     .12       0  5002.6     .05       0  5017.3     .12       0
Bank Sta=5002.6,5017.3
XS Rating Curve= 0 ,0
Exp/Cntr=0.3,0.1