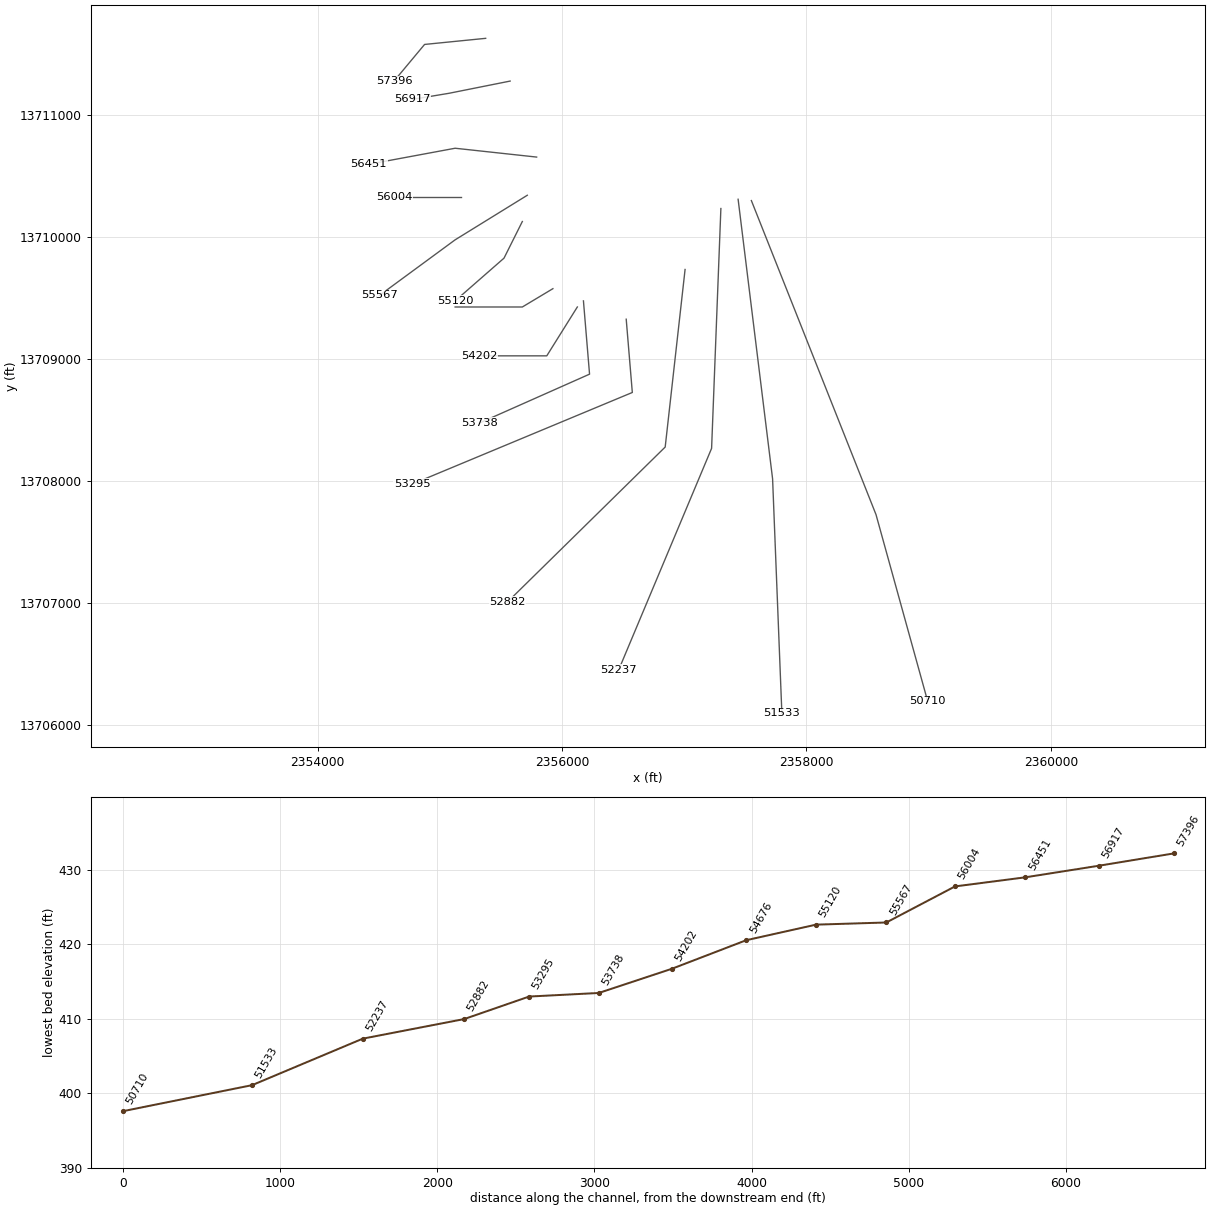
HEC-RAS study ONEIL CREEK.prj: ONEIL CREEK Base Level Engineering

--- ONEIL CREEK.g01 (geometry) --- (continued)

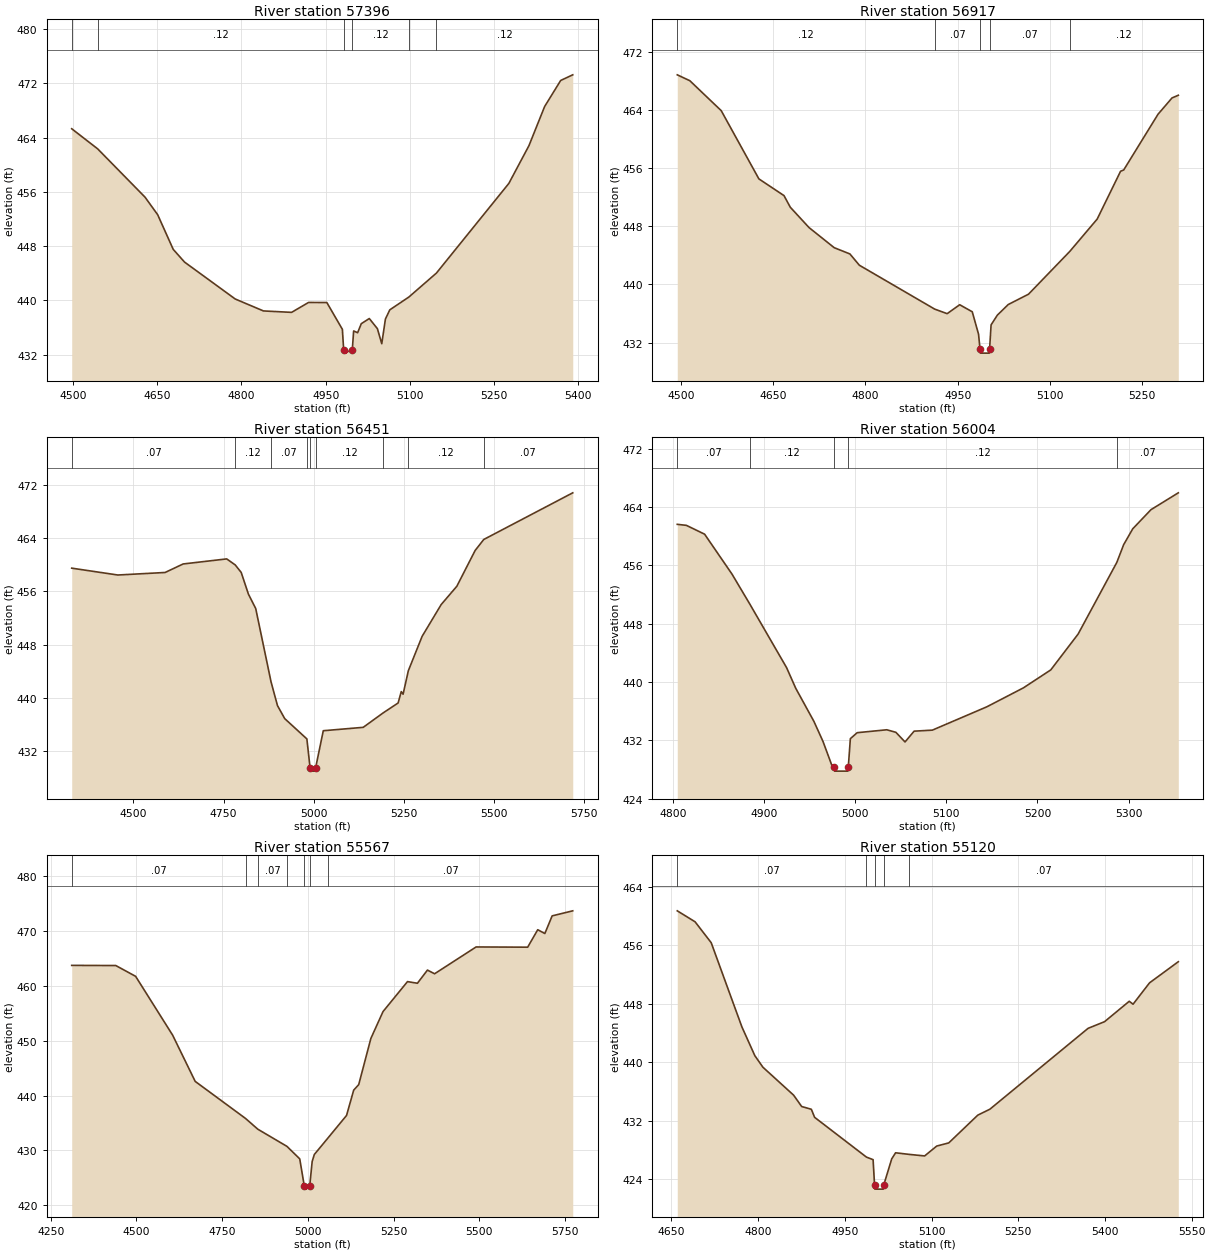
Type RM Length L Ch R = 1 ,57396   ,479,479,479
BEGIN DESCRIPTION:
ONEIL CREEK 7490
END DESCRIPTION:
XS GIS Cut Line= 3
      2355374.96       13711625.        2354875.       13711575.
      2354624.98     13711274.98
#Sta/Elev= 30
  4497.4  465.29  4543.6  462.33    4628  455.21  4650.6  452.62  4678.3  447.51
  4698.4  445.64  4788.8  440.19  4839.1  438.43  4889.3  438.22  4919.5  439.68
  4952.1  439.67  4979.8  435.72  4982.1  432.71  4982.6  432.21  4997.5  432.71
  4999.9  435.48    5007  435.22  5013.5  436.55  5027.8  437.31  5042.2  435.82
    5050   433.6  5056.5  437.23  5064.3  438.59  5098.3  440.48  5147.4  444.01
  5276.5  457.23  5312.3  462.79  5340.3  468.57  5368.9  472.41  5390.4  473.24
#Mann= 6 ,-1 , 0
  4497.4     .07       0  4543.6     .12       0  4982.1     .05       0
  4997.5     .12       0  5098.3     .07       0  5147.4     .12       0
Bank Sta=4982.1,4997.5
XS Rating Curve= 0 ,0
Exp/Cntr=0.3,0.1

Type RM Length L Ch R = 1 ,56917   ,466,466,466
BEGIN DESCRIPTION:
ONEIL CREEK 7489
END DESCRIPTION:
XS GIS Cut Line= 3
      2355575.02       13711275.        2355075.       13711175.
      2354774.96     13711124.99
#Sta/Elev= 30
  4494.4  468.85  4514.8  468.04  4565.8  463.92    4627  454.53  4667.8  452.23
    4678  450.63  4708.6  447.82  4749.4  445.06  4774.9   444.2  4790.2  442.65
  4912.6  436.61  4932.9  435.98  4953.3  437.21  4973.7  436.24  4983.9  433.16
  4986.4  431.05  4986.9  430.55  5001.3  430.55  5001.8  431.05  5004.3  434.44
  5014.5  435.78  5032.2  437.24  5065.1  438.66  5132.2  444.55  5176.7     449
  5214.7  455.58  5219.8  455.76  5275.5  463.42  5298.3  465.67  5308.5  466.04
#Mann= 5 ,-1 , 0
  4494.4     .12       0  4912.6     .07       0  4986.4     .05       0
  5001.8     .07       0  5132.2     .12       0
Bank Sta=4986.4,5001.8
XS Rating Curve= 0 ,0
Exp/Cntr=0.3,0.1

Type RM Length L Ch R = 1 ,56451   ,447,447,447
BEGIN DESCRIPTION:
ONEIL CREEK 7488
END DESCRIPTION:
XS GIS Cut Line= 3
      2355792.17     13710652.58        2355125.       13710725.
      2354418.98     13710593.77
#Sta/Elev= 30
    4329   459.5  4456.9  458.47  4587.9  458.85    4638  460.13  4758.7  460.89
  4782.3  459.99  4798.9  458.86    4819  455.59  4839.2  453.43  4881.7  442.41
  4899.5  438.85  4919.6  436.89    4981  433.84  4989.9   429.5  4990.4     429
  5004.8     429  5005.3   429.5  5026.5  435.07  5137.2  435.58  5192.8  437.76
    5234  439.24  5242.7  440.95  5247.8  440.56  5262.3  444.08  5300.6  449.26
  5353.4  454.03  5396.8  456.78  5447.6  462.16  5471.5  463.81  5718.2  470.82
#Mann= 9 ,-1 , 0
    4329     .07       0  4782.3     .12       0  4881.7     .07       0
    4981     .12       0  4989.9     .05       0  5005.3     .12       0
  5192.8     .07       0  5262.3     .12       0  5471.5     .07       0
Bank Sta=4989.9,5005.3
XS Rating Curve= 0 ,0
Exp/Cntr=0.3,0.1

Type RM Length L Ch R = 1 ,56004   ,437,437,437
BEGIN DESCRIPTION:
ONEIL CREEK 7487
END DESCRIPTION:
XS GIS Cut Line= 3
      2355174.97       13710325.        2354975.       13710325.
      2354624.97       13710325.
#Sta/Elev= 30
  4804.6  461.62  4814.6  461.48  4834.6  460.27  4864.6  454.81  4884.4  450.65
  4924.6  441.97  4934.6  439.15  4954.6   434.6  4964.6  431.84  4974.6  428.46
  4976.8  428.28  4977.3  427.78  4991.8  427.78  4992.3  428.28  4994.6  432.23
  5002.1  433.05  5034.6  433.45  5044.6   433.1  5054.6  431.78  5064.6  433.26
  5084.6   433.4  5144.6  436.61  5184.6   439.2  5214.6  441.66  5244.6  446.57
  5287.1   456.4  5294.6  458.83  5304.6  461.01  5324.6  463.63  5354.6  465.94
#Mann= 5 ,-1 , 0
  4804.6     .07       0  4884.4     .12       0  4976.8     .05       0
  4992.3     .12       0  5287.1     .07       0
Bank Sta=4976.8,4992.3
XS Rating Curve= 0 ,0
Exp/Cntr=0.3,0.1

Type RM Length L Ch R = 1 ,55567   ,447,447,447
BEGIN DESCRIPTION:
ONEIL CREEK 7486
END DESCRIPTION:
XS GIS Cut Line= 3
      2355715.55       13710340.        2355125.       13709975.
      2354506.55     13709520.24
#Sta/Elev= 30
  4311.1  463.75  4439.7  463.72  4497.6  461.75  4605.6  451.02  4671.4  442.59
  4818.3  435.83  4854.1  433.87  4939.1  430.74  4976.4  428.46  4989.9  423.44
  4990.4  422.94  5005.4  423.44  5012.7  427.98  5018.9  429.25  5059.6  432.33
    5113  436.38  5133.8  440.99  5148.5     442    5184  450.43  5219.5  455.33
  5290.8  460.79  5319.8  460.49    5349  462.89  5369.9  462.22    5491  467.11
  5641.5  467.07  5670.8  470.25  5691.6  469.56  5712.9  472.78    5773   473.7
#Mann= 7 ,-1 , 0
  4311.1     .07       0  4818.3     .12       0  4854.1     .07       0
  4939.1     .12       0  4989.9     .05       0  5005.4     .12       0
  5059.6     .07       0
Bank Sta=4989.9,5005.4
XS Rating Curve= 0 ,0
Exp/Cntr=0.3,0.1

Type RM Length L Ch R = 1 ,55120   ,444,444,444
BEGIN DESCRIPTION:
ONEIL CREEK 7485
END DESCRIPTION:
XS GIS Cut Line= 3
      2355675.01     13710125.02        2355525.       13709825.
      2355125.03     13709475.03
#Sta/Elev= 30
  4660.1  460.71  4690.9  459.21  4718.8  456.35  4771.9  444.84  4794.3   440.9
  4808.3  439.32  4861.4   435.5  4875.3  433.95  4892.1  433.57  4897.7  432.47
  4987.4  427.03  4998.9  426.68  5001.5  423.15    5002  422.65  5016.6  422.65
  5017.1  423.15  5031.1  426.78  5037.8  427.62  5061.4   427.4  5088.1  427.19
    5109  428.54  5129.8  428.97  5180.1  432.77    5201  433.58  5370.9  444.64
  5399.4  445.55  5442.1  448.34  5448.7  447.94  5477.2  450.86    5527  453.75
#Mann= 5 ,-1 , 0
  4660.1     .07       0  4987.4     .12       0  5001.5     .05       0
  5017.1     .12       0  5061.4     .07       0
Bank Sta=5001.5,5017.1
XS Rating Curve= 0 ,0
Exp/Cntr=0.3,0.1

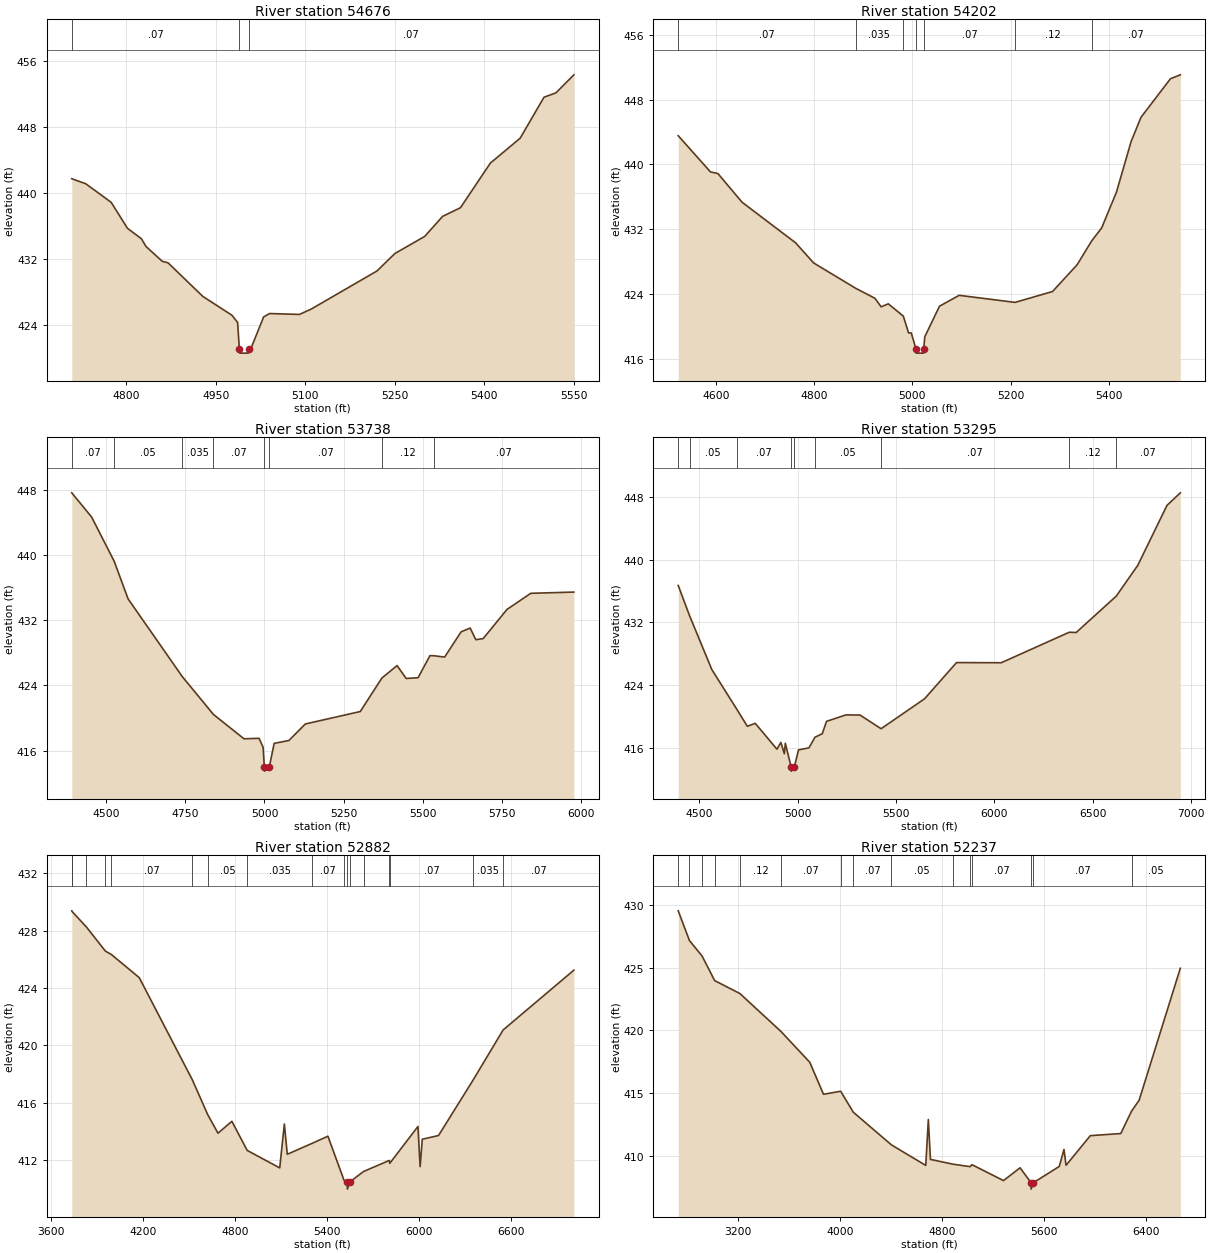
Type RM Length L Ch R = 1 ,54676   ,474,474,474
BEGIN DESCRIPTION:
ONEIL CREEK 7484
END DESCRIPTION:
XS GIS Cut Line= 3
      2355925.03     13709575.02        2355675.       13709425.
      2355124.99       13709425.
#Sta/Elev= 30
  4708.4  441.75  4731.8  441.14  4774.5  438.88  4801.7  435.73  4825.1  434.46
  4832.8  433.52    4860  431.72  4869.8  431.53  4928.1  427.45  4976.7  425.17
  4986.4  424.29  4989.3  421.06  4989.8  420.56  5004.4  420.56  5004.9  421.06
    5010  421.35    5030  424.96    5040  425.37    5090  425.26    5110  425.92
    5220  430.54    5250  432.66    5300  434.74    5330  437.17    5360  438.23
    5410  443.64    5460  446.67    5500  451.65    5520  452.18    5550  454.37
#Mann= 3 ,-1 , 0
  4708.4     .07       0  4989.3     .05       0  5004.9     .07       0
Bank Sta=4989.3,5004.9
XS Rating Curve= 0 ,0
Exp/Cntr=0.3,0.1

Type RM Length L Ch R = 1 ,54202   ,464,464,464
BEGIN DESCRIPTION:
ONEIL CREEK 7483
END DESCRIPTION:
XS GIS Cut Line= 3
      2356125.02     13709425.03        2355875.       13709025.
      2355325.04       13709025.
#Sta/Elev= 30
  4523.5  443.54    4589  439.08  4604.3  438.87  4653.3  435.34  4762.3  430.33
  4798.9  427.85  4884.3  424.73  4923.9  423.48  4936.3  422.43    4951   422.8
  4981.5  421.29  4992.3  419.21  4997.7  419.21  5007.4  417.22  5007.9  416.72
  5022.5  416.72    5023  417.22  5025.2  418.74  5055.2  422.51  5095.2  423.85
    5209  422.98  5285.2  424.32  5335.2  427.62  5364.7  430.55  5385.2  432.17
  5415.2  436.57  5445.2  442.84  5465.2  445.81  5525.2  450.57  5545.2  451.05
#Mann= 7 ,-1 , 0
  4523.5     .07       0  4884.3    .035       0  4981.5     .07       0
  5007.4     .05       0    5023     .07       0    5209     .12       0
  5364.7     .07       0
Bank Sta=5007.4,5023
XS Rating Curve= 0 ,0
Exp/Cntr=0.3,0.1

Type RM Length L Ch R = 1 ,53738   ,443,443,443
BEGIN DESCRIPTION:
ONEIL CREEK 7482
END DESCRIPTION:
XS GIS Cut Line= 3
        2356175.     13709474.97        2356225.       13708875.
      2355325.04     13708475.02
#Sta/Elev= 30
    4391  447.66  4453.7  444.69  4524.9  439.27  4569.1  434.63  4740.3  425.09
  4838.8  420.44  4935.4  417.45    4983  417.51  4995.8  416.41  4999.6  413.98
  5000.1  413.48  5015.3  413.98  5030.7  416.89  5077.2  417.24  5129.2  419.27
  5302.9   420.8  5371.3  424.92  5419.2  426.44  5447.9  424.86  5485.5  424.95
  5523.1  427.66  5535.6  427.65  5569.6  427.49  5621.6  430.59  5650.3  431.05
  5668.1  429.62  5691.4  429.76  5766.6  433.34  5841.8  435.32  5977.9  435.47
#Mann= 8 ,-1 , 0
    4391     .07       0  4524.9     .05       0  4740.3    .035       0
  4838.8     .07       0  4999.6     .05       0  5015.3     .07       0
  5371.3     .12       0  5535.6     .07       0
Bank Sta=4999.6,5015.3
XS Rating Curve= 0 ,0
Exp/Cntr=0.3,0.1

Type RM Length L Ch R = 1 ,53295   ,413,413,413
BEGIN DESCRIPTION:
ONEIL CREEK 7481
END DESCRIPTION:
XS GIS Cut Line= 3
        2356525.     13709325.02        2356575.       13708725.
        2354775.       13707975.
#Sta/Elev= 30
  4393.6  436.69  4451.2  432.83  4564.2  425.97    4692  420.87  4744.8  418.72
    4785   419.1  4895.3   415.8  4915.4  416.66    4933  415.22    4938  416.56
  4967.8   413.5  4968.3     413  4983.5   413.5  5004.9  415.71    5058  415.97
  5088.5  417.32  5125.7  417.77  5147.4  419.35  5246.5  420.18    5318  420.15
  5424.7  418.41  5645.7  422.23  5808.2  426.85  6035.7  426.83  6381.2  430.72
  6416.5  430.69  6620.1  435.33  6729.6  439.26    6878  446.91  6945.7  448.51
#Mann= 9 ,-1 , 0
  4393.6     .07       0  4451.2     .05       0    4692     .07       0
  4967.8     .05       0  4983.5     .07       0  5088.5     .05       0
  5424.7     .07       0  6381.2     .12       0  6620.1     .07       0
Bank Sta=4967.8,4983.5
XS Rating Curve= 0 ,0
Exp/Cntr=0.3,0.1

Type RM Length L Ch R = 1 ,52882   ,645,645,645
BEGIN DESCRIPTION:
B19902
END DESCRIPTION:
XS GIS Cut Line= 3
      2357006.73     13709732.18      2356843.97     13708278.15
      2355553.46     13707009.32
#Sta/Elev= 30
  3734.9  429.39  3736.3  429.35  3830.6  428.26  3954.2  426.58  3992.3  426.35
  4174.8  424.73  4521.1   417.6  4620.5  415.19    4688  413.88  4778.6  414.71
  4878.5  412.68  5090.5  411.46  5120.7  414.52  5139.8  412.41    5299  413.16
  5404.6  413.67  5510.4  410.58  5531.1  410.48  5531.6  409.98  5546.8  410.48
  5637.2  411.21  5804.6  411.98  5807.9  411.78  5991.5  414.35  6005.7  411.55
  6019.8  413.46  6125.8  413.72    6353  417.62  6546.7  421.08  7007.8  425.25
#Mann= 17 ,-1 , 0
  3734.9     .07       0  3736.3     .12       0  3830.6     .07       0
  3954.2     .12       0  3992.3     .07       0  4521.1    .035       0
  4620.5     .05       0  4878.5    .035       0    5299     .07       0
  5510.4    .035       0  5531.1    .035       0  5546.8    .035       0
  5637.2     .05       0  5804.6    .035       0  5807.9     .07       0
    6353    .035       0  6546.7     .07       0
Bank Sta=5531.1,5546.8
XS Rating Curve= 0 ,0
Exp/Cntr=0.3,0.1

Type RM Length L Ch R = 1 ,52237   ,704,704,704
BEGIN DESCRIPTION:
B19901
END DESCRIPTION:
XS GIS Cut Line= 3
       2357299.7      13710231.3      2357223.74      13708267.3
      2356464.19     13706455.22
#Sta/Elev= 30
  2735.6  429.53  2823.5  427.16  2922.2  425.93  3020.8  423.97  3218.1  422.94
  3539.5  419.92  3765.3  417.46  3872.8  414.91  4007.3  415.15    4106  413.48
  4404.1  410.88  4673.3  409.24  4693.4   412.9  4709.9  409.72  4885.4  409.34
  5021.9  409.14  5034.3   409.3  5281.8  408.03  5411.5  409.05  5498.1  407.85
  5498.6  407.35  5513.8  407.85  5718.5  409.16  5755.3  410.51  5771.5  409.25
  5961.3  411.61  6199.9  411.78    6284  413.56  6343.4  414.43  6665.9  424.95
#Mann= 15 ,-1 , 0
  2735.6    .035       0  2823.5     .07       0  2922.2     .12       0
  3020.8     .07       0  3218.1     .12       0  3539.5     .07       0
  4007.3    .035       0    4106     .07       0  4404.1     .05       0
  4885.4     .07       0  5021.9    .035       0  5034.3     .07       0
  5498.1     .05       0  5513.8     .07       0    6284     .05       0
Bank Sta=5498.1,5513.8
XS Rating Curve= 0 ,0
Exp/Cntr=0.3,0.1

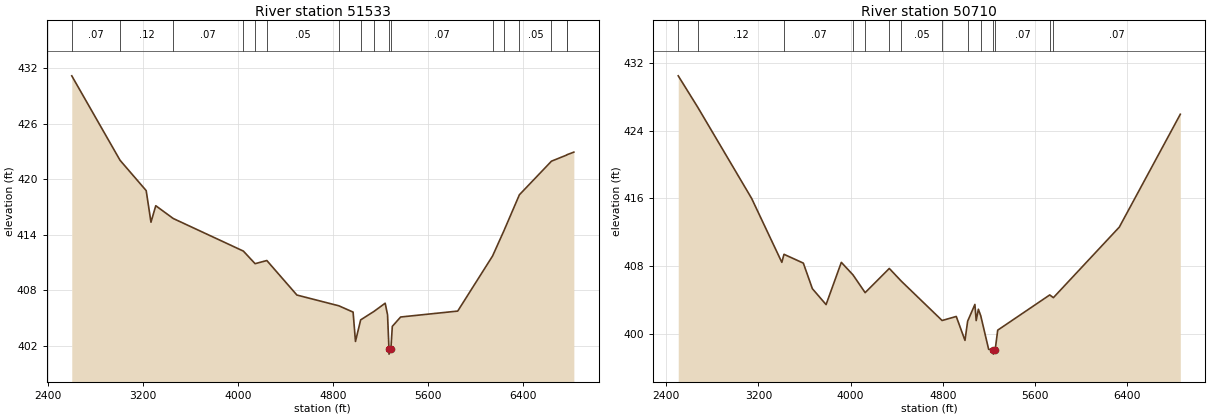
Type RM Length L Ch R = 1 ,51533   ,823,823,823
BEGIN DESCRIPTION:
B19900
END DESCRIPTION:
XS GIS Cut Line= 3
      2357440.76     13710307.23      2357722.88     13708017.73
      2357798.83     13706097.15
#Sta/Elev= 30
  2600.8  431.17  3007.4  422.05  3227.7  418.77    3268  415.36  3308.3  417.14
  3455.4  415.76  4046.1  412.24    4145  410.88  4243.8  411.22  4497.3  407.49
  4850.1  406.33  4970.4  405.65  4990.4  402.48  5034.1  404.81  5145.8  405.72
  5240.6  406.61  5260.6  405.36  5272.7  401.61  5273.2  401.11  5288.5  401.61
  5300.7  404.11  5370.7  405.12  5851.6  405.76  6144.7   411.7  6239.6   414.4
    6371  418.32  6641.1  421.95    6769  422.61  6770.6  422.64  6829.7  422.93
#Mann= 17 ,-1 , 0
  2600.8     .07       0  3007.4     .12       0  3455.4     .07       0
  4046.1    .035       0    4145     .07       0  4243.8     .05       0
  4850.1     .07       0  5034.1    .035       0  5145.8     .07       0
  5272.7     .05       0  5288.5     .07       0  6144.7     .05       0
  6239.6     .07       0    6371     .05       0  6641.1     .07       0
    6769     .05       0  6770.6     .07       0
Bank Sta=5272.7,5288.5
XS Rating Curve= 0 ,0
Exp/Cntr=0.3,0.1

Type RM Length L Ch R = 1 ,50710   ,792,792,792
BEGIN DESCRIPTION:
B19899
END DESCRIPTION:
XS GIS Cut Line= 3
      2357549.25     13710296.41      2358569.23     13707724.76
       2358992.4     13706194.85
#Sta/Elev= 30
  2505.1  430.48  2675.7  426.74  3141.3  416.01  3403.6  408.45  3422.2   409.4
  3589.9  408.36  3668.3  405.34  3787.1  403.46  3919.4  408.45  4021.2  406.96
    4126  404.87  4335.4  407.73  4440.1  406.22  4793.4  401.58  4916.1  402.06
  4991.7  399.23  5014.8   401.5  5077.7  403.48  5088.9  401.57  5107.8  402.91
  5128.7  402.13  5196.9  398.18  5237.6  398.11  5238.1  397.61  5253.4  398.11
  5275.6  400.44  5726.6   404.6  5758.4  404.28  6329.9  412.61    6859  425.94
#Mann= 14 ,-1 , 0
  2505.1     .07       0  2675.7     .12       0  3422.2     .07       0
  4021.2    .035       0    4126     .07       0  4335.4    .035       0
  4440.1     .05       0  4793.4     .07       0  5014.8    .035       0
  5128.7     .07       0  5237.6     .05       0  5253.4     .07       0
  5726.6     .05       0  5758.4     .07       0
Bank Sta=5237.6,5253.4
XS Rating Curve= 0 ,0
Exp/Cntr=0.3,0.1