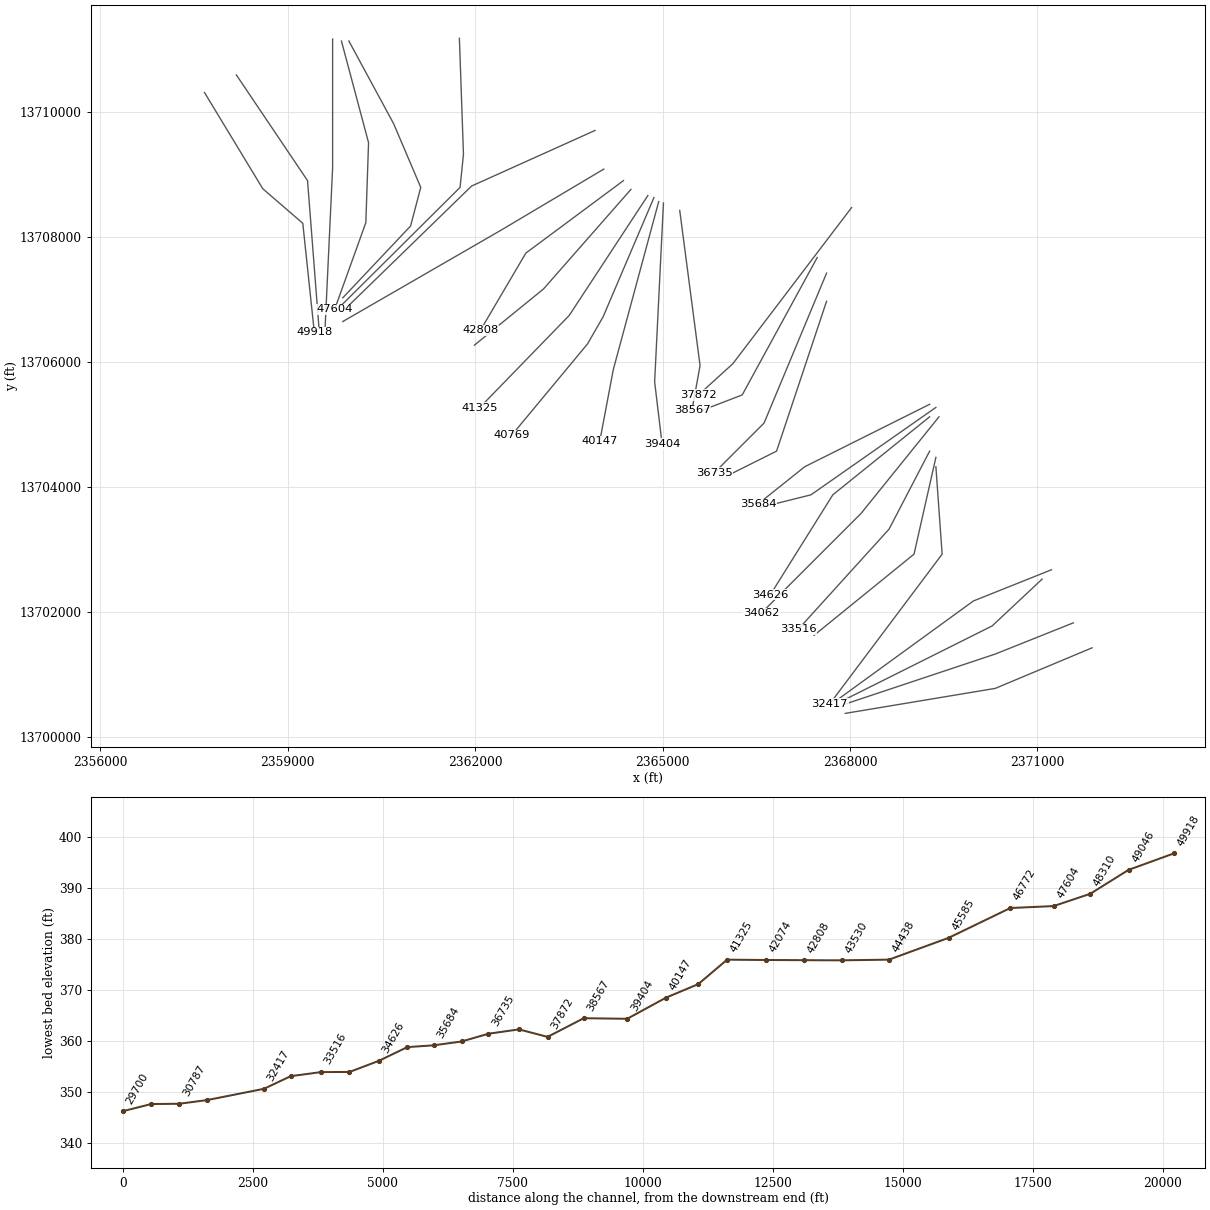
HEC-RAS study ONEIL CREEK.prj: ONEIL CREEK Base Level Engineering

--- ONEIL CREEK.g01 (geometry) --- (continued)

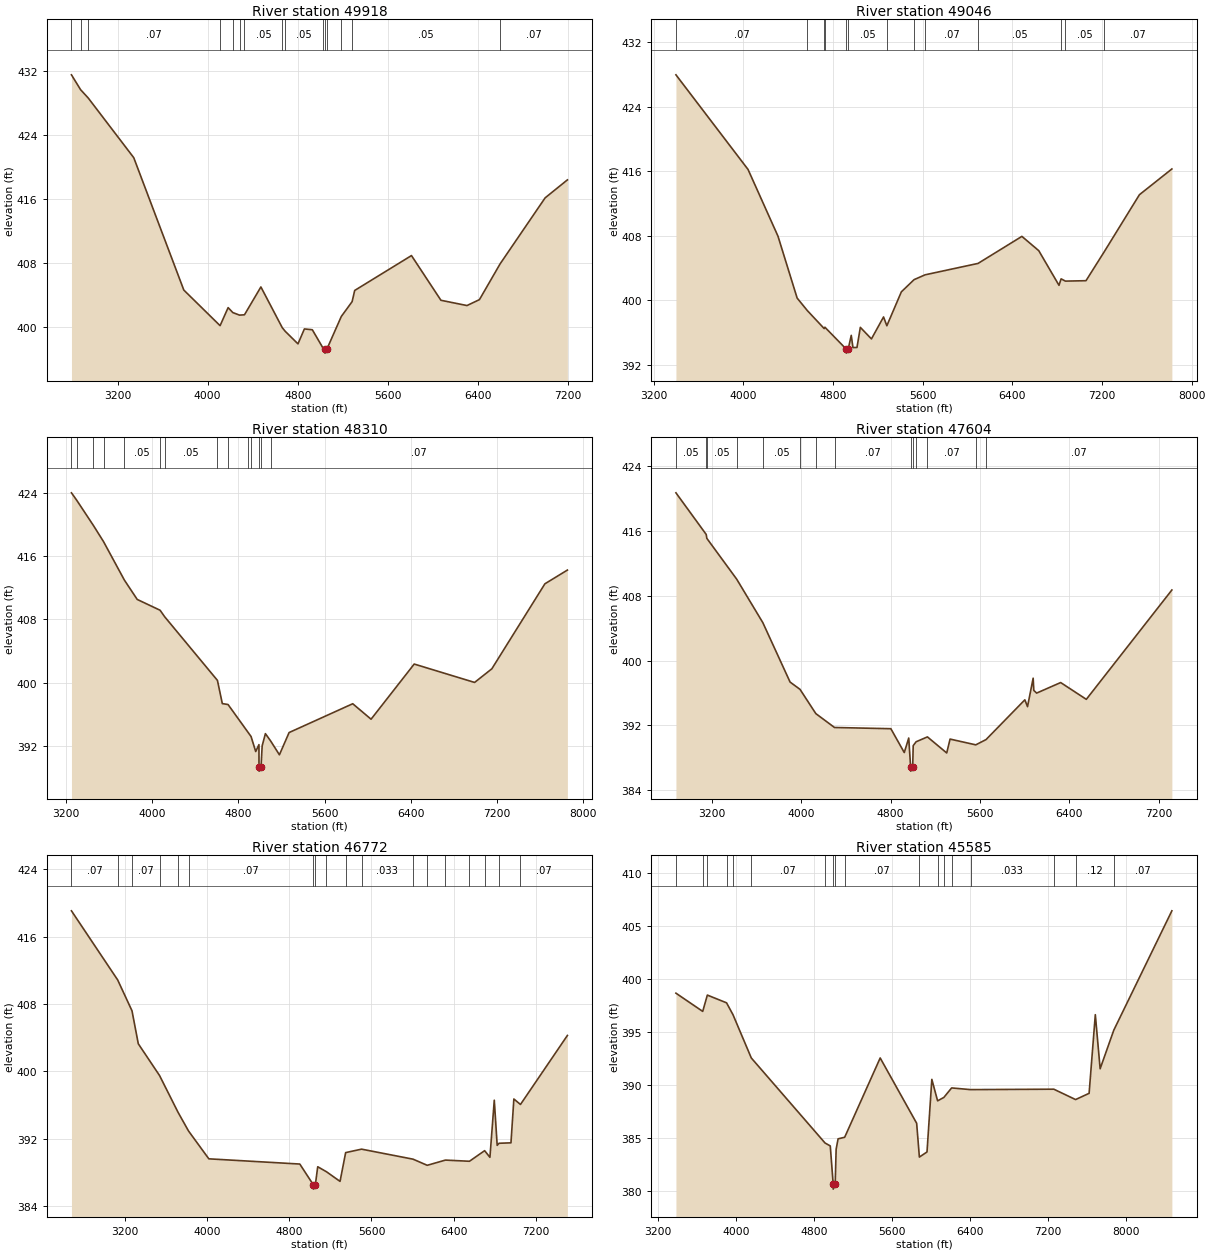
Type RM Length L Ch R = 1 ,49918   ,872,872,872
BEGIN DESCRIPTION:
B19898
END DESCRIPTION:
XS GIS Cut Line= 4
       2357668.6     13710318.11      2358601.78     13708777.28
      2359241.97     13708223.89      2359426.27      13706478.5
#Sta/Elev= 30
    2791  431.56    2872   429.7  2939.7  428.66  3344.1  421.18  3788.4   404.6
  4110.4  400.14  4181.8   402.4  4223.5  401.78  4283.1  401.46  4326.9   401.5
  4472.7  404.99  4662.3  399.89  4688.9  399.43  4801.9  397.86  4858.9  399.73
  4929.2  399.63  5027.3  397.26  5041.1   397.2  5041.6   396.7  5058.6   397.2
  5186.5  401.29  5282.6  403.15  5305.4  404.55  5809.5  408.92    6071  403.32
  6302.3  402.66  6412.9   403.4  6596.3  407.88  6996.1  416.15  7193.7   418.4
#Mann= 15 ,-1 , 0
    2791     .07       0    2872     .12       0  2939.7     .07       0
  4110.4    .035       0  4223.5     .05       0  4283.1    .035       0
  4326.9     .05       0  4662.3     .07       0  4688.9     .05       0
  5027.3     .12       0  5041.1     .05       0  5058.6     .12       0
  5186.5    .035       0  5282.6     .05       0  6596.3     .07       0
Bank Sta=5041.1,5058.6
XS Rating Curve= 0 ,0
Exp/Cntr=0.3,0.1

Type RM Length L Ch R = 1 ,49046   ,736,736,736
BEGIN DESCRIPTION:
B19897
END DESCRIPTION:
XS GIS Cut Line= 3
       2358178.6      13710600.2      2359317.93     13708907.49
      2359502.39     13706531.16
#Sta/Elev= 30
  3399.7  427.94  4042.9  416.22  4309.8  407.96  4480.8  400.29  4571.1  398.75
  4722.1  396.51  4728.3  396.68  4918.8  393.97  4919.3  393.47  4936.4  393.97
  4963.6  395.67  4978.6  394.16  5014.6  394.17  5044.6  396.66  5143.6  395.23
  5251.6  397.95  5281.1  396.86  5410.5  401.06  5523.8  402.57  5622.3  403.17
  6094.5  404.58  6485.7  407.93  6636.2  406.16  6816.7  401.87  6835.6  402.67
  6873.9  402.39  7057.5  402.44  7219.1     406  7534.1  413.09  7823.6  416.28
#Mann= 13 ,-1 , 0
  3399.7     .07       0  4571.1     .05       0  4722.1     .07       0
  4728.3     .05       0  4918.8     .05       0  4936.4     .05       0
  5281.1    .035       0  5523.8     .05       0  5622.3     .07       0
  6094.5     .05       0  6835.6     .07       0  6873.9     .05       0
  7219.1     .07       0
Bank Sta=4918.8,4936.4
XS Rating Curve= 0 ,0
Exp/Cntr=0.3,0.1

Type RM Length L Ch R = 1 ,48310   ,706,706,706
BEGIN DESCRIPTION:
B19896
END DESCRIPTION:
XS GIS Cut Line= 3
       2359719.4     13711175.26       2359719.4     13709113.65
      2359600.05     13706574.57
#Sta/Elev= 30
  3249.9  424.05  3299.2   423.1  3453.7  419.91  3547.9  417.86  3740.8     413
  3860.2  410.54  4072.5  409.17  4115.4  408.34  4604.9  400.28  4650.2  397.34
  4703.4  397.22  4892.1  393.64  4917.3  393.16  4960.2  391.26  4990.2  392.14
  4990.9  389.28  4991.4  388.78  5009.4  389.28  5020.2  391.99  5050.2  393.53
    5099   392.6  5180.2  390.85  5270.2  393.67  5860.8  397.32    6031  395.36
  6431.4  402.35    6992  400.02  7152.2  401.75  7644.6  412.52  7853.4  414.26
#Mann= 14 ,-1 , 0
  3249.9     .05       0  3299.2     .07       0  3453.7     .05       0
  3547.9     .07       0  3740.8     .05       0  4072.5     .07       0
  4115.4     .05       0  4604.9    .035       0  4703.4     .05       0
  4892.1     .07       0  4917.3     .12       0  4990.9     .05       0
  5009.4     .12       0    5099     .07       0
Bank Sta=4990.9,5009.4
XS Rating Curve= 0 ,0
Exp/Cntr=0.3,0.1

Type RM Length L Ch R = 1 ,47604   ,832,832,832
BEGIN DESCRIPTION:
B19895
END DESCRIPTION:
XS GIS Cut Line= 4
      2359860.47     13711142.72      2360294.49     13709515.13
      2360251.09     13708234.74      2359751.97     13706845.89
#Sta/Elev= 30
  2878.1  420.68  3149.1  415.55  3154.7  415.07    3423  410.02  3656.8  404.66
  3900.3  397.35  3989.4  396.45  4130.9  393.46  4298.2  391.75  4802.8   391.6
  4922.9  388.66  4962.9  390.45  4979.9  386.87  4980.4  386.37  4998.4  386.87
  5002.9  389.51  5029.1  389.99  5130.2  390.59  5303.1  388.61  5333.1  390.32
  5563.4  389.61  5655.3  390.26  6002.8  395.16  6026.8  394.32  6077.2  397.83
    6083  396.32  6108.4  395.99  6323.5  397.29  6553.3  395.22  7319.5   408.7
#Mann= 14 ,-1 , 0
  2878.1     .05       0  3149.1     .07       0  3154.7     .05       0
    3423     .07       0  3656.8     .05       0  3989.4    .035       0
  4130.9     .05       0  4298.2     .07       0  4979.9     .05       0
  4998.4     .07       0  5029.1     .12       0  5130.2     .07       0
  5563.4      .1       0  5655.3     .07       0
Bank Sta=4979.9,4998.4
XS Rating Curve= 0 ,0
Exp/Cntr=0.3,0.1

Type RM Length L Ch R = 1 ,46772   ,1187,1187,1187
BEGIN DESCRIPTION:
B19894
END DESCRIPTION:
XS GIS Cut Line= 5
       2359979.8     13711142.76      2360695.97     13709818.94
      2361129.99     13708798.98      2360967.23     13708180.49
      2359882.14     13707030.29
#Sta/Elev= 30
  2675.7  419.06  3126.6  410.84  3265.8  407.18  3327.3  403.26  3534.4  399.49
  3714.7  395.12  3816.8   392.9  4014.8  389.59  4901.6  388.97  5034.4  386.49
  5034.9  385.99    5053  386.49  5076.3  388.65  5160.8  388.06  5293.9  386.91
  5348.5  390.33  5503.6  390.74  6005.4  389.55  6143.7  388.82  6321.4  389.44
  6555.4   389.3  6703.3  390.56  6754.9  389.77  6797.4  396.56  6825.7  391.19
    6844  391.44    6960  391.49  6988.3   396.7  7052.7  396.05  7510.1  404.25
#Mann= 18 ,-1 , 0
  2675.7     .07       0  3126.6     .05       0  3265.8     .07       0
  3534.4     .05       0  3714.7    .035       0  3816.8     .07       0
  5034.4     .05       0    5053     .07       0  5160.8      .1       0
  5348.5     .12       0  5503.6    .033       0  6005.4     .12       0
  6143.7    .033       0  6321.4     .07       0  6555.4     .12       0
  6703.3     .07       0    6844     .12       0  7052.7     .07       0
Bank Sta=5034.4,5053
XS Rating Curve= 0 ,0
Exp/Cntr=0.3,0.1

Type RM Length L Ch R = 1 ,45585   ,1147,1147,1147
BEGIN DESCRIPTION:
B19893
END DESCRIPTION:
XS GIS Cut Line= 4
      2361748.48     13711186.16      2361813.59     13709330.66
      2361759.33     13708798.98      2359849.81      13706900.3
#Sta/Elev= 30
  3387.3  398.65  3661.7  396.93  3709.3  398.47  3906.1  397.74  3972.5  396.61
  4159.8  392.53  4915.5   384.5  4969.4  384.22  4999.1  380.64  4999.6  380.14
  5019.8  380.64  5029.5  383.91  5049.5  384.89  5117.1  385.04  5481.1  392.53
    5855  386.36  5882.8  383.17    5961  383.65  6010.5  390.51  6069.6  388.48
  6133.4   388.8  6213.5   389.7    6407  389.54    7261  389.58  7484.1   388.6
  7622.7  389.19  7686.4  396.62  7735.9  391.51  7875.5  395.15  8471.2  406.43
#Mann= 18 ,-1 , 0
  3387.3     .05       0  3661.7    .035       0  3709.3     .05       0
  3906.1     .07       0  3972.5     .05       0  4159.8     .07       0
  4915.5      .1       0  4999.1     .05       0  5019.8      .1       0
  5117.1     .07       0  5882.8      .1       0  6069.6     .12       0
  6133.4      .1       0  6213.5     .12       0    6407    .033       0
    7261     .07       0  7484.1     .12       0  7875.5     .07       0
Bank Sta=4999.1,5019.8
XS Rating Curve= 0 ,0
Exp/Cntr=0.3,0.1

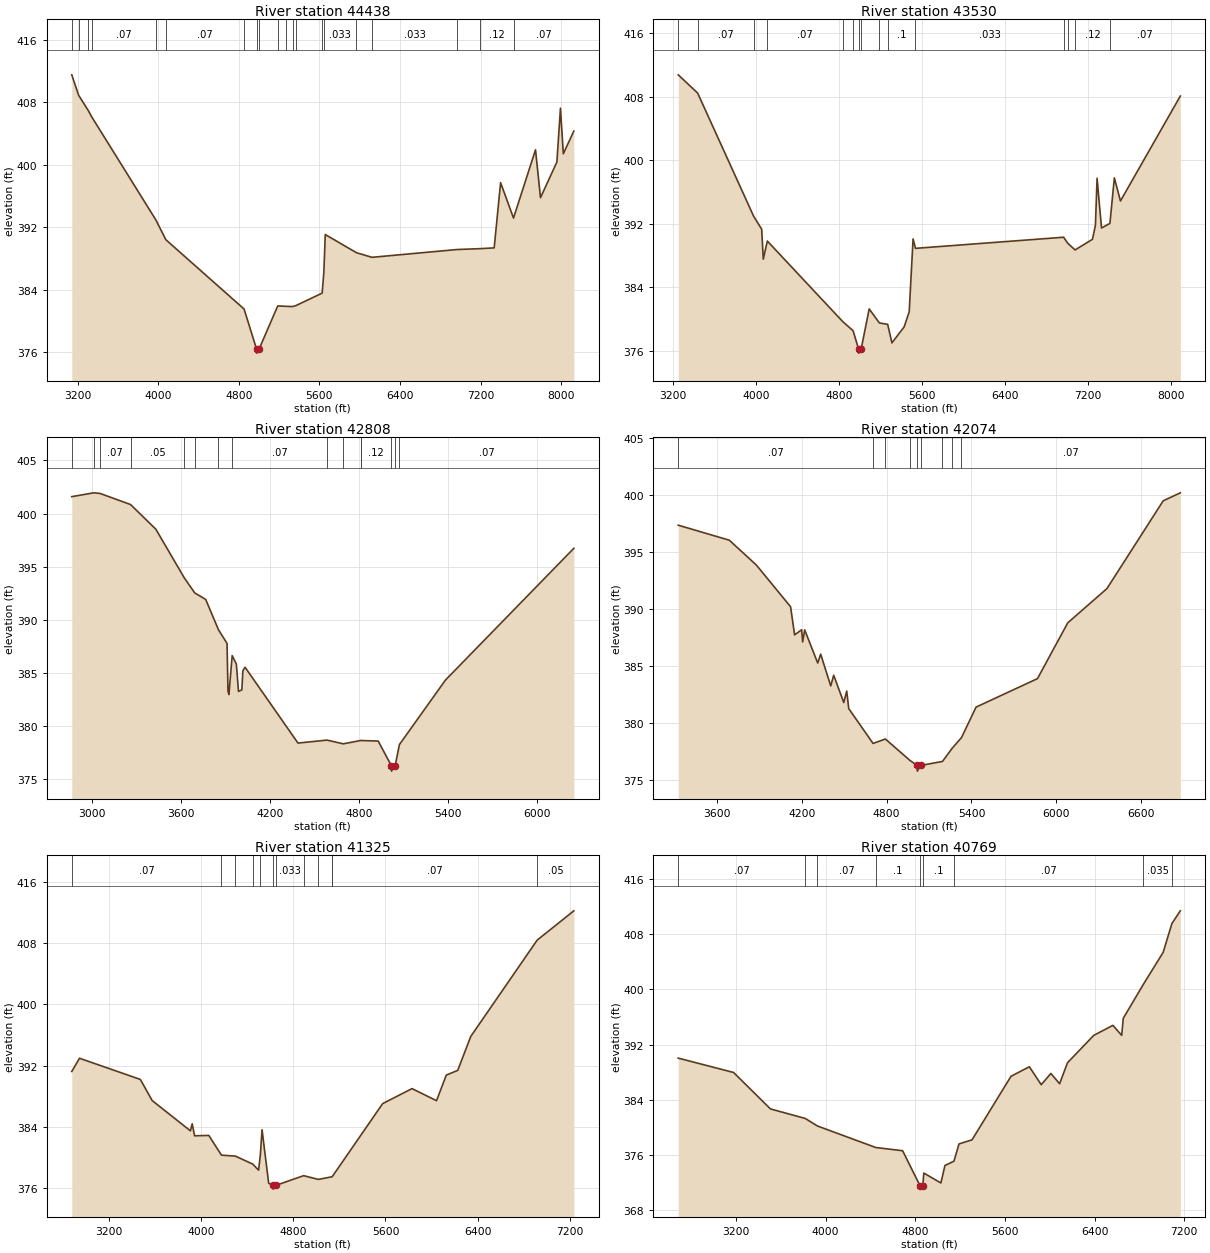
Type RM Length L Ch R = 1 ,44438   ,908,908,908
BEGIN DESCRIPTION:
B19892
END DESCRIPTION:
XS GIS Cut Line= 3
      2363918.66     13709710.46       2361943.8     13708820.68
      2359925.54     13706856.68
#Sta/Elev= 30
  3142.6  411.54  3210.7  408.92  3307.1  406.95  3338.4   406.2  3977.8  392.93
    4076  390.41  4852.6  381.52  4976.8  376.37  4977.3  375.87  5000.8  376.37
  5186.4  381.92  5270.7  381.87  5336.3  381.84  5366.3  381.96  5627.4  383.56
  5644.2   386.3  5658.3  391.07    5968  388.74  6121.4  388.15  6966.6  389.15
  7195.4  389.26  7334.3  389.36    7398  397.72  7526.1  393.18  7744.5  401.93
  7793.9  395.79  7956.7  400.37    7992  407.27  8020.3  401.42  8124.8  404.33
#Mann= 20 ,-1 , 0
  3142.6    .035       0  3210.7     .07       0  3307.1    .035       0
  3338.4     .07       0  3977.8    .035       0    4076     .07       0
  4852.6      .1       0  4976.8     .05       0  5000.8      .1       0
  5186.4     .07       0  5270.7      .1       0  5336.3     .07       0
  5366.3      .1       0  5627.4     .12       0  5644.2    .033       0
    5968     .12       0  6121.4    .033       0  6966.6     .12       0
  7195.4     .12       0  7526.1     .07       0
Bank Sta=4976.8,5000.8
XS Rating Curve= 0 ,0
Exp/Cntr=0.3,0.1

Type RM Length L Ch R = 1 ,43530   ,722,722,722
BEGIN DESCRIPTION:
B19891
END DESCRIPTION:
XS GIS Cut Line= 3
       2364059.7     13709091.96      2362399.53     13708104.54
      2359882.19     13706650.55
#Sta/Elev= 30
    3248  410.74  3434.9  408.45  3974.8  392.95  4052.2  391.32  4067.8  387.55
  4106.7  389.83  4833.9  379.69    4933  378.55  4986.7  376.23  4987.2  375.73
  5010.8  376.23  5088.3  381.29  5186.5  379.53  5266.6  379.35  5307.4  377.02
  5425.1  379.03    5474  380.93  5511.3   390.1  5534.5  388.91  6962.4  390.31
  7000.5  389.57  7072.3  388.71  7240.4  390.05  7268.7  391.83  7284.5  397.73
  7327.5  391.47  7408.3  392.05    7451  397.78  7509.9  394.87  8086.7  408.07
#Mann= 15 ,-1 , 0
    3248    .035       0  3434.9     .07       0  3974.8    .035       0
  4106.7     .07       0  4833.9     .12       0    4933      .1       0
  4986.7     .05       0  5010.8      .1       0  5186.5    .035       0
  5266.6      .1       0  5534.5    .033       0  6962.4     .12       0
  7000.5     .07       0  7072.3     .12       0  7408.3     .07       0
Bank Sta=4986.7,5010.8
XS Rating Curve= 0 ,0
Exp/Cntr=0.3,0.1

Type RM Length L Ch R = 1 ,42808   ,734,734,734
BEGIN DESCRIPTION:
B19890
END DESCRIPTION:
XS GIS Cut Line= 3
      2364374.38      13708907.5      2362811.85     13707746.46
      2362084.99     13706509.71
#Sta/Elev= 30
  2865.7  401.59  3013.2  401.95  3056.5  401.89  3261.3  400.85  3431.7  398.53
    3623  393.96  3693.9  392.53  3767.5  391.92  3853.5  389.07  3911.4  387.78
  3917.7   383.3    3924  382.97    3946  386.63    3974  385.84  3988.6  383.26
  4011.1  383.41  4017.9   385.2  4032.5  385.54  4389.2   378.4  4584.7  378.68
  4693.8  378.33  4814.6  378.65  4815.1  378.64  4929.3  378.59  5018.5  376.26
    5019  375.76  5043.3  376.26  5072.3  378.26  5382.4  384.33  6246.9  396.73
#Mann= 15 ,-1 , 0
  2865.7     .07       0  3013.2    .035       0  3056.5     .07       0
  3261.3     .05       0    3623     .07       0  3693.9     .05       0
  3853.5    .035       0    3946     .07       0  4584.7     .12       0
  4693.8      .1       0  4814.6     .07       0  4815.1     .12       0
  5018.5     .05       0  5043.3     .12       0  5072.3     .07       0
Bank Sta=5018.5,5043.3
XS Rating Curve= 0 ,0
Exp/Cntr=0.3,0.1

Type RM Length L Ch R = 1 ,42074   ,749,749,749
BEGIN DESCRIPTION:
B19889
END DESCRIPTION:
XS GIS Cut Line= 3
      2364493.71     13708766.43      2363093.97     13707171.38
      2361988.62     13706271.93
#Sta/Elev= 30
  3328.2  397.39  3689.3  396.07  3880.9  393.88    4122  390.23  4150.4  387.76
  4199.8  388.21  4207.4  387.14  4221.5   388.2  4313.6  385.29  4334.5  386.07
  4405.7  383.28  4426.6  384.22  4497.7  381.82  4518.6  382.83  4532.8  381.29
  4704.7  378.23  4791.6  378.62  4965.4  376.74  5016.7   376.3  5017.2   375.8
  5041.6   376.3  5194.9  376.65  5263.7  377.81  5329.3  378.74  5432.4  381.42
  5866.2  383.92  6080.3  388.82  6356.8  391.82  6754.6  399.53  6875.4  400.23
#Mann= 9 ,-1 , 0
  3328.2     .07       0  4704.7     .12       0  4791.6      .1       0
  4965.4    .033       0  5016.7    .033       0  5041.6    .033       0
  5194.9     .07       0  5263.7     .12       0  5329.3     .07       0
Bank Sta=5016.7,5041.6
XS Rating Curve= 0 ,0
Exp/Cntr=0.3,0.1

Type RM Length L Ch R = 1 ,41325   ,556,556,556
BEGIN DESCRIPTION:
B19888
END DESCRIPTION:
XS GIS Cut Line= 3
      2364764.95     13708668.73       2363506.3      13706748.2
      2362074.02     13705272.52
#Sta/Elev= 30
  2880.3  391.24  2947.3  392.97  3474.9   390.2  3577.4  387.44    3909  383.48
  3924.1   384.4  3945.2  382.83  4068.4  382.88    4178   380.3    4298  380.18
  4449.5  379.13  4499.8  378.34  4515.2  380.33    4530  383.62  4587.3  376.63
    4626  376.36  4626.5  375.86    4651  376.36  4890.6  377.62  5018.1  377.13
  5137.2  377.48  5137.9  377.48  5575.7  387.04  5830.3     389  6042.5  387.42
  6127.4  390.77  6226.2  391.38  6339.4  395.82  6915.1  408.41    7233  412.24
#Mann= 12 ,-1 , 0
  2880.3     .07       0    4178    .035       0    4298     .07       0
  4449.5      .1       0  4515.2    .033       0    4626     .05       0
    4651    .033       0  4890.6     .12       0  5018.1     .07       0
  5137.2     .12       0  5137.9     .07       0  6915.1     .05       0
Bank Sta=4626,4651
XS Rating Curve= 0 ,0
Exp/Cntr=0.3,0.1

Type RM Length L Ch R = 1 ,40769   ,622,622,622
BEGIN DESCRIPTION:
B19887
END DESCRIPTION:
XS GIS Cut Line= 4
      2364862.64     13708636.23      2364048.83      13706726.5
      2363799.27     13706292.47      2362584.94     13704828.78
#Sta/Elev= 30
  2685.9  390.04  3179.6  387.96  3508.4  382.68  3818.8   381.3  3927.2  380.21
  4447.8  377.09  4687.5  376.62  4842.4  371.56  4842.9  371.06  4867.5  371.56
  4876.5  373.39  5028.8  371.95  5064.8  374.48  5145.2  375.11  5190.3  377.61
  5306.5   378.2  5654.2  387.41  5817.9  388.79  5923.7  386.19  6009.7  387.82
  6087.8  386.33  6158.1  389.37  6392.5  393.34  6563.1  394.79  6641.3  393.34
  6655.6  395.81  6833.3  400.69  7011.1  405.36  7089.6  409.55  7164.3  411.38
#Mann= 9 ,-1 , 0
  2685.9     .07       0  3818.8    .035       0  3927.2     .07       0
  4447.8      .1       0  4842.4     .05       0  4867.5      .1       0
  5145.2     .07       0  6833.3    .035       0  7089.6     .07       0
Bank Sta=4842.4,4867.5
XS Rating Curve= 0 ,0
Exp/Cntr=0.3,0.1

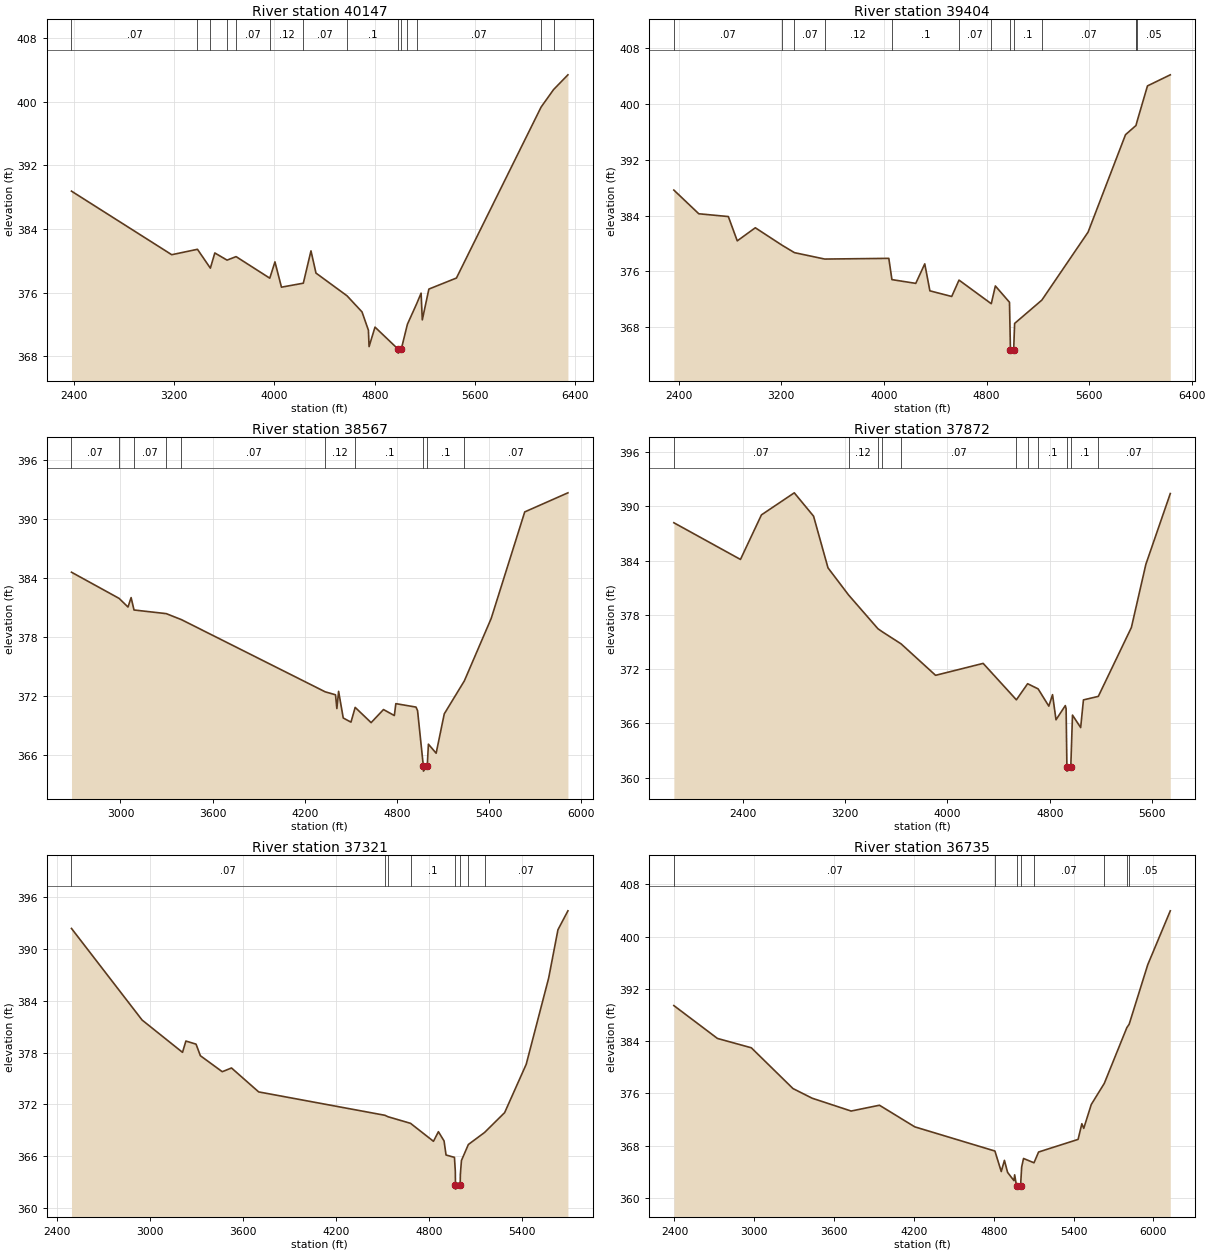
Type RM Length L Ch R = 1 ,40147   ,743,743,743
BEGIN DESCRIPTION:
B19886
END DESCRIPTION:
XS GIS Cut Line= 3
      2364938.58     13708571.09      2364211.59     13705880.14
      2363994.58     13704729.96
#Sta/Elev= 30
  2381.9  388.76  3181.1  380.77  3386.2  381.45  3489.1  379.08  3524.6  380.99
  3622.2  380.09  3694.2  380.53  3962.8  377.82  4004.1  379.87  4055.9  376.69
  4230.2  377.19  4291.3  381.25  4331.2  378.46  4578.3  375.61  4698.2  373.58
  4749.2  371.28  4754.4  369.22  4801.7  371.67    4986   368.9  4986.5   368.4
  5011.2   368.9  5060.1  372.03    5134  374.61  5169.3  375.94  5178.8  372.58
  5231.2  376.45    5451  377.84  6126.1  399.33  6225.6  401.53  6339.8  403.38
#Mann= 14 ,-1 , 0
  2381.9     .07       0  3386.2    .035       0  3489.1     .07       0
  3622.2     .12       0  3694.2     .07       0  3962.8     .12       0
  4230.2     .07       0  4578.3      .1       0    4986     .05       0
  5011.2      .1       0  5060.1     .12       0    5134     .07       0
  6126.1     .05       0  6225.6     .07       0
Bank Sta=4986,5011.2
XS Rating Curve= 0 ,0
Exp/Cntr=0.3,0.1

Type RM Length L Ch R = 1 ,39404   ,837,837,837
BEGIN DESCRIPTION:
B19885
END DESCRIPTION:
XS GIS Cut Line= 3
      2365014.54     13708549.41      2364873.48     13705684.83
      2364992.64     13704688.28
#Sta/Elev= 30
  2361.7  387.67  2556.3  384.27  2786.6  383.87  2856.2  380.38  2996.9  382.26
  3203.5  379.78  3302.2  378.69  3538.1  377.77  4038.1  377.87  4062.4  374.82
  4248.4  374.28  4318.5  377.08  4358.5  373.21  4528.7   372.4  4585.7  374.75
  4837.3  371.36  4869.1  373.91  4979.3  371.57  4986.7  364.77  4987.2  364.27
    5012  364.77  5019.3  368.53  5231.7  371.88  5592.1  381.63  5884.2  395.62
  5965.9  396.94    5969  397.16  5974.5  397.54  6055.4  402.62  6233.4  404.21
#Mann= 13 ,-1 , 0
  2361.7     .07       0  3203.5    .035       0  3302.2     .07       0
  3538.1     .12       0  4062.4      .1       0  4585.7     .07       0
  4837.3      .1       0  4986.7     .05       0    5012      .1       0
  5231.7     .07       0  5965.9     .05       0    5969     .07       0
  5974.5     .05       0
Bank Sta=4986.7,5012
XS Rating Curve= 0 ,0
Exp/Cntr=0.3,0.1

Type RM Length L Ch R = 1 ,38567   ,695,695,695
BEGIN DESCRIPTION:
B19884
END DESCRIPTION:
XS GIS Cut Line= 3
      2365274.96     13708430.02      2365600.48     13705945.25
      2365470.36     13705229.58
#Sta/Elev= 30
    2681   384.6  2991.1  381.94  3049.1  381.06  3069.3  382.02  3088.3  380.76
    3298  380.39    3397  379.78  4333.6  372.44  4400.6  372.14  4409.5  370.74
  4420.8  372.49    4451  369.78  4501.4  369.36  4528.7  370.86  4632.6  369.31
  4713.2  370.64  4783.8  370.03  4793.6  371.24    4925  370.89  4935.1  370.53
  4972.8  364.88  4973.3  364.38  4998.2  364.88  5005.7  367.12  5056.1   366.2
    5109   370.2    5240  373.56  5414.6   379.9  5633.1  390.73  5914.4  392.67
#Mann= 10 ,-1 , 0
    2681     .07       0  2991.1    .035       0  3088.3     .07       0
    3298    .035       0    3397     .07       0  4333.6     .12       0
  4528.7      .1       0  4972.8     .05       0  4998.2      .1       0
    5240     .07       0
Bank Sta=4972.8,4998.2
XS Rating Curve= 0 ,0
Exp/Cntr=0.3,0.1

Type RM Length L Ch R = 1 ,37872   ,551,551,551
BEGIN DESCRIPTION:
ONEIL CREEK 7466
END DESCRIPTION:
XS GIS Cut Line= 3
      2368025.03     13708475.04        2366125.       13705975.
      2365575.01     13705475.01
#Sta/Elev= 30
    1860   388.2    2381  384.14  2545.2  389.07  2802.1  391.51  2952.8  388.93
  3065.8  383.21  3226.7  380.21    3456  376.48  3489.1  376.15  3637.6   374.8
  3907.4  371.32  4279.5  372.64  4539.5  368.61  4627.4  370.39  4709.5  369.82
  4793.2  367.91  4822.3  369.18  4849.4   366.4  4922.1  367.97  4928.4  367.63
  4934.6  361.22  4935.1  360.72  4965.1  361.22  4978.3  366.92  5042.3  365.54
    5064   368.6  5180.4  368.99    5439  376.61  5552.5  383.61  5743.4  391.43
#Mann= 11 ,-1 , 0
    1860     .07       0  3226.7     .12       0    3456    .035       0
  3489.1     .12       0  3637.6     .07       0  4539.5     .12       0
  4627.4     .07       0  4709.5      .1       0  4934.6     .05       0
  4965.1      .1       0  5180.4     .07       0
Bank Sta=4934.6,4965.1
XS Rating Curve= 0 ,0
Exp/Cntr=0.3,0.1

Type RM Length L Ch R = 1 ,37321   ,586,586,586
BEGIN DESCRIPTION:
ONEIL CREEK 7465
END DESCRIPTION:
XS GIS Cut Line= 3
      2367474.98     13707674.96        2366275.       13705475.
      2365624.97     13705224.99
#Sta/Elev= 30
  2493.8  392.38  2949.4  381.77    3210  378.03  3231.8  379.34  3297.3  378.98
  3325.3  377.64  3466.3  375.79  3526.1  376.22  3701.2  373.45    4516  370.74
    4536  370.57  4680.9  369.81  4828.9  367.73  4860.7  368.84  4897.2  367.77
    4910  366.14  4964.2  365.87  4969.8  364.25  4970.7  362.69  4971.2  362.19
  5001.2  362.69  5002.4  363.91  5009.4  365.51  5054.1  367.36  5158.4  368.75
    5288  371.05  5427.2  376.65  5571.9  386.63  5631.9  392.23  5696.2  394.42
#Mann= 8 ,-1 , 0
  2493.8     .07       0    4516     .12       0    4536     .07       0
  4680.9      .1       0  4970.7     .05       0  5001.2      .1       0
  5054.1     .12       0  5158.4     .07       0
Bank Sta=4970.7,5001.2
XS Rating Curve= 0 ,0
Exp/Cntr=0.3,0.1

Type RM Length L Ch R = 1 ,36735   ,516,516,516
BEGIN DESCRIPTION:
ONEIL CREEK 7464
END DESCRIPTION:
XS GIS Cut Line= 3
      2367625.02     13707425.04        2366625.       13705025.
      2365825.01     13704225.01
#Sta/Elev= 30
  2395.6  389.43  2723.3   384.4  2977.9  382.97    3291  376.73  3435.6  375.25
  3728.1  373.29    3941  374.18  4206.4  370.87  4808.8  367.17  4856.4  364.03
  4880.3  365.74  4904.1   363.9  4951.8  362.64  4957.2  363.53  4971.1  361.84
  4971.6  361.34  5001.7  361.84  5009.8  364.72  5023.9  366.03  5102.5  365.37
  5137.1  367.02    5434  368.95  5462.3  371.35  5476.5  370.64    5533  374.29
  5630.9  377.52  5800.5  386.06  5817.7  386.57  5957.3  395.67    6127  403.93
#Mann= 8 ,-1 , 0
  2395.6     .07       0  4808.8      .1       0  4971.1     .05       0
  5001.7      .1       0  5102.5     .07       0  5630.9     .05       0
  5800.5     .07       0  5817.7     .05       0
Bank Sta=4971.1,5001.7
XS Rating Curve= 0 ,0
Exp/Cntr=0.3,0.1

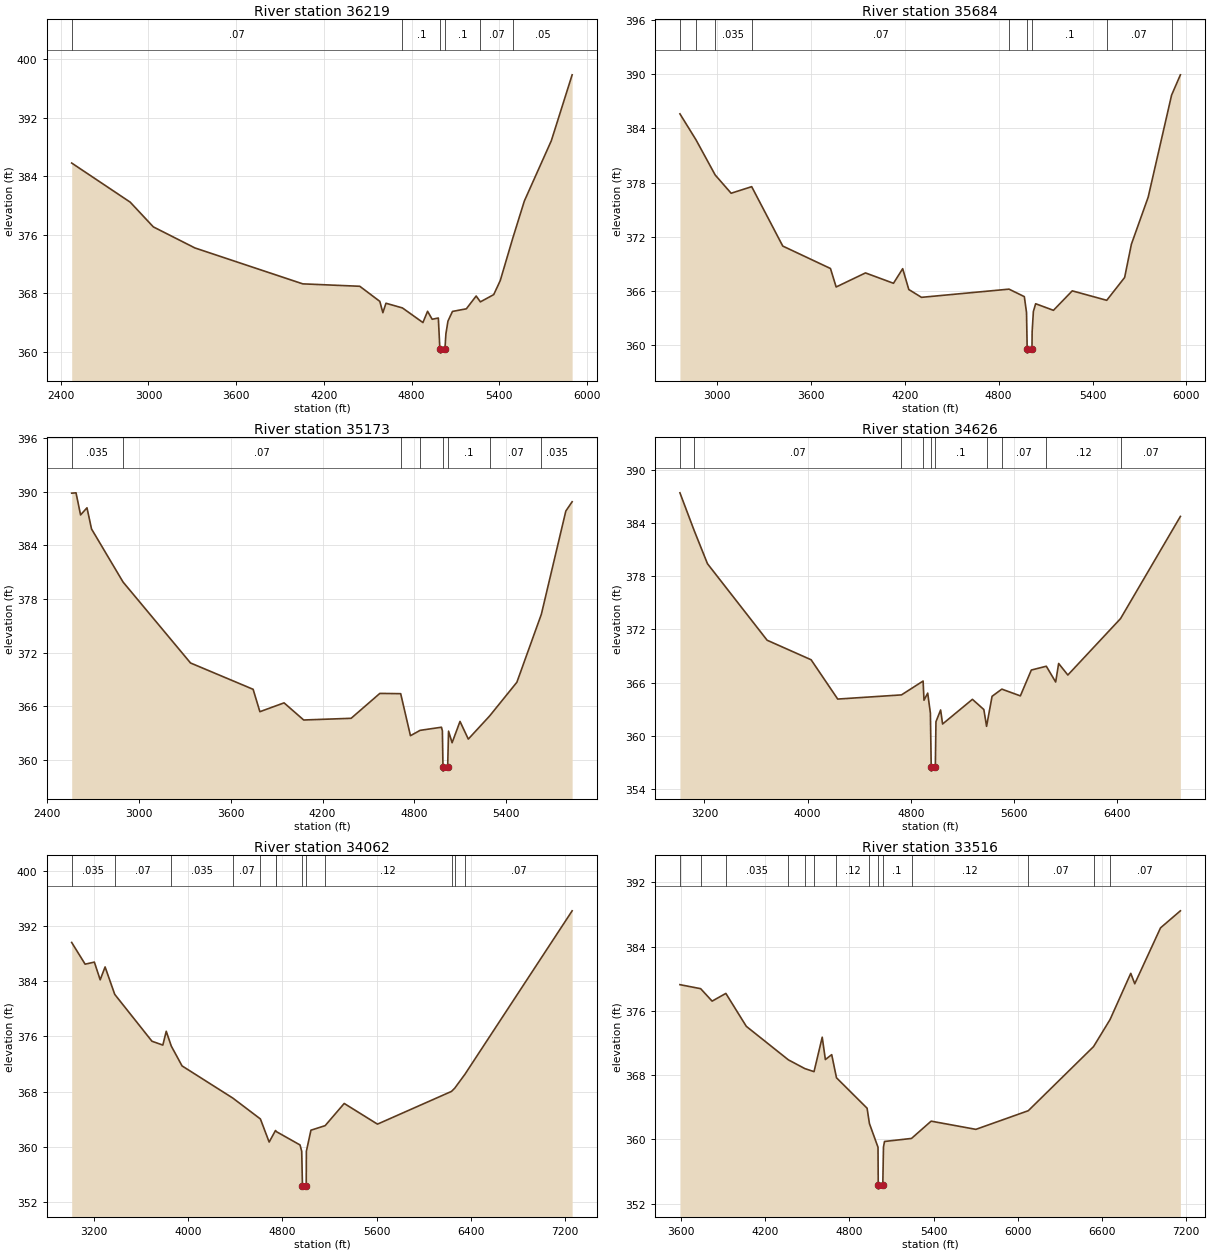
Type RM Length L Ch R = 1 ,36219   ,535,535,535
BEGIN DESCRIPTION:
ONEIL CREEK 7463
END DESCRIPTION:
XS GIS Cut Line= 3
      2367624.99     13706974.97        2366825.       13704575.
      2366025.02     13704175.01
#Sta/Elev= 30
  2474.5  385.81    2875  380.46  3033.1  377.08  3317.7   374.2  4055.6  369.29
  4445.6  368.96  4582.7   366.9  4603.7  365.35  4624.8  366.64  4737.5     366
  4877.8     364  4909.4  365.54    4941  364.45  4983.2  364.62  4993.7  360.38
  4997.4  360.32  4997.9  359.82    5028  360.32    5035  362.46    5049   364.2
  5079.8  365.52  5174.8  365.88  5241.9  367.63  5270.8  366.83  5362.1  367.82
  5406.8  369.74  5491.9   375.5  5571.7  380.62  5756.2  388.86  5898.7  397.87
#Mann= 6 ,-1 , 0
  2474.5     .07       0  4737.5      .1       0  4997.4     .05       0
    5028      .1       0  5270.8     .07       0  5491.9     .05       0
Bank Sta=4997.4,5028
XS Rating Curve= 0 ,0
Exp/Cntr=0.3,0.1

Type RM Length L Ch R = 1 ,35684   ,511,511,511
BEGIN DESCRIPTION:
ONEIL CREEK 7462
END DESCRIPTION:
XS GIS Cut Line= 3
      2369274.96     13705324.98        2367275.       13704325.
        2366525.       13703725.
#Sta/Elev= 30
  2764.5  385.62  2867.8  382.72  2989.6  378.84  3091.5  376.81  3222.8  377.54
  3421.3  370.95    3726  368.46  3762.3  366.41  3949.6  367.97  4128.5  366.82
  4187.2  368.44  4226.3  366.13  4307.3  365.26  4866.3  366.17  4964.2  365.34
  4978.2  363.58  4982.4  359.57  4982.9  359.07  5013.1  359.57  5014.1  361.44
  5022.1   363.7  5036.5  364.55  5150.2  363.82  5270.3  365.98  5490.5  364.93
  5604.8  367.46    5648  371.15  5755.3  376.38  5904.8   387.7    5961  389.95
#Mann= 9 ,-1 , 0
  2764.5    .035       0  2867.8     .05       0  2989.6    .035       0
  3222.8     .07       0  4866.3      .1       0  4982.4     .05       0
  5013.1      .1       0  5490.5     .07       0  5904.8     .05       0
Bank Sta=4982.4,5013.1
XS Rating Curve= 0 ,0
Exp/Cntr=0.3,0.1

Type RM Length L Ch R = 1 ,35173   ,547,547,547
BEGIN DESCRIPTION:
ONEIL CREEK 7461
END DESCRIPTION:
XS GIS Cut Line= 3
        2369375.       13705275.        2367375.       13703875.
      2366575.03     13703675.01
#Sta/Elev= 30
  2563.2  389.86  2591.5   389.9  2621.2  387.42    2663  388.22  2692.7  385.85
  2898.5   379.9  3338.8  370.83  3747.2  367.88  3791.3  365.37  3949.1  366.36
  4077.2  364.44  4386.8  364.63  4574.2  367.42  4710.2  367.39  4773.9  362.68
  4836.8  363.28  4976.2  363.63  4982.3  363.23  4986.1  359.21  4986.6  358.71
  5016.8  359.21  5022.5  363.19  5045.7  361.89  5097.3  364.28  5151.4   362.3
  5290.5  364.89  5468.4  368.67  5628.3   376.3  5787.9  387.86  5829.1   388.9
#Mann= 8 ,-1 , 0
  2563.2    .035       0  2898.5     .07       0  4710.2    .035       0
  4836.8      .1       0  4986.1     .05       0  5016.8      .1       0
  5290.5     .07       0  5628.3    .035       0
Bank Sta=4986.1,5016.8
XS Rating Curve= 0 ,0
Exp/Cntr=0.3,0.1

Type RM Length L Ch R = 1 ,34626   ,564,564,564
BEGIN DESCRIPTION:
ONEIL CREEK 7460
END DESCRIPTION:
XS GIS Cut Line= 3
      2369274.97     13705124.98        2367725.       13703875.
        2366725.     13702274.99
#Sta/Elev= 30
  3010.2  387.38  3120.6  383.13  3223.7  379.39  3685.9  370.77  4026.6  368.57
  4232.9  364.14  4726.9  364.61  4894.5  366.17  4901.4  364.01  4930.2  364.81
    4951  362.56  4957.4  356.52  4957.9  356.02  4989.3  356.52  4994.2  361.59
  5030.3  362.91  5045.6  361.33  5276.7  364.11  5365.2  362.96  5386.3  361.07
  5428.9  364.45  5504.5  365.26  5648.2   364.5  5733.1  367.41  5849.3  367.84
  5921.8  366.06  5944.8  368.15  6016.1  366.85  6424.6  373.21  6888.2  384.72
#Mann= 10 ,-1 , 0
  3010.2    .035       0  3120.6     .07       0  4726.9    .035       0
  4894.5      .1       0  4957.4     .05       0  4989.3      .1       0
  5386.3     .12       0  5504.5     .07       0  5849.3     .12       0
  6424.6     .07       0
Bank Sta=4957.4,4989.3
XS Rating Curve= 0 ,0
Exp/Cntr=0.3,0.1

Type RM Length L Ch R = 1 ,34062   ,546,546,546
BEGIN DESCRIPTION:
ONEIL CREEK 7459
END DESCRIPTION:
XS GIS Cut Line= 3
        2369425.       13705125.        2368175.       13703575.
      2366574.98     13701974.98
#Sta/Elev= 30
  3008.2  389.63  3122.5  386.48  3200.9  386.78  3250.5  384.21  3292.1  386.08
  3374.1   382.1  3690.4   375.3  3783.1  374.74  3811.9  376.74    3855  374.59
  3946.3  371.72  4377.9  367.05  4612.3  364.02  4686.7  360.67  4740.8  362.35
  4748.2  362.18  4949.1  360.25  4963.5  359.32  4969.8  354.34  4970.3  353.84
  5001.8  354.34    5003  359.33  5041.9  362.39  5162.7  363.05  5324.7  366.27
  5607.5  363.27  6236.8  368.02  6264.3  368.49  6351.1  370.51  7262.2  394.22
#Mann= 13 ,-1 , 0
  3008.2    .035       0  3374.1     .07       0    3855    .035       0
  4377.9     .07       0  4612.3      .1       0  4740.8    .035       0
  4748.2      .1       0  4969.8     .05       0  5001.8      .1       0
  5162.7     .12       0  6236.8     .07       0  6264.3     .12       0
  6351.1     .07       0
Bank Sta=4969.8,5001.8
XS Rating Curve= 0 ,0
Exp/Cntr=0.3,0.1

Type RM Length L Ch R = 1 ,33516   ,586,586,586
BEGIN DESCRIPTION:
ONEIL CREEK 7458
END DESCRIPTION:
XS GIS Cut Line= 3
      2369275.02     13704575.04        2368625.       13703325.
      2367175.02     13701725.02
#Sta/Elev= 30
  3591.3  379.27  3739.1  378.77  3820.7  377.22  3918.7  378.18  4064.7  374.08
  4364.6  369.91  4482.1  368.82  4547.4  368.44  4605.8  372.73  4628.3  369.95
  4673.4  370.56  4707.5  367.68  4925.7  363.89  4942.4  361.98  5003.6  359.03
  5005.3  354.32  5005.9  353.82  5037.7  354.32  5042.5  359.05  5049.9  359.75
  5242.4  360.13  5382.4  362.28  5701.4  361.26    6075  363.58  6540.4  371.56
  6658.1  374.93  6805.7  380.68  6834.1  379.38  7017.9  386.34  7159.5  388.46
#Mann= 14 ,-1 , 0
  3591.3    .035       0  3739.1     .07       0  3918.7    .035       0
  4364.6     .07       0  4482.1    .035       0  4547.4     .07       0
  4707.5     .12       0  4942.4      .1       0  5005.3     .05       0
  5037.7      .1       0  5242.4     .12       0    6075     .07       0
  6540.4    .035       0  6658.1     .07       0
Bank Sta=5005.3,5037.7
XS Rating Curve= 0 ,0
Exp/Cntr=0.3,0.1

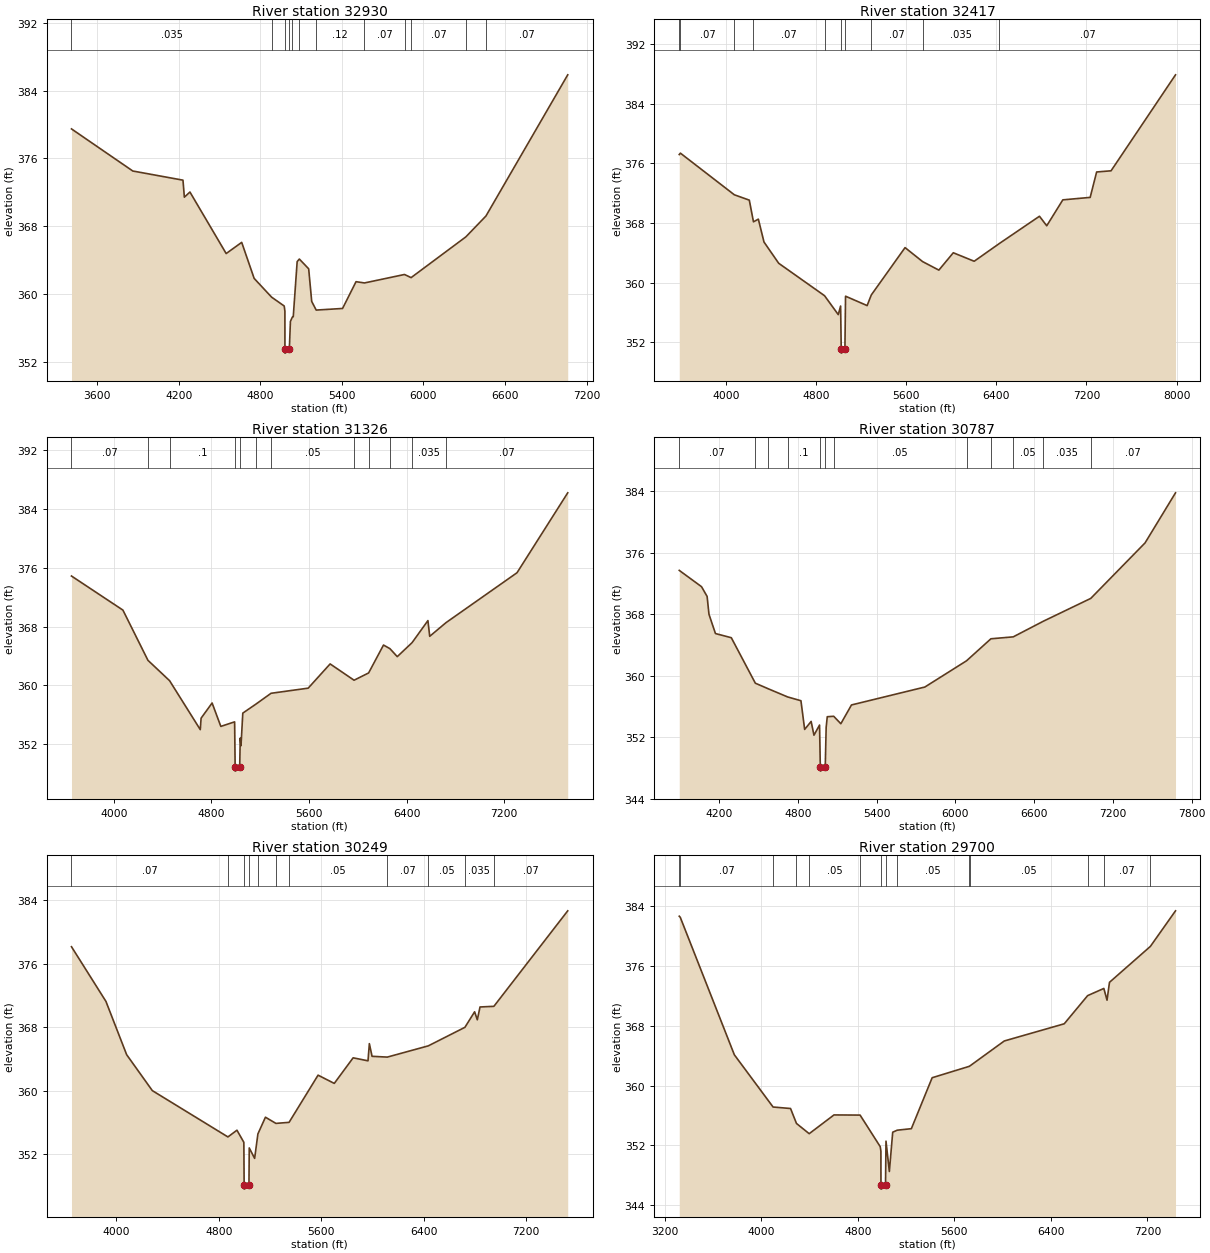
Type RM Length L Ch R = 1 ,32930   ,513,513,513
BEGIN DESCRIPTION:
ONEIL CREEK 7457
END DESCRIPTION:
XS GIS Cut Line= 3
      2369375.01     13704475.03        2369025.       13702925.
      2367425.01     13701625.01
#Sta/Elev= 30
  3410.9  379.47    3862   374.5  4231.1  373.42  4241.3  371.41  4282.3  372.02
  4548.9  364.76  4663.1  366.08  4754.6  361.83  4882.8  359.62  4975.8  358.57
  4980.9  357.96  4981.1  353.51  4981.6  353.01  5013.7  353.51  5021.5  356.75
  5035.9  357.27  5042.3   357.3  5071.1  363.81  5087.2  364.11  5155.8  362.96
  5178.1  359.11  5211.1  358.09  5405.1  358.28  5504.2  361.44  5566.1  361.29
  5860.7  362.29  5909.3  361.92  6312.2  366.73  6459.9  369.19  7061.5  385.85
#Mann= 12 ,-1 , 0
  3410.9    .035       0  4882.8    .063       0  4981.1    .063       0
  5013.7    .063       0  5035.9    .035       0  5087.2    .063       0
  5211.1     .12       0  5566.1     .07       0  5860.7     .12       0
  5909.3     .07       0  6312.2    .035       0  6459.9     .07       0
Bank Sta=4981.1,5013.7
XS Rating Curve= 0 ,0
Exp/Cntr=0.3,0.1

Type RM Length L Ch R = 1 ,32417   ,1091,1091,1091
BEGIN DESCRIPTION:
ONEIL CREEK 7456
END DESCRIPTION:
XS GIS Cut Line= 3
        2369375.     13704325.01        2369475.       13702925.
      2367674.99     13700524.98
#Sta/Elev= 30
  3586.4  377.19  3596.5  377.38  4075.1  371.79    4208  371.07  4244.9  368.16
  4288.2  368.52  4338.3  365.45  4468.7   362.6  4875.4  358.25  4997.3  355.71
  5018.1  356.86  5023.7  351.04  5024.2  350.54  5056.3  351.04  5061.9  358.18
  5253.5  356.92  5290.2  358.34    5590   364.7  5746.1  362.82    5890  361.68
  6018.1  364.01  6203.5  362.87  6426.7  365.25  6782.7  368.91  6847.3  367.63
    6990  371.11  7232.7  371.44    7290  374.85  7418.1  375.01    7990  387.89
#Mann= 10 ,-1 , 0
  3586.4    .035       0  3596.5     .07       0  4075.1    .035       0
  4244.9     .07       0  4875.4      .1       0  5023.7     .05       0
  5056.3      .1       0  5290.2     .07       0  5746.1    .035       0
  6426.7     .07       0
Bank Sta=5023.7,5056.3
XS Rating Curve= 0 ,0
Exp/Cntr=0.3,0.1

Type RM Length L Ch R = 1 ,31326   ,539,539,539
BEGIN DESCRIPTION:
ONEIL CREEK 7455
END DESCRIPTION:
XS GIS Cut Line= 3
      2371224.99       13702675.        2369975.       13702175.
      2367774.98     13700574.99
#Sta/Elev= 30
  3653.6   374.9    4075  370.26  4280.3  363.42  4457.4  360.65  4709.1  353.98
  4715.8  355.54    4806  357.61  4877.4  354.42  4990.5  355.04  4994.8  348.83
  4995.8  348.33    5032  348.83  5036.6  352.83  5042.8  351.79  5057.5  356.23
  5163.7  357.44    5289  358.93  5593.4  359.63  5773.1  362.93  5969.3  360.71
  6088.5   361.7  6210.5   365.5  6263.1  365.01  6323.3  363.92  6444.9  365.83
  6574.5  368.83  6589.2  366.69  6723.5  368.56  7304.8  375.35  7720.2  386.23
#Mann= 12 ,-1 , 0
  3653.6     .07       0  4280.3     .12       0  4457.4      .1       0
  4994.8     .05       0    5032      .1       0  5163.7     .07       0
    5289     .05       0  5969.3    .035       0  6088.5     .07       0
  6263.1     .05       0  6444.9    .035       0  6723.5     .07       0
Bank Sta=4994.8,5032
XS Rating Curve= 0 ,0
Exp/Cntr=0.3,0.1

Type RM Length L Ch R = 1 ,30787   ,538,538,538
BEGIN DESCRIPTION:
ONEIL CREEK 7454
END DESCRIPTION:
XS GIS Cut Line= 3
      2371074.99     13702524.99        2370275.       13701775.
      2367874.96     13700574.98
#Sta/Elev= 30
  3897.3   373.7    4067  371.58  4109.5  370.31  4123.7  367.99    4173  365.49
  4293.7  364.95  4476.7  359.04    4574  358.32    4723  357.25  4824.1  356.76
  4852.5  353.03  4901.8  354.07  4923.3  352.28  4965.8   353.6  4971.7  348.11
  4972.6  347.61  5009.2  348.11  5016.2  353.29  5024.6  354.68  5073.5  354.74
    5128  353.77  5209.1  356.21  5768.1  358.54  6085.5  361.95  6271.1  364.81
  6441.2  365.06  6670.3  367.09  7031.8  370.06  7445.2  377.27  7677.2  383.78
#Mann= 12 ,-1 , 0
  3897.3     .07       0  4476.7     .12       0    4574     .07       0
    4723      .1       0  4971.7     .05       0  5009.2      .1       0
  5073.5     .05       0  6085.5    .035       0  6271.1     .07       0
  6441.2     .05       0  6670.3    .035       0  7031.8     .07       0
Bank Sta=4971.7,5009.2
XS Rating Curve= 0 ,0
Exp/Cntr=0.3,0.1

Type RM Length L Ch R = 1 ,30249   ,549,549,549
BEGIN DESCRIPTION:
ONEIL CREEK 7453
END DESCRIPTION:
XS GIS Cut Line= 3
      2371575.02     13701825.01        2370325.       13701325.
      2367925.03     13700525.01
#Sta/Elev= 30
  3649.4  378.16  3918.7  371.25  4080.2  364.53  4280.8  359.99  4871.3  354.14
  4941.9  354.99  4995.7  353.46    4998  348.05    4999  347.55  5035.6  348.05
  5037.9  352.75    5080  351.43  5105.5  354.52  5164.4  356.63  5246.2  355.85
    5349  355.98  5575.5  361.94    5702   360.9  5849.5  364.13  5965.5  363.75
    5976  365.92  5997.1  364.32  6116.2  364.22  6436.5  365.64  6722.4  367.98
  6798.2  369.94  6819.3  368.93  6840.4  370.55  6948.6  370.63  7525.5  382.69
#Mann= 11 ,-1 , 0
  3649.4     .07       0  4871.3      .1       0    4998     .05       0
  5035.6      .1       0  5105.5     .05       0  5246.2     .12       0
    5349     .05       0  6116.2     .07       0  6436.5     .05       0
  6722.4    .035       0  6948.6     .07       0
Bank Sta=4998,5035.6
XS Rating Curve= 0 ,0
Exp/Cntr=0.3,0.1

Type RM Length L Ch R = 1 ,29700   ,566,566,566
BEGIN DESCRIPTION:
ONEIL CREEK 7452
END DESCRIPTION:
XS GIS Cut Line= 3
      2371875.03     13701425.01        2370325.       13700775.
      2367925.02       13700375.
#Sta/Elev= 30
  3319.2  382.67  3327.7  382.52  3775.9  364.12  4096.9  357.13  4241.8  356.93
  4290.9  354.93  4396.3  353.56  4601.7  356.07  4818.2  356.05  4985.4  351.82
  4990.8  351.21  4991.2  346.64  4992.2  346.14    5029  346.64    5033  352.56
  5060.8   348.5  5088.7  353.76  5126.7  354.03  5243.3  354.23  5415.7  361.05
  5722.5  362.57  5728.7  362.63  6013.8  365.97  6510.6  368.27  6704.6  372.04
  6838.9     373  6865.4  371.43  6885.7  373.82  7224.8  378.63  7433.1  383.39
#Mann= 14 ,-1 , 0
  3319.2     .05       0  3327.7     .07       0  4096.9     .05       0
  4290.9     .07       0  4396.3     .05       0  4818.2      .1       0
  4991.2     .05       0    5029      .1       0  5126.7     .05       0
  5722.5    .035       0  5728.7     .05       0  6704.6    .035       0
  6838.9     .07       0  7224.8    .035       0
Bank Sta=4991.2,5029
XS Rating Curve= 0 ,0
Exp/Cntr=0.3,0.1