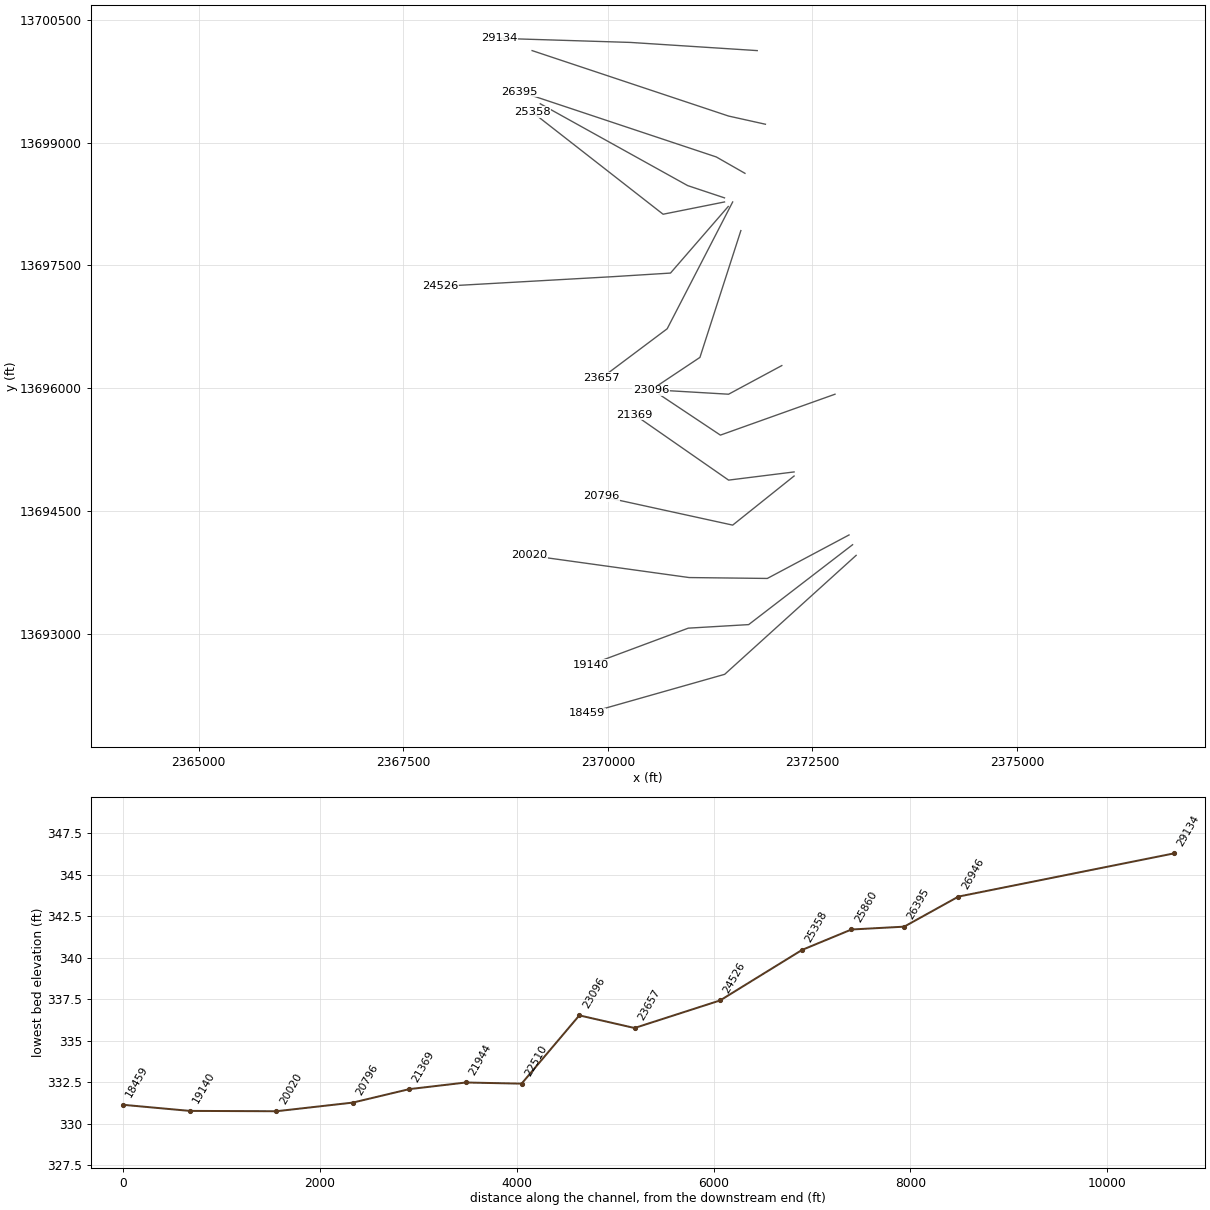
HEC-RAS study ONEIL CREEK.prj: ONEIL CREEK Base Level Engineering

--- ONEIL CREEK.g01 (geometry) --- (continued)

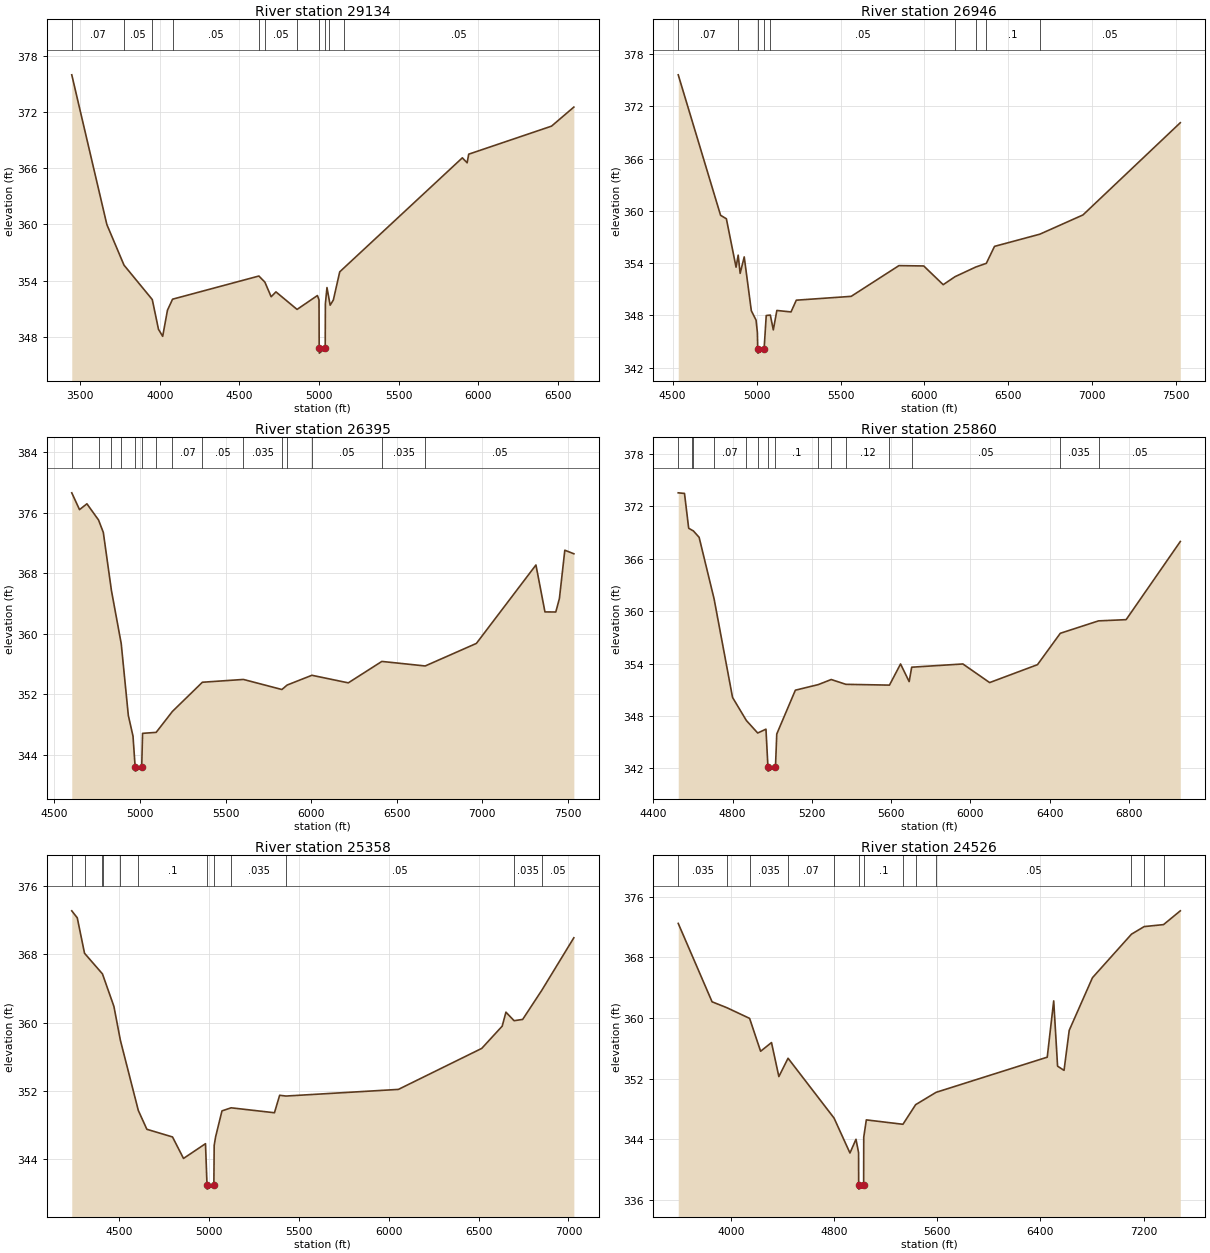
Type RM Length L Ch R = 1 ,29134   ,2188,2188,2188
BEGIN DESCRIPTION:
ONEIL CREEK 7451
END DESCRIPTION:
XS GIS Cut Line= 3
      2371824.95       13700125.        2370275.       13700225.
      2368674.96       13700275.
#Sta/Elev= 30
  3446.8  375.94  3667.2  359.98    3775  355.65  3952.6  351.98  3991.6  348.81
  4017.9  348.06    4048  350.85    4080  352.02  4622.3  354.49  4659.8  353.84
  4699.4  352.28  4729.4   352.8  4862.1  350.93    4990  352.41    5000  351.95
  5001.1  346.77  5002.1  346.27  5038.9  346.77    5040  351.53    5050  353.26
  5059.6  352.36    5070  351.38    5090  351.93    5130  354.93  5158.2  355.38
  5900.4  367.09  5930.4  366.56  5940.4  367.48  6460.7  370.47  6600.8   372.5
#Mann= 11 ,-1 , 0
  3446.8     .07       0    3775     .05       0  3952.6     .12       0
    4080     .05       0  4622.3     .12       0  4659.8     .05       0
  4862.1      .1       0  5001.1     .05       0  5038.9      .1       0
  5059.6    .035       0  5158.2     .05       0
Bank Sta=5001.1,5038.9
XS Rating Curve= 0 ,0
Exp/Cntr=0.3,0.1

Type RM Length L Ch R = 1 ,26946   ,551,551,551
BEGIN DESCRIPTION:
ONEIL CREEK 7450
END DESCRIPTION:
XS GIS Cut Line= 3
      2371924.99       13699225.        2371475.       13699325.
      2369074.99       13700125.
#Sta/Elev= 30
  4533.3  375.63  4785.5   359.5  4820.1   359.1  4877.7  353.54  4890.4  354.92
  4902.1  352.83  4926.4  354.72  4968.7  348.54  4996.9  347.46  5004.8  346.04
  5006.8  344.17  5007.8  343.67  5044.9  344.17  5057.5  347.99  5081.8  348.04
  5099.7  346.34  5120.8  348.57  5205.1   348.4  5236.7  349.75  5563.5  350.19
  5848.1  353.72  5995.7  353.68  6111.6  351.53  6182.3  352.45  6307.1  353.57
  6368.5  353.98  6417.3  355.93  6687.5  357.33  6944.3  359.54  7524.1  370.13
#Mann= 9 ,-1 , 0
  4533.3     .07       0  4890.4      .1       0  5006.8     .05       0
  5044.9      .1       0  5081.8     .05       0  6182.3    .035       0
  6307.1     .05       0  6368.5      .1       0  6687.5     .05       0
Bank Sta=5006.8,5044.9
XS Rating Curve= 0 ,0
Exp/Cntr=0.3,0.1

Type RM Length L Ch R = 1 ,26395   ,535,535,535
BEGIN DESCRIPTION:
ONEIL CREEK 7449
END DESCRIPTION:
XS GIS Cut Line= 3
      2371674.97     13698625.02        2371325.       13698825.
        2368925.       13699625.
#Sta/Elev= 30
  4601.5  378.62  4646.8   376.4    4690  377.17  4757.7  375.04  4785.7   373.4
  4833.4  365.69  4890.4   358.7  4931.9  349.22  4959.2  346.48  4971.9  342.36
  4972.9  341.86    5010  342.36  5015.1  346.85  5094.5  346.98  5189.2  349.74
  5364.5   353.6  5604.2  353.97  5828.9  352.64  5859.6  353.23  6004.3  354.52
  6216.8  353.52  6412.9  356.35  6666.1  355.75  6965.2  358.73    7313  369.09
  7365.7  362.89    7429  362.88  7450.1  364.66  7481.7  371.04  7534.4  370.57
#Mann= 15 ,-1 , 0
  4601.5    .035       0  4757.7     .07       0  4833.4     .12       0
  4890.4     .07       0  4971.9     .05       0    5010     .07       0
  5094.5     .05       0  5189.2     .07       0  5364.5     .05       0
  5604.2    .035       0  5828.9     .05       0  5859.6    .035       0
  6004.3     .05       0  6412.9    .035       0  6666.1     .05       0
Bank Sta=4971.9,5010
XS Rating Curve= 0 ,0
Exp/Cntr=0.3,0.1

Type RM Length L Ch R = 1 ,25860   ,502,502,502
BEGIN DESCRIPTION:
ONEIL CREEK 7448
END DESCRIPTION:
XS GIS Cut Line= 3
      2371424.99       13698325.        2370975.       13698475.
      2369174.96     13699475.02
#Sta/Elev= 30
  4525.4  373.53    4557  373.46  4578.1  369.48  4595.4  369.25  4601.5  369.18
  4630.8  368.44  4706.3   361.4  4799.5  350.12  4869.3  347.48  4926.4  346.05
  4968.1  346.49    4978  342.19    4979  341.69  5016.1  342.19  5022.6  345.94
  5116.4  350.95  5232.1  351.59  5297.4  352.17  5371.5  351.62  5591.3  351.53
  5647.2  353.95  5690.7  351.93  5703.4  353.58  5961.8  353.95  6096.8  351.82
  6338.2  353.87  6453.4  357.46  6646.1  358.88  6785.5  359.02  7058.9  367.96
#Mann= 15 ,-1 , 0
  4525.4     .05       0  4595.4    .035       0  4601.5     .05       0
  4706.3     .07       0  4869.3     .05       0  4926.4      .1       0
    4978     .05       0  5016.1      .1       0  5232.1     .12       0
  5297.4    .035       0  5371.5     .12       0  5591.3    .035       0
  5703.4     .05       0  6453.4    .035       0  6646.1     .05       0
Bank Sta=4978,5016.1
XS Rating Curve= 0 ,0
Exp/Cntr=0.3,0.1

Type RM Length L Ch R = 1 ,25358   ,832,832,832
BEGIN DESCRIPTION:
ONEIL CREEK 7447
END DESCRIPTION:
XS GIS Cut Line= 3
      2371425.01       13698275.        2370675.       13698125.
      2369074.96     13699375.03
#Sta/Elev= 30
  4234.5  373.11  4265.1  372.29  4305.6  368.13  4405.4  365.71  4405.7  365.69
  4469.1   361.9  4505.2  357.92    4605  349.69  4652.6  347.48  4795.4  346.58
  4856.6  344.06    4979  345.79  4987.5  340.96  4988.5  340.46  5025.6  340.96
  5027.4  345.59  5035.5  346.61  5070.8  349.64  5121.9     350  5362.9  349.42
  5391.9  351.47  5427.2  351.38    6053  352.16    6517  356.97  6630.9  359.58
  6651.7  361.22  6697.2  360.22  6744.9  360.37  6851.4  363.79  7029.8  369.95
#Mann= 12 ,-1 , 0
  4234.5     .05       0  4305.6    .035       0  4405.4     .05       0
  4405.7    .035       0  4505.2     .05       0    4605      .1       0
  4987.5     .05       0  5025.6      .1       0  5121.9    .035       0
  5427.2     .05       0  6697.2    .035       0  6851.4     .05       0
Bank Sta=4987.5,5025.6
XS Rating Curve= 0 ,0
Exp/Cntr=0.3,0.1

Type RM Length L Ch R = 1 ,24526   ,869,869,869
BEGIN DESCRIPTION:
B19883
END DESCRIPTION:
XS GIS Cut Line= 4
       2371470.7     13698219.55      2370765.41     13697405.75
      2370070.97     13697362.35      2367955.12     13697242.99
#Sta/Elev= 30
  3592.9   372.5  3855.2  362.15  3968.7  361.38  4146.2  359.96  4231.4  355.62
  4315.9  356.77  4372.9  352.28  4444.3   354.7  4800.8   346.8    4924  342.19
  4970.8     344  4990.8  342.25  4991.7  337.92  4992.7  337.42  5030.1  337.92
  5030.9  344.27  5050.9  346.56  5334.7  345.98  5433.2  348.57  5591.9   350.2
  6453.3  354.84  6503.4  362.27  6533.4  353.65  6583.5   353.1  6623.6  358.38
  6803.8  365.33  7106.4  371.08  7204.9  372.08  7354.7  372.34  7484.8  374.16
#Mann= 13 ,-1 , 0
  3592.9    .035       0  3968.7     .07       0  4146.2    .035       0
  4444.3     .07       0  4800.8      .1       0  4991.7     .05       0
  5030.1      .1       0  5334.7     .05       0  5433.2    .035       0
  5591.9     .05       0  7106.4    .035       0  7204.9     .05       0
  7354.7    .035       0
Bank Sta=4991.7,5030.1
XS Rating Curve= 0 ,0
Exp/Cntr=0.3,0.1

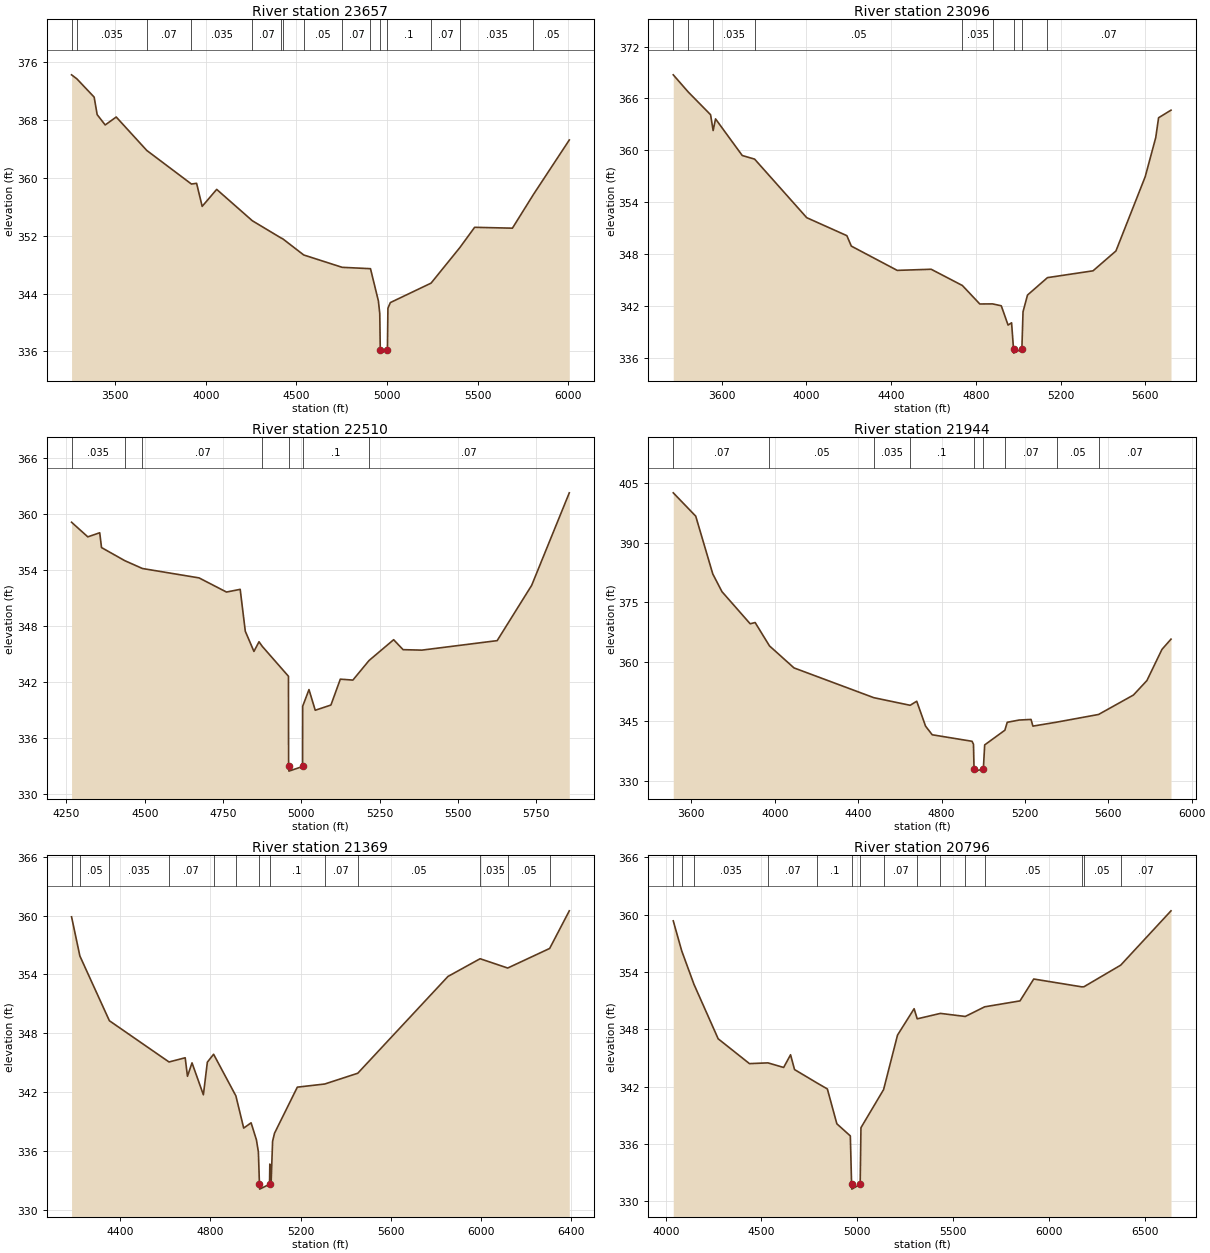
Type RM Length L Ch R = 1 ,23657   ,561,561,561
BEGIN DESCRIPTION:
ONEIL CREEK 7446
END DESCRIPTION:
XS GIS Cut Line= 3
        2371525.       13698275.        2370725.       13696725.
      2369924.98     13696124.99
#Sta/Elev= 30
  3260.3  374.29  3289.8  373.73    3385   371.2  3401.5  368.78  3445.8  367.35
  3506.6  368.45  3675.1  363.82  3921.2  359.17  3949.7  359.27  3980.5  356.08
  4060.5  358.43  4256.9  354.09  4414.8  351.71  4424.1   351.6  4540.3  349.35
  4752.3  347.64  4908.5  347.45    4952  342.99  4959.6  341.24  4962.4  336.26
  4963.4  335.76  5001.8  336.26  5004.6  341.98  5018.1  342.76  5242.4  345.45
  5401.4  350.38  5482.7  353.18    5691  353.06  5806.5  357.71  6004.6  365.27
#Mann= 15 ,-1 , 0
  3260.3     .05       0  3289.8    .035       0  3675.1     .07       0
  3921.2    .035       0  4256.9     .07       0  4414.8     .05       0
  4424.1     .07       0  4540.3     .05       0  4752.3     .07       0
  4908.5      .1       0  4962.4     .05       0  5001.8      .1       0
  5242.4     .07       0  5401.4    .035       0  5806.5     .05       0
Bank Sta=4962.4,5001.8
XS Rating Curve= 0 ,0
Exp/Cntr=0.3,0.1

Type RM Length L Ch R = 1 ,23096   ,586,586,586
BEGIN DESCRIPTION:
ONEIL CREEK 7445
END DESCRIPTION:
XS GIS Cut Line= 3
      2371624.99     13697924.97        2371125.       13696375.
      2370525.02     13695975.01
#Sta/Elev= 30
  3371.4  368.74  3442.2  366.75  3547.6  364.12  3559.7  362.29    3571  363.64
  3697.1   359.4  3755.5  358.98  4001.5   352.2  4190.9  350.12    4212  348.91
  4428.7   346.1  4588.9  346.23  4736.2  344.35  4818.5  342.21  4878.7  342.22
  4919.9     342  4951.9  339.77  4968.5  340.03  4977.6  337.02  4978.6  336.52
  5017.1  337.02  5022.6  341.31  5043.6  343.24  5137.8  345.26  5353.1  346.05
  5461.2  348.35  5599.4  356.95    5649  361.47  5662.5  363.77  5721.1  364.65
#Mann= 9 ,-1 , 0
  3371.4     .07       0  3442.2     .05       0  3559.7    .035       0
  3755.5     .05       0  4736.2    .035       0  4878.7      .1       0
  4977.6     .05       0  5017.1      .1       0  5137.8     .07       0
Bank Sta=4977.6,5017.1
XS Rating Curve= 0 ,0
Exp/Cntr=0.3,0.1

Type RM Length L Ch R = 1 ,22510   ,566,566,566
BEGIN DESCRIPTION:
ONEIL CREEK 7444
END DESCRIPTION:
XS GIS Cut Line= 3
      2372124.98     13696274.99        2371475.       13695925.
      2370624.99       13695975.
#Sta/Elev= 30
  4266.4  359.15  4318.3  357.58  4356.4  358.02  4362.1  356.43  4436.5  355.02
  4492.7  354.18  4673.6  353.17  4761.2  351.65    4805  351.94  4821.3  347.44
  4848.9  345.27  4865.1  346.31  4875.6  345.81  4959.2   342.6  4959.6  332.91
  4960.6  332.41  5004.3  332.91  5004.6  339.38  5024.7  341.17  5044.7  338.95
  5094.8  339.51  5124.8  342.29  5164.9  342.19  5216.4  344.29  5295.1  346.53
  5325.2  345.46  5385.3  345.41  5625.7  346.43  5735.9  352.37  5856.1  362.31
#Mann= 7 ,-1 , 0
  4266.4    .035       0  4436.5     .05       0  4492.7     .07       0
  4875.6      .1       0  4959.6     .05       0  5004.3      .1       0
  5216.4     .07       0
Bank Sta=4959.6,5004.3
XS Rating Curve= 0 ,0
Exp/Cntr=0.3,0.1

Type RM Length L Ch R = 1 ,21944   ,575,575,575
BEGIN DESCRIPTION:
ONEIL CREEK 7443
END DESCRIPTION:
XS GIS Cut Line= 3
      2372775.02     13695925.01        2371375.       13695425.
      2370625.02     13695924.99
#Sta/Elev= 30
  3512.9  402.53  3620.7  396.66  3702.5  382.12  3746.5  377.66  3881.9  369.57
  3905.8  369.88  3974.4  364.01  4092.2  358.46  4474.9  350.97  4649.3  349.05
    4681  350.07  4723.4   343.8  4755.3  341.63  4946.4  339.99  4953.3  339.24
  4955.9  332.98  4956.9  332.48  5000.6  332.98    5007  339.08  5103.9  342.78
  5115.2  344.77  5172.3  345.34  5229.4  345.49  5238.4  343.81  5352.7  344.81
  5553.3  346.74  5720.6  351.63  5785.2  355.27  5857.4  363.11  5900.9   365.7
#Mann= 9 ,-1 , 0
  3512.9     .07       0  3974.4     .05       0  4474.9    .035       0
  4649.3      .1       0  4955.9     .05       0  5000.6      .1       0
  5103.9     .07       0  5352.7     .05       0  5553.3     .07       0
Bank Sta=4955.9,5000.6
XS Rating Curve= 0 ,0
Exp/Cntr=0.3,0.1

Type RM Length L Ch R = 1 ,21369   ,573,573,573
BEGIN DESCRIPTION:
ONEIL CREEK 7442
END DESCRIPTION:
XS GIS Cut Line= 3
      2372275.04       13694975.        2371475.       13694875.
      2370324.96     13695675.03
#Sta/Elev= 30
  4184.5  359.88  4221.4  355.88  4352.3  349.27  4616.7  345.06  4688.4  345.49
  4698.5   343.6  4718.7  344.97  4769.1  341.71  4786.7  345.04  4814.4  345.85
  4913.2   341.6  4947.9  338.31  4980.7  338.85  5004.3  337.11    5013  335.88
  5017.7  332.58  5018.7  332.08  5062.5  332.58  5063.7  334.64  5069.8  332.93
    5076  336.97  5084.6  337.79  5185.7  342.49  5307.1  342.81  5453.7  343.91
  5853.6  353.79  5996.2   355.6  6118.6  354.65  6304.6  356.65  6391.7  360.49
#Mann= 13 ,-1 , 0
  4184.5     .07       0  4221.4     .05       0  4352.3    .035       0
  4616.7     .07       0  4814.4    .035       0  4913.2      .1       0
  5017.7     .05       0  5062.5      .1       0  5307.1     .07       0
  5453.7     .05       0  5996.2    .035       0  6118.6     .05       0
  6304.6    .035       0
Bank Sta=5017.7,5062.5
XS Rating Curve= 0 ,0
Exp/Cntr=0.3,0.1

Type RM Length L Ch R = 1 ,20796   ,776,776,776
BEGIN DESCRIPTION:
ONEIL CREEK 7441
END DESCRIPTION:
XS GIS Cut Line= 3
      2372274.99       13694925.        2371525.       13694325.
        2369925.       13694675.
#Sta/Elev= 30
  4039.5  359.36  4083.6  356.22  4147.7  352.71    4274  347.01  4437.3  344.41
  4533.7  344.49  4615.8  344.01  4651.8  345.34  4672.6  343.79  4792.1  342.36
  4843.9  341.76  4893.5  338.11  4963.9  336.84  4970.4  331.77  4971.4  331.27
  5015.2  331.77  5019.3   337.7  5137.4  341.69  5210.2   347.4  5296.8  350.16
    5313   349.1  5434.1  349.67  5563.9  349.35  5665.3  350.36  5849.6  350.98
  5921.2  353.27  6171.9  352.45  6183.2  352.46  6375.1  354.72  6637.8  360.41
#Mann= 15 ,-1 , 0
  4039.5     .07       0  4083.6     .05       0  4147.7    .035       0
  4533.7     .07       0  4792.1      .1       0  4970.4     .05       0
  5015.2      .1       0  5137.4     .07       0    5313    .035       0
  5434.1     .07       0  5563.9    .035       0  5665.3     .05       0
  6171.9     .07       0  6183.2     .05       0  6375.1     .07       0
Bank Sta=4970.4,5015.2
XS Rating Curve= 0 ,0
Exp/Cntr=0.3,0.1

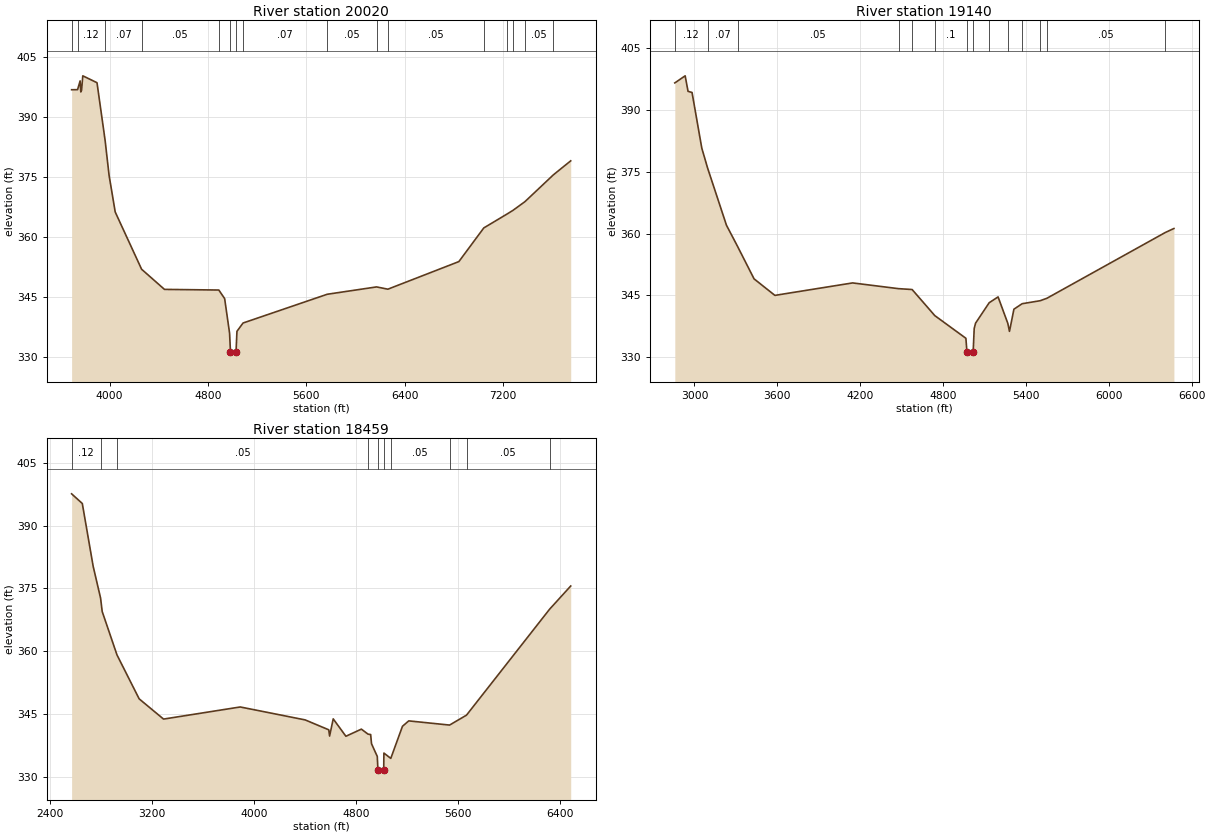
Type RM Length L Ch R = 1 ,20020   ,880,880,880
BEGIN DESCRIPTION:
B19882
END DESCRIPTION:
XS GIS Cut Line= 4
      2372946.39     13694204.79      2371948.14     13693673.11
      2370993.28     13693683.96      2369040.16     13693955.23
#Sta/Elev= 30
  3690.9  396.87  3739.4  396.89  3759.9  399.08  3765.5  396.32  3771.8  396.74
  3781.8  400.35  3897.3  398.63  3962.8   384.3  3995.8  375.39  4045.4  366.29
  4259.9  351.98  4445.8  346.94  4887.7  346.78  4935.1  344.63  4975.1     336
  4982.5  331.25  4983.5  330.75  5027.6  331.25  5035.1  336.45  5084.6  338.53
  5768.9  345.72  6170.5  347.56    6262  346.99  6839.3  353.89  7042.1  362.31
  7233.2  365.83    7280  366.72  7376.4  368.88  7608.2   375.6  7748.7  379.09
#Mann= 16 ,-1 , 0
  3690.9     .07       0  3739.4     .12       0  3962.8     .07       0
  4259.9     .05       0  4887.7     .12       0  4982.5     .05       0
  5027.6     .12       0  5084.6     .07       0  5768.9     .05       0
  6170.5     .07       0    6262     .05       0  7042.1     .07       0
  7233.2     .05       0    7280     .07       0  7376.4     .05       0
  7608.2     .07       0
Bank Sta=4982.5,5027.6
XS Rating Curve= 0 ,0
Exp/Cntr=0.3,0.1

Type RM Length L Ch R = 1 ,19140   ,681,681,681
BEGIN DESCRIPTION:
B19881
END DESCRIPTION:
XS GIS Cut Line= 4
      2372989.78     13694085.42      2371720.27     13693108.88
      2370982.42     13693065.47      2369789.38     13692620.79
#Sta/Elev= 30
  2857.5  396.51  2932.5  398.23  2953.3  394.47  2982.3  394.19  3052.9   380.7
  3095.5  375.82  3231.5  362.02    3313  356.81  3431.3  349.02  3582.2  345.01
  4144.9  348.03  4477.5  346.64  4575.9  346.43    4740  340.11  4965.3  334.61
  4972.8  331.27  4973.8  330.77  5017.9  331.27  5025.4  336.99  5035.4  338.28
    5134  343.23  5198.3  344.64  5268.6  338.25  5280.9  336.29  5312.9  341.66
  5372.5  342.99  5503.5  343.72  5552.4  344.32  6408.9  360.25  6471.5  361.22
#Mann= 14 ,-1 , 0
  2857.5     .12       0  3095.5     .07       0    3313     .05       0
  4477.5     .07       0  4575.9     .05       0    4740      .1       0
  4972.8     .05       0  5017.9      .1       0    5134      .1       0
  5268.6     .07       0  5372.5     .05       0  5503.5     .07       0
  5552.4     .05       0  6408.9     .07       0
Bank Sta=4972.8,5017.9
XS Rating Curve= 0 ,0
Exp/Cntr=0.3,0.1

Type RM Length L Ch R = 1 ,18459   ,957,957,957
BEGIN DESCRIPTION:
B19880
END DESCRIPTION:
XS GIS Cut Line= 3
      2373033.23     13693955.25       2371427.3     13692501.24
      2369745.42      13692023.8
#Sta/Elev= 30
  2571.4  397.56  2655.2  395.25  2740.4  380.26  2798.6  372.67  2811.3  369.46
  2927.3  359.11  3101.3  348.62  3292.5   343.8  3894.1  346.69  4403.6   343.6
  4588.2  341.24  4594.9  339.75  4623.3  343.85  4722.7   339.7  4844.1   341.4
  4896.7   340.2  4916.9  340.11  4923.7  337.91  4968.9  334.88    4974  331.64
    4975  331.14  5019.4  331.64  5020.8  335.69  5074.8  334.42  5166.4  342.08
  5215.7  343.37  5535.9  342.37  5668.7  344.74  6320.4  370.02  6486.1  375.56
#Mann= 10 ,-1 , 0
  2571.4     .12       0  2798.6     .07       0  2927.3     .05       0
  4896.7      .1       0    4974     .05       0  5019.4      .1       0
  5074.8     .05       0  5535.9    .035       0  5668.7     .05       0
  6320.4     .07       0
Bank Sta=4974,5019.4
XS Rating Curve= 0 ,0
Exp/Cntr=0.3,0.1