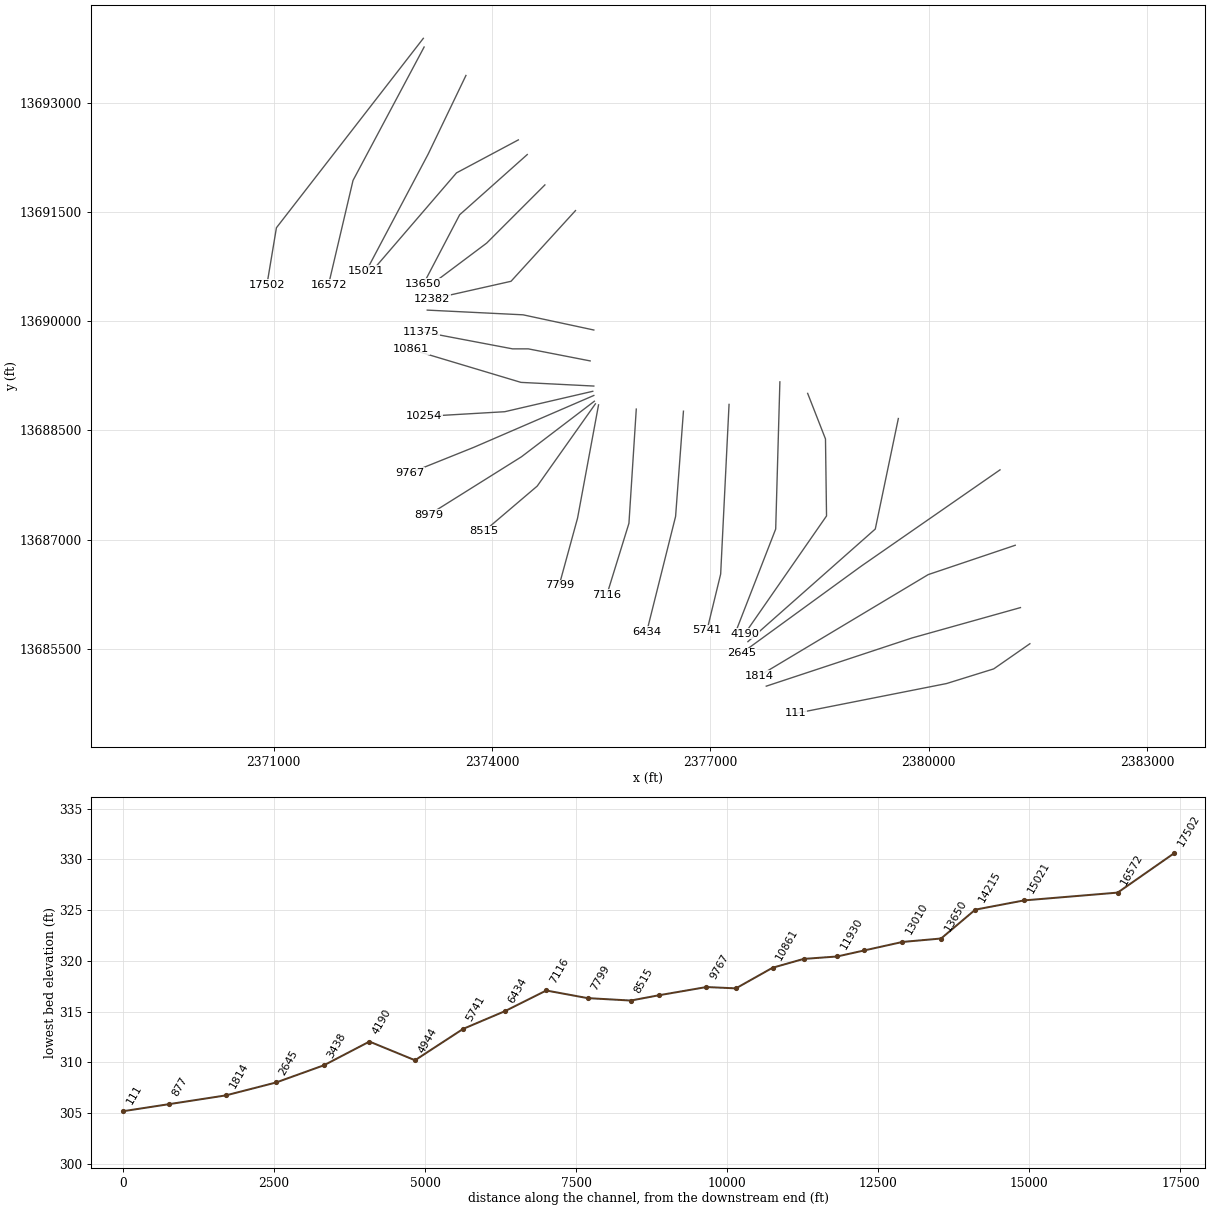
HEC-RAS study ONEIL CREEK.prj: ONEIL CREEK Base Level Engineering

--- ONEIL CREEK.g01 (geometry) --- (continued)

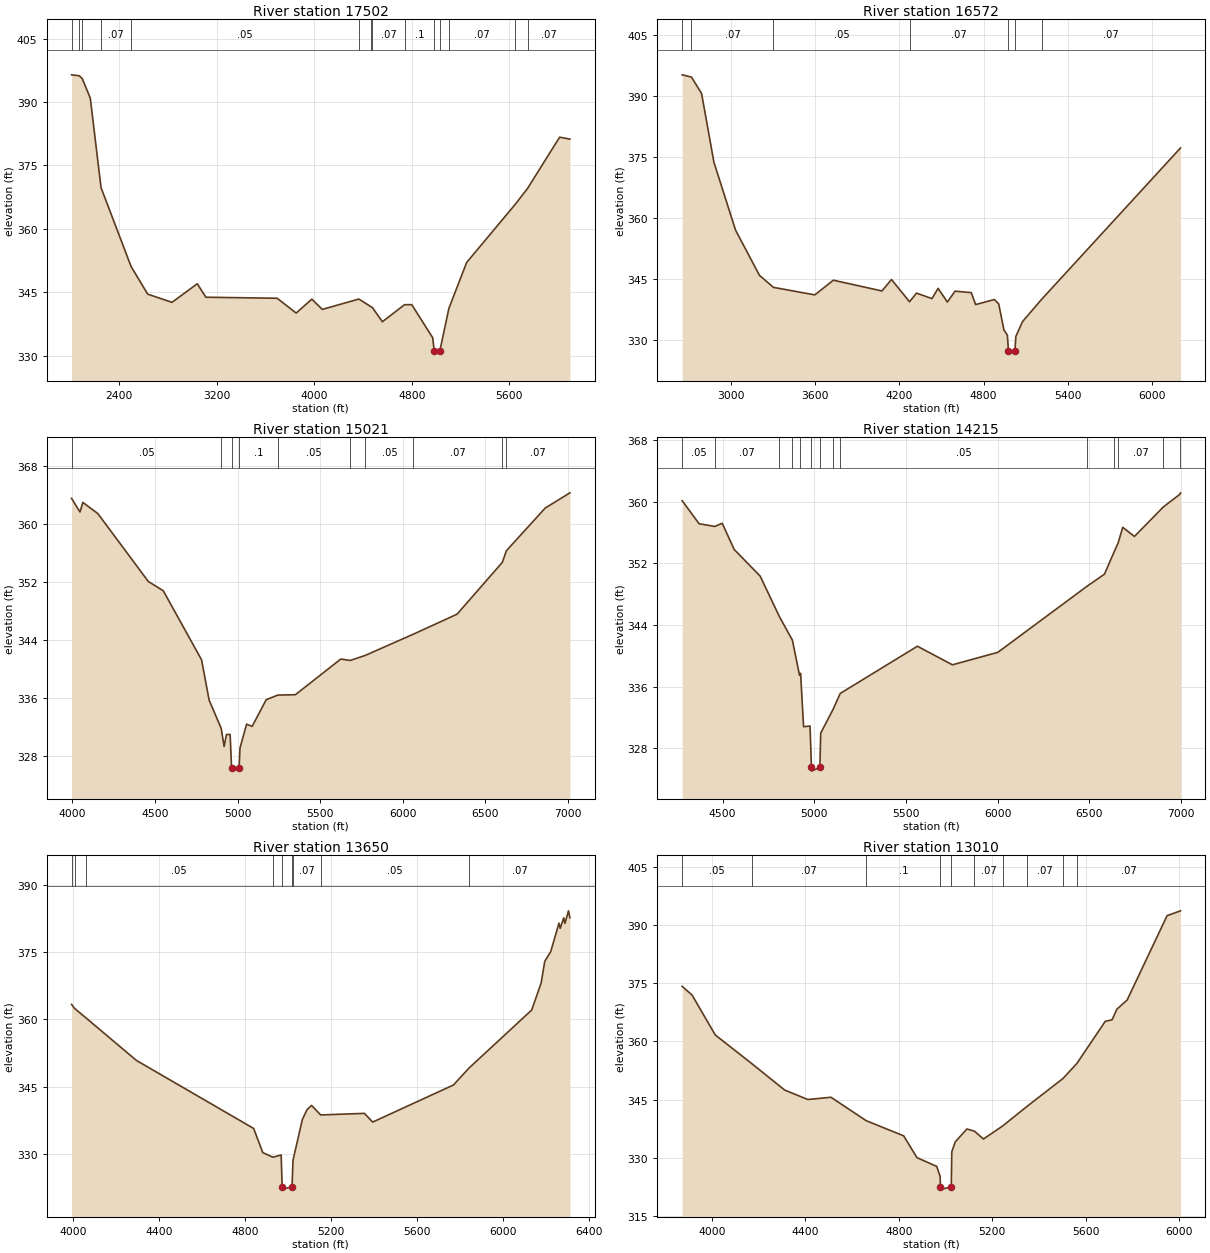
Type RM Length L Ch R = 1 ,17502   ,930,930,930
BEGIN DESCRIPTION:
B19879
END DESCRIPTION:
XS GIS Cut Line= 3
       2373054.9     13693890.12      2371036.68     13691285.96
      2370906.47     13690504.71
#Sta/Elev= 30
  2009.9  396.45  2072.9  396.23  2097.1  395.58  2163.3  390.94  2251.4  369.76
  2497.7   351.1  2634.1  344.54  2833.3   342.6  3040.6     347  3111.2  343.81
    3696  343.57  3851.7  340.06  3980.3  343.36  4065.9  340.93  4365.9  343.38
  4462.6  341.61  4477.1  341.36  4558.8  338.01  4740.3  342.04  4799.7  342.05
  4971.6  334.21  4984.1  331.08  4985.1  330.58  5029.7  331.08  5104.2  341.17
  5249.5  352.02    5649  365.83  5749.4  369.57  6012.2  381.69  6096.6  381.24
#Mann= 14 ,-1 , 0
  2009.9     .12       0  2072.9     .07       0  2097.1     .12       0
  2251.4     .07       0  2497.7     .05       0  4365.9     .07       0
  4462.6     .05       0  4477.1     .07       0  4740.3      .1       0
  4984.1     .05       0  5029.7      .1       0  5104.2     .07       0
    5649    .035       0  5749.4     .07       0
Bank Sta=4984.1,5029.7
XS Rating Curve= 0 ,0
Exp/Cntr=0.3,0.1

Type RM Length L Ch R = 1 ,16572   ,1551,1551,1551
BEGIN DESCRIPTION:
B19878
END DESCRIPTION:
XS GIS Cut Line= 3
      2373065.74     13693770.73       2372089.2       13691937.
      2371752.83     13690504.71
#Sta/Elev= 30
  2653.3  395.21  2719.4  394.65  2791.6  390.62  2879.5  373.69  3033.7  356.97
  3203.6  345.87  3303.5   342.9    3598  341.05  3729.8  344.67    4076  342.02
    4144  344.84  4272.4  339.36  4322.2  341.49  4432.1  340.14    4476  342.66
  4541.9  339.29  4596.5  341.97    4712  341.61  4743.2  338.67  4876.7  339.91
  4907.5  338.83  4944.8  332.43  4969.2  331.15  4977.2  327.22  4978.2  326.72
  5022.8  327.22  5029.6  330.83  5077.1  334.48    5213  339.95  6202.1  377.21
#Mann= 7 ,-1 , 0
  2653.3     .12       0  2719.4     .07       0  3303.5     .05       0
  4272.4     .07       0  4977.2     .05       0  5022.8     .07       0
    5213     .07       0
Bank Sta=4977.2,5022.8
XS Rating Curve= 0 ,0
Exp/Cntr=0.3,0.1

Type RM Length L Ch R = 1 ,15021   ,806,806,806
BEGIN DESCRIPTION:
B19877
END DESCRIPTION:
XS GIS Cut Line= 3
       2373640.3     13693379.71      2373121.86     13692299.63
      2372272.21     13690693.93
#Sta/Elev= 30
  3996.2  363.57  4047.2   361.7  4064.3  363.02  4154.9  361.48  4460.4  352.11
    4551  350.83  4782.6   341.3  4828.3  335.75  4901.5  331.84  4918.9  329.34
  4933.2     331  4955.4  331.01  4963.9  326.45  4964.9  325.95  5009.7  326.45
    5015  329.13  5054.8  332.43  5088.5  332.12  5173.6   335.8  5243.6  336.44
  5350.1  336.49  5624.8  341.41  5682.9  341.22  5773.5  341.92  6063.9  344.84
  6328.3   347.6    6602  354.75  6626.6  356.35  6861.5  362.24  7010.9  364.34
#Mann= 10 ,-1 , 0
  3996.2     .05       0  4901.5      .1       0  4963.9     .05       0
  5009.7      .1       0  5243.6     .05       0  5682.9     .07       0
  5773.5     .05       0  6063.9     .07       0    6602     .05       0
  6626.6     .07       0
Bank Sta=4963.9,5009.7
XS Rating Curve= 0 ,0
Exp/Cntr=0.3,0.1

Type RM Length L Ch R = 1 ,14215   ,565,565,565
BEGIN DESCRIPTION:
B19876
END DESCRIPTION:
XS GIS Cut Line= 3
      2374360.36     13692494.05      2373510.69     13692040.41
       2372366.5     13690709.13
#Sta/Elev= 30
  4279.7  360.12    4372  357.13  4458.1  356.78  4498.1  357.19  4563.9  353.78
  4705.2  350.34    4810  345.09  4881.1  342.03  4919.9  337.47  4925.8  337.73
    4942   330.8  4977.3  330.89    4985  325.54    4986  325.04  5030.9  325.54
  5035.5  329.97  5102.3  333.02  5142.1  335.12    5563  341.24    5754  338.83
    6002  340.45    6490  349.05  6583.5  350.59  6633.8  353.35  6658.1  354.64
  6683.4  356.67    6747  355.48  6905.3  359.32  6996.5  360.98  6998.3  361.14
#Mann= 14 ,-1 , 0
  4279.7     .05       0  4458.1     .07       0    4810     .05       0
  4881.1     .07       0  4919.9     .12       0    4985     .05       0
  5030.9     .12       0  5102.3     .07       0  5142.1     .05       0
    6490     .07       0  6633.8     .05       0  6658.1     .07       0
  6905.3    .035       0  6996.5     .07       0
Bank Sta=4985,5030.9
XS Rating Curve= 0 ,0
Exp/Cntr=0.3,0.1

Type RM Length L Ch R = 1 ,13650   ,640,640,640
BEGIN DESCRIPTION:
B19875
END DESCRIPTION:
XS GIS Cut Line= 3
      2374482.77     13692292.45      2373553.89     13691464.37
      2373057.05     13690513.89
#Sta/Elev= 30
  3992.9  363.36  4006.6  362.48  4057.9  360.43  4294.2  350.88  4839.4  335.72
    4882  330.34  4928.8  329.31  4967.3  329.81  4971.9   322.7  4972.9   322.2
  5017.8   322.7  5022.5  328.66  5065.9  337.73  5087.7  339.91  5108.6  340.86
  5151.1  338.73  5354.3  339.08  5392.9  337.14  5768.2   345.4  5840.7  349.18
  6132.2  362.11  6176.3  368.17  6192.8  372.95  6220.5   375.1    6259  381.47
  6264.7   380.3  6281.1  382.66  6286.7  381.42  6303.2  384.21  6309.8  382.65
#Mann= 9 ,-1 , 0
  3992.9     .05       0  4006.6     .07       0  4057.9     .05       0
  4928.8      .1       0  4971.9     .05       0  5017.8      .1       0
  5022.5     .07       0  5151.1     .05       0  5840.7     .07       0
Bank Sta=4971.9,5017.8
XS Rating Curve= 0 ,0
Exp/Cntr=0.3,0.1

Type RM Length L Ch R = 1 ,13010   ,628,628,628
BEGIN DESCRIPTION:
ONEIL CREEK 7434
END DESCRIPTION:
XS GIS Cut Line= 3
      2374724.97     13691874.97        2373925.       13691075.
      2373125.03     13690475.02
#Sta/Elev= 30
  3873.3  374.22  3915.7  371.97  4014.7  361.68  4172.7  354.19  4311.7  347.44
  4410.7     345  4509.7  345.58  4660.2  339.54  4820.8  335.61  4877.4  329.99
  4962.2  327.72  4976.4  325.18  4978.1  322.36  4979.1  321.86  5024.1  322.36
  5026.5  331.51  5041.1  334.04  5091.1  337.39  5123.2  336.83  5161.9   334.8
  5243.6  338.15    5350  343.31  5502.1  350.43  5561.2  354.29  5682.8  365.19
  5711.9  365.58  5732.8  368.34  5776.5   370.7  5947.3  392.47  6004.6  393.72
#Mann= 10 ,-1 , 0
  3873.3     .05       0  4172.7     .07       0  4660.2      .1       0
  4978.1     .05       0  5024.1      .1       0  5123.2     .07       0
  5243.6     .05       0    5350     .07       0  5502.1     .05       0
  5561.2     .07       0
Bank Sta=4978.1,5024.1
XS Rating Curve= 0 ,0
Exp/Cntr=0.3,0.1

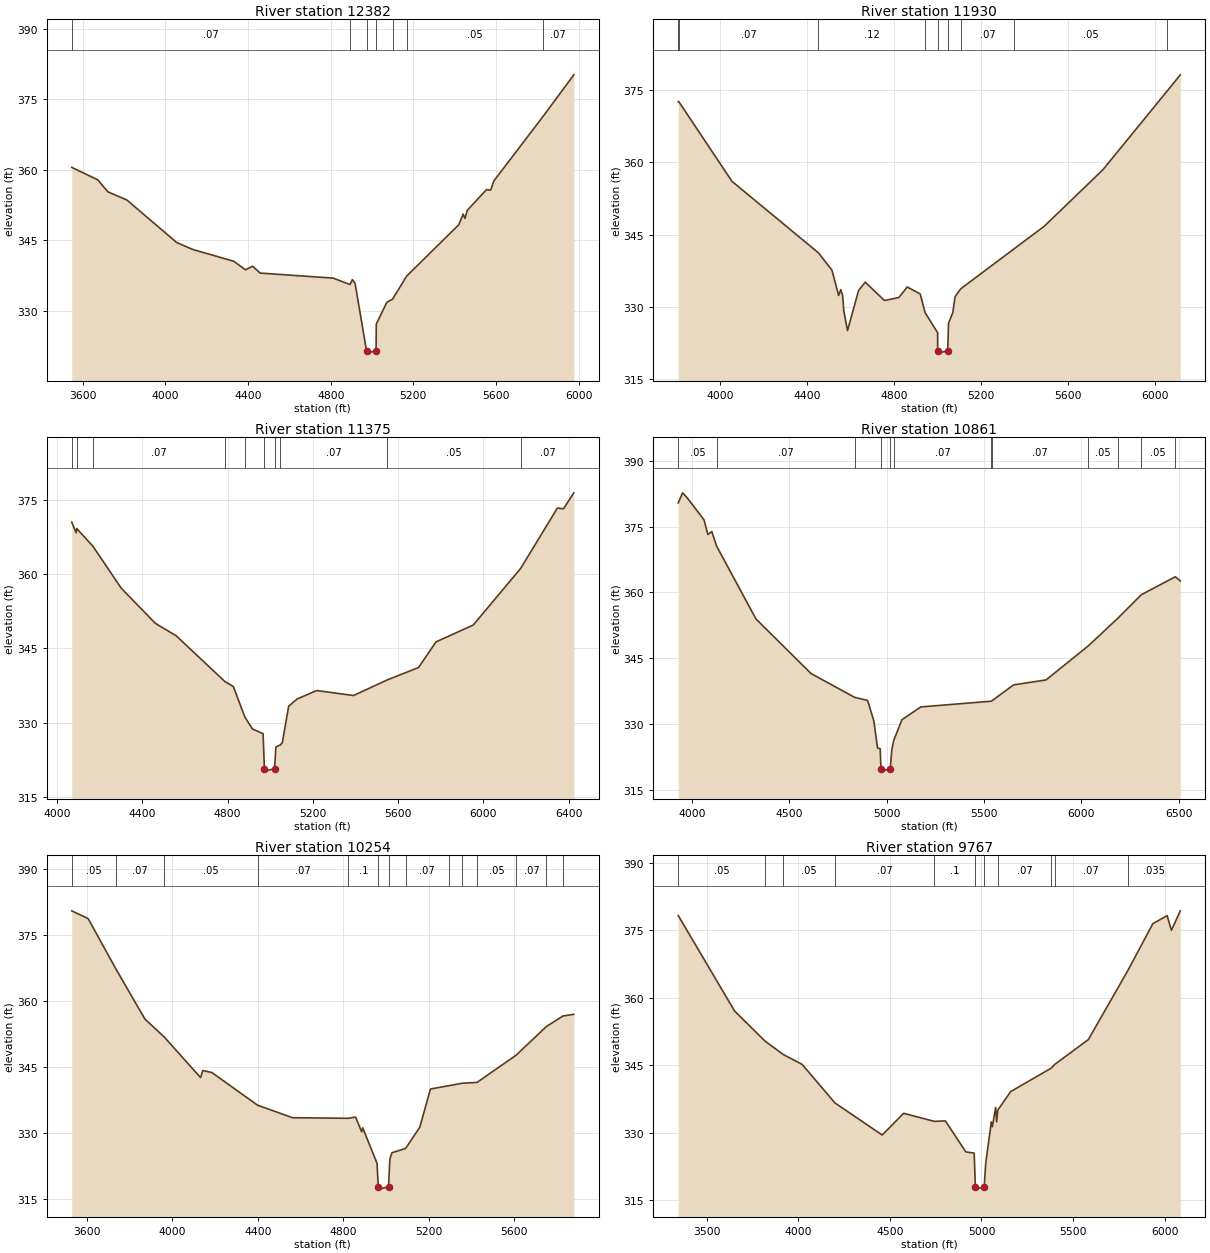
Type RM Length L Ch R = 1 ,12382   ,452,452,452
BEGIN DESCRIPTION:
B19874
END DESCRIPTION:
XS GIS Cut Line= 3
      2375145.21       13691522.      2374259.53     13690549.91
      2373172.22     13690305.08
#Sta/Elev= 30
    3547  360.52  3672.5  357.89  3721.8  355.33  3813.7  353.59  4054.9  344.54
  4132.6  343.07  4330.6  340.57  4387.3  338.75  4422.5  339.51  4458.3  338.05
  4812.3  336.98  4893.2  335.61  4904.9  336.65    4918  335.85  4973.5  321.53
  4974.5  321.03  5019.6  321.53  5020.5  327.19  5071.7  331.85  5099.5   332.5
  5167.5  337.41  5420.2  348.35  5440.7  350.59  5449.7  349.68  5461.2   351.4
  5553.5  355.78    5574  355.69  5589.7  357.65  5825.8  371.25  5976.6   380.2
#Mann= 7 ,-1 , 0
    3547     .07       0  4893.2      .1       0  4973.5     .05       0
  5019.6      .1       0  5099.5     .07       0  5167.5     .05       0
  5825.8     .07       0
Bank Sta=4973.5,5019.6
XS Rating Curve= 0 ,0
Exp/Cntr=0.3,0.1

Type RM Length L Ch R = 1 ,11930   ,555,555,555
BEGIN DESCRIPTION:
ONEIL CREEK 7433
END DESCRIPTION:
XS GIS Cut Line= 3
      2375397.21     13689880.27      2374425.15     13690089.08
      2373108.78     13690153.82
#Sta/Elev= 30
  3805.6  372.57  3808.3  372.57  4053.3  356.04  4451.2  341.23  4513.5  337.63
  4544.3  332.39  4554.5  333.59  4562.9  332.35    4568  329.23  4585.2   325.1
  4636.3  333.43    4667  335.14  4755.3  331.34  4821.8  331.96  4860.1  334.15
  4920.1  332.69  4942.5  328.83  5000.2  324.65  5000.6  320.93  5001.6  320.43
  5046.7  320.93  5050.3  326.59  5070.3  328.86  5080.3  332.11  5106.1  333.75
  5352.2  342.05  5490.8  346.72  5761.1  358.44  6055.6  374.68  6117.8  378.13
#Mann= 9 ,-1 , 0
  3805.6    .035       0  3808.3     .07       0  4451.2     .12       0
  4942.5      .1       0  5000.6     .05       0  5046.7      .1       0
  5106.1     .07       0  5352.2     .05       0  6055.6     .07       0
Bank Sta=5000.6,5046.7
XS Rating Curve= 0 ,0
Exp/Cntr=0.3,0.1

Type RM Length L Ch R = 1 ,11375   ,514,514,514
BEGIN DESCRIPTION:
B19873
END DESCRIPTION:
XS GIS Cut Line= 4
      2375346.85     13689455.43      2374497.15     13689621.05
      2374281.14     13689621.05      2373029.16     13689858.49
#Sta/Elev= 30
    4069   370.5  4089.5  368.35  4092.5   369.2  4168.5  365.62    4301  357.16
  4460.9  350.06  4559.1  347.53  4786.9  338.32  4827.3  337.28    4881  331.14
  4916.5  328.73  4966.8  327.75  4972.9  320.69  4973.9  320.19  5020.7  320.69
  5026.8  325.07  5048.3  325.51  5056.8  325.91  5086.8   333.3  5126.8  334.77
    5218  336.47    5391  335.47  5550.2  338.63  5696.4  341.13  5777.8  346.29
    5953  349.71    6176  361.18  6347.8  373.34  6376.3  373.19    6425  376.42
#Mann= 10 ,-1 , 0
    4069    .035       0  4092.5     .05       0  4168.5     .07       0
  4786.9     .12       0    4881      .1       0  4972.9     .05       0
  5020.7      .1       0  5048.3     .07       0  5550.2     .05       0
    6176     .07       0
Bank Sta=4972.9,5020.7
XS Rating Curve= 0 ,0
Exp/Cntr=0.3,0.1

Type RM Length L Ch R = 1 ,10861   ,607,607,607
BEGIN DESCRIPTION:
B19872
END DESCRIPTION:
XS GIS Cut Line= 3
       2375397.2     13689109.82      2374396.34     13689160.22
      2372884.24     13689613.85
#Sta/Elev= 30
  3928.5  380.39  3950.7  382.69  3970.7  381.76  4060.9  376.56  4080.9  373.21
  4100.9  373.86  4126.5   370.5    4328  353.97  4611.6  341.53  4835.3  336.12
  4901.9  335.41  4933.9  330.78  4952.9  324.57  4966.6  324.42  4970.5  319.82
  4971.5  319.32  5018.4  319.82    5026  324.06  5035.8  326.27  5078.2  331.02
  5175.4  333.94  5537.1  335.24  5539.4  335.28  5652.4  338.96  5819.4  340.09
  6036.8  347.86  6187.4   354.1  6308.6  359.48  6483.5  363.57  6509.3  362.63
#Mann= 12 ,-1 , 0
  3928.5     .05       0  4126.5     .07       0  4835.3      .1       0
  4970.5     .05       0  5018.4      .1       0  5035.8     .07       0
  5537.1     .05       0  5539.4     .07       0  6036.8     .05       0
  6187.4     .07       0  6308.6     .05       0  6483.5     .07       0
Bank Sta=4970.5,5018.4
XS Rating Curve= 0 ,0
Exp/Cntr=0.3,0.1

Type RM Length L Ch R = 1 ,10254   ,487,487,487
BEGIN DESCRIPTION:
B19871
END DESCRIPTION:
XS GIS Cut Line= 3
      2375382.78      13689037.8      2374173.13     13688756.99
      2373064.23     13688692.19
#Sta/Elev= 30
  3528.3  380.43    3605  378.67    3735  367.25  3871.1  355.88  3962.8  351.75
  4131.7   342.6  4142.4   344.2    4185  343.74  4398.6  336.34  4562.9  333.49
  4823.6  333.36  4858.4  333.63  4886.7  330.28  4891.7   331.2  4958.6  323.16
  4964.6  317.79  4965.6  317.29  5012.6  317.79  5018.7  324.07  5028.7  325.55
  5092.4  326.51  5158.9  331.32    5209     340  5294.3  340.75  5356.4  341.31
  5427.3   341.5  5611.2  347.71    5752  354.17  5830.3  356.58  5880.9  356.95
#Mann= 14 ,-1 , 0
  3528.3     .05       0    3735     .07       0  3962.8     .05       0
  4398.6     .07       0  4823.6      .1       0  4964.6     .05       0
  5012.6      .1       0  5092.4     .07       0  5294.3     .05       0
  5356.4     .07       0  5427.3     .05       0  5611.2     .07       0
    5752     .05       0  5830.3     .07       0
Bank Sta=4964.6,5012.6
XS Rating Curve= 0 ,0
Exp/Cntr=0.3,0.1

Type RM Length L Ch R = 1 ,9767    ,788,788,788
BEGIN DESCRIPTION:
B19870
END DESCRIPTION:
XS GIS Cut Line= 3
      2375397.19      13688980.2       2373748.3     13688267.36
      2372869.88     13687914.55
#Sta/Elev= 30
  3343.3  378.26  3651.2  357.03  3817.3  350.35  3916.7  347.37    4020  345.17
  4199.2   336.6  4457.5  329.45    4575  334.29  4742.1  332.49  4802.8  332.59
  4914.5   325.7  4960.1  325.43  4966.7  317.92  4967.7  317.42  5014.7  317.92
  5023.4  323.28    5054  332.36  5059.5   331.3  5077.5  335.57    5083  332.37
  5088.8  334.97  5159.4  339.11  5380.5  344.31  5400.7  345.17  5584.2  350.69
  5798.3  365.93  5936.4  376.46  6014.4  378.24  6037.7  374.98  6086.3  379.31
#Mann= 11 ,-1 , 0
  3343.3     .05       0  3817.3     .07       0  3916.7     .05       0
  4199.2     .07       0  4742.1      .1       0  4966.7     .05       0
  5014.7      .1       0  5088.8     .07       0  5380.5     .05       0
  5400.7     .07       0  5798.3    .035       0
Bank Sta=4966.7,5014.7
XS Rating Curve= 0 ,0
Exp/Cntr=0.3,0.1

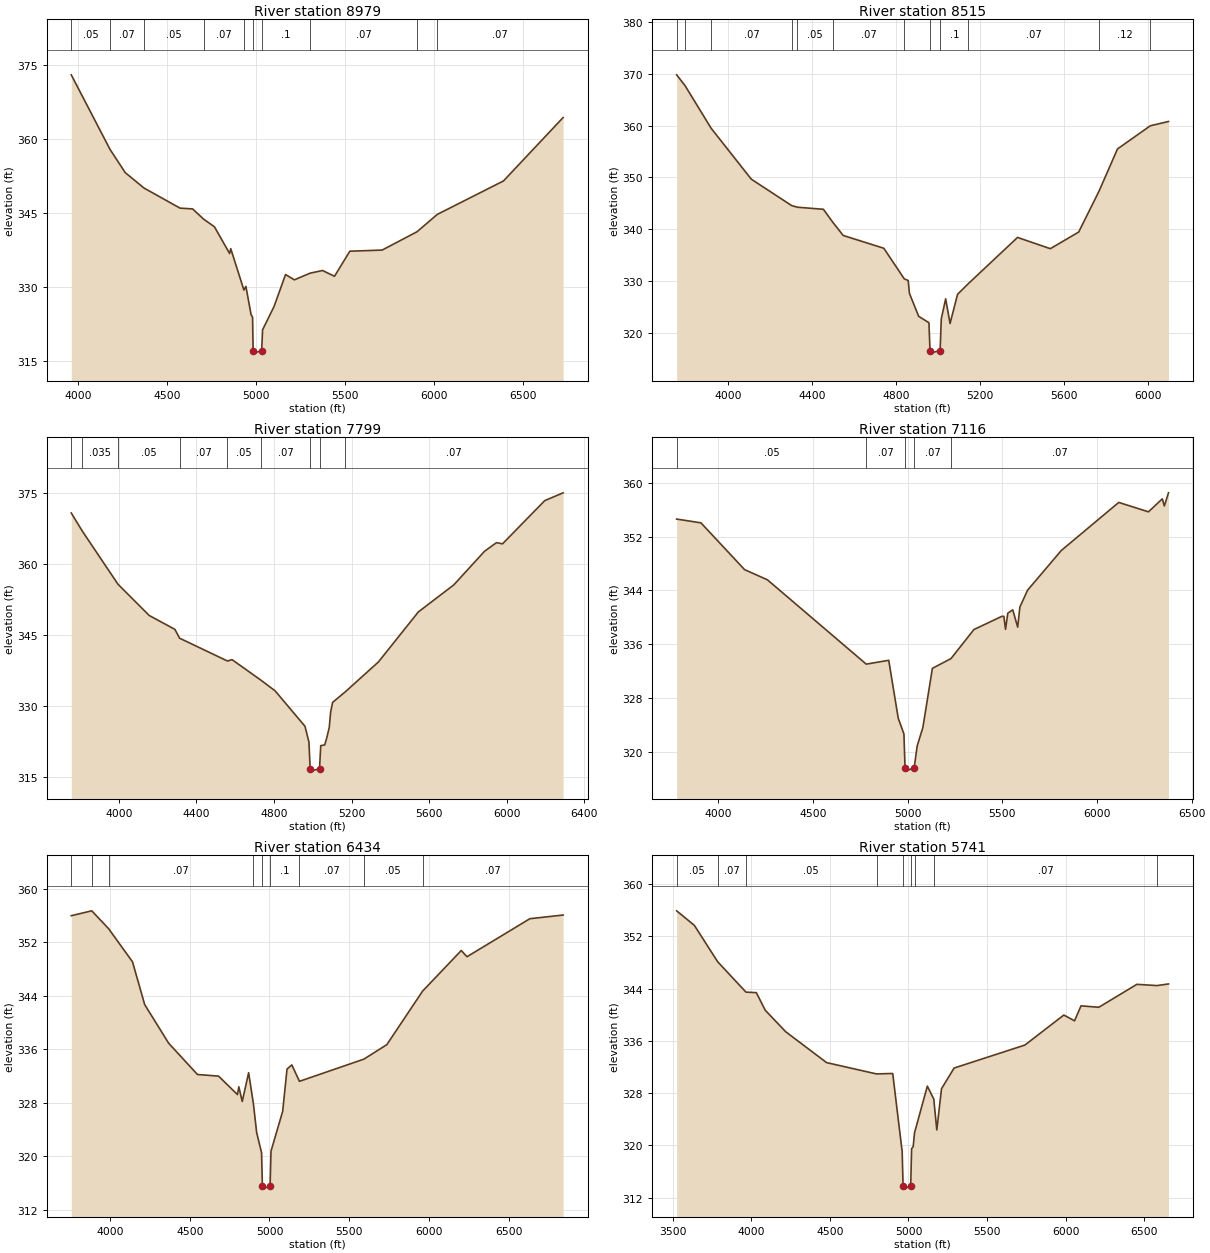
Type RM Length L Ch R = 1 ,8979    ,464,464,464
BEGIN DESCRIPTION:
B19869
END DESCRIPTION:
XS GIS Cut Line= 3
       2375404.4     13688900.99      2374403.54     13688137.75
       2373130.7     13687339.53
#Sta/Elev= 30
  3962.1     373  4179.6   357.9    4265  353.19  4370.2  350.07  4572.6  345.99
  4643.3  345.83  4704.9  343.77  4765.9  342.21  4851.1  336.79  4857.4  337.78
  4931.3  329.39  4942.6  330.13  4971.7  324.39  4979.9  323.89  4983.1  317.11
  4984.1  316.61  5031.1  317.11  5036.1  321.33  5100.5  326.05    5165  332.53
  5214.9  331.46  5302.7  332.81  5372.8  333.35  5439.9  332.18  5525.9  337.26
  5707.4  337.49    5903   341.2  6017.1  344.72  6388.5   351.5  6723.2  364.34
#Mann= 10 ,-1 , 0
  3962.1     .05       0  4179.6     .07       0  4370.2     .05       0
  4704.9     .07       0  4931.3      .1       0  4983.1     .05       0
  5031.1      .1       0  5302.7     .07       0    5903    .035       0
  6017.1     .07       0
Bank Sta=4983.1,5031.1
XS Rating Curve= 0 ,0
Exp/Cntr=0.3,0.1

Type RM Length L Ch R = 1 ,8515    ,716,716,716
BEGIN DESCRIPTION:
B19868
END DESCRIPTION:
XS GIS Cut Line= 3
      2375418.78     13688864.96      2374619.56     13687734.53
      2373892.31     13687115.28
#Sta/Elev= 30
  3756.1  369.78    3796   367.7  3920.4  359.46  4111.2  349.65  4303.3  344.55
  4330.7  344.24  4454.1  343.84  4499.2  341.32  4548.4  338.79  4741.6  336.32
  4838.9  330.42  4857.4  330.11  4863.5  327.62  4907.3  323.19  4956.2  321.96
  4961.3  316.59  4962.3  316.09  5009.4  316.59  5014.9  322.68  5035.8  326.56
  5056.7  321.81  5092.4  327.44  5143.8   329.5  5377.6  338.41  5533.6  336.24
  5668.6  339.45  5765.1  347.32  5853.1  355.48  6009.2  359.95  6095.7  360.78
#Mann= 12 ,-1 , 0
  3756.1    .035       0    3796     .05       0  3920.4     .07       0
  4303.3    .035       0  4330.7     .05       0  4499.2     .07       0
  4838.9      .1       0  4961.3     .05       0  5009.4      .1       0
  5143.8     .07       0  5765.1     .12       0  6009.2     .07       0
Bank Sta=4961.3,5009.4
XS Rating Curve= 0 ,0
Exp/Cntr=0.3,0.1

Type RM Length L Ch R = 1 ,7799    ,683,683,683
BEGIN DESCRIPTION:
B19867
END DESCRIPTION:
XS GIS Cut Line= 3
      2375462.02     13688850.62      2375173.99      13687295.3
      2374921.97      13686373.6
#Sta/Elev= 30
  3754.3  370.79  3811.4  366.96  3995.7  355.74  4156.6  349.16  4288.9  346.24
    4313  344.38  4560.1  339.56  4583.8  339.85  4731.7  335.55  4805.6  333.28
  4960.1  325.79  4980.4  322.45  4986.8  316.83  4987.8  316.33    5035  316.83
  5041.4  321.71  5061.8  321.86  5071.9  323.28  5085.3  325.55  5092.3  328.75
  5102.5  330.83  5167.8  333.05  5338.8  339.36  5544.8  349.91  5727.7  355.62
  5886.5  362.72    5948  364.53  5979.1  364.28  6196.8  373.39  6291.6  375.04
#Mann= 9 ,-1 , 0
  3754.3     .05       0  3811.4    .035       0  3995.7     .05       0
    4313     .07       0  4560.1     .05       0  4731.7     .07       0
  4986.8     .05       0    5035     .07       0  5167.8     .07       0
Bank Sta=4986.8,5035
XS Rating Curve= 0 ,0
Exp/Cntr=0.3,0.1

Type RM Length L Ch R = 1 ,7116    ,682,682,682
BEGIN DESCRIPTION:
B19866
END DESCRIPTION:
XS GIS Cut Line= 3
      2375980.45     13688793.01      2375879.64     13687223.29
      2375577.21     13686243.98
#Sta/Elev= 30
  3779.7  354.63    3908  354.07  4138.5   347.1  4259.3  345.58  4781.1  333.02
    4900  333.59  4950.1  324.97  4980.2  322.61  4986.1  317.58  4987.1  317.08
  5034.4  317.58  5050.3  320.84  5080.4  323.59  5130.5  332.39    5229  333.85
  5349.8  338.17  5497.4  340.14  5507.9  340.14    5517  338.21  5528.8  340.61
  5554.9  341.11  5581.1  338.53  5592.7  341.53  5633.5  344.04  5811.4  349.95
  6114.9  357.11  6271.9  355.71  6345.1  357.65  6355.6  356.58  6377.6  358.54
#Mann= 5 ,-1 , 0
  3779.7     .05       0  4781.1     .07       0  4986.1     .05       0
  5034.4     .07       0    5229     .07       0
Bank Sta=4986.1,5034.4
XS Rating Curve= 0 ,0
Exp/Cntr=0.3,0.1

Type RM Length L Ch R = 1 ,6434    ,693,693,693
BEGIN DESCRIPTION:
B19865
END DESCRIPTION:
XS GIS Cut Line= 3
      2376628.49     13688764.24      2376520.48      13687316.9
      2376124.46     13685732.82
#Sta/Elev= 30
    3757  355.96  3885.5  356.69    3991  354.03  4141.1  349.06  4217.5  342.66
  4367.9  336.88  4548.4   332.2  4680.6  331.96  4799.1   329.2  4807.9  330.36
  4829.2  328.17  4869.3  332.47  4899.4  327.79  4919.5  323.53  4950.3   320.5
  4955.5  315.55  4956.5  315.05  5003.8  315.55  5009.7  320.74  5082.7  326.69
    5110  333.01  5140.1  333.64    5188  331.18  5592.1   334.5    5736  336.67
  5959.9  344.67  6202.5  350.75  6238.5  349.82  6632.8  355.51  6841.2  356.06
#Mann= 9 ,-1 , 0
    3757     .07       0  3885.5     .05       0    3991     .07       0
  4899.4      .1       0  4955.5     .05       0  5003.8      .1       0
    5188     .07       0  5592.1     .05       0  5959.9     .07       0
Bank Sta=4955.5,5003.8
XS Rating Curve= 0 ,0
Exp/Cntr=0.3,0.1

Type RM Length L Ch R = 1 ,5741    ,797,797,797
BEGIN DESCRIPTION:
B19864
END DESCRIPTION:
XS GIS Cut Line= 3
      2377254.93     13688857.77      2377139.72     13686524.85
      2376952.52     13685754.43
#Sta/Elev= 30
  3525.5  355.89  3638.4  353.66  3786.4   348.1  3966.4  343.45  4032.4  343.37
    4089  340.68  4219.1  337.39  4479.4  332.66  4796.8  330.93  4899.9     331
    4960  319.05  4965.8   313.8  4966.8   313.3  5014.3   313.8  5020.1  319.48
  5030.1  319.81  5038.9  321.94  5120.2  329.06  5161.1  327.08  5180.3  322.36
  5210.3  328.66  5290.4  331.83    5741  335.35  5988.4  339.94  6056.6  339.06
  6097.8  341.35    6211  341.13  6452.9  344.64  6580.7  344.45  6654.1   344.7
#Mann= 9 ,-1 , 0
  3525.5     .05       0  3786.4     .07       0  3966.4     .05       0
  4796.8     .07       0  4965.8     .05       0  5014.3     .07       0
  5038.9      .1       0  5161.1     .07       0  6580.7    .035       0
Bank Sta=4965.8,5014.3
XS Rating Curve= 0 ,0
Exp/Cntr=0.3,0.1

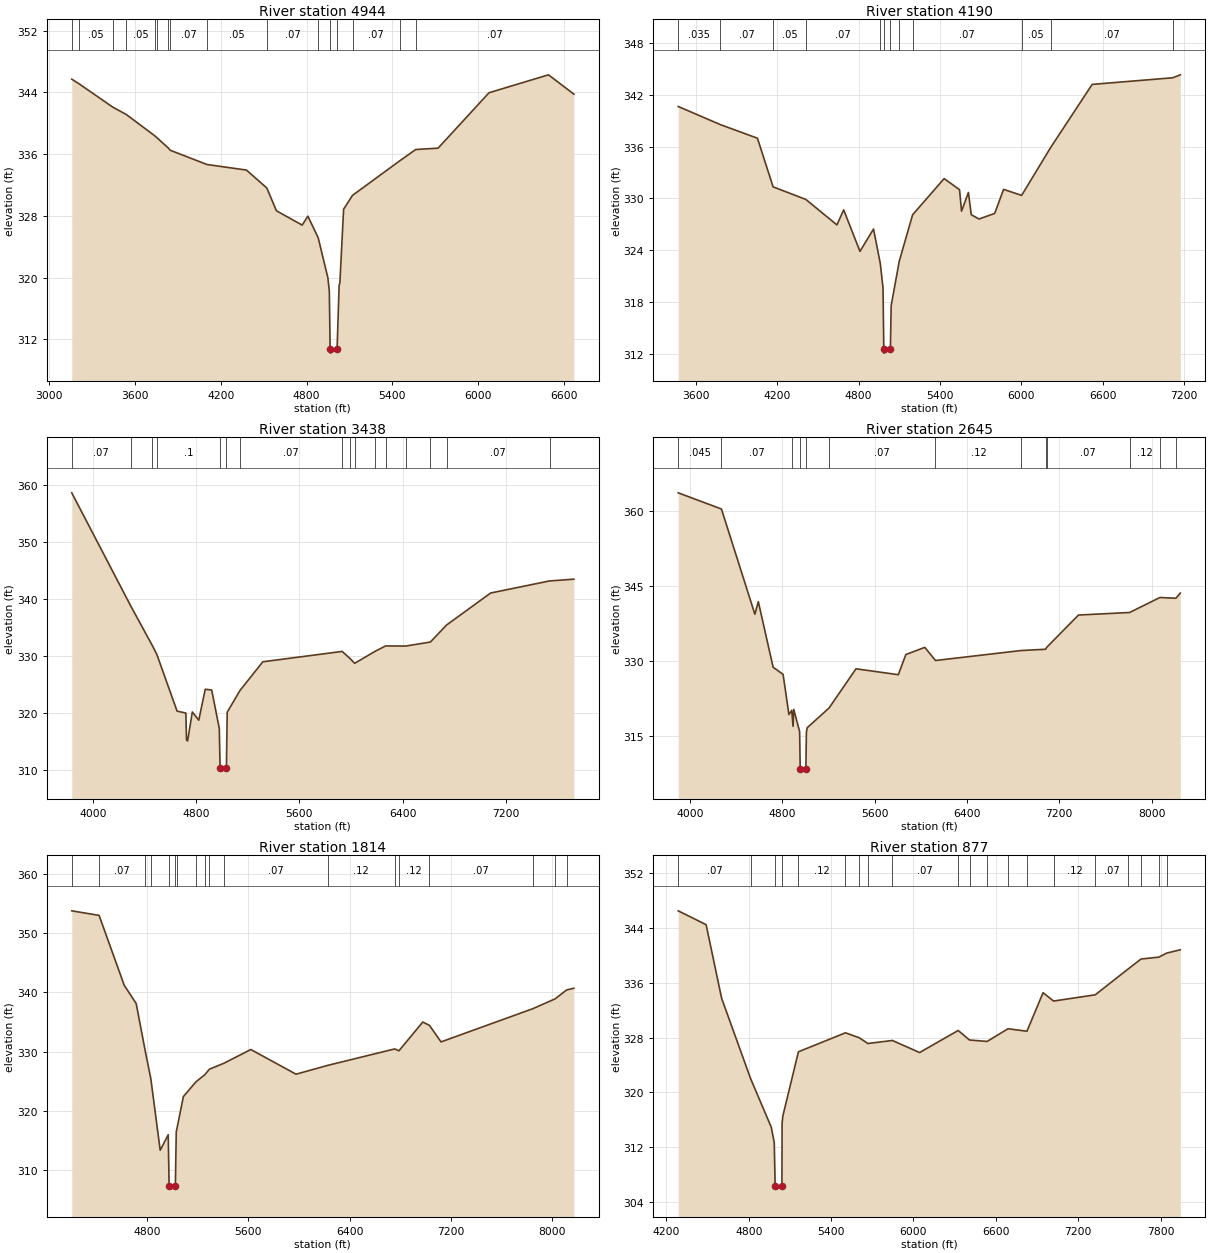
Type RM Length L Ch R = 1 ,4944    ,754,754,754
BEGIN DESCRIPTION:
B19863
END DESCRIPTION:
XS GIS Cut Line= 3
      2377953.38     13689167.44      2377895.77     13687144.09
      2377355.74      13685754.4
#Sta/Elev= 30
  3156.6  345.71  3206.5  345.12  3443.5  342.09  3539.1  341.12  3736.3  338.39
  3753.6  338.11  3833.1  336.78  3845.5   336.5  4103.3  334.65  4379.5  333.93
  4522.1  331.61  4589.6  328.65  4769.7   326.8  4809.7  327.95  4881.9  325.16
  4949.8  319.96  4959.8  318.21  4965.5  310.71  4966.5  310.21  5014.1  310.71
  5028.5     319  5033.5  319.28  5059.8  328.86  5122.2  330.65  5452.9  335.13
  5564.7  336.59  5721.4  336.77  6077.9  343.95  6494.2  346.27  6671.7  343.77
#Mann= 16 ,-1 , 0
  3156.6    .035       0  3206.5     .05       0  3443.5     .07       0
  3539.1     .05       0  3736.3    .035       0  3753.6     .07       0
  3833.1     .05       0  3845.5     .07       0  4103.3     .05       0
  4522.1     .07       0  4881.9      .1       0  4965.5     .05       0
  5014.1      .1       0  5122.2     .07       0  5452.9     .05       0
  5564.7     .07       0
Bank Sta=4965.5,5014.1
XS Rating Curve= 0 ,0
Exp/Cntr=0.3,0.1

Type RM Length L Ch R = 1 ,4190    ,752,752,752
BEGIN DESCRIPTION:
B19862
END DESCRIPTION:
XS GIS Cut Line= 4
      2378334.99     13689009.04      2378579.82     13688382.57
      2378594.22      13687324.1      2377470.94     13685703.99
#Sta/Elev= 30
  3469.8  340.65    3780  338.55  4053.9  336.97  4169.4  331.33  4410.9  329.87
    4640  326.92    4690  328.66    4810  323.85  4910.1  326.44  4959.9  322.44
  4980.1   319.6  4985.7  312.55  4986.7  312.05  5034.4  312.55  5040.1  317.56
  5099.8  322.71  5198.2  328.09  5430.8  332.29  5544.3     331  5559.1  328.51
  5609.8  330.68  5630.7   328.1  5687.5   327.6  5803.7  328.25  5869.2  331.04
  6002.3  330.34  6216.2  335.89  6522.4  343.21  7117.3  343.98  7172.4  344.32
#Mann= 12 ,-1 , 0
  3469.8    .035       0    3780     .07       0  4169.4     .05       0
  4410.9     .07       0  4959.9      .1       0  4985.7     .05       0
  5034.4      .1       0  5099.8     .12       0  5198.2     .07       0
  6002.3     .05       0  6216.2     .07       0  7117.3     .12       0
Bank Sta=4985.7,5034.4
XS Rating Curve= 0 ,0
Exp/Cntr=0.3,0.1

Type RM Length L Ch R = 1 ,3438    ,793,793,793
BEGIN DESCRIPTION:
B19861
END DESCRIPTION:
XS GIS Cut Line= 3
      2379580.69     13688663.42      2379263.86     13687144.09
      2377514.13     13685595.97
#Sta/Elev= 30
  3837.1  358.61  4292.1  338.81  4461.7  331.75    4496  330.22  4652.7  320.26
  4720.7  319.92  4725.8  315.17  4734.4  315.03  4770.7  320.11  4820.7  318.67
  4870.7   324.1  4920.8  323.97  4979.6  317.22  4985.9  310.22  4986.9  309.72
  5034.6  310.22  5040.9  320.07  5140.2   323.9  5316.7  328.93  5931.1  330.75
  5995.6  329.43  6027.8  328.66  6185.8  330.76    6267  331.71  6422.4  331.69
  6614.5   332.4  6739.3  335.38  7081.1  341.01    7537  343.13  7725.4  343.44
#Mann= 16 ,-1 , 0
  3837.1     .07       0  4292.1      .1       0  4461.7     .07       0
    4496      .1       0  4985.9     .05       0  5034.6      .1       0
  5140.2     .07       0  5931.1     .12       0  5995.6     .07       0
  6027.8     .12       0  6185.8     .07       0    6267     .12       0
  6422.4     .07       0  6614.5     .05       0  6739.3     .07       0
    7537     .12       0
Bank Sta=4985.9,5034.6
XS Rating Curve= 0 ,0
Exp/Cntr=0.3,0.1

Type RM Length L Ch R = 1 ,2645    ,831,831,831
BEGIN DESCRIPTION:
B19860
END DESCRIPTION:
XS GIS Cut Line= 3
      2380977.61     13687957.76      2379069.45     13686632.86
      2377428.84     13685438.38
#Sta/Elev= 30
  3897.1  363.72  4271.7  360.48  4561.6  339.42  4591.3  341.94  4719.6  328.82
  4806.1  327.38  4856.7  319.33  4881.1  320.18  4892.5  316.97  4898.6  320.38
  4949.3  315.94  4954.4  308.52  4955.4  308.02  5003.6  308.52  5008.1  315.81
  5014.8   316.7  5204.4  320.65  5438.2   328.5  5804.9  327.32  5870.4  331.36
  6034.6  332.79  6127.2  330.16  6870.9  332.16  7081.4  332.41  7090.3  332.77
  7366.6  339.26  7810.2  339.77  8072.7  342.77  8211.5  342.62  8249.5  343.66
#Mann= 13 ,-1 , 0
  3897.1    .045       0  4271.7     .07       0  4881.1      .1       0
  4954.4     .05       0  5003.6      .1       0  5204.4     .07       0
  6127.2     .12       0  6870.9     .07       0  7081.4     .05       0
  7090.3     .07       0  7810.2     .12       0  8072.7    .035       0
  8211.5     .07       0
Bank Sta=4954.4,5003.6
XS Rating Curve= 0 ,0
Exp/Cntr=0.3,0.1

Type RM Length L Ch R = 1 ,1814    ,937,937,937
BEGIN DESCRIPTION:
B19859
END DESCRIPTION:
XS GIS Cut Line= 3
      2381186.39     13686920.87      2379991.11     13686517.65
      2377674.26     13685128.98
#Sta/Elev= 30
  4206.1   353.8  4421.8  353.03    4620  341.22  4714.4  338.13  4785.7  330.14
  4829.5   325.5  4904.1  313.32  4967.4  315.94  4974.5  307.25  4975.5  306.75
  5023.7  307.25  5030.8  316.48  5034.1  316.76  5086.8  322.39  5186.8   324.9
  5255.5  326.08  5292.8  327.03  5404.7  328.01  5619.5  330.35    5976  326.18
  6228.1  327.68  6754.3  330.45  6788.5  330.14  6976.5     335  7029.4  334.43
  7120.4  331.64  7845.6  337.26  8021.1  338.92  8111.8  340.42  8168.7  340.72
#Mann= 18 ,-1 , 0
  4206.1    .045       0  4421.8     .07       0  4785.7     .12       0
  4829.5      .1       0  4974.5     .05       0  5023.7      .1       0
  5034.1     .07       0  5186.8      .1       0  5255.5     .07       0
  5292.8      .1       0  5404.7     .07       0  6228.1     .12       0
  6754.3     .07       0  6788.5     .12       0  7029.4     .07       0
  7845.6    .035       0  8021.1     .07       0  8111.8     .12       0
Bank Sta=4974.5,5023.7
XS Rating Curve= 0 ,0
Exp/Cntr=0.3,0.1

Type RM Length L Ch R = 1 ,877     ,766,766,766
BEGIN DESCRIPTION:
B19858
END DESCRIPTION:
XS GIS Cut Line= 3
      2381258.41     13686064.02      2379767.89     13685646.39
      2377766.18     13684983.95
#Sta/Elev= 30
  4286.9  346.48    4490  344.46  4602.8  333.73  4814.3  321.99  4964.6  314.91
  4986.2  312.66  4992.7  306.39  4993.7  305.89    5042  306.39  5043.2  315.51
  5048.6  316.54  5162.2  325.92  5504.8  328.69  5606.2  327.96  5667.8  327.13
  5846.6  327.57  6044.7  325.81  6325.7  329.03  6408.2  327.64  6536.2  327.43
  6688.6  329.28  6826.5  328.92  6943.9  334.54  7020.3  333.32  7323.8  334.23
  7565.4  338.03  7657.1  339.45    7786  339.72  7843.8  340.31  7943.3   340.8
#Mann= 20 ,-1 , 0
  4286.9     .07       0  4814.3      .1       0  4992.7     .05       0
    5042      .1       0  5162.2     .12       0  5504.8     .07       0
  5606.2     .12       0  5667.8     .05       0  5846.6     .07       0
  6325.7     .12       0  6408.2     .07       0  6536.2     .12       0
  6688.6     .12       0  6826.5     .07       0  7020.3     .12       0
  7323.8     .07       0  7565.4    .035       0  7657.1     .07       0
    7786     .12       0  7843.8     .07       0
Bank Sta=4992.7,5042
XS Rating Curve= 0 ,0
Exp/Cntr=0.3,0.1

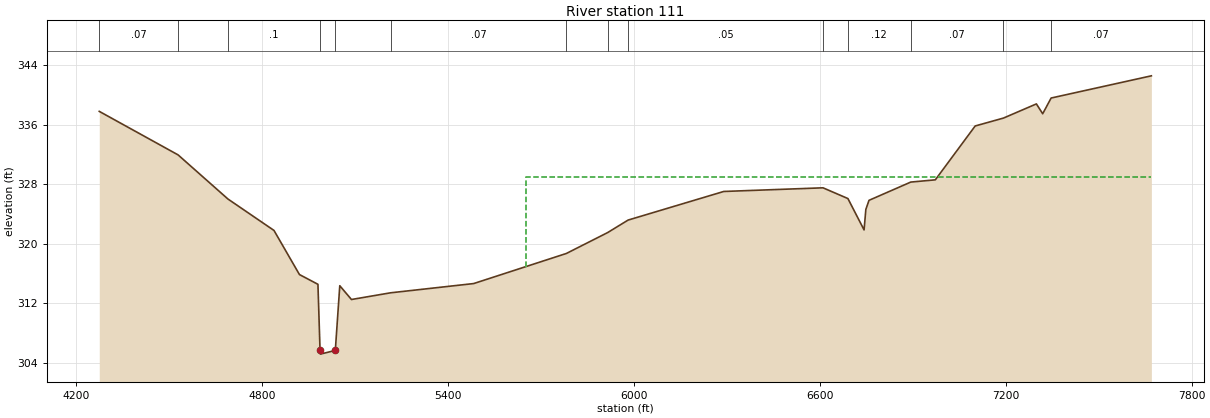
Type RM Length L Ch R = 1 ,111     ,0,0,0
BEGIN DESCRIPTION:
B19857
END DESCRIPTION:
XS GIS Cut Line= 4
      2381387.96     13685567.16      2380891.17     13685221.56
      2380243.13     13685019.95      2378170.88     13684609.82
#Sta/Elev= 30
  4273.7  337.77  4528.1  331.93    4689  326.01  4837.7  321.79  4919.9  315.87
  4979.6  314.56  4986.4  305.69  4987.4  305.19  5035.7  305.69  5050.1  314.37
  5087.8  312.52  5214.2  313.42  5482.3  314.66  5781.6   318.7  5914.7   321.5
  5980.8  323.18  6289.6  327.02    6610  327.51  6690.4  326.07  6742.6  321.86
  6748.3  324.61  6758.5  325.83  6893.3  328.28  6972.6  328.58  7101.3  335.81
  7192.6  336.87  7298.8  338.77  7319.2  337.45  7346.4  339.56    7670  342.54
#Mann= 14 ,-1 , 0
  4273.7     .07       0  4528.1     .12       0    4689      .1       0
  4986.4     .05       0  5035.7      .1       0  5214.2     .07       0
  5781.6     .05       0  5914.7     .07       0  5980.8     .05       0
    6610     .07       0  6690.4     .12       0  6893.3     .07       0
  7192.6    .035       0  7346.4     .07       0
#XS Ineff= 2 , 0
       0                    5650       0     329
Permanent Ineff=
       F       F
Bank Sta=4986.4,5035.7
XS Rating Curve= 0 ,0
Exp/Cntr=0.3,0.1

Chan Stop Cuts=-1
Use User Specified Reach Order=0
Composite Channel Slope=5