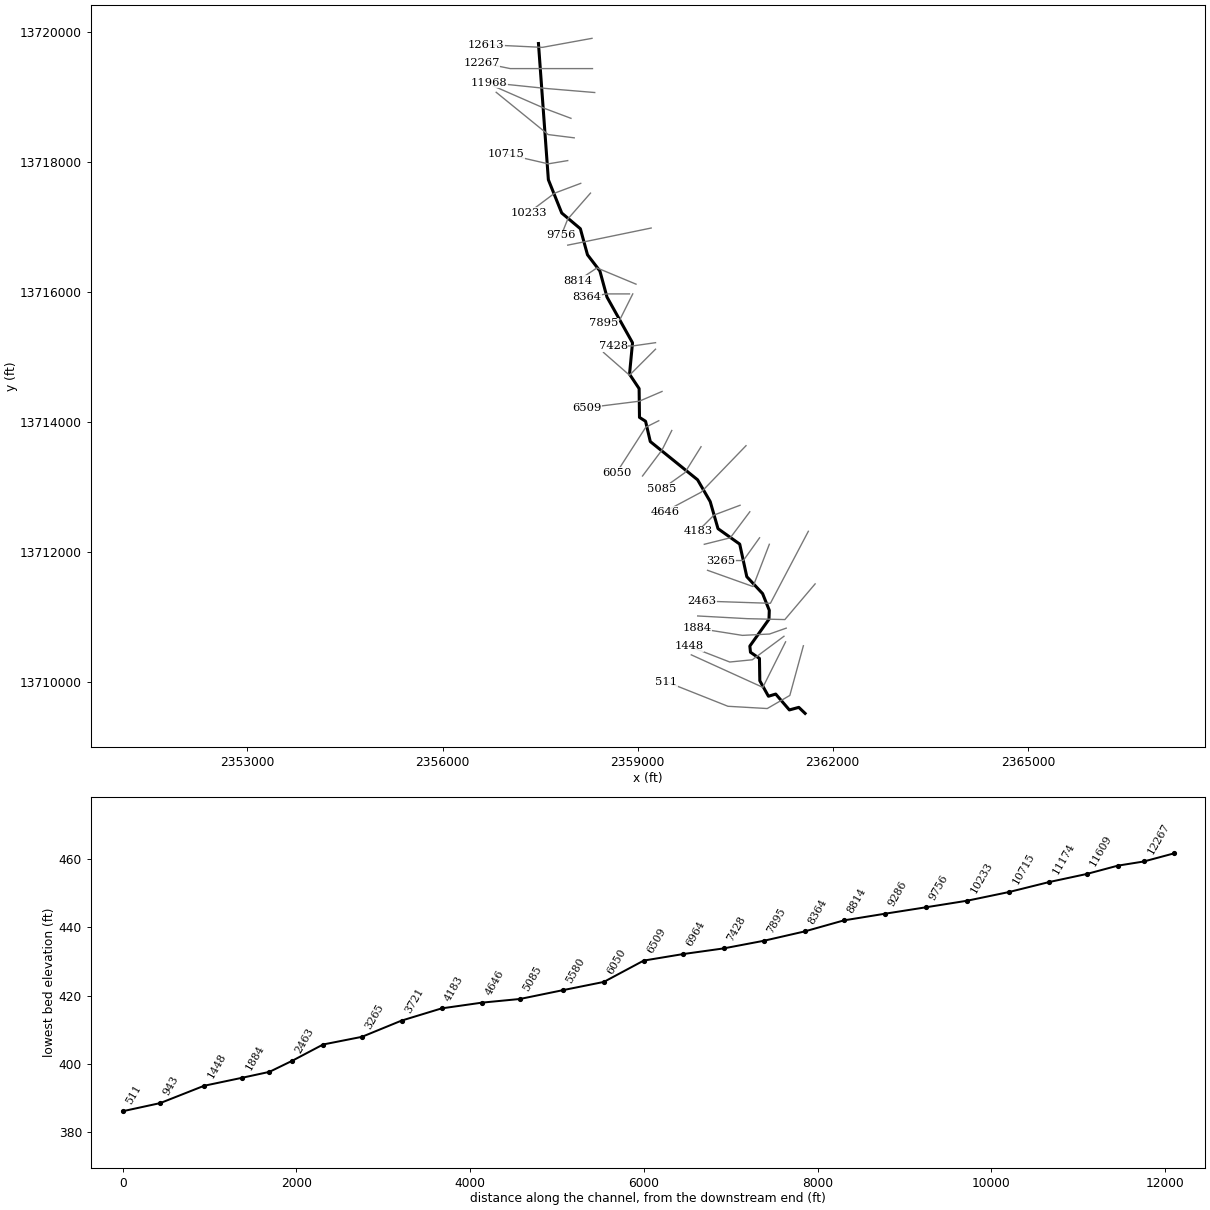
--- ONEIL TRIBUTARY 1.prj (project) ---

Proj Title=ONEIL TRIBUTARY 1 Base Level Engineering
Current Plan=p01
Default Exp/Contr=0.3,0.1
English Units
Geom File=g01
Flow File=f01
Plan File=p01
BEGIN DESCRIPTION:
ONEIL TRIBUTARY 1
END DESCRIPTION:

--- ONEIL TRIBUTARY 1.p01 (plan) ---

Plan Title=Multiple Run
Short Identifier=Multiple
Geom File=g01
Flow File=f01
Subcritical Flow
K Sum by GR= 0
Std Step Tol= 0.01
Critical Tol= 0.01
Num of Std Step Trials= 20
Max Error Tol= 0.3
Flow Tol Ratio= 0.001
Split Flow NTrial= 30
Split Flow Tol= 0.02
Split Flow Ratio= 0.02
Log Output Level= 0
Friction Slope Method= 1
Unsteady Friction Slope Method= 2
Unsteady Bridges Friction Slope Method= 1
Parabolic Critical Depth
Global Vel Dist=  1 , 1 , 1
Global Log Level= 0
CheckData=True
Encroach Param= -1, 0, 0, 0
BEGIN DESCRIPTION:
Multiple Run
END DESCRIPTION:

--- ONEIL TRIBUTARY 1.f01 (steady flow) ---

Flow Title=Multiple
Number of Profiles=7
Profile Names=10-year,25-year,50-year,1pct_min,100-year,1pct_plu,500-year
River Rch & RM= ONEIL TRIBUTARY ,Reach-1,12613
     812    1344    1837    1217    2428    4844    4200
River Rch & RM= ONEIL TRIBUTARY ,Reach-1,10715
    1090    1823    2508    1669    3330    6645    5823
Boundary for River Rch & Prof#=ONEIL TRIBUTARY ,Reach-1,1
Up Type=0
Dn Type=3
Dn Slope=0.005
Boundary for River Rch & Prof#=ONEIL TRIBUTARY ,Reach-1,2
Up Type=0
Dn Type=3
Dn Slope=0.005
Boundary for River Rch & Prof#=ONEIL TRIBUTARY ,Reach-1,3
Up Type=0
Dn Type=3
Dn Slope=0.005
Boundary for River Rch & Prof#=ONEIL TRIBUTARY ,Reach-1,4
Up Type=0
Dn Type=3
Dn Slope=0.005
Boundary for River Rch & Prof#=ONEIL TRIBUTARY ,Reach-1,5
Up Type=0
Dn Type=3
Dn Slope=0.005
Boundary for River Rch & Prof#=ONEIL TRIBUTARY ,Reach-1,6
Up Type=0
Dn Type=3
Dn Slope=0.005
Boundary for River Rch & Prof#=ONEIL TRIBUTARY ,Reach-1,7
Up Type=0
Dn Type=3
Dn Slope=0.005

--- ONEIL TRIBUTARY 1.g01 (geometry) ---

Geom Title=Existing Conditions

River Reach=ONEIL TRIBUTARY ,Reach-1
Reach XY= 30
      2357475.00     13719825.00      2357627.24     13717730.93
      2357832.86     13717218.83      2358119.18     13716977.31
      2358228.82     13716576.58      2358419.48     13716327.43
      2358528.62     13715926.50      2358921.25     13715223.45
      2358875.37     13714740.17      2359022.76     13714519.07
      2359028.48     13714076.26      2359121.89     13714016.68
      2359194.61     13713704.80      2359921.84     13713116.66
      2360115.85     13712781.73      2360235.76     13712365.32
      2360569.64     13712127.70      2360678.62     13711626.50
      2360921.49     13711366.52      2361024.50     13711109.78
      2361019.55     13710972.55      2360725.24     13710559.77
      2360735.30     13710464.90      2360873.02     13710369.33
      2360878.75     13710026.55      2361011.27     13709788.40
      2361123.35     13709821.84      2361333.04     13709577.90
      2361478.42     13709617.32      2361575.00     13709525.00

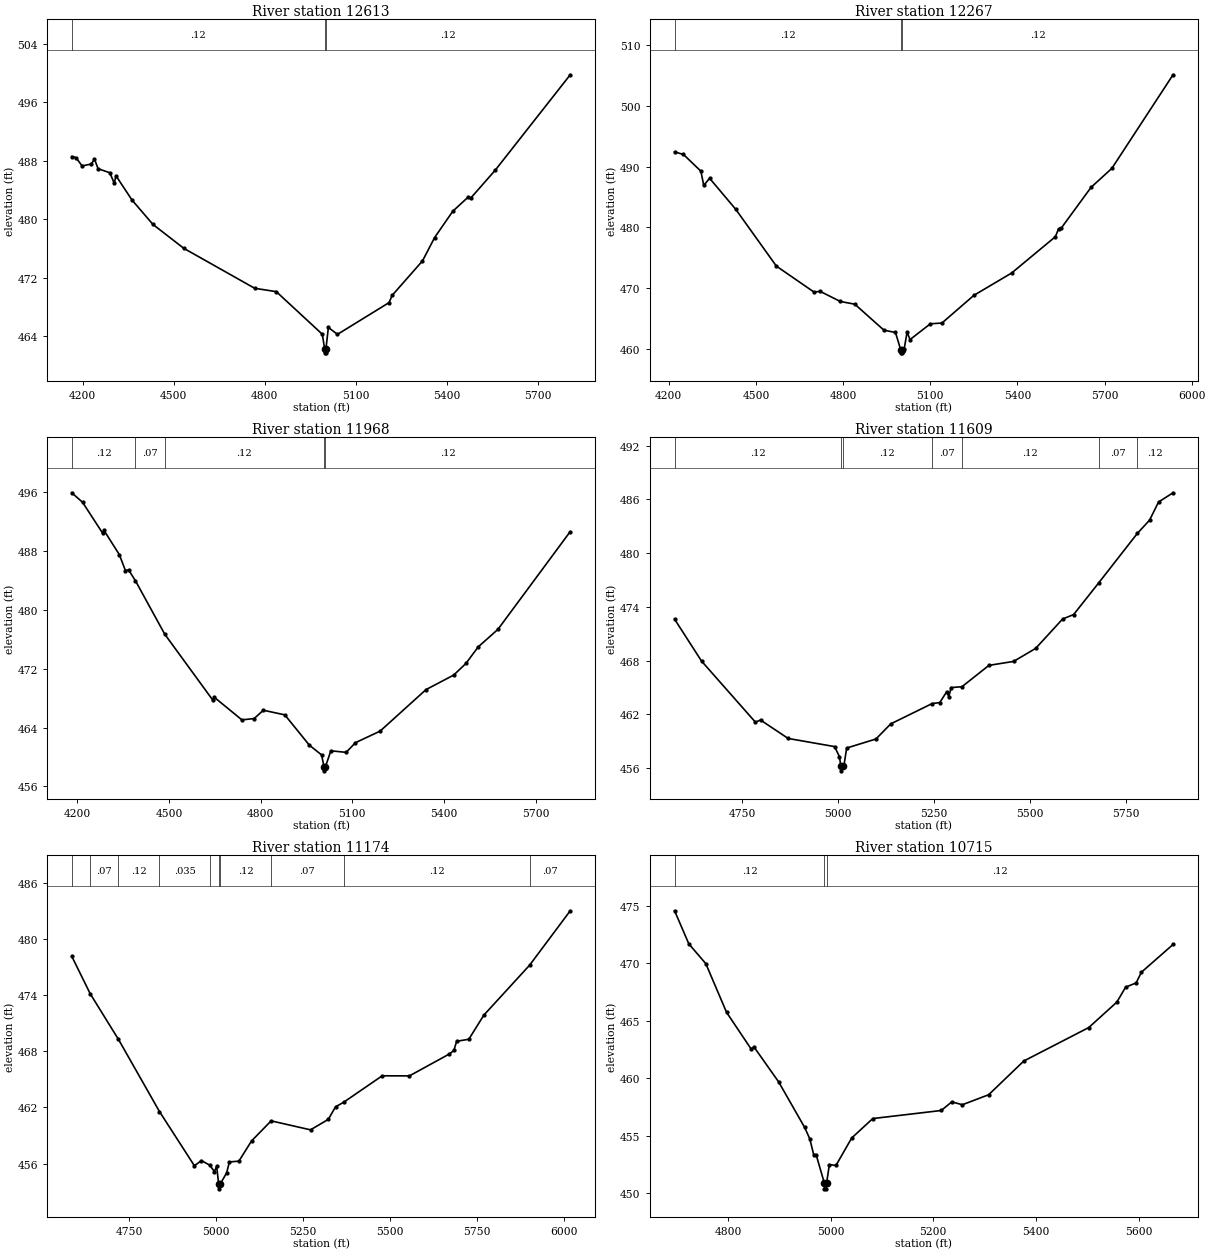
Type RM Length L Ch R = 1,12613,346,346,346
BEGIN DESCRIPTION:
ONEIL TRIBUTARY 1 25.0
END DESCRIPTION:
XS GIS Cut Line= 3
      2358298.50     13719904.93      2357534.65     13719766.05
      2356668.32     13719807.63
#Sta/Elev= 30
  4163.9  488.59  4177.6  488.45  4197.9  487.31  4228.4  487.57  4238.6  488.25
  4250.6  486.93  4289.4  486.37  4304.0  484.93  4309.7  485.96  4362.4  482.64
  4431.7  479.29  4533.4  476.02  4767.1  470.55  4838.3  470.09  4990.0  464.26
  4998.0  462.21  4998.2  461.71  5001.7  461.71  5002.0  462.21  5010.0  465.19
  5040.0  464.24  5210.2  468.59  5220.2  469.57  5320.4  474.30  5360.4  477.50
  5420.5  481.11  5470.5  483.02  5480.5  482.95  5560.6  486.74  5807.6  499.79
#Mann=3,-1,0
  4163.9    0.12       0  4998.0    0.05       0  5002.0    0.12       0
Bank Sta=4998,5002
Exp/Cntr=0.3,0.1

Type RM Length L Ch R = 1,12267,299,299,299
BEGIN DESCRIPTION:
B19908
END DESCRIPTION:
XS GIS Cut Line= 3
      2358305.53     13719439.66      2357041.60     13719439.66
      2356598.58     13719529.65
#Sta/Elev= 30
  4219.9  492.43  4250.4  492.01  4310.4  489.26  4320.4  486.90  4340.4  488.09
  4430.4  482.98  4570.4  473.62  4700.4  469.33  4720.4  469.48  4790.4  467.80
  4840.4  467.35  4940.4  463.08  4980.4  462.69  4998.4  459.84  4998.6  459.34
  5002.2  459.34  5002.5  459.84  5010.4  460.01  5020.4  462.77  5030.4  461.52
  5100.4  464.12  5140.4  464.25  5250.4  468.81  5380.4  472.49  5531.0  478.47
  5541.6  479.75  5551.8  479.93  5653.8  486.60  5725.3  489.72  5935.9  505.13
#Mann=3,-1,0
  4219.9    0.12       0  4998.4    0.05       0  5002.5    0.12       0
Bank Sta=4998.4,5002.5
Exp/Cntr=0.3,0.1

Type RM Length L Ch R = 1,11968,359,359,359
BEGIN DESCRIPTION:
ONEIL TRIBUTARY 1 24.0
END DESCRIPTION:
XS GIS Cut Line= 3
      2358340.17     13719071.61      2357590.21     13719134.10
      2356715.21     13719224.38
#Sta/Elev= 30
  4181.3  495.88  4216.6  494.59  4282.1  490.41  4287.1  490.76  4337.0  487.48
  4357.1  485.31  4367.1  485.42  4389.8  483.93  4485.8  476.67  4643.3  467.71
  4648.3  468.10  4738.4  465.04  4778.5  465.22  4808.6  466.35  4878.9  465.72
  4959.2  461.61  4999.4  460.28  5007.4  458.62  5007.7  458.12  5011.5  458.62
  5029.6  460.84  5079.8  460.63  5110.0  461.94  5190.8  463.51  5341.2  469.15
  5431.7  471.12  5471.9  472.70  5512.1  474.95  5576.7  477.33  5813.5  490.61
#Mann=5,-1,0
  4181.3    0.12       0  4389.8    0.07       0  4485.8    0.12       0
  5007.4    0.05       0  5011.5    0.12       0
Bank Sta=5007.4,5011.5
Exp/Cntr=0.3,0.1

Type RM Length L Ch R = 1,11609,435,435,435
BEGIN DESCRIPTION:
ONEIL TRIBUTARY 1 23.0
END DESCRIPTION:
XS GIS Cut Line= 3
      2357974.97     13718675.01      2357575.00     13718825.00
      2356774.98     13719175.01
#Sta/Elev= 30
  4573.3  472.62  4643.6  467.94  4784.2  461.11  4797.5  461.35  4869.6  459.29
  4990.7  458.38  5003.2  457.27  5007.3  456.17  5007.6  455.67  5011.5  456.17
  5014.9  456.20  5022.3  458.22  5098.7  459.23  5137.3  460.92  5245.3  463.19
  5265.2  463.30  5283.1  464.51  5288.5  463.97  5295.2  464.98  5323.0  465.07
  5393.4  467.46  5457.7  467.90  5515.4  469.36  5585.6  472.64  5614.4  473.14
  5679.6  476.67  5780.4  482.20  5812.5  483.69  5835.9  485.72  5873.7  486.75
#Mann=7,-1,0
  4573.3    0.12       0  5007.3    0.05       0  5011.5    0.12       0
  5245.3    0.07       0  5323.0    0.12       0  5679.6    0.07       0
  5780.4    0.12       0
Bank Sta=5007.3,5011.5
Exp/Cntr=0.3,0.1

Type RM Length L Ch R = 1,11174,459,459,459
BEGIN DESCRIPTION:
ONEIL TRIBUTARY 1 22.0
END DESCRIPTION:
XS GIS Cut Line= 3
      2358024.99     13718375.00      2357625.00     13718425.00
      2356824.98     13719075.01
#Sta/Elev= 30
  4585.0  478.16  4638.1  474.15  4719.2  469.28  4837.2  461.56  4937.7  455.76
  4957.9  456.31  4981.6  455.83  4995.3  455.14  5001.7  455.71  5007.6  453.79
  5007.8  453.29  5011.8  453.79  5030.5  455.00  5038.4  456.17  5065.7  456.25
  5102.3  458.42  5158.5  460.56  5271.8  459.60  5322.9  460.72  5343.7  462.06
  5366.7  462.54  5478.0  465.38  5556.3  465.37  5671.0  467.71  5684.1  468.09
  5692.1  469.07  5727.2  469.29  5770.4  471.87  5902.0  477.21  6018.9  483.03
#Mann=10,-1,0
  4585.0   0.035       0  4638.1    0.07       0  4719.2    0.12       0
  4837.2   0.035       0  4981.6    0.12       0  5007.6    0.05       0
  5011.8    0.12       0  5158.5    0.07       0  5366.7    0.12       0
  5902.0    0.07       0
Bank Sta=5007.6,5011.8
Exp/Cntr=0.3,0.1

Type RM Length L Ch R = 1,10715,482,482,482
BEGIN DESCRIPTION:
ONEIL TRIBUTARY 1 21.0
END DESCRIPTION:
XS GIS Cut Line= 3
      2357924.96     13718024.99      2357625.00     13717975.00
      2356974.98     13718125.01
#Sta/Elev= 30
  4695.9  474.55  4723.7  471.67  4756.7  469.96  4797.2  465.72  4845.4  462.51
  4850.5  462.72  4898.6  459.68  4949.3  455.72  4959.4  454.72  4967.0  453.34
  4972.1  453.29  4987.7  450.88  4988.0  450.38  4991.8  450.38  4992.1  450.88
  4997.5  452.49  5010.3  452.41  5041.0  454.80  5082.1  456.49  5215.5  457.19
  5236.0  457.94  5256.6  457.69  5307.9  458.56  5376.3  461.49  5502.9  464.40
  5557.6  466.61  5574.7  467.91  5595.2  468.28  5605.5  469.21  5667.1  471.62
#Mann=3,-1,0
  4695.9    0.12       0  4987.7    0.05       0  4992.1    0.12       0
Bank Sta=4987.7,4992.1
Exp/Cntr=0.3,0.1

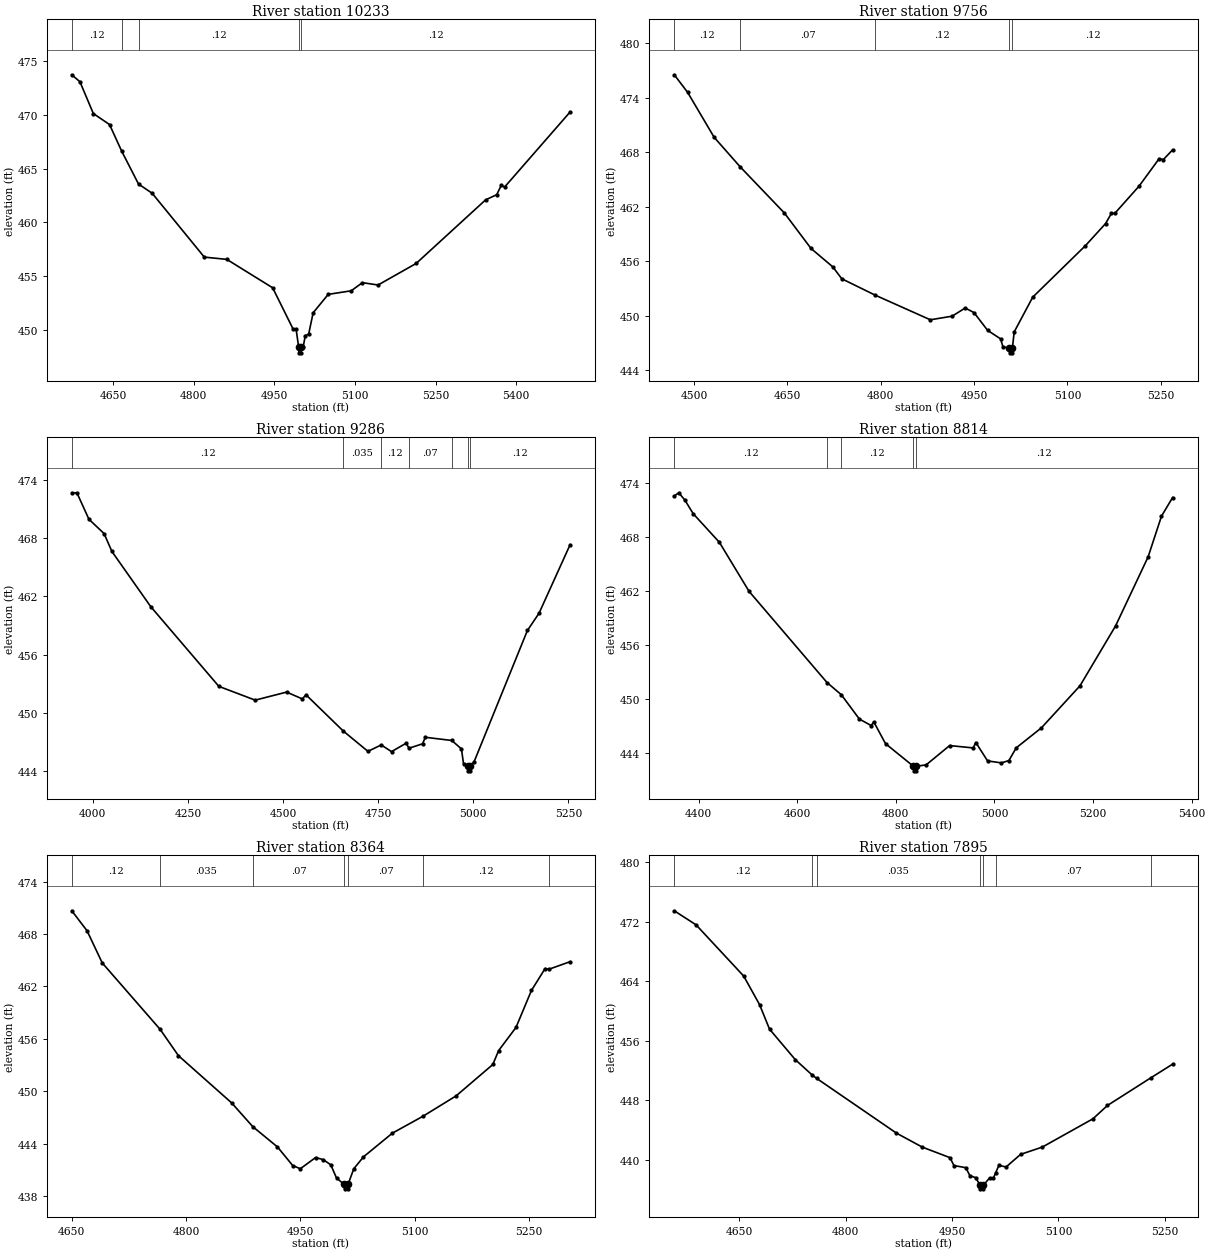
Type RM Length L Ch R = 1,10233,477,477,477
BEGIN DESCRIPTION:
ONEIL TRIBUTARY 1 20.0
END DESCRIPTION:
XS GIS Cut Line= 3
      2358125.03     13717675.01      2357725.00     13717525.00
      2357325.03     13717225.02
#Sta/Elev= 30
  4573.1  473.74  4588.3  473.09  4613.2  470.13  4643.4  469.10  4666.1  466.61
  4697.3  463.56  4722.7  462.70  4819.7  456.75  4861.5  456.54  4946.9  453.89
  4985.2  450.02  4990.5  450.03  4995.4  448.33  4995.7  447.83  4999.6  447.83
  5000.0  448.33  5003.5  448.33  5007.6  449.43  5013.9  449.58  5022.2  451.56
  5050.3  453.28  5093.0  453.61  5113.9  454.37  5143.0  454.15  5213.9  456.16
  5343.0  462.08  5363.9  462.57  5372.2  463.44  5378.5  463.28  5500.3  470.27
#Mann=5,-1,0
  4573.1    0.12       0  4666.1    0.07       0  4697.3    0.12       0
  4995.4    0.05       0  5000.0    0.12       0
Bank Sta=4995.4,5000
Exp/Cntr=0.3,0.1

Type RM Length L Ch R = 1,9756,470,470,470
BEGIN DESCRIPTION:
ONEIL TRIBUTARY 1 19.0
END DESCRIPTION:
XS GIS Cut Line= 3
      2358275.01     13717525.01      2357925.00     13717125.00
      2357824.99     13716874.98
#Sta/Elev= 30
  4468.2  476.52  4489.6  474.59  4532.3  469.63  4574.1  466.38  4645.2  461.29
  4687.9  457.39  4723.1  455.35  4737.3  454.05  4790.9  452.25  4879.7  449.53
  4914.8  449.93  4935.7  450.83  4949.9  450.32  4971.7  448.37  4992.6  447.43
  4996.4  446.55  5006.8  446.39  5007.1  445.89  5011.1  445.89  5011.5  446.39
  5014.5  448.20  5044.2  452.02  5129.0  457.70  5161.3  460.13  5170.7  461.25
  5176.1  461.25  5215.1  464.25  5247.4  467.28  5254.2  467.18  5269.0  468.25
#Mann=5,-1,0
  4468.2    0.12       0  4574.1    0.07       0  4790.9    0.12       0
  5006.8    0.05       0  5011.5    0.12       0
Bank Sta=5006.8,5011.5
Exp/Cntr=0.3,0.1

Type RM Length L Ch R = 1,9286,472,472,472
BEGIN DESCRIPTION:
ONEIL TRIBUTARY 1 18.0
END DESCRIPTION:
XS GIS Cut Line= 3
      2359208.28     13716988.27      2358175.00     13716775.00
      2357925.01     13716725.00
#Sta/Elev= 30
  3944.6  472.68  3958.2  472.67  3989.7  469.95  4029.6  468.47  4050.1  466.63
  4152.2  460.94  4331.3  452.72  4426.8  451.30  4509.5  452.13  4550.4  451.43
  4560.6  451.84  4658.2  448.12  4723.2  446.02  4758.1  446.68  4785.2  445.99
  4823.7  446.86  4831.1  446.34  4866.9  446.80  4874.0  447.47  4943.7  447.14
  4969.0  446.27  4974.5  444.73  4987.1  444.51  4987.5  444.01  4991.5  444.01
  4991.8  444.51  5002.2  444.94  5142.4  458.48  5173.0  460.26  5254.6  467.32
#Mann=7,-1,0
  3944.6    0.12       0  4658.2   0.035       0  4758.1    0.12       0
  4831.1    0.07       0  4943.7    0.12       0  4987.1    0.05       0
  4991.8    0.12       0
Bank Sta=4987.1,4991.8
Exp/Cntr=0.3,0.1

Type RM Length L Ch R = 1,8814,450,450,450
BEGIN DESCRIPTION:
ONEIL TRIBUTARY 1 17.0
END DESCRIPTION:
XS GIS Cut Line= 3
      2358974.96     13716125.02      2358375.00     13716375.00
      2358075.01     13716175.01
#Sta/Elev= 30
  4350.7  472.52  4359.9  472.87  4372.3  472.05  4389.1  470.55  4442.2  467.38
  4502.3  461.95  4660.5  451.84  4689.5  450.49  4726.0  447.80  4749.9  447.08
  4755.3  447.48  4779.1  445.07  4835.8  442.56  4836.2  442.06  4840.2  442.06
  4840.5  442.56  4861.4  442.72  4909.1  444.86  4956.8  444.60  4962.2  445.20
  4986.0  443.16  5014.2  442.94  5029.2  443.20  5044.2  444.61  5095.3  446.83
  5173.4  451.48  5245.5  458.11  5311.6  465.77  5338.7  470.28  5361.2  472.34
#Mann=5,-1,0
  4350.7    0.12       0  4660.5   0.035       0  4689.5    0.12       0
  4835.8    0.05       0  4840.5    0.12       0
Bank Sta=4835.8,4840.5
Exp/Cntr=0.3,0.1

Type RM Length L Ch R = 1,8364,469,469,469
BEGIN DESCRIPTION:
ONEIL TRIBUTARY 1 16.0
END DESCRIPTION:
XS GIS Cut Line= 3
      2358874.96     13715975.00      2358525.00     13715975.00
      2358225.00     13715925.00
#Sta/Elev= 30
  4650.0  470.67  4670.0  468.39  4690.0  464.70  4766.1  457.08  4790.0  454.08
  4860.0  448.66  4887.6  445.95  4920.0  443.63  4940.0  441.50  4950.0  441.13
  4970.0  442.41  4980.0  442.18  4990.0  441.58  4997.5  440.07  5007.7  439.33
  5008.0  438.83  5012.2  438.83  5012.6  439.33  5020.2  441.13  5032.9  442.49
  5070.9  445.21  5111.0  447.14  5154.6  449.48  5202.7  453.07  5210.3  454.66
  5233.1  457.31  5253.4  461.55  5271.2  464.04  5276.5  463.98  5304.1  464.84
#Mann=7,-1,0
  4650.0    0.12       0  4766.1   0.035       0  4887.6    0.07       0
  5007.7    0.05       0  5012.6    0.07       0  5111.0    0.12       0
  5276.5    0.07       0
Bank Sta=5007.7,5012.6
Exp/Cntr=0.3,0.1

Type RM Length L Ch R = 1,7895,467,467,467
BEGIN DESCRIPTION:
ONEIL TRIBUTARY 1 15.0
END DESCRIPTION:
XS GIS Cut Line= 3
      2358925.00     13715975.00      2358725.00     13715575.00
      2358474.96     13715524.99
#Sta/Elev= 30
  4558.6  473.45  4589.3  471.56  4656.4  464.68  4678.8  460.84  4692.8  457.55
  4729.1  453.45  4752.4  451.43  4759.2  450.93  4871.6  443.58  4908.0  441.70
  4947.1  440.28  4952.7  439.22  4969.5  438.93  4975.1  437.86  4983.4  437.59
  4989.4  436.59  4989.7  436.09  4993.9  436.09  4994.3  436.59  5003.0  437.56
  5008.4  437.56  5011.5  438.25  5016.0  439.24  5026.2  439.03  5046.6  440.72
  5077.2  441.70  5148.6  445.50  5169.0  447.29  5230.7  451.04  5260.8  452.84
#Mann=7,-1,0
  4558.6    0.12       0  4752.4    0.07       0  4759.2   0.035       0
  4989.4   0.035       0  4994.3   0.035       0  5011.5    0.07       0
  5230.7    0.12       0
Bank Sta=4989.4,4994.3
Exp/Cntr=0.3,0.1

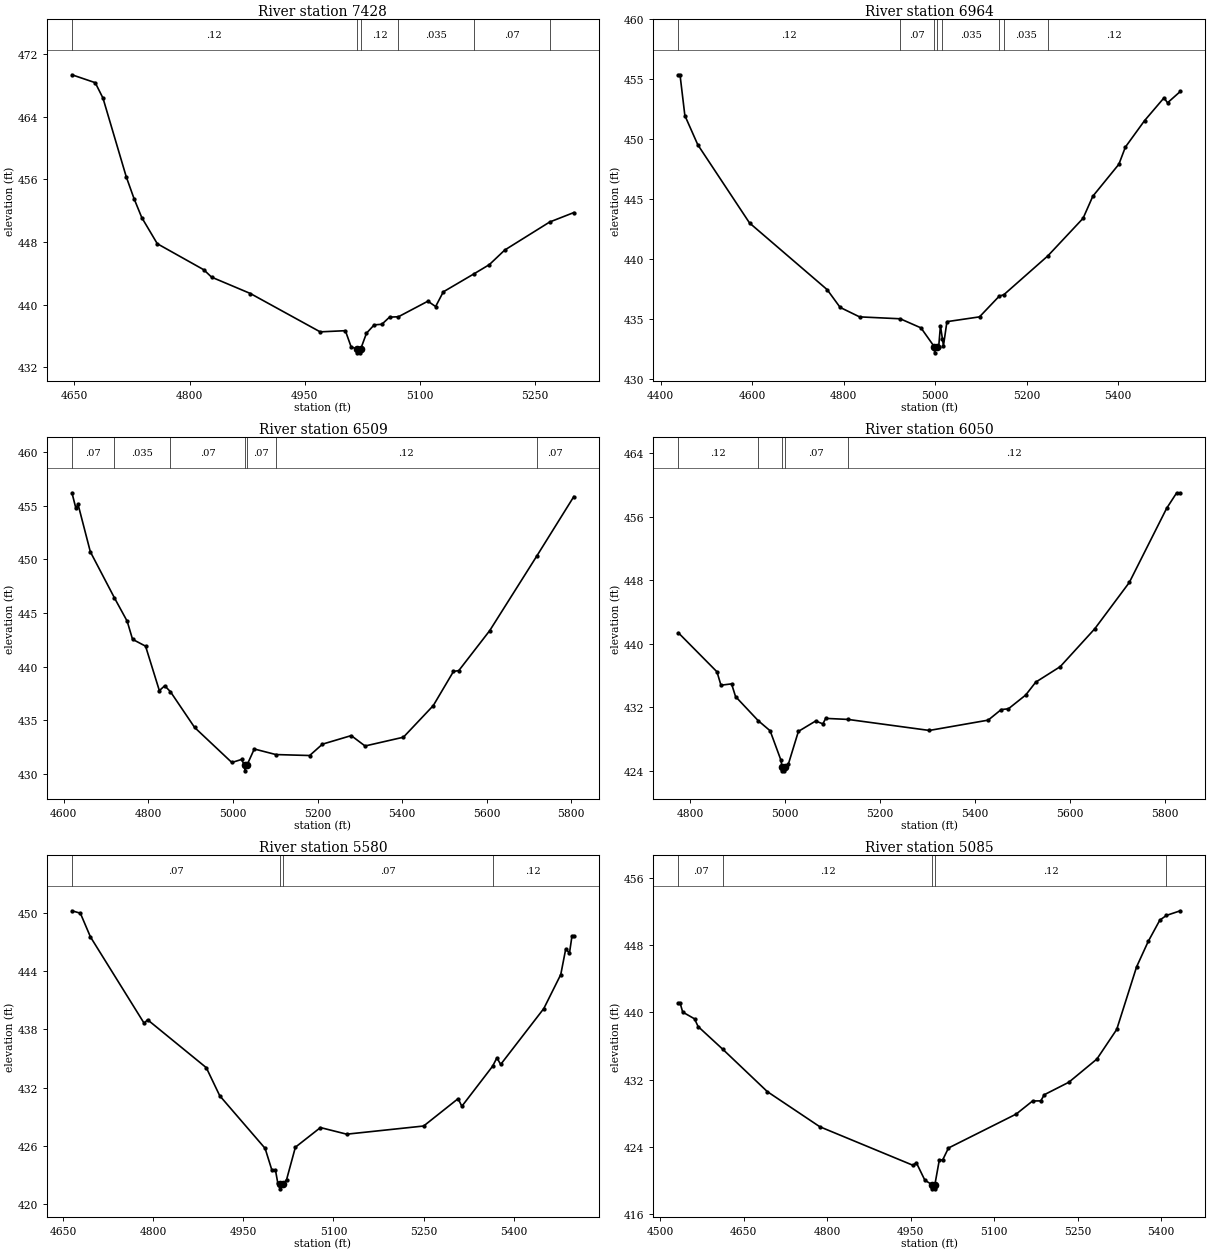
Type RM Length L Ch R = 1,7428,464,464,464
BEGIN DESCRIPTION:
ONEIL TRIBUTARY 1 14.0
END DESCRIPTION:
XS GIS Cut Line= 3
      2359274.96     13715224.99      2358925.00     13715175.00
      2358625.01     13715175.00
#Sta/Elev= 30
  4646.9  469.35  4677.2  468.34  4687.3  466.37  4717.6  456.32  4727.7  453.54
  4737.8  451.11  4758.0  447.77  4818.6  444.44  4828.7  443.50  4879.2  441.41
  4970.1  436.51  5002.9  436.66  5010.4  434.59  5017.9  434.33  5018.3  433.83
  5022.6  433.83  5022.9  434.33  5030.4  436.34  5040.4  437.40  5050.4  437.48
  5060.4  438.39  5072.0  438.44  5110.4  440.43  5120.4  439.74  5130.4  441.62
  5170.5  443.93  5190.4  445.10  5210.4  446.96  5268.9  450.54  5300.4  451.75
#Mann=6,-1,0
  4646.9    0.12       0  5017.9    0.05       0  5022.9    0.12       0
  5072.0   0.035       0  5170.5    0.07       0  5268.9    0.12       0
Bank Sta=5017.9,5022.9
Exp/Cntr=0.3,0.1

Type RM Length L Ch R = 1,6964,455,455,455
BEGIN DESCRIPTION:
ONEIL TRIBUTARY 1 13.0
END DESCRIPTION:
XS GIS Cut Line= 3
      2359274.99     13715124.99      2358875.00     13714725.00
      2358474.98     13715075.02
#Sta/Elev= 30
  4438.6  455.37  4442.1  455.37  4452.7  451.97  4481.0  449.53  4594.1  443.01
  4763.8  437.45  4792.1  435.97  4834.6  435.18  4923.5  435.02  4968.9  434.26
  4998.2  432.68  4998.6  432.18  5003.2  432.68  5007.6  432.68  5011.4  434.44
  5015.8  433.33  5018.0  432.77  5025.6  434.78  5096.8  435.18  5140.0  436.91
  5150.1  437.03  5246.3  440.27  5323.2  443.40  5344.5  445.24  5401.5  447.91
  5415.7  449.34  5457.5  451.54  5500.2  453.45  5507.8  453.03  5535.8  453.98
#Mann=8,-1,0
  4438.6    0.12       0  4923.5    0.07       0  4998.2    0.05       0
  5003.2    0.07       0  5015.8   0.035       0  5140.0    0.07       0
  5150.1   0.035       0  5246.3    0.12       0
Bank Sta=4998.2,5003.2
Exp/Cntr=0.3,0.1

Type RM Length L Ch R = 1,6509,459,459,459
BEGIN DESCRIPTION:
ONEIL TRIBUTARY 1 12.0
END DESCRIPTION:
XS GIS Cut Line= 3
      2359375.02     13714475.01      2359025.00     13714325.00
      2358225.03     13714225.00
#Sta/Elev= 30
  4619.2  456.22  4628.3  454.80  4633.7  455.13  4662.7  450.71  4719.8  446.40
  4749.8  444.23  4762.5  442.54  4793.3  441.90  4825.9  437.75  4838.6  438.20
  4852.1  437.65  4909.3  434.31  4997.3  431.04  5020.2  431.32  5027.7  430.76
  5028.1  430.26  5032.8  430.76  5050.4  432.30  5101.5  431.78  5181.4  431.69
  5211.6  432.75  5279.7  433.55  5312.4  432.58  5403.1  433.40  5473.7  436.35
  5521.5  439.54  5534.1  439.62  5607.2  443.35  5718.3  450.30  5806.2  455.87
#Mann=7,-1,0
  4619.2    0.07       0  4719.8   0.035       0  4852.1    0.07       0
  5027.7    0.05       0  5032.8    0.07       0  5101.5    0.12       0
  5718.3    0.07       0
Bank Sta=5027.7,5032.8
Exp/Cntr=0.3,0.1

Type RM Length L Ch R = 1,6050,470,470,470
BEGIN DESCRIPTION:
ONEIL TRIBUTARY 1 11.0
END DESCRIPTION:
XS GIS Cut Line= 3
      2359325.03     13714025.01      2359125.00     13713925.00
      2358675.00     13713225.00
#Sta/Elev= 30
  4775.8  441.39  4856.9  436.48  4865.3  434.79  4887.6  434.96  4896.0  433.36
  4943.5  430.33  4968.7  429.05  4991.1  425.40  4994.0  424.50  4994.4  424.00
  4998.8  424.00  4999.2  424.50  5007.0  424.83  5028.2  428.97  5064.5  430.28
  5079.7  429.92  5085.6  430.61  5132.4  430.48  5303.6  429.09  5427.4  430.39
  5454.8  431.72  5470.0  431.82  5506.3  433.55  5527.5  435.18  5579.0  437.13
  5651.6  441.90  5724.3  447.74  5802.9  457.09  5824.0  459.04  5831.6  458.99
#Mann=5,-1,0
  4775.8    0.12       0  4943.5    0.07       0  4994.0    0.05       0
  4999.2    0.07       0  5132.4    0.12       0
Bank Sta=4994,4999.2
Exp/Cntr=0.3,0.1

Type RM Length L Ch R = 1,5580,495,495,495
BEGIN DESCRIPTION:
ONEIL TRIBUTARY 1 10.0
END DESCRIPTION:
XS GIS Cut Line= 3
      2359525.01     13713875.02      2359375.00     13713575.00
      2359075.02     13713175.02
#Sta/Elev= 30
  4664.8  450.18  4678.8  449.93  4695.6  447.49  4785.0  438.61  4790.6  438.98
  4888.4  434.05  4910.8  431.16  4986.3  425.75  4997.4  423.55  5003.4  423.55
  5007.5  422.16  5011.2  422.09  5011.6  421.59  5016.4  422.09  5022.1  422.55
  5036.7  425.87  5078.4  427.89  5122.1  427.21  5250.2  428.05  5307.5  430.86
  5313.8  430.08  5365.0  434.20  5372.1  435.06  5378.4  434.38  5450.2  440.13
  5478.4  443.62  5486.7  446.26  5492.9  445.83  5497.1  447.59  5500.2  447.59
#Mann=4,-1,0
  4664.8    0.07       0  5011.2    0.05       0  5016.4    0.07       0
  5365.0    0.12       0
Bank Sta=5011.2,5016.4
Exp/Cntr=0.3,0.1

Type RM Length L Ch R = 1,5085,439,439,439
BEGIN DESCRIPTION:
ONEIL TRIBUTARY 1 9.0
END DESCRIPTION:
XS GIS Cut Line= 3
      2359975.01     13713625.02      2359725.00     13713225.00
      2359375.03     13712975.02
#Sta/Elev= 30
  4532.7  441.12  4535.7  441.12  4540.4  440.04  4561.6  439.24  4568.1  438.32
  4612.8  435.59  4692.5  430.57  4786.8  426.39  4954.3  421.80  4960.2  422.11
  4975.5  420.03  4988.2  419.50  4988.6  419.00  4993.1  419.00  4993.5  419.50
  5001.5  422.44  5007.5  422.44  5017.9  423.86  5139.6  427.90  5169.1  429.46
  5183.8  429.47  5190.0  430.20  5234.2  431.69  5284.6  434.45  5320.2  437.97
  5355.9  445.42  5376.8  448.45  5397.7  450.99  5409.6  451.55  5434.5  452.10
#Mann=5,-1,0
  4532.7    0.07       0  4612.8    0.12       0  4988.2    0.05       0
  4993.5    0.12       0  5409.6    0.07       0
Bank Sta=4988.2,4993.5
Exp/Cntr=0.3,0.1

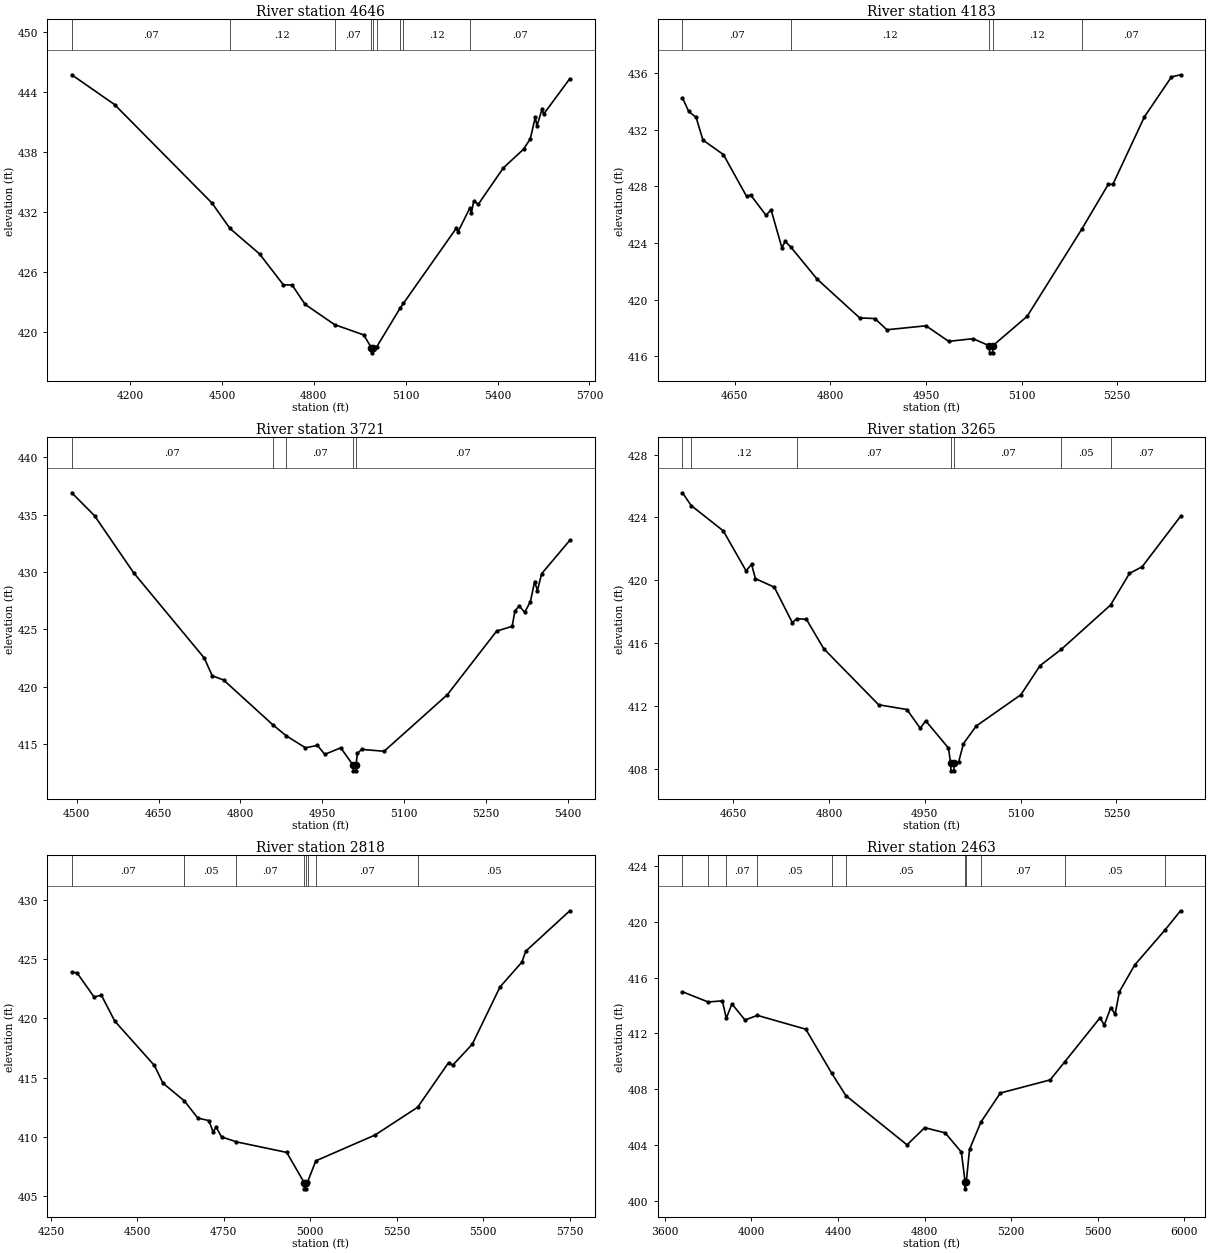
Type RM Length L Ch R = 1,4646,463,463,463
BEGIN DESCRIPTION:
ONEIL TRIBUTARY 1 8.0
END DESCRIPTION:
XS GIS Cut Line= 3
      2360666.60     13713641.05      2359975.00     13712925.00
      2359418.26     13712628.04
#Sta/Elev= 30
  4009.3  445.75  4149.1  442.77  4467.3  432.91  4525.9  430.37  4622.9  427.81
  4700.6  424.72  4728.9  424.71  4771.4  422.77  4867.9  420.74  4962.5  419.72
  4988.1  418.42  4988.5  417.92  4993.5  418.42  5005.6  418.54  5082.2  422.42
  5092.2  422.86  5265.1  430.39  5270.8  430.03  5309.0  432.39  5314.7  431.94
  5322.2  433.12  5336.7  432.78  5418.8  436.43  5484.7  438.30  5506.7  439.33
  5522.9  441.48  5528.6  440.63  5544.9  442.28  5550.6  441.82  5635.8  445.36
#Mann=9,-1,0
  4009.3    0.07       0  4525.9    0.12       0  4867.9    0.07       0
  4988.1    0.05       0  4993.5    0.07       0  5005.6    0.12       0
  5082.2    0.07       0  5092.2    0.12       0  5309.0    0.07       0
Bank Sta=4988.1,4993.5
Exp/Cntr=0.3,0.1

Type RM Length L Ch R = 1,4183,462,462,462
BEGIN DESCRIPTION:
ONEIL TRIBUTARY 1 7.0
END DESCRIPTION:
XS GIS Cut Line= 3
      2360575.02     13712725.01      2360175.00     13712575.00
      2359924.98     13712324.98
#Sta/Elev= 30
  4568.4  434.24  4578.2  433.28  4589.8  432.86  4600.5  431.26  4632.5  430.24
  4669.0  427.28  4675.2  427.39  4699.3  425.95  4707.3  426.34  4724.2  423.67
  4729.5  424.11  4738.2  423.71  4779.4  421.45  4846.1  418.71  4870.1  418.66
  4888.8  417.87  4950.2  418.15  4985.8  417.05  5023.9  417.24  5049.4  416.74
  5049.9  416.24  5054.5  416.24  5054.9  416.74  5108.8  418.82  5194.1  424.95
  5236.0  428.14  5243.1  428.13  5292.6  432.90  5335.0  435.72  5349.2  435.87
#Mann=5,-1,0
  4568.4    0.07       0  4738.2    0.12       0  5049.4    0.05       0
  5054.9    0.12       0  5194.1    0.07       0
Bank Sta=5049.4,5054.9
Exp/Cntr=0.3,0.1

Type RM Length L Ch R = 1,3721,456,456,456
BEGIN DESCRIPTION:
ONEIL TRIBUTARY 1 6.0
END DESCRIPTION:
XS GIS Cut Line= 3
      2360725.00     13712625.00      2360425.00     13712225.00
      2360025.01     13712125.00
#Sta/Elev= 30
  4491.1  436.92  4532.8  434.92  4604.6  429.93  4733.8  422.50  4748.4  420.95
  4769.2  420.58  4859.2  416.68  4884.0  415.71  4919.2  414.66  4941.1  414.87
  4954.6  414.09  4983.8  414.66  5006.4  413.15  5006.8  412.65  5011.4  412.65
  5011.9  413.15  5014.3  414.17  5022.0  414.52  5063.3  414.36  5179.2  419.30
  5269.4  424.85  5297.8  425.26  5302.9  426.60  5310.6  427.04  5320.9  426.49
  5331.3  427.43  5339.0  429.17  5344.1  428.39  5351.9  429.86  5403.4  432.77
#Mann=5,-1,0
  4491.1    0.07       0  4859.2    0.12       0  4884.0    0.07       0
  5006.4    0.05       0  5011.9    0.07       0
Bank Sta=5006.4,5011.9
Exp/Cntr=0.3,0.1

Type RM Length L Ch R = 1,3265,447,447,447
BEGIN DESCRIPTION:
ONEIL TRIBUTARY 1 5.0
END DESCRIPTION:
XS GIS Cut Line= 3
      2360875.02     13712225.02      2360625.00     13711875.00
      2360275.05     13711875.00
#Sta/Elev= 30
  4570.4  425.57  4584.0  424.76  4634.3  423.15  4670.0  420.61  4678.6  421.02
  4684.7  420.11  4714.2  419.57  4742.5  417.31  4749.4  417.57  4764.6  417.52
  4791.6  415.66  4877.7  412.09  4921.9  411.79  4942.8  410.60  4951.4  411.07
  4987.0  409.34  4990.4  408.39  4990.9  407.89  4995.5  407.89  4995.9  408.39
  5003.0  408.45  5010.5  409.62  5030.5  410.74  5100.5  412.73  5130.5  414.58
  5163.9  415.62  5240.9  418.43  5270.5  420.44  5290.5  420.87  5350.5  424.07
#Mann=7,-1,0
  4570.4    0.07       0  4584.0    0.12       0  4749.4    0.07       0
  4990.4    0.05       0  4995.9    0.07       0  5163.9    0.05       0
  5240.9    0.07       0
Bank Sta=4990.4,4995.9
Exp/Cntr=0.3,0.1

Type RM Length L Ch R = 1,2818,355,355,355
BEGIN DESCRIPTION:
ONEIL TRIBUTARY 1 4.0
END DESCRIPTION:
XS GIS Cut Line= 3
      2361025.01     13712125.02      2360775.00     13711475.00
      2360075.04     13711724.98
#Sta/Elev= 30
  4310.4  423.88  4325.4  423.86  4374.7  421.82  4396.1  421.96  4434.7  419.78
  4549.3  416.04  4574.0  414.55  4636.0  413.05  4674.7  411.61  4706.8  411.39
  4718.6  410.47  4728.3  410.82  4743.3  410.02  4786.6  409.60  4931.8  408.71
  4982.7  406.14  4983.1  405.64  4987.8  405.64  4988.2  406.14  4992.4  406.24
  5015.9  408.00  5187.4  410.18  5310.3  412.52  5399.7  416.28  5411.9  416.07
  5468.2  417.83  5548.4  422.66  5611.6  424.75  5622.7  425.67  5750.1  429.08
#Mann=8,-1,0
  4310.4    0.07       0  4636.0    0.05       0  4786.6    0.07       0
  4982.7    0.05       0  4988.2    0.07       0  4992.4    0.05       0
  5015.9    0.07       0  5310.3    0.05       0
Bank Sta=4982.7,4988.2
Exp/Cntr=0.3,0.1

Type RM Length L Ch R = 1,2463,263,263,263
BEGIN DESCRIPTION:
ONEIL TRIBUTARY 1 3.0
END DESCRIPTION:
XS GIS Cut Line= 3
      2361625.00     13712325.00      2361041.60     13711217.44
      2359992.99     13711252.16
#Sta/Elev= 30
  3681.5  414.98  3800.0  414.25  3865.9  414.33  3883.8  413.08  3910.0  414.11
  3970.4  412.96  4027.5  413.29  4251.2  412.30  4371.3  409.14  4436.2  407.55
  4718.9  404.02  4800.4  405.25  4895.2  404.88  4969.9  403.50  4987.2  401.37
  4987.6  400.87  4992.7  401.37  5007.8  403.70  5060.3  405.65  5150.0  407.73
  5380.2  408.67  5448.0  409.97  5610.2  413.11  5630.3  412.60  5660.3  413.85
  5680.3  413.38  5700.3  414.99  5770.4  416.89  5910.0  419.39  5982.5  420.78
#Mann=11,-1,0
  3681.5    0.07       0  3800.0   0.035       0  3883.8    0.07       0
  4027.5    0.05       0  4371.3    0.07       0  4436.2    0.05       0
  4987.2    0.05       0  4992.7    0.05       0  5060.3    0.07       0
  5448.0    0.05       0  5910.0    0.07       0
Bank Sta=4987.2,4992.7
Exp/Cntr=0.3,0.1

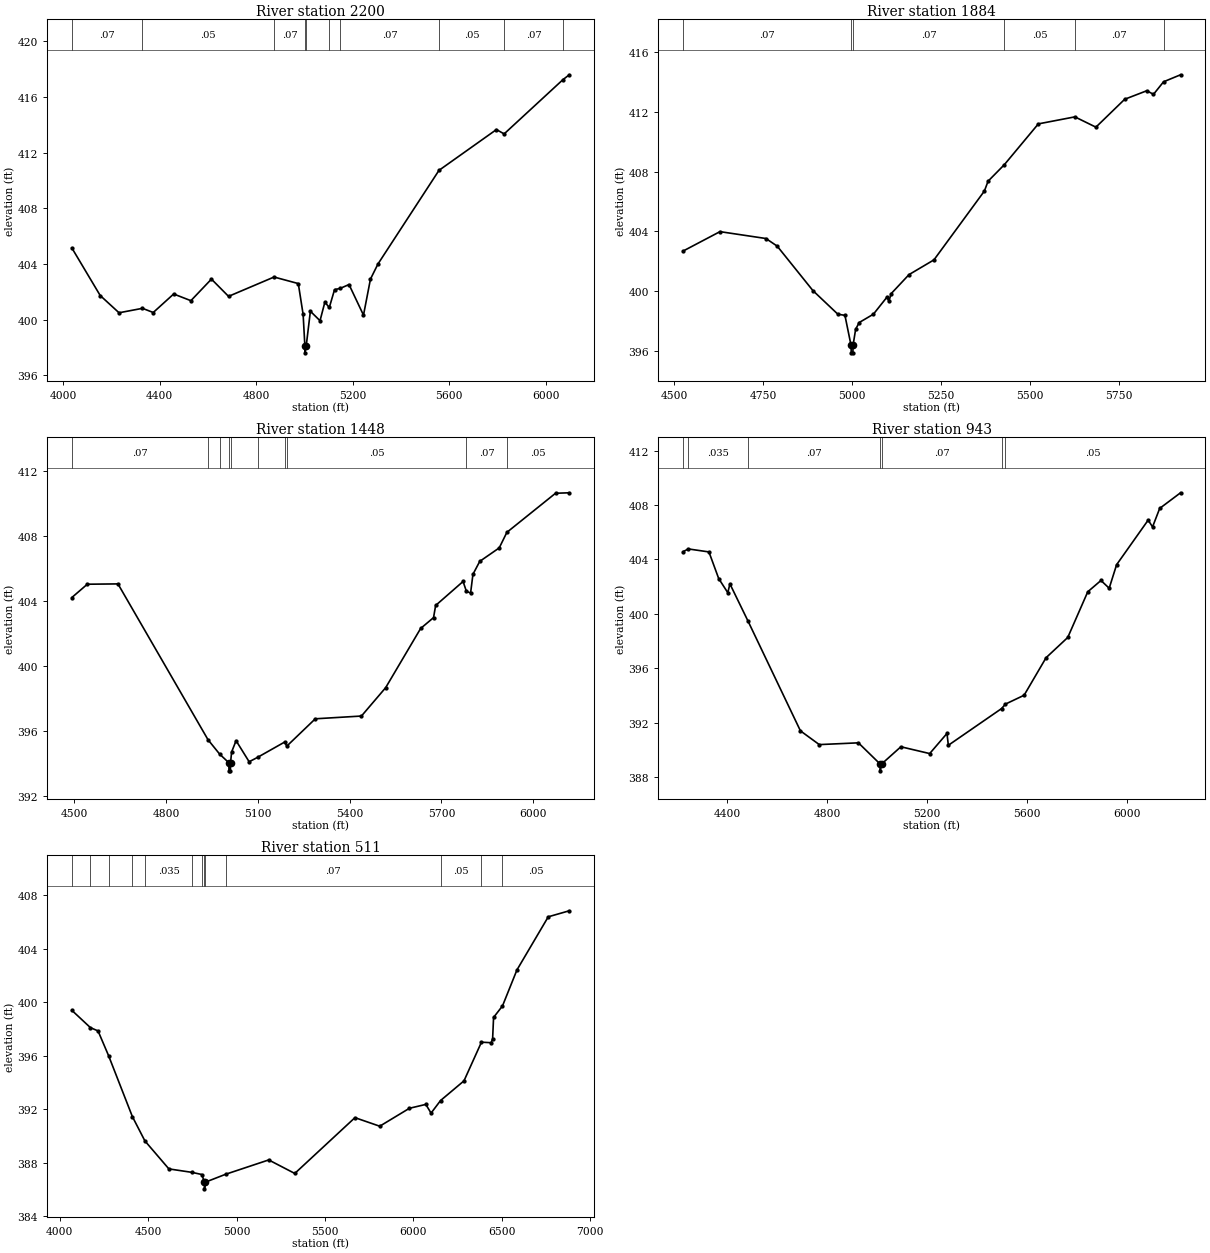
Type RM Length L Ch R = 1,2200,316,316,316
BEGIN DESCRIPTION:
B19907
END DESCRIPTION:
XS GIS Cut Line= 4
      2361729.09     13711516.04      2361263.82     13710967.44
      2360687.43     13710981.33      2359923.55     13711022.99
#Sta/Elev= 30
  4036.7  405.15  4154.2  401.73  4232.2  400.49  4329.3  400.81  4373.9  400.51
  4458.5  401.84  4529.9  401.36  4615.0  402.91  4685.9  401.67  4874.4  403.06
  4974.9  402.59  4994.9  400.37  5002.1  398.11  5002.6  397.61  5007.7  398.11
  5024.9  400.60  5064.9  399.92  5084.9  401.25  5103.4  400.87  5125.0  402.15
  5149.4  402.25  5185.0  402.52  5245.0  400.32  5273.8  402.91  5305.0  404.00
  5557.8  410.73  5795.7  413.66  5827.7  413.35  6071.3  417.25  6097.6  417.60
#Mann=10,-1,0
  4036.7    0.07       0  4329.3    0.05       0  4874.4    0.07       0
  5002.1    0.05       0  5007.7    0.07       0  5103.4    0.05       0
  5149.4    0.07       0  5557.8    0.05       0  5827.7    0.07       0
  6071.3    0.05       0
Bank Sta=5002.1,5007.7
Exp/Cntr=0.3,0.1

Type RM Length L Ch R = 1,1884,436,436,436
BEGIN DESCRIPTION:
B19906
END DESCRIPTION:
XS GIS Cut Line= 4
      2361284.69     13710835.51      2361027.71     13710745.22
      2360611.04     13710724.38      2359909.85     13710835.46
#Sta/Elev= 30
  4524.5  402.69  4628.2  403.99  4757.5  403.53  4789.2  403.02  4889.7  400.04
  4959.8  398.46  4979.8  398.38  4997.0  396.37  4997.5  395.87  5002.2  395.87
  5002.6  396.37  5009.9  397.45  5019.9  397.90  5059.9  398.46  5098.3  399.61
  5103.3  399.32  5110.0  399.84  5160.0  401.11  5230.3  402.10  5372.1  406.71
  5382.5  407.37  5428.4  408.48  5523.9  411.21  5626.7  411.68  5685.9  410.99
  5766.9  412.86  5829.0  413.43  5847.9  413.19  5876.2  414.03  5924.0  414.50
#Mann=6,-1,0
  4524.5    0.07       0  4997.0    0.05       0  5002.6    0.07       0
  5428.4    0.05       0  5626.7    0.07       0  5876.2    0.05       0
Bank Sta=4997,5002.6
Exp/Cntr=0.3,0.1

Type RM Length L Ch R = 1,1448,505,505,505
BEGIN DESCRIPTION:
B19905
END DESCRIPTION:
XS GIS Cut Line= 4
      2361249.95     13710710.51      2360763.82     13710349.38
      2360416.60     13710314.66      2359791.64     13710557.70
#Sta/Elev= 30
  4492.7  404.22  4543.2  405.04  4643.3  405.06  4937.5  395.45  4975.6  394.56
  5005.6  394.03  5006.0  393.53  5010.7  393.53  5011.2  394.03  5014.6  394.69
  5029.2  395.39  5071.9  394.09  5099.3  394.36  5188.3  395.31  5194.7  395.05
  5288.1  396.74  5438.8  396.91  5517.9  398.66  5632.1  402.31  5674.3  402.98
  5681.2  403.73  5770.8  405.21  5781.7  404.60  5795.4  404.50  5803.0  405.65
  5825.3  406.45  5888.9  407.28  5913.9  408.24  6072.8  410.65  6117.8  410.68
#Mann=10,-1,0
  4492.7    0.07       0  4937.5   0.035       0  4975.6    0.07       0
  5005.6    0.05       0  5011.2    0.07       0  5099.3    0.05       0
  5188.3   0.035       0  5194.7    0.05       0  5781.7    0.07       0
  5913.9    0.05       0
Bank Sta=5005.6,5011.2
Exp/Cntr=0.3,0.1

Type RM Length L Ch R = 1,943,432,432,432
BEGIN DESCRIPTION:
ONEIL TRIBUTARY 1 1.0
END DESCRIPTION:
XS GIS Cut Line= 3
      2361275.00     13710625.00      2360925.00     13709925.00
      2359825.03     13710424.99
#Sta/Elev= 30
  4223.7  404.57  4244.5  404.77  4327.1  404.55  4366.2  402.59  4402.6  401.55
  4411.0  402.20  4484.1  399.44  4693.3  391.39  4768.7  390.38  4925.3  390.51
  5012.3  388.95  5012.8  388.45  5018.0  388.95  5095.3  390.22  5210.6  389.72
  5279.8  391.20  5285.3  390.33  5498.3  393.03  5514.0  393.36  5588.5  394.01
  5676.4  396.77  5763.2  398.26  5843.3  401.62  5896.1  402.45  5929.0  401.88
  5958.7  403.61  6085.0  406.89  6102.6  406.39  6131.1  407.75  6214.6  408.90
#Mann=7,-1,0
  4223.7    0.07       0  4244.5   0.035       0  4484.1    0.07       0
  5012.3    0.05       0  5018.0    0.07       0  5498.3   0.035       0
  5514.0    0.05       0
Bank Sta=5012.3,5018
Exp/Cntr=0.3,0.1

Type RM Length L Ch R = 1,511,0,0,0
BEGIN DESCRIPTION:
B19904
END DESCRIPTION:
XS GIS Cut Line= 5
      2361548.54     13710564.63      2361340.21     13709800.77
      2360992.99     13709599.38      2360388.82     13709634.10
      2359444.37     13710009.11
#Sta/Elev= 30
  4068.4  399.40  4173.2  398.11  4216.6  397.86  4276.0  396.02  4410.8  391.46
  4481.8  389.64  4617.4  387.55  4748.8  387.29  4803.8  387.13  4818.4  386.56
  4818.9  386.06  4824.1  386.56  4938.7  387.15  5182.3  388.22  5329.7  387.21
  5670.2  391.38  5810.4  390.74  5978.4  392.08  6071.1  392.37  6100.8  391.72
  6154.6  392.66  6287.1  394.13  6385.9  397.02  6441.1  396.98  6449.1  397.28
  6454.5  398.87  6505.0  399.73  6586.8  402.42  6763.9  406.39  6882.9  406.84
#Mann=13,-1,0
  4068.4   0.035       0  4173.2    0.05       0  4276.0   0.035       0
  4410.8    0.07       0  4481.8   0.035       0  4748.8    0.07       0
  4803.8   0.035       0  4818.4    0.05       0  4824.1   0.035       0
  4938.7    0.07       0  6154.6    0.05       0  6385.9   0.035       0
  6505.0    0.05       0
Bank Sta=4818.4,4824.1
Exp/Cntr=0.3,0.1

Chan Stop Cuts=-1