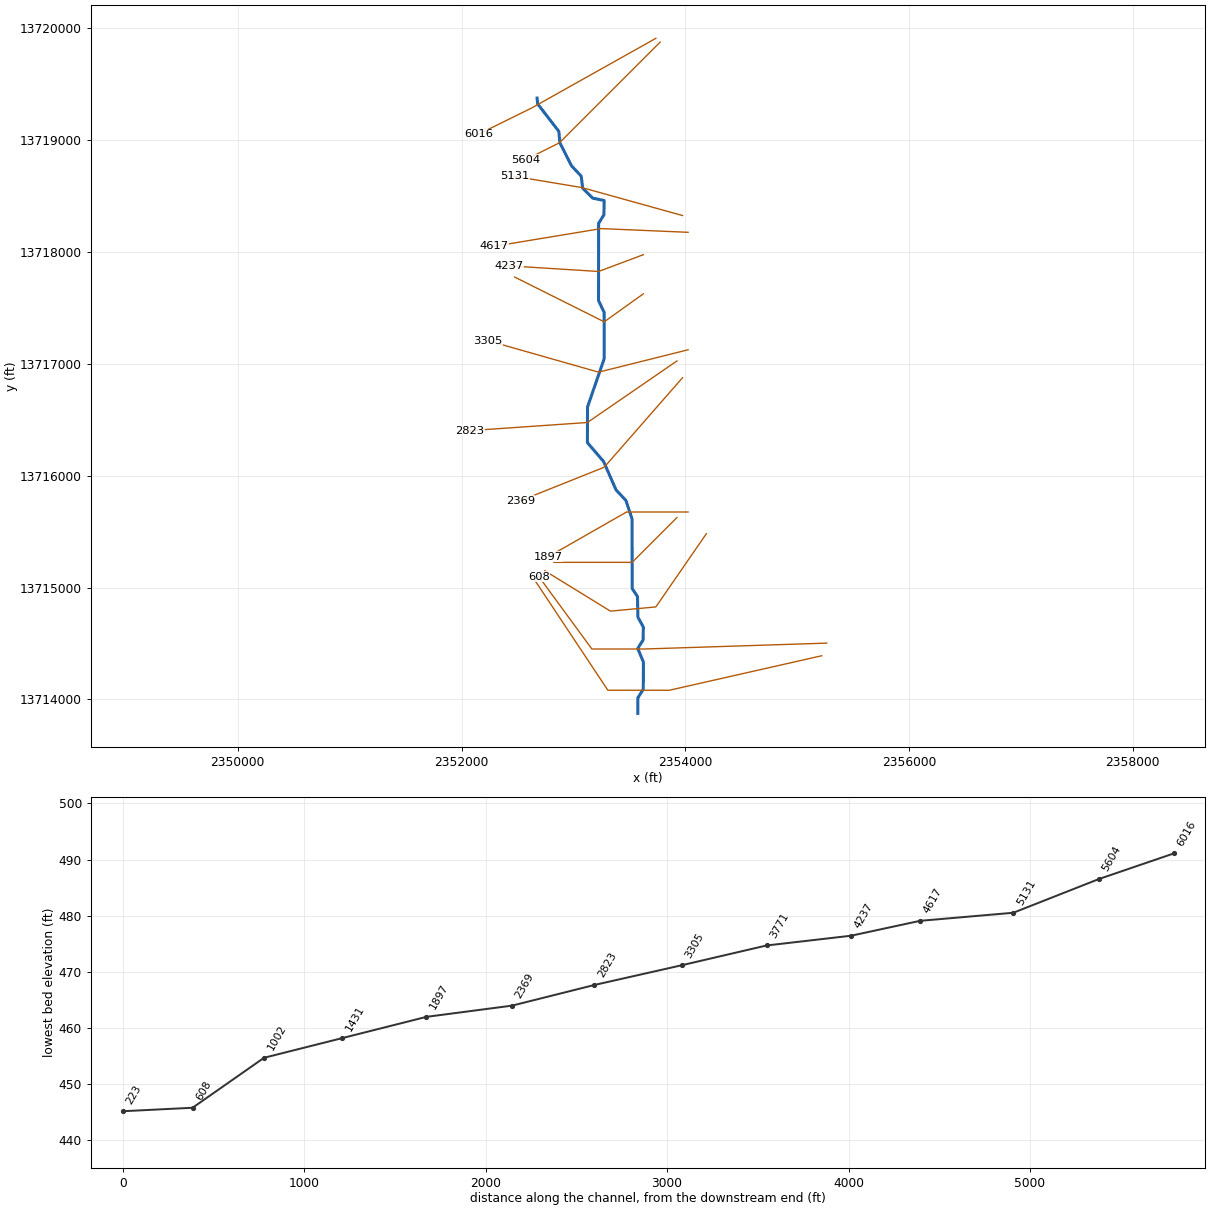
--- ONEIL TRIBUTARY 2.prj (project) ---

Proj Title=ONEIL TRIBUTARY 2 Base Level Engineering
Current Plan=p01
Default Exp/Contr=0.3,0.1
English Units
Geom File=g01
Flow File=f01
Plan File=p01
BEGIN DESCRIPTION:
ONEIL TRIBUTARY 2
END DESCRIPTION:

--- ONEIL TRIBUTARY 2.p01 (plan) ---

Plan Title=Multiple Run
Short Identifier=Multiple
Geom File=g01
Flow File=f01
Subcritical Flow
K Sum by GR= 0
Std Step Tol= 0.01
Critical Tol= 0.01
Num of Std Step Trials= 20
Max Error Tol= 0.3
Flow Tol Ratio= 0.001
Split Flow NTrial= 30
Split Flow Tol= 0.02
Split Flow Ratio= 0.02
Log Output Level= 0
Friction Slope Method= 1
Unsteady Friction Slope Method= 2
Unsteady Bridges Friction Slope Method= 1
Parabolic Critical Depth
Global Vel Dist=  1 , 1 , 1
Global Log Level= 0
CheckData=True
Encroach Param= -1, 0, 0, 0
BEGIN DESCRIPTION:
Multiple Run
END DESCRIPTION:

--- ONEIL TRIBUTARY 2.f01 (steady flow) ---

Flow Title=Multiple
Number of Profiles=7
Profile Names=10-year,25-year,50-year,1pct_min,100-year,1pct_plu,500-year
River Rch & RM= ONEIL TRIBUTARY ,Reach-1,6016
     763    1256    1710    1129    2252    4493    3868
River Rch & RM= ONEIL TRIBUTARY ,Reach-1,4617
     878    1452    1983    1311    2615    5218    4509
Boundary for River Rch & Prof#=ONEIL TRIBUTARY ,Reach-1,1
Up Type=0
Dn Type=3
Dn Slope=0.005
Boundary for River Rch & Prof#=ONEIL TRIBUTARY ,Reach-1,2
Up Type=0
Dn Type=3
Dn Slope=0.005
Boundary for River Rch & Prof#=ONEIL TRIBUTARY ,Reach-1,3
Up Type=0
Dn Type=3
Dn Slope=0.005
Boundary for River Rch & Prof#=ONEIL TRIBUTARY ,Reach-1,4
Up Type=0
Dn Type=3
Dn Slope=0.005
Boundary for River Rch & Prof#=ONEIL TRIBUTARY ,Reach-1,5
Up Type=0
Dn Type=3
Dn Slope=0.005
Boundary for River Rch & Prof#=ONEIL TRIBUTARY ,Reach-1,6
Up Type=0
Dn Type=3
Dn Slope=0.005
Boundary for River Rch & Prof#=ONEIL TRIBUTARY ,Reach-1,7
Up Type=0
Dn Type=3
Dn Slope=0.005

--- ONEIL TRIBUTARY 2.g01 (geometry) ---

Geom Title=Existing Conditions

River Reach=ONEIL TRIBUTARY ,Reach-1
Reach XY= 30
      2352675.00     13719375.00      2352680.33     13719322.49
      2352869.46     13719077.42      2352878.83     13718976.59
      2352983.16     13718768.95      2353069.46     13718677.42
      2353082.86     13718568.81      2353172.62     13718480.54
      2353274.46     13718459.41      2353272.75     13718330.95
      2353225.07     13718254.97      2353224.55     13717564.81
      2353274.48     13717459.78      2353274.93     13717045.03
      2353126.22     13716614.50      2353124.96     13716294.98
      2353269.17     13716127.30      2353380.85     13715872.71
      2353469.46     13715777.42      2353523.78     13715614.50
      2353525.52     13714990.22      2353572.74     13714919.06
      2353576.22     13714735.51      2353625.39     13714645.13
      2353622.72     13714530.93      2353574.72     13714454.82
      2353625.45     13714335.19      2353624.48     13714090.22
      2353576.17     13714014.52      2353575.00     13713875.00

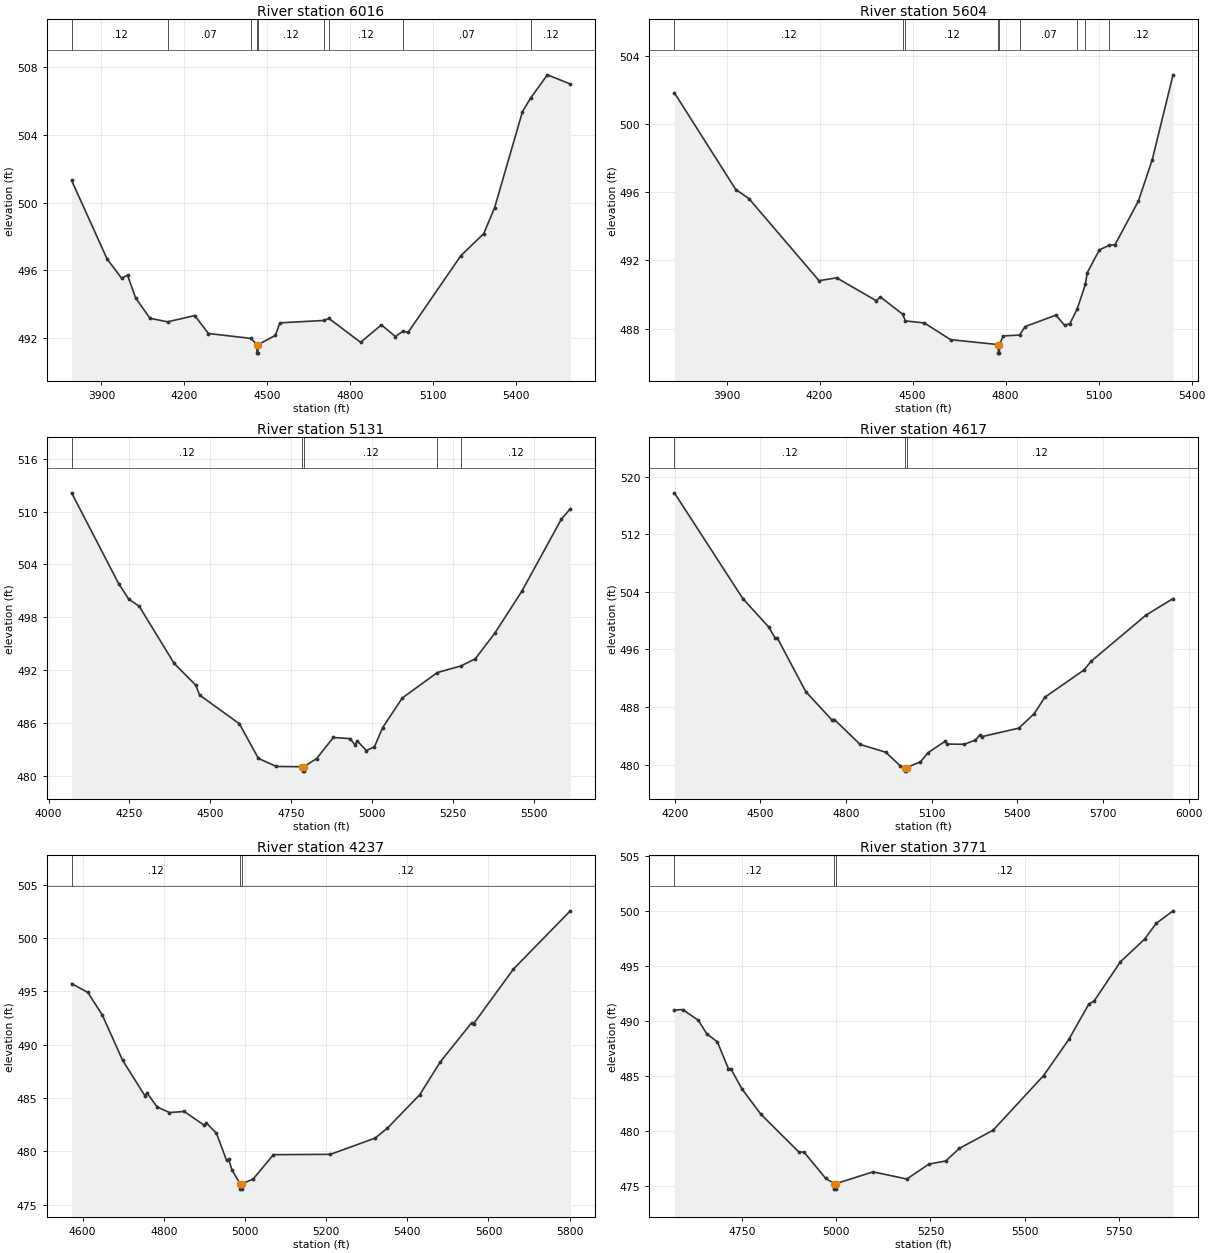
Type RM Length L Ch R = 1,6016,412,412,412
BEGIN DESCRIPTION:
B19912
END DESCRIPTION:
XS GIS Cut Line= 3
      2353736.93     13719908.85      2352623.26     13719284.29
      2352149.64     13719051.24
#Sta/Elev= 30
  3792.1  501.32  3920.4  496.68  3972.9  495.54  3994.6  495.71  4023.6  494.38
  4075.6  493.17  4139.4  492.96  4237.6  493.33  4287.3  492.27  4441.4  491.98
  4462.7  491.61  4463.0  491.11  4466.5  491.11  4466.7  491.61  4529.8  492.16
  4545.7  492.90  4704.0  493.04  4723.5  493.16  4837.9  491.75  4913.2  492.78
  4963.8  492.09  4990.7  492.40  5009.6  492.33  5200.7  496.87  5283.4  498.17
  5322.8  499.70  5423.8  505.39  5453.8  506.20  5513.7  507.56  5596.8  507.02
#Mann=9,-1,0
  3792.1    0.12       0  4139.4    0.07       0  4441.4    0.12       0
  4462.7    0.05       0  4466.7    0.12       0  4704.0    0.07       0
  4723.5    0.12       0  4990.7    0.07       0  5453.8    0.12       0
Bank Sta=4462.7,4466.7
Exp/Cntr=0.3,0.1

Type RM Length L Ch R = 1,5604,473,473,473
BEGIN DESCRIPTION:
ONEIL TRIBUTARY 2 10.0
END DESCRIPTION:
XS GIS Cut Line= 3
      2353775.01     13719875.01      2352875.00     13718975.00
      2352575.02     13718825.01
#Sta/Elev= 30
  3731.8  501.84  3929.8  496.16  3972.2  495.63  4198.5  490.81  4255.1  490.98
  4382.4  489.64  4396.5  489.85  4467.8  488.85  4477.0  488.45  4537.9  488.33
  4622.8  487.35  4776.3  487.06  4776.6  486.56  4780.1  486.56  4780.3  487.06
  4792.5  487.57  4844.9  487.62  4863.2  488.12  4962.2  488.79  4990.5  488.19
  5007.4  488.29  5031.2  489.17  5057.1  490.59  5063.3  491.28  5102.4  492.62
  5133.1  492.88  5152.7  492.92  5228.2  495.48  5272.9  497.91  5340.0  502.89
#Mann=9,-1,0
  3731.8    0.12       0  4467.8    0.07       0  4477.0    0.12       0
  4776.3    0.05       0  4780.3    0.12       0  4844.9    0.07       0
  5031.2    0.12       0  5057.1    0.07       0  5133.1    0.12       0
Bank Sta=4776.3,4780.3
Exp/Cntr=0.3,0.1

Type RM Length L Ch R = 1,5131,514,514,514
BEGIN DESCRIPTION:
ONEIL TRIBUTARY 2 9.0
END DESCRIPTION:
XS GIS Cut Line= 3
      2353975.02     13718324.99      2353075.00     13718575.00
      2352474.97     13718675.00
#Sta/Elev= 30
  4071.1  512.12  4216.4  501.83  4247.6  500.07  4280.3  499.24  4388.2  492.77
  4455.1  490.29  4467.1  489.17  4590.1  485.91  4648.7  481.99  4704.2  481.07
  4785.2  481.04  4785.5  480.54  4789.0  480.54  4789.2  481.04  4828.8  481.96
  4880.7  484.36  4932.5  484.23  4948.6  483.47  4953.8  483.99  4982.9  482.88
  5007.7  483.30  5033.1  485.48  5093.9  488.84  5202.1  491.72  5275.5  492.48
  5319.5  493.28  5380.3  496.21  5463.9  500.97  5585.6  509.12  5613.5  510.31
#Mann=5,-1,0
  4071.1    0.12       0  4785.2    0.05       0  4789.2    0.12       0
  5202.1    0.07       0  5275.5    0.12       0
Bank Sta=4785.2,4789.2
Exp/Cntr=0.3,0.1

Type RM Length L Ch R = 1,4617,380,380,380
BEGIN DESCRIPTION:
ONEIL TRIBUTARY 2 8.0
END DESCRIPTION:
XS GIS Cut Line= 3
      2354025.03     13718175.00      2353247.83     13718208.23
      2352292.12     13718050.20
#Sta/Elev= 30
  4198.7  517.76  4439.0  503.04  4529.0  499.13  4551.9  497.59  4559.1  497.61
  4659.2  490.13  4749.2  486.27  4759.2  486.27  4849.3  482.81  4939.4  481.72
  4989.6  479.84  5007.8  479.60  5008.1  479.10  5011.7  479.10  5012.0  479.60
  5060.6  480.39  5087.1  481.66  5148.2  483.28  5153.3  482.86  5214.3  482.83
  5253.1  483.41  5270.3  484.18  5275.4  483.89  5405.2  485.07  5458.6  487.06
  5496.4  489.37  5633.2  493.14  5658.6  494.37  5851.2  500.79  5945.3  503.07
#Mann=3,-1,0
  4198.7    0.12       0  5007.8    0.05       0  5012.0    0.12       0
Bank Sta=5007.8,5012
Exp/Cntr=0.3,0.1

Type RM Length L Ch R = 1,4237,466,466,466
BEGIN DESCRIPTION:
ONEIL TRIBUTARY 2 7.0
END DESCRIPTION:
XS GIS Cut Line= 3
      2353624.99     13717975.00      2353225.00     13717825.00
      2352424.95     13717875.00
#Sta/Elev= 30
  4572.8  495.72  4612.8  494.89  4648.4  492.78  4698.3  488.54  4753.5  485.20
  4758.8  485.46  4783.7  484.15  4814.0  483.63  4850.5  483.73  4899.4  482.44
  4904.8  482.65  4929.7  481.69  4954.6  479.15  4959.9  479.24  4967.9  478.25
  4988.0  476.95  4988.3  476.45  4992.0  476.45  4992.3  476.95  5020.0  477.39
  5070.1  479.68  5210.4  479.71  5320.6  481.23  5350.7  482.16  5430.8  485.31
  5480.9  488.36  5558.6  492.05  5563.6  491.97  5661.3  497.07  5801.6  502.54
#Mann=3,-1,0
  4572.8    0.12       0  4988.0    0.05       0  4992.3    0.12       0
Bank Sta=4988,4992.3
Exp/Cntr=0.3,0.1

Type RM Length L Ch R = 1,3771,466,466,466
BEGIN DESCRIPTION:
ONEIL TRIBUTARY 2 6.0
END DESCRIPTION:
XS GIS Cut Line= 3
      2353625.00     13717625.00      2353275.00     13717375.00
      2352475.04     13717774.98
#Sta/Elev= 30
  4570.0  491.00  4592.1  491.04  4633.9  490.06  4656.0  488.84  4684.3  488.10
  4713.8  485.64  4719.9  485.67  4749.4  483.83  4799.8  481.52  4900.6  478.09
  4914.1  478.09  4971.8  475.69  4994.9  475.21  4995.2  474.71  4998.9  474.71
  4999.2  475.21  5097.9  476.28  5187.4  475.63  5246.1  476.99  5290.8  477.27
  5327.1  478.42  5416.6  480.07  5550.7  485.04  5617.8  488.33  5670.9  491.55
  5684.9  491.82  5754.8  495.39  5819.1  497.45  5849.8  498.88  5894.5  500.02
#Mann=3,-1,0
  4570.0    0.12       0  4994.9    0.05       0  4999.2    0.12       0
Bank Sta=4994.9,4999.2
Exp/Cntr=0.3,0.1

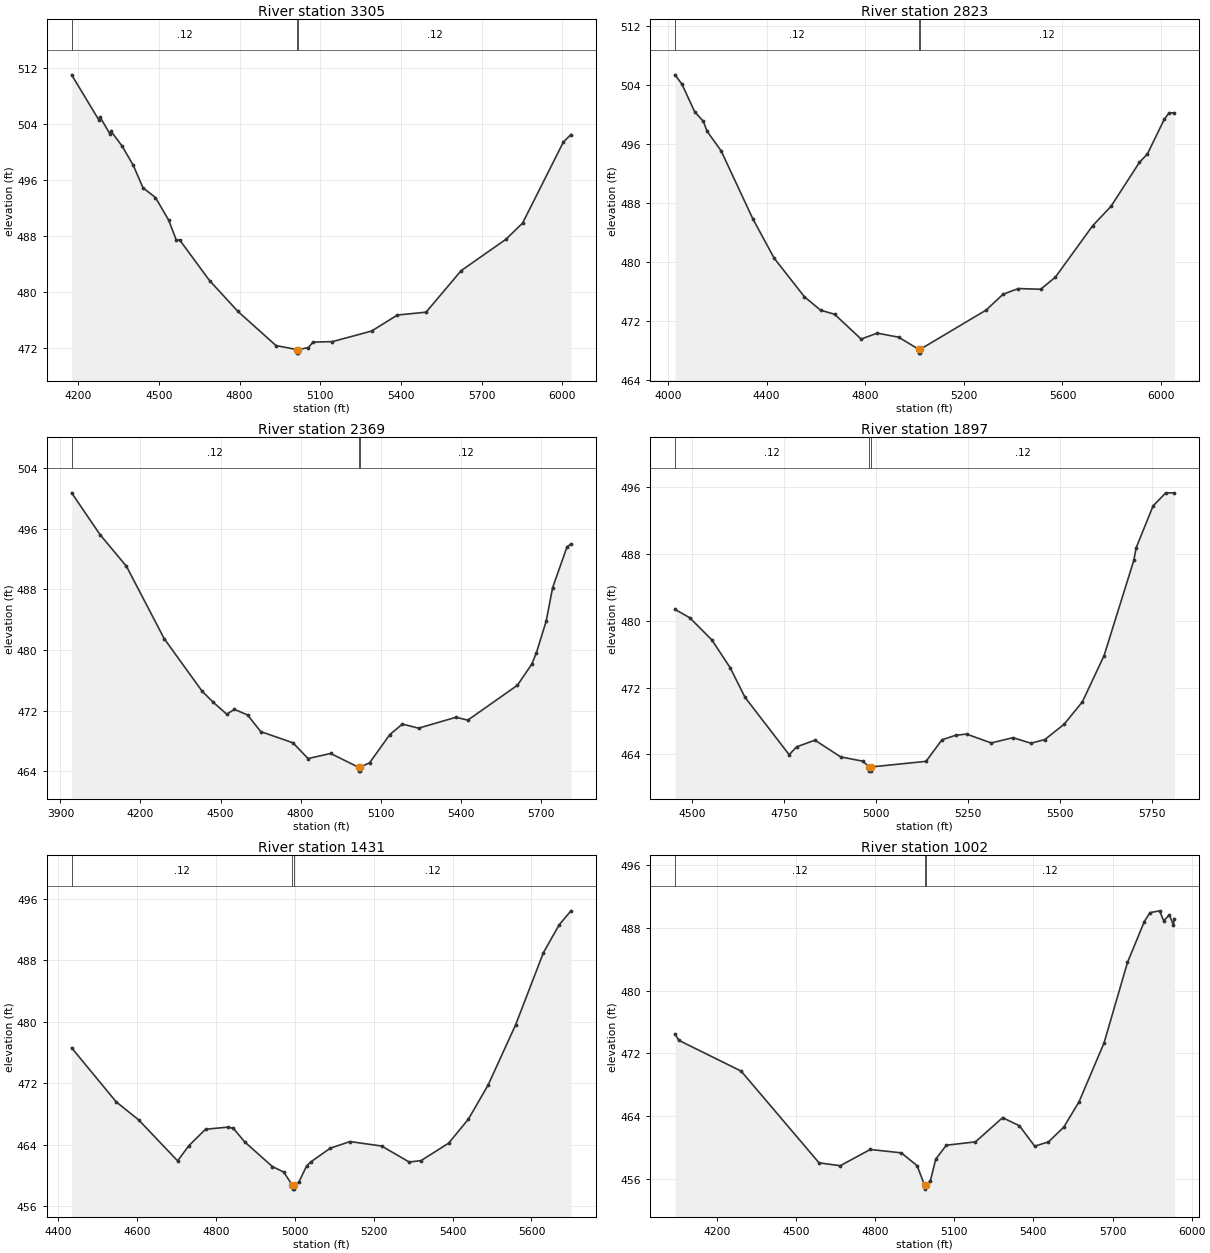
Type RM Length L Ch R = 1,3305,482,482,482
BEGIN DESCRIPTION:
ONEIL TRIBUTARY 2 5.0
END DESCRIPTION:
XS GIS Cut Line= 3
      2354024.98     13717124.99      2353225.00     13716925.00
      2352231.98     13717207.42
#Sta/Elev= 30
  4175.4  511.02  4275.9  504.61  4281.0  504.99  4317.1  502.61  4322.3  502.93
  4363.5  500.80  4404.7  498.07  4440.8  494.86  4487.2  493.46  4536.2  490.24
  4564.5  487.39  4577.4  487.39  4688.2  481.59  4793.8  477.17  4935.6  472.28
  5014.8  471.70  5015.1  471.20  5018.8  471.20  5019.1  471.70  5056.0  472.00
  5072.8  472.77  5145.6  472.85  5291.1  474.36  5386.9  476.65  5493.7  477.06
  5623.8  482.99  5790.6  487.49  5852.5  489.80  6004.3  501.40  6032.4  502.48
#Mann=3,-1,0
  4175.4    0.12       0  5014.8    0.05       0  5019.1    0.12       0
Bank Sta=5014.8,5019.1
Exp/Cntr=0.3,0.1

Type RM Length L Ch R = 1,2823,454,454,454
BEGIN DESCRIPTION:
ONEIL TRIBUTARY 2 4.0
END DESCRIPTION:
XS GIS Cut Line= 3
      2353925.03     13717025.02      2353125.00     13716475.00
      2352073.98     13716402.27
#Sta/Elev= 30
  4029.1  505.40  4057.5  504.11  4108.3  500.42  4144.1  499.08  4159.0  497.75
  4215.9  495.10  4344.7  485.87  4431.0  480.55  4553.4  475.33  4619.1  473.50
  4675.9  472.95  4783.5  469.59  4849.1  470.39  4935.7  469.84  5017.8  468.18
  5018.1  467.68  5021.9  467.68  5022.2  468.18  5290.7  473.52  5358.9  475.66
  5421.0  476.43  5511.6  476.34  5571.3  477.98  5721.7  484.92  5796.7  487.58
  5912.1  493.54  5944.3  494.68  6012.4  499.35  6032.4  500.26  6053.5  500.24
#Mann=3,-1,0
  4029.1    0.12       0  5017.8    0.05       0  5022.2    0.12       0
Bank Sta=5017.8,5022.2
Exp/Cntr=0.3,0.1

Type RM Length L Ch R = 1,2369,472,472,472
BEGIN DESCRIPTION:
ONEIL TRIBUTARY 2 3.0
END DESCRIPTION:
XS GIS Cut Line= 3
      2353975.02     13716875.02      2353275.00     13716075.00
      2352525.01     13715775.00
#Sta/Elev= 30
  3942.2  500.73  4048.5  495.22  4147.7  491.03  4289.1  481.48  4431.5  474.53
  4473.7  473.06  4523.6  471.51  4552.0  472.15  4601.4  471.42  4650.7  469.22
  4771.3  467.74  4828.2  465.66  4912.7  466.33  5017.7  464.50  5018.1  464.00
  5022.0  464.00  5022.3  464.50  5059.1  465.12  5134.5  468.83  5181.6  470.21
  5242.2  469.67  5382.2  471.11  5426.6  470.73  5612.4  475.33  5666.3  478.12
  5683.8  479.64  5720.1  483.77  5744.4  488.21  5798.2  493.59  5813.0  493.98
#Mann=3,-1,0
  3942.2    0.12       0  5017.7    0.05       0  5022.3    0.12       0
Bank Sta=5017.7,5022.3
Exp/Cntr=0.3,0.1

Type RM Length L Ch R = 1,1897,466,466,466
BEGIN DESCRIPTION:
ONEIL TRIBUTARY 2 2.0
END DESCRIPTION:
XS GIS Cut Line= 3
      2354024.96     13715675.00      2353475.00     13715675.00
      2352774.99     13715274.99
#Sta/Elev= 30
  4454.7  481.34  4494.7  480.34  4554.7  477.69  4604.7  474.35  4644.7  470.83
  4764.7  463.96  4784.7  464.90  4834.7  465.70  4904.7  463.70  4964.7  463.19
  4982.3  462.50  4982.7  462.00  4986.7  462.00  4987.0  462.50  5136.4  463.17
  5179.6  465.74  5217.0  466.29  5246.5  466.43  5313.5  465.37  5372.5  466.00
  5421.4  465.34  5458.9  465.77  5511.4  467.60  5561.1  470.29  5620.1  475.82
  5700.7  487.19  5707.2  488.71  5753.3  493.73  5787.8  495.28  5810.9  495.27
#Mann=3,-1,0
  4454.7    0.12       0  4982.3    0.05       0  4987.0    0.12       0
Bank Sta=4982.3,4987
Exp/Cntr=0.3,0.1

Type RM Length L Ch R = 1,1431,429,429,429
BEGIN DESCRIPTION:
ONEIL TRIBUTARY 2 1.0
END DESCRIPTION:
XS GIS Cut Line= 3
      2353925.01     13715625.01      2353525.00     13715225.00
      2352825.00     13715225.00
#Sta/Elev= 30
  4434.3  476.59  4547.4  469.55  4604.0  467.22  4703.0  461.88  4731.3  463.85
  4773.7  465.99  4830.3  466.27  4844.4  466.11  4872.7  464.36  4943.4  461.13
  4971.7  460.43  4994.1  458.70  4994.5  458.20  4998.5  458.20  4998.8  458.70
  5010.0  459.08  5030.0  461.22  5040.0  461.72  5090.0  463.53  5140.0  464.39
  5220.0  463.81  5290.0  461.73  5320.0  461.91  5390.0  464.18  5440.0  467.30
  5490.0  471.74  5560.0  479.61  5630.0  488.95  5670.0  492.59  5700.0  494.42
#Mann=3,-1,0
  4434.3    0.12       0  4994.1    0.05       0  4998.8    0.12       0
Bank Sta=4994.1,4998.8
Exp/Cntr=0.3,0.1

Type RM Length L Ch R = 1,1002,394,394,394
BEGIN DESCRIPTION:
B19911
END DESCRIPTION:
XS GIS Cut Line= 4
      2354188.43     13715481.22      2353736.94     13714826.55
      2353330.60     13714788.93      2352743.75     13715150.07
#Sta/Elev= 30
  4042.0  474.47  4056.2  473.66  4292.5  469.74  4587.7  458.06  4668.2  457.69
  4781.8  459.76  4899.5  459.33  4959.7  457.69  4987.5  455.21  4987.8  454.71
  4992.2  455.21  5009.9  455.79  5030.0  458.53  5070.2  460.30  5180.7  460.73
  5283.4  463.81  5347.2  462.78  5405.2  460.18  5457.3  460.73  5515.3  462.60
  5573.3  465.84  5667.9  473.32  5756.7  483.57  5820.6  488.78  5841.9  489.92
  5878.6  490.15  5894.0  488.88  5915.3  489.63  5930.7  488.36  5934.4  489.15
#Mann=3,-1,0
  4042.0    0.12       0  4987.5    0.05       0  4992.2    0.12       0
Bank Sta=4987.5,4992.2
Exp/Cntr=0.3,0.1

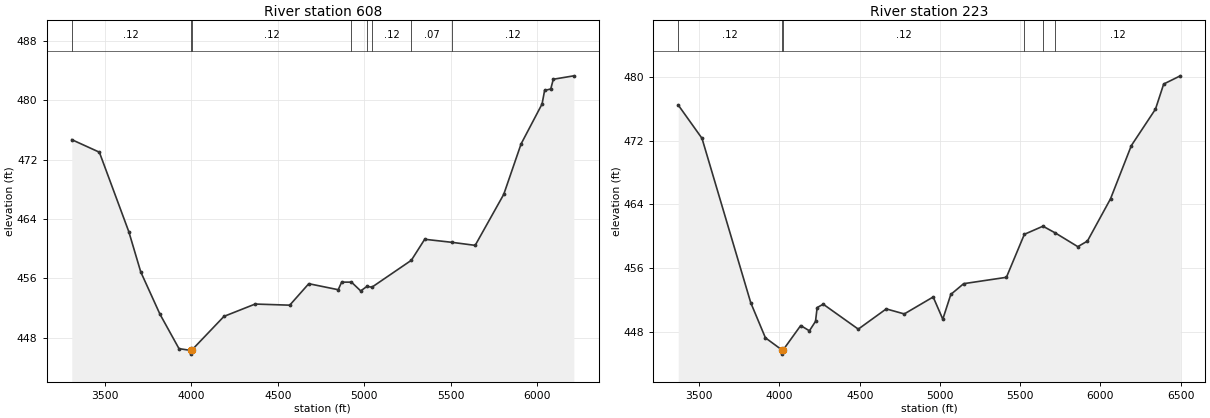
Type RM Length L Ch R = 1,608,385,385,385
BEGIN DESCRIPTION:
B19910
END DESCRIPTION:
XS GIS Cut Line= 4
      2355264.46     13714502.98      2353631.59     13714450.31
      2353165.05     13714450.31      2352690.96     13715097.49
#Sta/Elev= 30
  3309.3  474.68  3468.8  472.99  3638.9  462.30  3708.0  456.88  3819.0  451.19
  3929.1  446.55  3996.8  446.31  3997.1  445.81  4001.5  446.31  4189.2  450.89
  4369.3  452.55  4569.4  452.40  4679.5  455.29  4849.6  454.48  4869.6  455.50
  4926.2  455.50  4979.6  454.32  5016.0  454.93  5044.5  454.82  5272.3  458.44
  5349.6  461.27  5506.6  460.86  5641.4  460.45  5806.6  467.32  5906.9  474.11
  6028.1  479.48  6042.8  481.30  6078.3  481.50  6093.0  482.81  6211.8  483.27
#Mann=8,-1,0
  3309.3    0.12       0  3996.8   0.033       0  4001.5    0.12       0
  4926.2   0.033       0  5016.0   0.035       0  5044.5    0.12       0
  5272.3    0.07       0  5506.6    0.12       0
Bank Sta=3996.8,4001.5
Exp/Cntr=0.3,0.1

Type RM Length L Ch R = 1,223,0,0,0
BEGIN DESCRIPTION:
B19909
END DESCRIPTION:
XS GIS Cut Line= 4
      2355219.38     13714390.12      2353857.34     13714081.59
      2353308.02     13714081.59      2352653.37     13715067.34
#Sta/Elev= 30
  3369.0  476.48  3517.0  472.30  3820.9  451.65  3912.3  447.24  4017.1  445.69
  4017.4  445.19  4021.9  445.69  4132.2  448.78  4186.5  448.12  4224.5  449.30
  4234.8  451.04  4272.8  451.46  4491.1  448.33  4665.4  450.87  4777.9  450.24
  4957.9  452.37  5017.9  449.58  5067.9  452.69  5147.9  454.04  5414.4  454.84
  5526.2  460.24  5642.2  461.26  5720.2  460.40  5859.4  458.69  5919.2  459.39
  6063.2  464.70  6193.1  471.39  6343.5  475.97  6394.6  479.12  6498.2  480.15
#Mann=6,-1,0
  3369.0    0.12       0  4017.1    0.05       0  4021.9    0.12       0
  5526.2   0.035       0  5642.2    0.07       0  5720.2    0.12       0
Bank Sta=4017.1,4021.9
Exp/Cntr=0.3,0.1

Chan Stop Cuts=-1