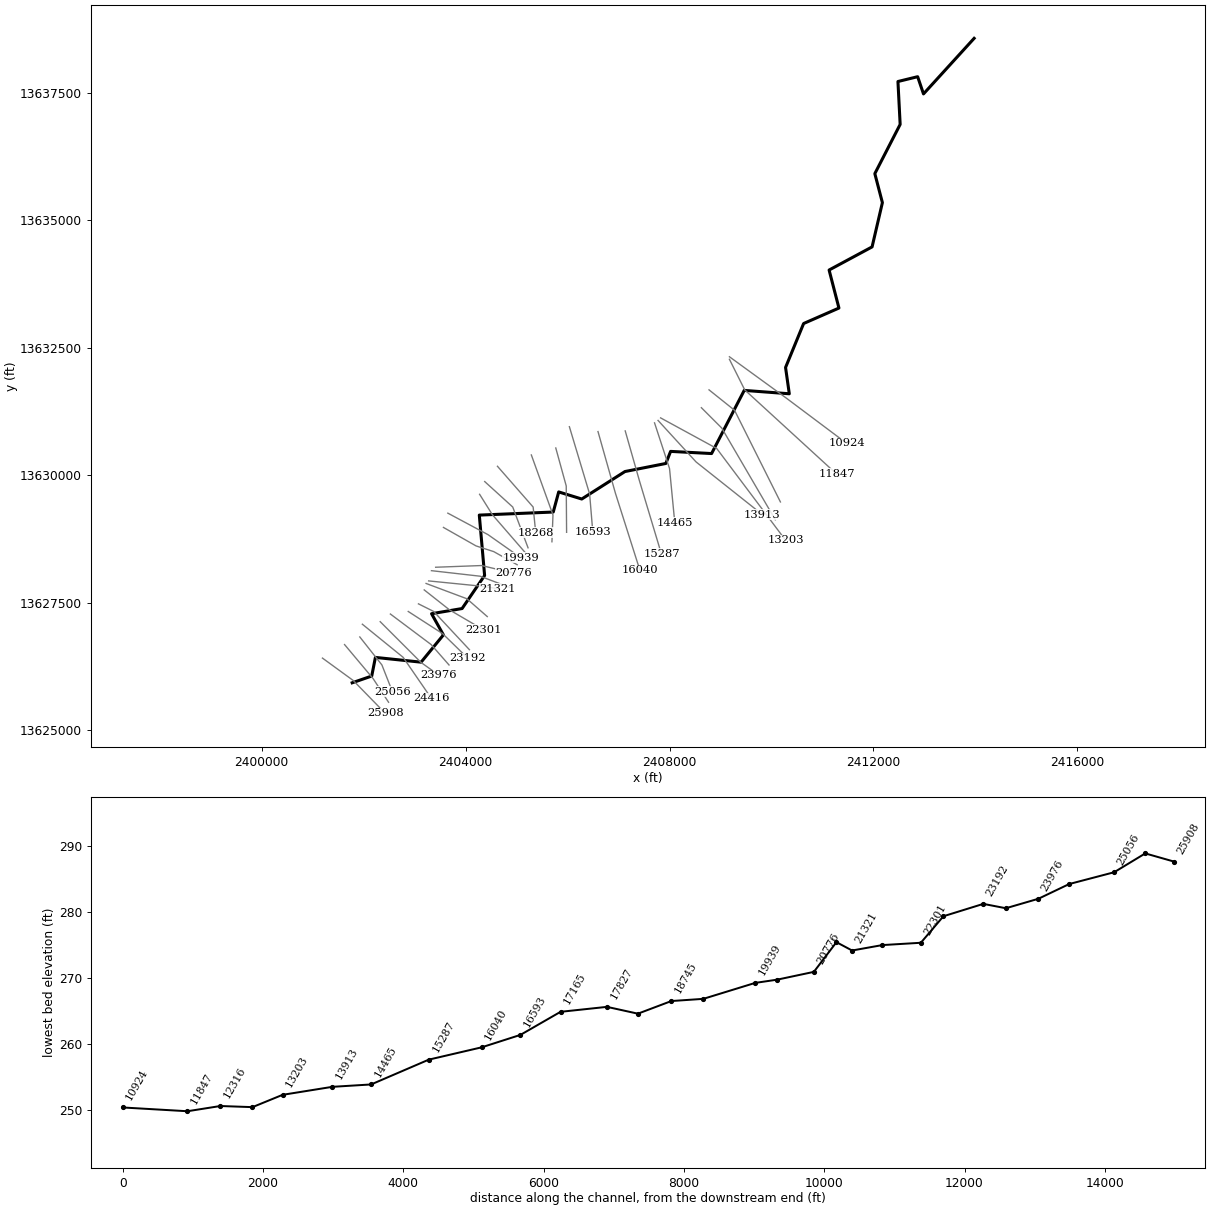
--- PANTHER BRANCH.prj (project) ---

Proj Title=PANTHER BRANCH Base Level Engineering
Current Plan=p01
Default Exp/Contr=0.3,0.1
English Units
Geom File=g01
Flow File=f01
Plan File=p01
Y Axis Title=Elevation
X Axis Title(PF)=Main Channel Distance
X Axis Title(XS)=Station
BEGIN DESCRIPTION:
PANTHER BRANCH
END DESCRIPTION:
DSS Export Rating Curves= 0
DSS Export Rating Curve Sorted= 0
DSS Export Volume Flow Curves= 0
DXF OffsetX= 0
DXF OffsetY= 0
DXF ScaleX= 1
DXF ScaleY= 10

--- PANTHER BRANCH.p01 (plan) ---

Plan Title=Multiple Run
Short Identifier=Multiple
Geom File=g01
Flow File=f01
Subcritical Flow
K Sum by GR= 0
Std Step Tol= 0.01
Critical Tol= 0.01
Num of Std Step Trials= 20
Max Error Tol= 0.3
Flow Tol Ratio= 0.001
Split Flow NTrial= 30
Split Flow Tol= 0.02
Split Flow Ratio= 0.02
Log Output Level= 0
Friction Slope Method= 1
Unsteady Friction Slope Method= 2
Unsteady Bridges Friction Slope Method= 1
Parabolic Critical Depth
Global Vel Dist=  1 , 1 , 1
Global Log Level= 0
CheckData=True
Encroach Param= -1, 0, 0, 0
BEGIN DESCRIPTION:
Multiple Run
END DESCRIPTION:

--- PANTHER BRANCH.f01 (steady flow) ---

Flow Title=Multiple
Number of Profiles=7
Profile Names=10-year,25-year,50-year,1pct_min,100-year,1pct_plu,500-year
River Rch & RM= PANTHER BRANCH,Reach-1,25908
     649    1048    1408     916    1828    3647    3052
River Rch & RM= PANTHER BRANCH,Reach-1,23976
     918    1505    2041    1339    2671    5329    4533
River Rch & RM= PANTHER BRANCH,Reach-1,16040
    1550    2600    3583    2381    4751    9480    8290
River Rch & RM= PANTHER BRANCH,Reach-1,13913
    2073    3509    4865    3250    6484   12938   11429
River Rch & RM= PANTHER BRANCH,Reach-1,7019
    2120    3576    4943    3291    6567   13102   11499
Boundary for River Rch & Prof#=PANTHER BRANCH,Reach-1,1
Up Type=0
Dn Type=3
Dn Slope=0.005
Boundary for River Rch & Prof#=PANTHER BRANCH,Reach-1,2
Up Type=0
Dn Type=3
Dn Slope=0.005
Boundary for River Rch & Prof#=PANTHER BRANCH,Reach-1,3
Up Type=0
Dn Type=3
Dn Slope=0.005
Boundary for River Rch & Prof#=PANTHER BRANCH,Reach-1,4
Up Type=0
Dn Type=3
Dn Slope=0.005
Boundary for River Rch & Prof#=PANTHER BRANCH,Reach-1,5
Up Type=0
Dn Type=3
Dn Slope=0.005
Boundary for River Rch & Prof#=PANTHER BRANCH,Reach-1,6
Up Type=0
Dn Type=3
Dn Slope=0.005
Boundary for River Rch & Prof#=PANTHER BRANCH,Reach-1,7
Up Type=0
Dn Type=3
Dn Slope=0.005

--- PANTHER BRANCH.g01 (geometry) ---

Geom Title=Existing Conditions
Program Version=4.10

River Reach=PANTHER BRANCH  ,Reach-1
Reach XY= 30
        2401775.       13625925.      2402158.79     13626057.78
      2402230.85     13626423.51      2403127.31     13626330.08
      2403564.83     13626865.32      2403332.46     13627281.09
      2403931.21      13627382.8      2404373.02      13628030.9
      2404268.91     13629216.86      2405719.51     13629276.96
      2405826.25     13629671.64      2406278.34      13629532.6
      2407126.16     13630071.88      2407927.74     13630230.34
       2408021.3      13630467.3        2408825.       13630425.
      2409465.19     13631664.58      2410349.23     13631598.33
      2410276.05     13632114.57      2410630.39     13632977.44
      2411323.05     13633280.88      2411130.09     13634027.33
      2411973.16     13634481.12      2412175.41       13635350.
      2412027.06     13635919.15      2412523.78      13636885.5
      2412480.52     13637727.44      2412867.09     13637822.09
      2412981.65     13637483.97        2413975.       13638575.

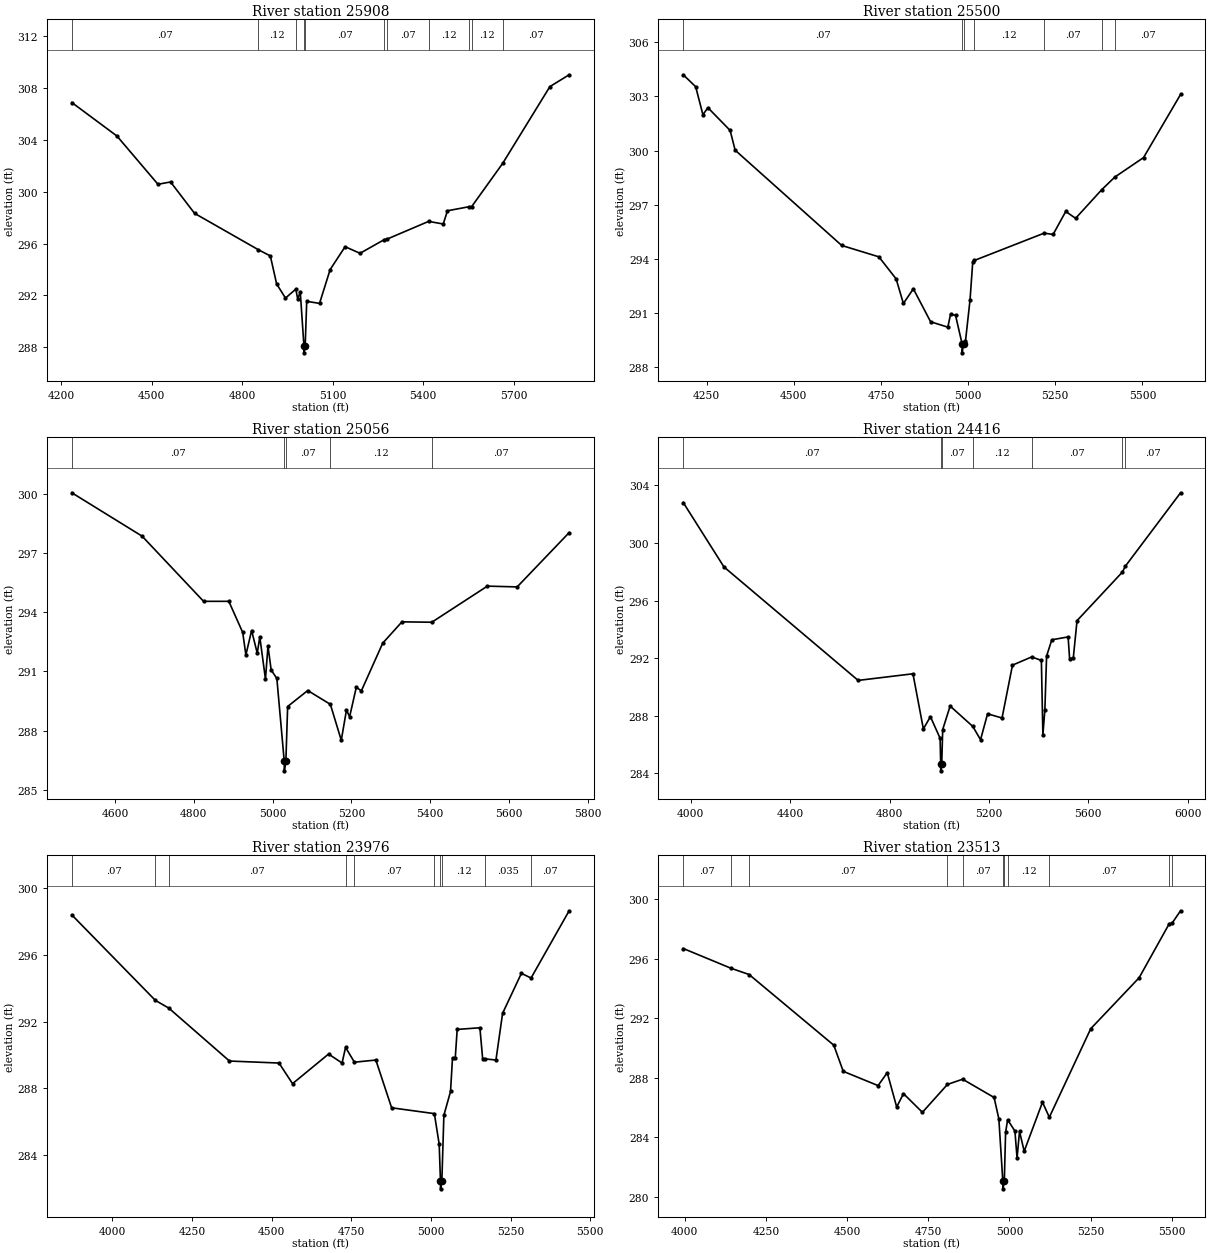
Type RM Length L Ch R = 1 ,25908   ,408,408,408
BEGIN DESCRIPTION:
PANTHER BRANCH 41.0
END DESCRIPTION:
XS GIS Cut Line= 3
      2401192.11      13626410.2      2401797.72     13625969.07
        2402425.       13625325.
#Sta/Elev= 30
  4235.7  306.87  4385.2  304.29  4521.2  300.57  4562.9  300.75  4642.5  298.33
  4853.7  295.53  4893.6  295.05  4914.5  292.89  4943.8   291.8    4978  292.49
  4984.2  291.75  4992.9  292.25  5005.1  288.08  5005.3  287.58  5009.1  288.08
  5014.2  291.55  5056.7  291.39  5091.9     294  5141.5  295.76  5190.9  295.25
  5271.5  296.31    5281  296.35  5418.2  297.71  5466.7  297.51  5480.8  298.53
    5552  298.84  5560.9  298.85  5663.7  302.18  5820.3   308.1    5884  309.01
#Mann= 11 ,-1 , 0
  4235.7     .07       0  4853.7     .12       0    4978     .07       0
  5005.1     .05       0  5009.1     .07       0  5271.5     .12       0
    5281     .07       0  5418.2     .12       0    5552     .07       0
  5560.9     .12       0  5663.7     .07       0
Bank Sta=5005.1,5009.1
XS Rating Curve= 0 ,0
Exp/Cntr=0.3,0.1

Type RM Length L Ch R = 1 ,25500   ,444,444,444
BEGIN DESCRIPTION:
B19925
END DESCRIPTION:
XS GIS Cut Line= 3
      2401625.74     13626675.62       2402186.5     13626006.45
      2402489.28     13625542.94
#Sta/Elev= 30
  4182.8  304.19  4218.4  303.53  4239.2  301.98  4253.5  302.37  4317.3  301.11
  4331.6  300.02  4637.3  294.75    4744  294.12  4793.5   292.9  4814.3  291.54
  4842.9  292.35  4892.4  290.53  4941.8  290.23  4949.6  290.94  4963.9  290.89
  4982.7  289.31    4983  288.81  4986.8  289.31  4992.5  289.46  5005.6  291.75
  5013.3  293.84  5017.9  293.92  5218.1  295.43  5243.9  295.36  5280.1  296.63
  5308.4  296.25  5383.2  297.83  5420.8  298.53  5503.3  299.61  5609.5   303.1
#Mann= 7 ,-1 , 0
  4182.8     .07       0  4982.7     .05       0  4986.8     .07       0
  5017.9     .12       0  5218.1     .07       0  5383.2     .12       0
  5420.8     .07       0
Bank Sta=4982.7,4986.8
XS Rating Curve= 0 ,0
Exp/Cntr=0.3,0.1

Type RM Length L Ch R = 1 ,25056   ,640,640,640
BEGIN DESCRIPTION:
PANTHER BRANCH 40.0
END DESCRIPTION:
XS GIS Cut Line= 3
      2401924.98     13626825.02      2402358.45      13626275.6
      2402564.05     13625752.27
#Sta/Elev= 30
  4490.7  300.05  4669.1  297.85    4825  294.55  4889.1  294.55  4924.4  292.97
  4932.4  291.83  4946.9  293.07  4961.3  291.92  4967.7  292.75  4982.1  290.61
  4988.5  292.28  4996.6  291.07    5011  290.64  5029.7  286.46    5030  285.96
  5033.9  286.46  5038.4  289.22  5089.4  290.03  5146.8  289.33  5174.5  287.51
  5187.7  289.04  5195.7   288.7  5212.7   290.2  5225.4  290.01  5279.7  292.43
  5328.5  293.51  5404.3  293.49  5545.3  295.32  5620.9  295.28  5752.8  298.03
#Mann= 5 ,-1 , 0
  4490.7     .07       0  5029.7     .05       0  5033.9     .07       0
  5146.8     .12       0  5404.3     .07       0
Bank Sta=5029.7,5033.9
XS Rating Curve= 0 ,0
Exp/Cntr=0.3,0.1

Type RM Length L Ch R = 1 ,24416   ,440,440,440
BEGIN DESCRIPTION:
PANTHER BRANCH 39.0
END DESCRIPTION:
XS GIS Cut Line= 3
        2401975.       13627075.        2402775.       13626425.
        2403325.       13625625.
#Sta/Elev= 30
  3969.5  302.81  4133.3  298.34  4673.5  290.46    4894  290.92  4935.9  287.09
  4964.3  287.94  5003.3  286.44  5005.6  284.68  5005.9  284.18  5009.8  284.68
  5013.8  287.05  5043.6  288.68  5135.1  287.26    5166  286.34  5194.4  288.14
  5252.6  287.85  5294.6  291.52  5371.7  292.09  5410.9  291.85    5417  286.67
    5425  288.43  5431.9  292.15  5452.9  293.28  5518.5  293.48  5524.6  291.96
  5539.5  292.04  5554.4  294.61  5737.4  297.99  5748.4  298.38  5971.1  303.49
#Mann= 7 ,-1 , 0
  3969.5     .07       0  5005.6     .05       0  5009.8     .07       0
  5135.1     .12       0  5371.7     .07       0  5737.4     .12       0
  5748.4     .07       0
Bank Sta=5005.6,5009.8
XS Rating Curve= 0 ,0
Exp/Cntr=0.3,0.1

Type RM Length L Ch R = 1 ,23976   ,463,463,463
BEGIN DESCRIPTION:
PANTHER BRANCH 38.0
END DESCRIPTION:
XS GIS Cut Line= 3
        2402325.       13627125.        2403125.       13626325.
      2403475.01     13626074.99
#Sta/Elev= 30
  3872.5  298.41  4134.5  293.28    4177  292.81  4367.5  289.63    4523  289.51
  4565.5  288.27  4678.6  290.05    4721  289.51    4732  290.45  4759.8  289.56
  4827.1  289.69  4876.6  286.82  5010.8  286.47    5026  284.63  5029.9  282.45
  5030.2  281.95  5034.4  282.45  5040.7  286.37  5061.6   287.8  5067.8  289.83
  5076.4   289.8  5082.5  291.53  5153.8  291.63  5162.4  289.78  5170.5  289.76
  5204.2  289.69  5225.1   292.5  5284.1   294.9  5314.5  294.62    5434  298.66
#Mann= 10 ,-1 , 0
  3872.5     .07       0  4134.5     .12       0    4177     .07       0
    4732     .12       0  4759.8     .07       0  5010.8     .12       0
  5029.9     .05       0  5034.4     .12       0  5170.5    .035       0
  5314.5     .07       0
Bank Sta=5029.9,5034.4
XS Rating Curve= 0 ,0
Exp/Cntr=0.3,0.1

Type RM Length L Ch R = 1 ,23513   ,321,321,321
BEGIN DESCRIPTION:
PANTHER BRANCH 37.0
END DESCRIPTION:
XS GIS Cut Line= 3
      2402524.97     13627275.02        2403325.       13626675.
      2403674.97     13626275.03
#Sta/Elev= 30
  3995.3   296.7  4142.3  295.37    4198  294.95  4458.9  290.19    4488  288.43
  4595.3  287.47  4623.5  288.34  4652.6  286.03  4673.5  286.93  4731.8  285.67
  4808.9  287.55  4855.7   287.9  4952.6  286.67  4967.2  285.23  4979.5  281.02
  4979.8  280.52    4984  281.02    4988  284.32  4994.2  285.17  5016.7  284.41
  5023.3  282.59  5030.9  284.39  5045.2  283.05  5101.6  286.35  5122.7  285.34
  5250.2   291.3  5399.2  294.73    5492  298.37  5500.5   298.4  5526.8  299.24
#Mann= 11 ,-1 , 0
  3995.3     .07       0  4142.3     .12       0    4198     .07       0
  4808.9     .12       0  4855.7     .07       0  4979.5     .05       0
    4984     .07       0  4994.2     .12       0  5122.7     .07       0
    5492    .035       0  5500.5     .07       0
Bank Sta=4979.5,4984
XS Rating Curve= 0 ,0
Exp/Cntr=0.3,0.1

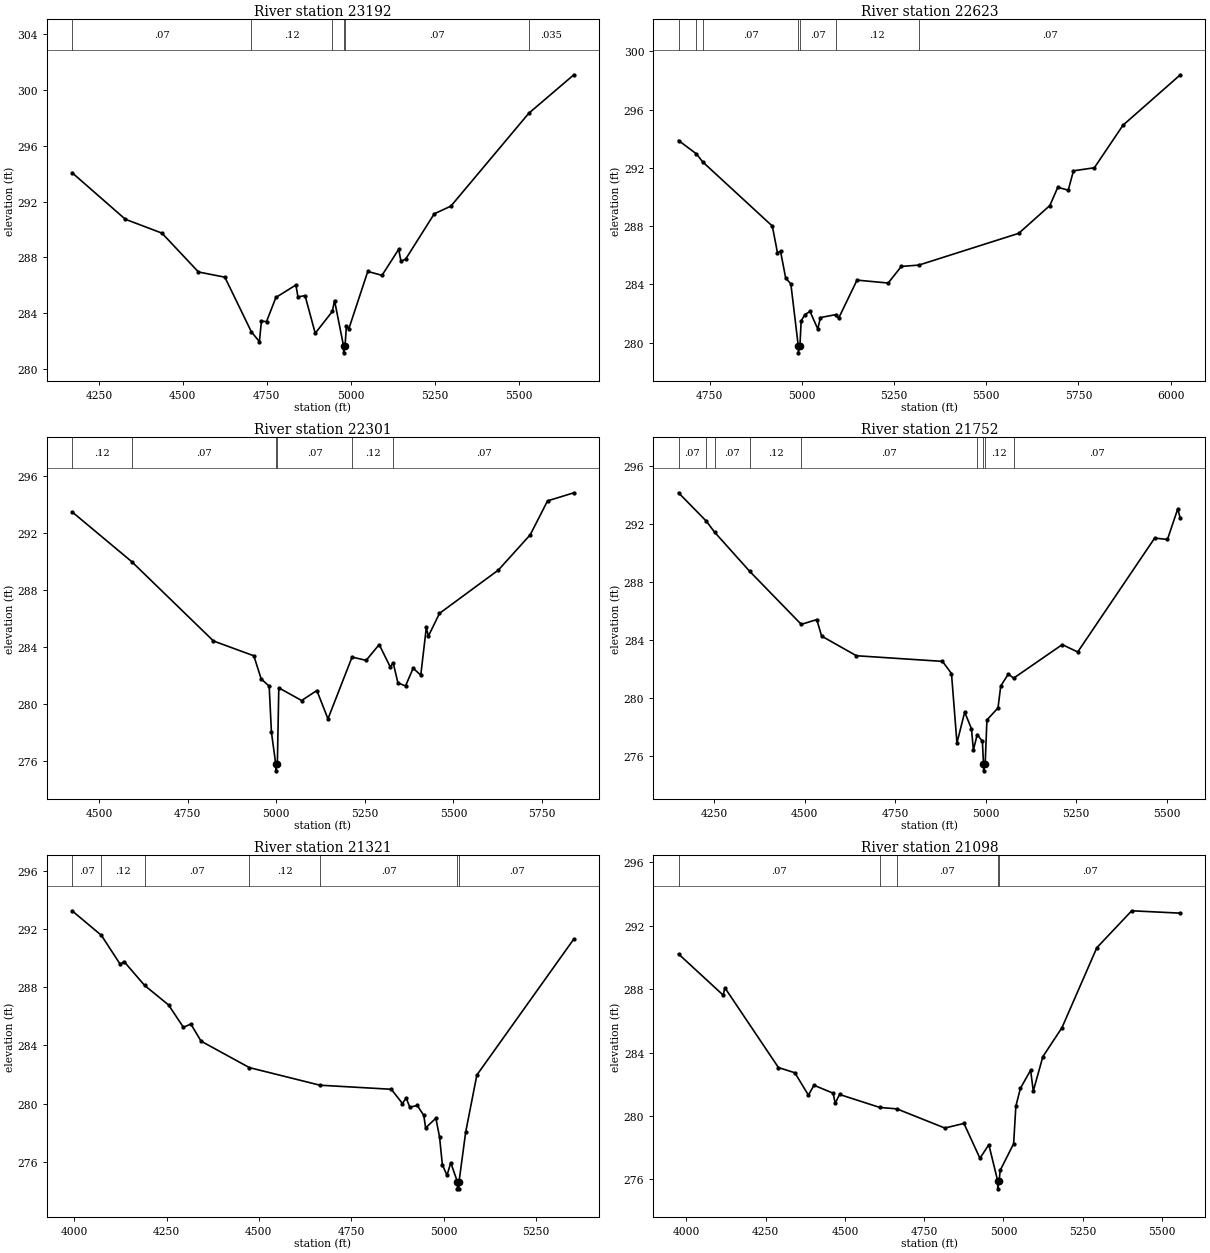
Type RM Length L Ch R = 1 ,23192   ,569,569,569
BEGIN DESCRIPTION:
PANTHER BRANCH 36.0
END DESCRIPTION:
XS GIS Cut Line= 3
      2402874.97     13627325.02      2403550.93     13626888.66
      2404044.36     13626406.45
#Sta/Elev= 30
  4170.3  294.06    4329  290.73  4437.9  289.74  4546.8  286.96  4625.3  286.59
  4704.4  282.68  4728.3  281.98  4734.2  283.45  4749.4  283.41  4777.4  285.14
  4836.9  286.03  4843.1  285.18  4864.2  285.27  4894.5  282.58  4945.5  284.14
    4952  284.92  4978.8  281.68  4979.1  281.18  4983.3  281.68  4987.4   283.1
  4994.5  282.89    5051     287  5093.4  286.72    5143  288.58    5150  287.72
  5164.1  287.89    5249  291.12  5298.6  291.67  5530.6  298.31  5664.8  301.06
#Mann= 6 ,-1 , 0
  4170.3     .07       0  4704.4     .12       0  4945.5     .07       0
  4978.8     .05       0  4983.3     .07       0  5530.6    .035       0
Bank Sta=4978.8,4983.3
XS Rating Curve= 0 ,0
Exp/Cntr=0.3,0.1

Type RM Length L Ch R = 1 ,22623   ,322,322,322
BEGIN DESCRIPTION:
PANTHER BRANCH 35.0
END DESCRIPTION:
XS GIS Cut Line= 3
      2403074.98     13627475.01        2403375.       13627325.
      2404074.97     13626575.03
#Sta/Elev= 30
  4665.2  293.88  4713.9  292.96  4730.8  292.41  4919.6  288.01  4933.6  286.18
  4941.9  286.28  4955.9  284.44  4969.9  284.04  4989.9  279.81  4990.2  279.31
  4994.6  279.81  4997.8  281.49  5007.7  281.93  5021.9  282.15  5042.9  280.95
  5050.2  281.73  5091.1  281.93  5099.6  281.69  5149.4   284.3  5233.9   284.1
  5269.6  285.24  5316.9  285.33  5588.1  287.51  5672.6  289.42  5694.1  290.67
  5722.4  290.47  5736.6   291.8  5793.3  292.01    5871  294.93  6026.5  298.39
#Mann= 7 ,-1 , 0
  4665.2     .07       0  4713.9     .12       0  4730.8     .07       0
  4989.9     .05       0  4994.6     .07       0  5091.1     .12       0
  5316.9     .07       0
Bank Sta=4989.9,4994.6
XS Rating Curve= 0 ,0
Exp/Cntr=0.3,0.1

Type RM Length L Ch R = 1 ,22301   ,549,549,549
BEGIN DESCRIPTION:
B19924
END DESCRIPTION:
XS GIS Cut Line= 3
      2403188.31     13627748.46      2403685.51     13627355.94
      2404360.76     13626960.48
#Sta/Elev= 30
  4423.7  293.49  4591.7     290  4822.7  284.42  4936.6  283.38  4957.4  281.75
  4979.9  281.25  4986.3  278.01  4998.3   275.8  4998.7   275.3    5003   275.8
  5007.1  281.13  5071.4  280.24  5114.5  280.94  5145.8  278.95  5213.8  283.29
  5253.6  283.06  5290.4  284.17  5321.7  282.59  5329.8  282.89  5343.2  281.48
  5364.7  281.26  5386.2  282.51  5407.7  282.02  5423.4  285.37  5429.2  284.76
  5460.5  286.36  5626.6   289.4  5716.6  291.88  5765.4  294.26  5839.7  294.83
#Mann= 6 ,-1 , 0
  4423.7     .12       0  4591.7     .07       0  4998.3     .05       0
    5003     .07       0  5213.8     .12       0  5329.8     .07       0
Bank Sta=4998.3,5003
XS Rating Curve= 0 ,0
Exp/Cntr=0.3,0.1

Type RM Length L Ch R = 1 ,21752   ,431,431,431
BEGIN DESCRIPTION:
PANTHER BRANCH 34.0
END DESCRIPTION:
XS GIS Cut Line= 3
      2403224.96     13627875.02        2404025.       13627575.
      2404425.04     13627224.97
#Sta/Elev= 30
  4151.8  294.18  4228.4  292.22  4251.6  291.45  4348.6  288.74  4490.8  285.08
  4533.7  285.41    4547  284.27  4643.1  282.91  4880.8  282.52  4905.7  281.68
  4920.8  276.88  4942.2  279.01  4960.9  277.86  4966.2  276.39  4976.8  277.46
  4991.1  276.99  4994.1  275.45  4994.5  274.95  4998.8  275.45  5003.6  278.47
  5034.2   279.3  5041.8  280.82  5062.7  281.64  5077.4  281.36  5211.7  283.68
  5254.4  283.17    5467  291.05  5502.2  290.95  5530.6  293.06  5537.8  292.41
#Mann= 9 ,-1 , 0
  4151.8     .07       0  4228.4     .12       0  4251.6     .07       0
  4348.6     .12       0  4490.8     .07       0  4976.8     .12       0
  4994.1     .05       0  4998.8     .12       0  5077.4     .07       0
Bank Sta=4994.1,4998.8
XS Rating Curve= 0 ,0
Exp/Cntr=0.3,0.1

Type RM Length L Ch R = 1 ,21321   ,223,223,223
BEGIN DESCRIPTION:
PANTHER BRANCH 33.0
END DESCRIPTION:
XS GIS Cut Line= 3
      2403275.02       13627925.        2404275.       13627825.
      2404624.98       13627775.
#Sta/Elev= 30
  3994.3  293.26  4073.7  291.57  4124.9  289.57    4135  289.77  4190.5  288.13
  4255.6  286.78  4295.8  285.24  4315.9  285.47  4343.5  284.29  4474.4  282.47
  4665.4  281.26  4858.6  280.98  4888.7     280  4898.8  280.38  4908.8  279.74
  4928.9  279.87  4946.5  279.18  4951.5  278.32  4979.2  278.99  4989.2  277.69
  4996.8  275.79  5009.4  275.06  5019.5  275.93  5037.3  274.63  5037.7  274.13
  5041.7  274.13    5042  274.63  5059.9  278.03  5090.2  281.96  5352.8  291.32
#Mann= 7 ,-1 , 0
  3994.3     .07       0  4073.7     .12       0  4190.5     .07       0
  4474.4     .12       0  4665.4     .07       0  5037.3     .05       0
    5042     .07       0
Bank Sta=5037.3,5042
XS Rating Curve= 0 ,0
Exp/Cntr=0.3,0.1

Type RM Length L Ch R = 1 ,21098   ,322,322,322
BEGIN DESCRIPTION:
B19923
END DESCRIPTION:
XS GIS Cut Line= 3
      2403330.42       13628126.      2404283.62      13628017.6
      2404866.76     13627797.05
#Sta/Elev= 30
  3975.1  290.22  4116.1  287.62  4121.2  288.09  4290.2  283.05    4342  282.72
  4384.7  281.31  4402.4  281.93  4462.8  281.43  4469.3  280.79  4482.9  281.35
  4609.9  280.53  4663.8  280.44  4815.1  279.23  4875.4  279.52  4925.8  277.32
  4953.9  278.18  4981.8  275.89  4982.1  275.39  4986.5  275.89  4989.5  276.55
  5032.1  278.24  5039.1  280.61  5053.5  281.74  5085.6  282.88  5094.1  281.57
  5124.3  283.74  5184.6  285.57  5294.6  290.62  5404.6  292.95  5557.9   292.8
#Mann= 5 ,-1 , 0
  3975.1     .07       0  4609.9     .12       0  4663.8     .07       0
  4981.8     .05       0  4986.5     .07       0
Bank Sta=4981.8,4986.5
XS Rating Curve= 0 ,0
Exp/Cntr=0.3,0.1

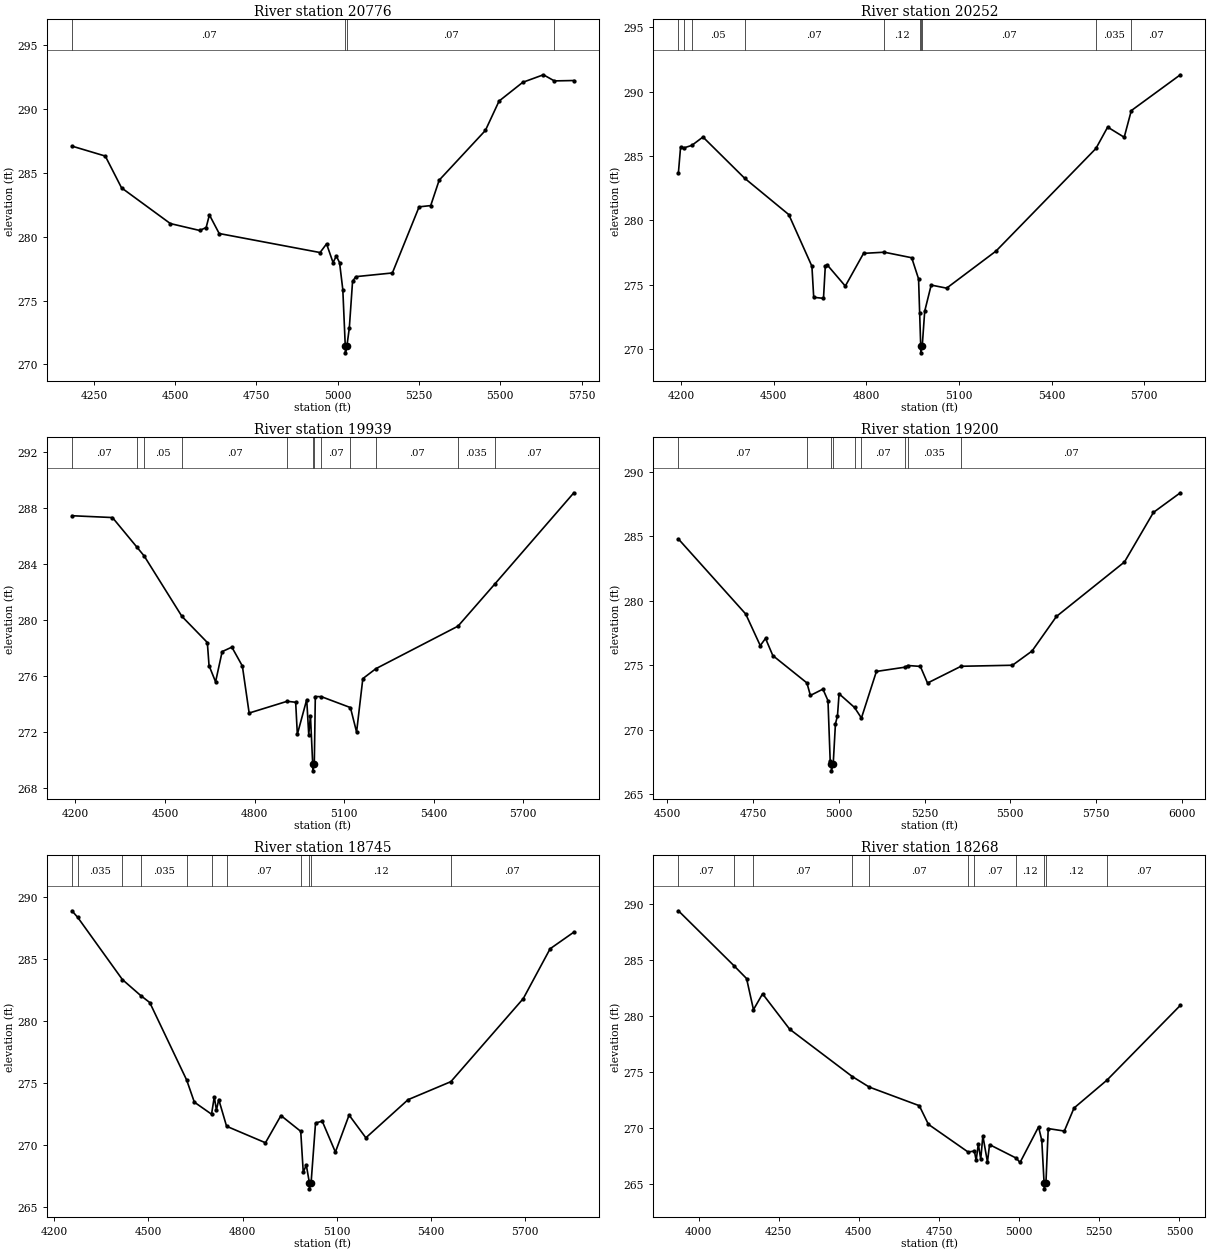
Type RM Length L Ch R = 1 ,20776   ,524,524,524
BEGIN DESCRIPTION:
B19922
END DESCRIPTION:
XS GIS Cut Line= 3
      2403412.58     13628193.29      2404313.52     13628226.93
      2404937.79     13628077.41
#Sta/Elev= 30
  4182.7   287.1  4285.2  286.32  4335.2  283.83  4485.3  281.03  4575.4  280.49
  4595.4  280.72  4605.4  281.71  4635.5  280.25  4945.7  278.76  4965.7  279.44
  4985.7  277.97  4995.7  278.49  5005.7  277.97  5015.7  275.85  5023.3   271.4
  5023.7   270.9  5028.1   271.4  5035.7  272.85  5045.7  276.51  5055.7  276.87
  5168.1  277.16  5250.3  282.34    5286  282.44    5312  284.43  5454.2  288.33
  5496.2  290.63  5569.1   292.1  5632.6  292.69  5666.2  292.21  5726.2  292.24
#Mann= 4 ,-1 , 0
  4182.7     .07       0  5023.3     .05       0  5028.1     .07       0
  5666.2    .035       0
Bank Sta=5023.3,5028.1
XS Rating Curve= 0 ,0
Exp/Cntr=0.3,0.1

Type RM Length L Ch R = 1 ,20252   ,313,313,313
BEGIN DESCRIPTION:
B19921
END DESCRIPTION:
XS GIS Cut Line= 4
      2403565.85     13628974.59      2404205.11     13628611.97
      2404552.77     13628499.82       2405011.3     13628242.59
#Sta/Elev= 30
  4191.1   283.7  4198.1  285.69  4209.4  285.63  4234.5  285.82  4270.6  286.47
  4405.2  283.28  4548.6  280.45  4623.6  276.44  4629.4  274.03  4661.1  273.95
  4666.9  276.43    4673  276.55  4731.8   274.9  4790.9  277.44    4858  277.53
  4946.9   277.1  4969.1  275.46  4972.6  272.84  4976.1  270.22  4976.4  269.72
  4980.9  270.22    4989  272.95    5010  274.98    5060  274.74  5220.1  277.62
  5543.7  285.58  5581.7  287.24  5635.3  286.45  5658.3  288.52  5817.1   291.3
#Mann= 10 ,-1 , 0
  4191.1     .07       0  4209.4    .035       0  4234.5     .05       0
  4405.2     .07       0    4858     .12       0  4972.6     .07       0
  4976.1     .05       0  4980.9     .07       0  5543.7    .035       0
  5658.3     .07       0
Bank Sta=4976.1,4980.9
XS Rating Curve= 0 ,0
Exp/Cntr=0.3,0.1

Type RM Length L Ch R = 1 ,19939   ,739,739,739
BEGIN DESCRIPTION:
B19920
END DESCRIPTION:
XS GIS Cut Line= 3
      2403651.89     13629254.92      2404440.62     13628832.52
      2405083.55     13628380.22
#Sta/Elev= 30
  4188.6  287.46  4324.3  287.33  4405.2  285.24  4430.6  284.58  4556.8  280.27
    4642   278.4  4647.7  276.75  4669.6  275.59  4691.6  277.75  4724.1  278.07
  4759.3  276.72    4782  273.36  4909.3   274.2  4937.8  274.13  4943.4  271.84
  4974.8  274.32  4981.6  271.82  4987.3  273.17  4994.8  269.73  4995.2  269.23
  5000.2  269.73  5003.6  274.54  5023.9  274.53  5121.2  273.75  5141.8     272
  5162.7  275.82  5206.4  276.53  5481.5  279.57  5604.3  282.57  5869.4   289.1
#Mann= 12 ,-1 , 0
  4188.6     .07       0  4405.2    .035       0  4430.6     .05       0
  4556.8     .07       0  4909.3     .12       0  4994.8     .05       0
  5000.2     .12       0  5023.9     .07       0  5121.2     .12       0
  5206.4     .07       0  5481.5    .035       0  5604.3     .07       0
Bank Sta=4994.8,5000.2
XS Rating Curve= 0 ,0
Exp/Cntr=0.3,0.1

Type RM Length L Ch R = 1 ,19200   ,455,455,455
BEGIN DESCRIPTION:
PANTHER BRANCH 29.0
END DESCRIPTION:
XS GIS Cut Line= 3
        2404275.       13629625.        2404525.       13629225.
      2405175.02     13628474.98
#Sta/Elev= 30
  4531.9  284.78  4728.2  278.97  4770.7  276.52    4786  277.08  4807.3  275.75
  4906.8  273.63  4916.9  272.66  4953.5  273.15  4968.2  272.26  4974.7  267.57
  4977.8  267.32  4978.3  266.82  4983.4  267.32    4990  270.47  4995.9  271.07
  5000.6  272.79  5045.6  271.73  5065.8  270.91  5109.5  274.52  5192.9  274.85
    5201  274.98  5237.7  274.91  5258.6  273.62  5356.4  274.92  5506.4     275
  5563.5   276.1  5634.7  278.78  5833.2     283  5917.7  286.84  5996.1  288.36
#Mann= 9 ,-1 , 0
  4531.9     .07       0  4906.8     .12       0  4977.8     .05       0
  4983.4     .12       0  5045.6    .035       0  5065.8     .07       0
  5192.9     .12       0    5201    .035       0  5356.4     .07       0
Bank Sta=4977.8,4983.4
XS Rating Curve= 0 ,0
Exp/Cntr=0.3,0.1

Type RM Length L Ch R = 1 ,18745   ,477,477,477
BEGIN DESCRIPTION:
PANTHER BRANCH 28.0
END DESCRIPTION:
XS GIS Cut Line= 3
      2404374.97     13629875.03        2404925.       13629375.
      2405224.98     13628575.05
#Sta/Elev= 30
  4256.8  288.88  4275.4  288.34  4417.4  283.34  4475.9  282.05  4504.5  281.49
    4622  275.25  4646.4  273.47  4701.2   272.5  4709.9   273.9  4716.7  272.83
  4724.1  273.68    4749  271.53  4872.8   270.2  4922.1  272.39  4985.1  271.12
  4993.1  267.82  5002.8  268.41  5012.5  266.99  5012.9  266.49  5018.1  266.99
  5032.2  271.79  5053.5  271.94  5095.4  269.45    5139  272.43  5192.4   270.6
  5326.8  273.67    5463  275.12  5693.5  281.81  5778.9  285.82  5854.5  287.16
#Mann= 11 ,-1 , 0
  4256.8     .07       0  4275.4    .035       0  4417.4     .07       0
  4475.9    .035       0    4622     .07       0  4701.2     .12       0
    4749     .07       0  4985.1     .12       0  5012.5     .05       0
  5018.1     .12       0    5463     .07       0
Bank Sta=5012.5,5018.1
XS Rating Curve= 0 ,0
Exp/Cntr=0.3,0.1

Type RM Length L Ch R = 1 ,18268   ,441,441,441
BEGIN DESCRIPTION:
PANTHER BRANCH 27.0
END DESCRIPTION:
XS GIS Cut Line= 3
      2404624.98     13630175.03        2405325.       13629375.
        2405375.     13628875.04
#Sta/Elev= 30
  3937.2  289.36    4111  284.45  4149.8  283.32  4171.3  280.55  4199.7  281.96
  4284.1  278.81  4479.4  274.59  4532.4  273.65  4688.5  271.99  4716.9  270.33
  4840.8  267.86  4860.4  267.95  4865.9  267.11  4872.6  268.58  4880.2  267.22
  4886.8  269.31  4901.1  266.97  4907.7  268.52  4990.7  267.32  5002.8  266.93
  5060.5   270.1  5070.6   268.9  5077.8  265.08  5078.2  264.58  5083.5  265.08
  5090.7  269.95  5140.9  269.73  5171.1  271.78  5273.6  274.26  5502.7  280.93
#Mann= 11 ,-1 , 0
  3937.2     .07       0    4111    .035       0  4171.3     .07       0
  4479.4     .12       0  4532.4     .07       0  4840.8     .12       0
  4860.4     .07       0  4990.7     .12       0  5077.8     .05       0
  5083.5     .12       0  5273.6     .07       0
Bank Sta=5077.8,5083.5
XS Rating Curve= 0 ,0
Exp/Cntr=0.3,0.1

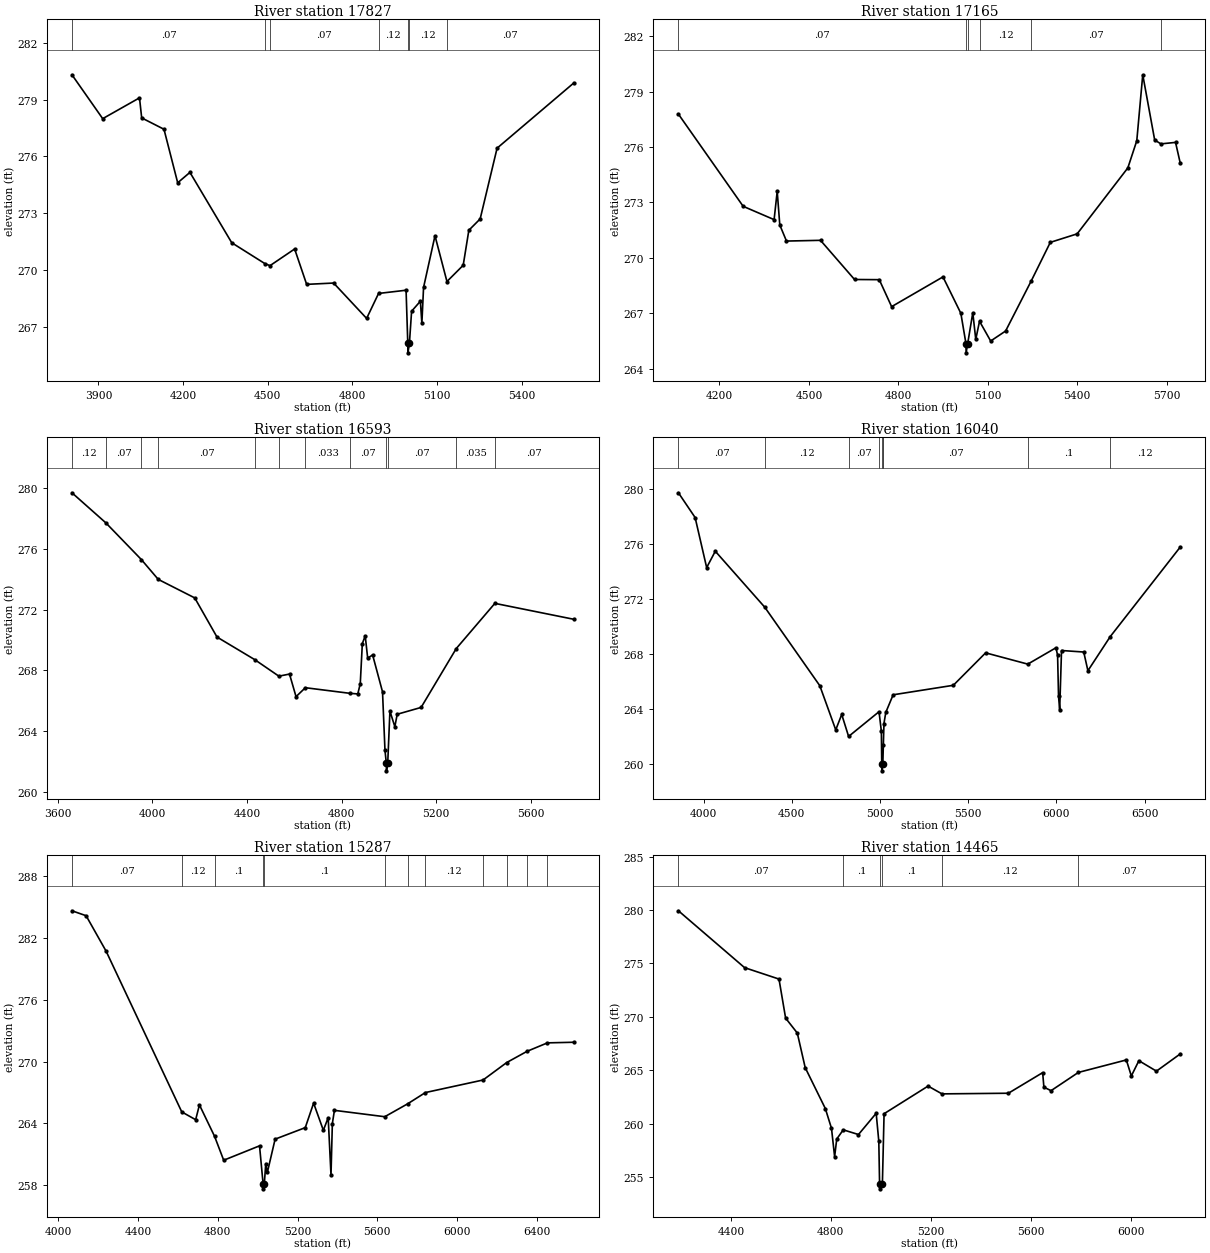
Type RM Length L Ch R = 1 ,17827   ,662,662,662
BEGIN DESCRIPTION:
B19919
END DESCRIPTION:
XS GIS Cut Line= 3
      2405289.66     13630397.57      2405714.06     13629220.19
      2405693.53     13628693.12
#Sta/Elev= 30
    3806  280.31    3915  277.99  4045.4  279.09  4053.2  278.03  4132.2  277.43
  4180.8   274.6  4224.2  275.15  4372.4  271.43  4490.7  270.32  4508.1  270.22
  4595.3   271.1  4637.9  269.23  4733.5   269.3  4850.5  267.43  4892.8  268.75
  4990.3  268.92  4996.4  266.11  4996.9  265.61  5002.1  266.11  5009.9  267.81
    5041  268.34  5046.3  267.17  5052.3  269.07  5092.8   271.8  5135.2  269.38
  5192.8  270.24  5212.8  272.09  5252.9  272.69  5312.9  276.43    5585  279.88
#Mann= 7 ,-1 , 0
    3806     .07       0  4490.7     .12       0  4508.1     .07       0
  4892.8     .12       0  4996.4     .05       0  5002.1     .12       0
  5135.2     .07       0
Bank Sta=4996.4,5002.1
XS Rating Curve= 0 ,0
Exp/Cntr=0.3,0.1

Type RM Length L Ch R = 1 ,17165   ,572,572,572
BEGIN DESCRIPTION:
B19918
END DESCRIPTION:
XS GIS Cut Line= 3
      2405768.83      13630534.4      2405974.17     13629788.33
      2405981.01     13628878.97
#Sta/Elev= 30
  4062.4  277.78  4279.6  272.79  4383.3  272.07  4393.7   273.6  4402.4  271.78
  4424.8  270.91  4538.9  270.95    4653  268.83    4736  268.82  4777.4  267.36
  4949.6  268.97  5009.6     267  5026.7  265.36  5027.2  264.86  5032.5  265.36
  5049.6  267.03  5059.6  265.59  5072.2  266.57  5109.6   265.5  5159.6  266.04
  5246.2  268.77  5309.6  270.84  5399.6   271.3  5569.6  274.87  5599.6  276.34
  5619.6  279.91  5659.6  276.38  5680.4  276.17  5729.6  276.25  5745.6  275.11
#Mann= 6 ,-1 , 0
  4062.4     .07       0  5026.7     .05       0  5032.5     .07       0
  5072.2     .12       0  5246.2     .07       0  5680.4    .063       0
Bank Sta=5026.7,5032.5
XS Rating Curve= 0 ,0
Exp/Cntr=0.3,0.1

Type RM Length L Ch R = 1 ,16593   ,553,553,553
BEGIN DESCRIPTION:
PANTHER BRANCH 24.0
END DESCRIPTION:
XS GIS Cut Line= 3
      2406035.77     13630952.02      2406432.79      13629630.9
      2406494.39     13628891.65
#Sta/Elev= 30
  3660.1   279.7  3803.2  277.72  3953.3   275.3  4024.9  273.99  4179.1  272.77
  4273.1  270.19  4432.7   268.7  4534.7  267.61  4579.6  267.75  4607.2  266.26
  4646.6  266.85  4834.8  266.48  4868.2  266.44  4878.7  267.12  4887.4  269.76
  4899.6  270.27    4910   268.8  4930.9  269.01  4972.7  266.58  4983.1  262.73
  4988.8  261.87  4989.3  261.37  4994.7  261.87    5004  265.31  5024.8  264.28
  5034.8   265.1  5135.8  265.55  5284.3  269.43  5447.6  272.41  5781.4  271.36
#Mann= 12 ,-1 , 0
  3660.1     .12       0  3803.2     .07       0  3953.3    .035       0
  4024.9     .07       0  4432.7     .12       0  4534.7     .07       0
  4646.6    .033       0  4834.8     .07       0  4988.8     .05       0
  4994.7     .07       0  5284.3    .035       0  5447.6     .07       0
Bank Sta=4988.8,4994.7
XS Rating Curve= 0 ,0
Exp/Cntr=0.3,0.1

Type RM Length L Ch R = 1 ,16040   ,753,753,753
BEGIN DESCRIPTION:
PANTHER BRANCH 23.0
END DESCRIPTION:
XS GIS Cut Line= 3
      2406597.07     13630856.17      2406939.32     13629644.59
      2407419.38      13628133.3
#Sta/Elev= 30
  3857.8  279.71  3952.5  277.91  4017.9  274.27  4066.8  275.46  4347.1  271.39
  4659.2  265.68  4749.5  262.47  4783.4  263.59  4822.4  261.99  4994.8  263.79
  5008.1  262.36  5010.2  259.99  5010.7  259.49  5016.3  259.99  5019.3  261.35
  5022.8  262.93  5033.2  263.74  5074.8  265.02  5415.9  265.71    5599  268.07
  5837.9  267.25  5997.7  268.44  6006.9  267.89  6012.2  264.93  6018.7  263.92
  6029.2  268.24  6155.1  268.13  6178.7  266.77  6305.2  269.25  6702.5  275.77
#Mann= 9 ,-1 , 0
  3857.8     .07       0  4347.1     .12       0  4822.4     .07       0
  4994.8    .035       0  5010.2    .035       0  5016.3    .035       0
  5019.3     .07       0  5837.9      .1       0  6305.2     .12       0
Bank Sta=5010.2,5016.3
XS Rating Curve= 0 ,0
Exp/Cntr=0.3,0.1

Type RM Length L Ch R = 1 ,15287   ,822,822,822
BEGIN DESCRIPTION:
PANTHER BRANCH 22.0
END DESCRIPTION:
XS GIS Cut Line= 3
      2407130.99     13630869.82      2407411.63     13629884.16
      2407840.57     13628454.98
#Sta/Elev= 30
  4068.6  284.66  4139.6  284.18    4240  280.73  4619.3  265.11    4689  264.35
  4707.9  265.79  4783.7  262.74  4829.6  260.41  5009.3  261.81  5027.1  258.13
  5027.6  257.63  5033.3  258.13  5040.6  260.08  5048.4  259.22  5087.4  262.46
  5238.7  263.58  5280.5  265.96  5329.4  263.32  5353.6  264.55  5367.7  258.97
  5374.5  263.98  5384.9  265.26  5637.3  264.64  5751.7  265.89  5841.2  266.99
  6130.3  268.21  6249.1  269.91  6351.1     271  6453.1  271.82  6585.6  271.88
#Mann= 12 ,-1 , 0
  4068.6     .07       0  4619.3     .12       0  4783.7      .1       0
  5027.1     .05       0  5033.3      .1       0  5637.3     .12       0
  5751.7     .07       0  5841.2     .12       0  6130.3     .07       0
  6249.1     .12       0  6351.1    .035       0  6453.1     .07       0
Bank Sta=5027.1,5033.3
XS Rating Curve= 0 ,0
Exp/Cntr=0.3,0.1

Type RM Length L Ch R = 1 ,14465   ,552,552,552
BEGIN DESCRIPTION:
PANTHER BRANCH 21.0
END DESCRIPTION:
XS GIS Cut Line= 3
      2407705.96      13631027.3       2408000.3     13630130.58
      2408102.95     13629069.83
#Sta/Elev= 30
  4189.9  279.94  4454.8  274.61  4592.6  273.54  4619.1  269.88  4665.9  268.48
  4697.5  265.24  4778.2   261.4  4802.8  259.55  4815.3  256.89  4823.8  258.55
  4849.9  259.41  4910.8  258.97  4981.7  260.96  4992.2  258.34  4995.3  254.38
  4995.8  253.88  5006.6  254.38  5013.3  260.92  5189.5  263.51  5245.1  262.78
    5511  262.84  5648.2  264.77  5653.2  263.41  5681.8  263.08  5791.2  264.79
  5983.2  265.96  6003.3  264.46  6033.5  265.89  6103.8  264.91  6199.4  266.53
#Mann= 6 ,-1 , 0
  4189.9     .07       0  4849.9      .1       0  4995.3     .05       0
  5006.6      .1       0  5245.1     .12       0  5791.2     .07       0
Bank Sta=4995.3,5006.6
XS Rating Curve= 0 ,0
Exp/Cntr=0.3,0.1

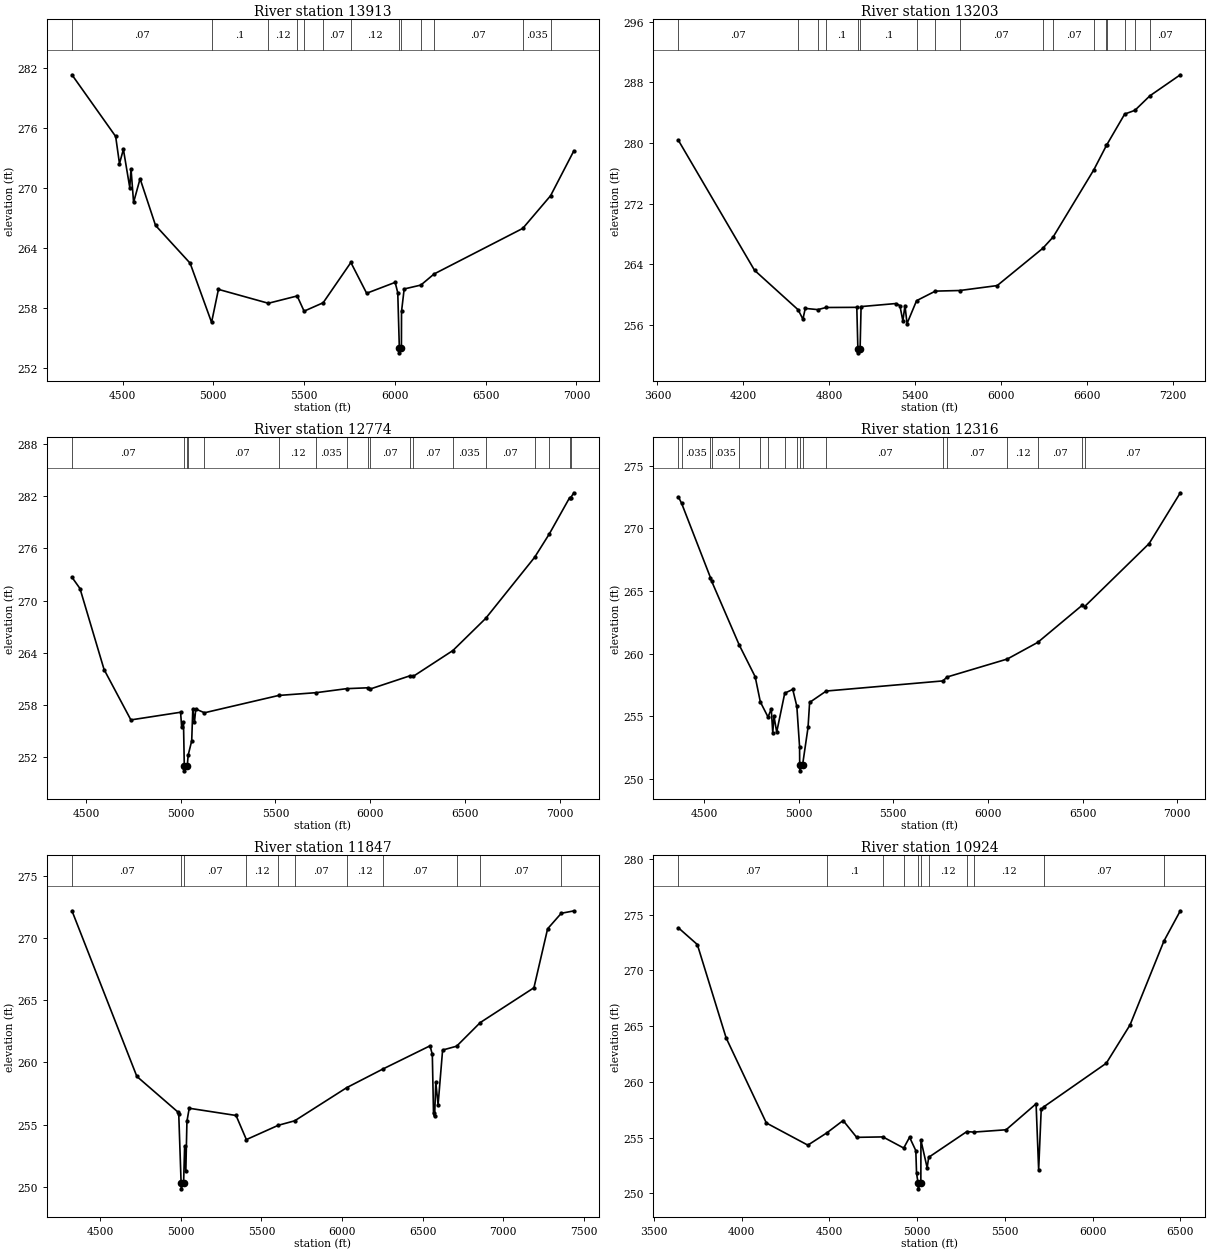
Type RM Length L Ch R = 1 ,13913   ,710,710,710
BEGIN DESCRIPTION:
PANTHER BRANCH 20.0
END DESCRIPTION:
XS GIS Cut Line= 3
      2407774.98     13631075.02      2408520.52     13630260.64
      2409820.56     13629227.45
#Sta/Elev= 30
  4221.4  281.34  4462.2  275.17  4483.2  272.45  4504.8  273.88  4539.9  270.05
  4546.8  271.92  4560.9  268.57  4596.7  270.94  4681.8  266.27  4872.3  262.49
  4990.5  256.57  5028.3  259.87  5303.3  258.48    5462  259.21  5500.1  257.69
  5605.1  258.53  5757.8  262.56  5844.7  259.48  6001.7  260.57  6016.1  259.54
  6024.8  254.02  6025.3  253.52  6036.2  254.02  6036.9  257.66  6051.4  259.91
  6143.3   260.3  6216.2  261.41  6704.6  265.97  6857.9  269.24  6986.1  273.73
#Mann= 13 ,-1 , 0
  4221.4     .07       0  4990.5      .1       0  5303.3     .12       0
    5462     .07       0  5500.1      .1       0  5605.1     .07       0
  5757.8     .12       0  6024.8     .05       0  6036.2     .12       0
  6143.3    .035       0  6216.2     .07       0  6704.6    .035       0
  6857.9     .07       0
Bank Sta=6024.8,6036.2
XS Rating Curve= 0 ,0
Exp/Cntr=0.3,0.1

Type RM Length L Ch R = 1 ,13203   ,429,429,429
BEGIN DESCRIPTION:
PANTHER BRANCH 19.0
END DESCRIPTION:
XS GIS Cut Line= 3
      2407824.96     13631125.02        2408925.       13630525.
      2410274.98     13628725.03
#Sta/Elev= 30
  3746.7  280.33  4277.8   263.2  4582.2  257.99  4615.8  256.75  4631.9  258.17
  4720.3  258.01  4776.5  258.29  4991.7  258.31  4999.3  252.81  4999.8  252.31
  5014.7  252.81  5021.6  258.41  5263.3  258.81  5292.4  258.55  5313.3  256.52
  5327.9  258.54  5342.4  256.17  5408.9  259.19  5540.2  260.45  5710.8  260.53
  5971.6  261.18  6289.6  266.09  6361.8  267.58  6645.8  276.44    6734  279.66
  6734.8  279.69  6861.5   283.8  6932.6  284.29  7037.6  286.21  7249.7  288.98
#Mann= 17 ,-1 , 0
  3746.7     .07       0  4582.2      .1       0  4720.3     .07       0
  4776.5      .1       0  4999.3     .05       0  5014.7      .1       0
  5408.9     .12       0  5540.2    .035       0  5710.8     .07       0
  6289.6    .035       0  6361.8     .07       0  6645.8     .12       0
    6734     .07       0  6734.8     .12       0  6861.5     .07       0
  6932.6     .12       0  7037.6     .07       0
Bank Sta=4999.3,5014.7
XS Rating Curve= 0 ,0
Exp/Cntr=0.3,0.1

Type RM Length L Ch R = 1 ,12774   ,458,458,458
BEGIN DESCRIPTION:
PANTHER BRANCH 18.0
END DESCRIPTION:
XS GIS Cut Line= 3
      2408625.03     13631324.97        2409025.       13630925.
      2410074.99     13629125.01
#Sta/Elev= 30
  4425.9  272.69  4468.3  271.39  4595.6  262.08    4737   256.3  4999.4  257.18
  5005.2  255.43  5014.7  256.05    5019  250.95  5019.5  250.45  5034.4  250.95
  5039.3  252.24  5058.1   253.9  5063.9  257.56  5072.6  256.05  5079.6  257.55
  5125.4  257.12  5517.3  259.11  5715.5  259.43    5876  259.89  5988.5  259.99
    5999  259.84  6209.4  261.36  6228.7  261.32  6436.9  264.27  6609.5  267.95
  6868.4  274.98    6946  277.67  7053.1  281.83  7058.2  281.81  7075.4  282.39
#Mann= 18 ,-1 , 0
  4425.9     .07       0    5019     .05       0  5034.4     .07       0
  5039.3     .12       0  5125.4     .07       0  5517.3     .12       0
  5715.5    .035       0    5876     .07       0  5988.5     .12       0
    5999     .07       0  6209.4     .12       0  6228.7     .07       0
  6436.9    .035       0  6609.5     .07       0  6868.4     .12       0
    6946     .07       0  7053.1     .12       0  7058.2     .07       0
Bank Sta=5019,5034.4
XS Rating Curve= 0 ,0
Exp/Cntr=0.3,0.1

Type RM Length L Ch R = 1 ,12316   ,469,469,469
BEGIN DESCRIPTION:
PANTHER BRANCH 17.0
END DESCRIPTION:
XS GIS Cut Line= 3
      2408774.96     13631675.03        2409275.       13631275.
      2410174.99     13629475.02
#Sta/Elev= 30
  4364.2  272.52  4381.3     272  4533.5  266.07  4539.3   265.8  4685.7  260.68
    4770  258.14  4797.2  256.13  4837.9  254.92  4854.9  255.57  4862.9  253.66
  4869.3  254.98  4883.7  253.72  4926.2  256.83  4968.5  257.13  4990.1  255.78
  5004.6  252.54  5005.2  251.12  5005.7  250.62  5020.7  251.12  5049.3  254.09
  5057.7  256.09  5145.6     257  5762.3  257.81  5783.8  258.12  6102.6  259.56
  6263.5  260.89    6497  263.84    6511  263.75  6852.1  268.79    7017  272.85
#Mann= 18 ,-1 , 0
  4364.2     .05       0  4381.3    .035       0  4533.5     .05       0
  4539.3    .035       0  4685.7     .07       0  4797.2    .035       0
  4837.9     .07       0  4926.2    .035       0  4990.1      .1       0
  5005.2     .05       0  5020.7      .1       0  5145.6     .07       0
  5762.3    .035       0  5783.8     .07       0  6102.6     .12       0
  6263.5     .07       0    6497    .035       0    6511     .07       0
Bank Sta=5005.2,5020.7
XS Rating Curve= 0 ,0
Exp/Cntr=0.3,0.1

Type RM Length L Ch R = 1 ,11847   ,923,923,923
BEGIN DESCRIPTION:
PANTHER BRANCH 16.0
END DESCRIPTION:
XS GIS Cut Line= 3
        2409175.     13632275.01        2409475.       13631675.
      2411275.03     13630024.97
#Sta/Elev= 30
  4324.9  272.19  4727.4  258.87  4981.8  256.01  4987.3  255.82  5001.8  250.33
  5002.3  249.83  5017.4  250.33  5023.8  253.27  5031.2  251.28    5038  255.26
  5052.2  256.31  5342.6  255.73  5406.6  253.79  5604.4  254.94  5706.2   255.3
  6029.3  257.97  6252.5  259.46  6545.6  261.33  6559.8  260.64  6567.2  255.91
    6574  255.65  6581.4   258.4  6595.6  256.59  6623.6  260.99  6710.5   261.3
  6857.1   263.2    7190     266  7274.8  270.74  7359.6  271.99  7437.6  272.18
#Mann= 11 ,-1 , 0
  4324.9     .07       0  5001.8     .05       0  5017.4     .07       0
  5406.6     .12       0  5604.4    .035       0  5706.2     .07       0
  6029.3     .12       0  6252.5     .07       0  6710.5     .12       0
  6857.1     .07       0  7359.6    .035       0
Bank Sta=5001.8,5017.4
XS Rating Curve= 0 ,0
Exp/Cntr=0.3,0.1

Type RM Length L Ch R = 1 ,10924   ,433,433,433
BEGIN DESCRIPTION:
PANTHER BRANCH 15.0
END DESCRIPTION:
XS GIS Cut Line= 3
      2409175.03     13632324.98        2410275.       13631525.
      2411474.99     13630625.01
#Sta/Elev= 30
  3639.6  273.82  3747.4  272.32  3911.6  263.94  4140.7  256.31  4377.2  254.32
  4485.1  255.42  4578.1  256.53  4655.4  255.02  4804.7  255.06  4923.5  254.06
  4956.8  255.03  4992.4  253.83  4996.6  251.81  5005.4   250.9  5005.9   250.4
  5021.1   250.9  5021.6  254.76    5057  252.29  5065.8  253.23  5283.3  255.54
  5321.6  255.49    5507   255.7  5677.8  258.03  5692.4  252.11    5707  257.53
  5720.9  257.75  6077.8  261.67  6213.3  265.11  6406.2  272.63  6499.7  275.35
#Mann= 11 ,-1 , 0
  3639.6     .07       0  4485.1      .1       0  4804.7    .035       0
  4923.5      .1       0  5005.4     .05       0  5021.1      .1       0
  5065.8     .12       0  5283.3     .07       0  5321.6     .12       0
  5720.9     .07       0  6406.2    .035       0
Bank Sta=5005.4,5021.1
XS Rating Curve= 0 ,0
Exp/Cntr=0.3,0.1