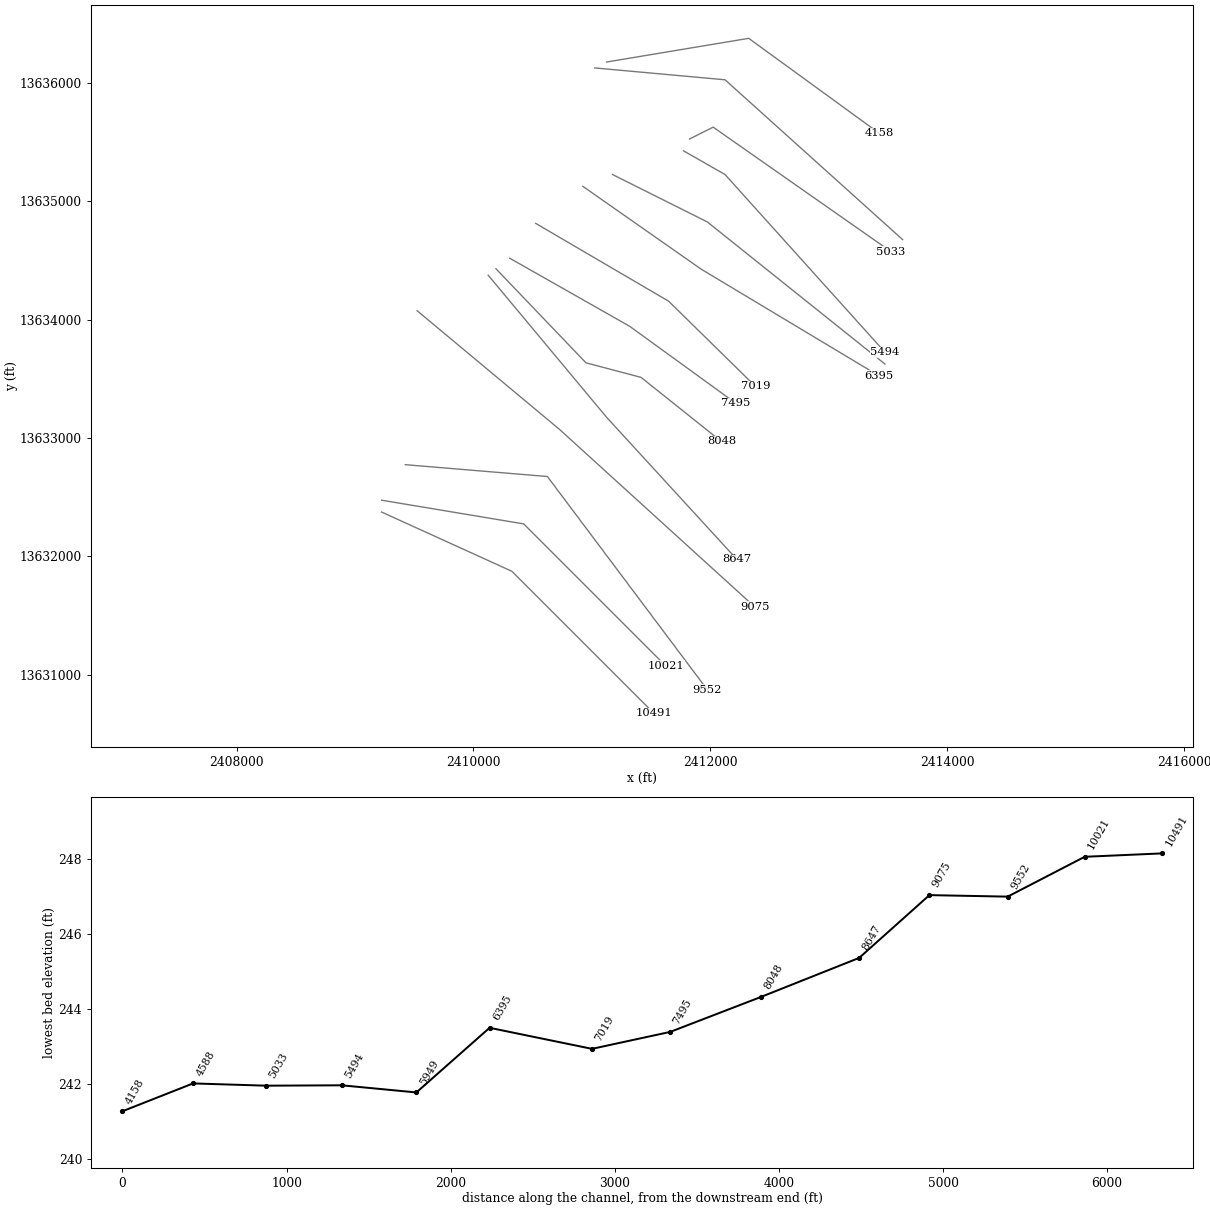
HEC-RAS study PANTHER BRANCH.prj: PANTHER BRANCH Base Level Engineering

--- PANTHER BRANCH.g01 (geometry) --- (continued)

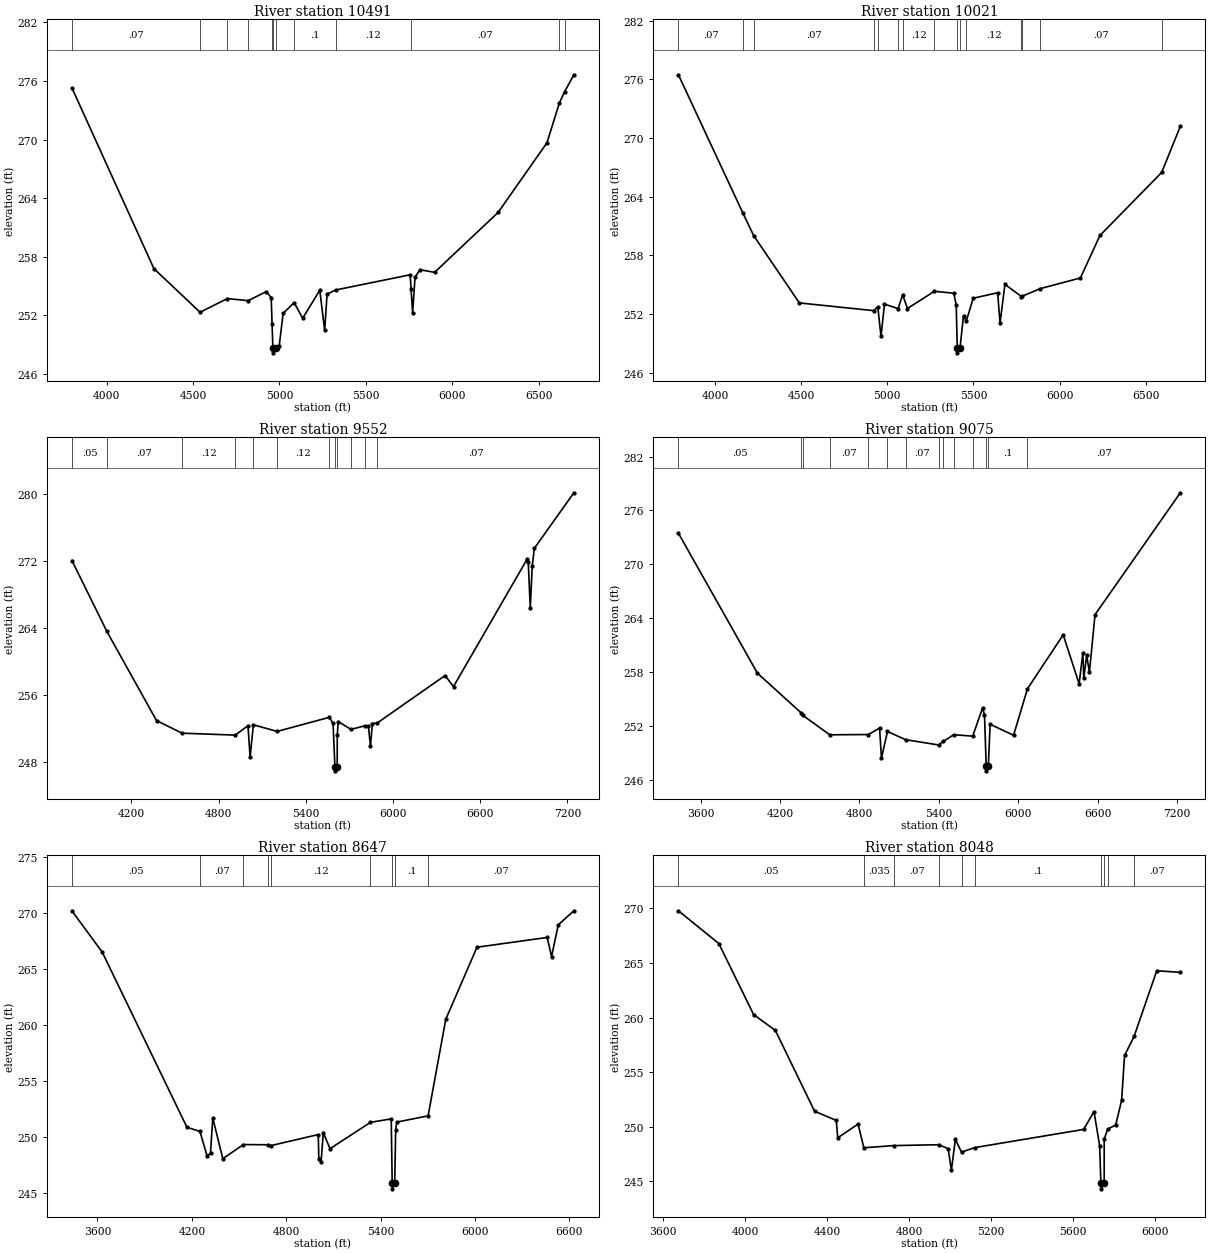
Type RM Length L Ch R = 1 ,10491   ,470,470,470
BEGIN DESCRIPTION:
PANTHER BRANCH 14.0
END DESCRIPTION:
XS GIS Cut Line= 3
      2409225.01       13632375.        2410325.       13631875.
      2411525.03     13630674.97
#Sta/Elev= 30
    3799  275.29  4273.5  256.77  4540.7   252.3  4698.3   253.7  4819.4  253.49
  4923.8  254.41  4952.4  253.81  4957.5  251.09  4962.1  248.64  4962.6  248.14
  4977.8  248.64  4998.5  248.81  5021.4  252.18  5085.4  253.29  5134.6  251.68
  5233.6  254.56  5261.9  250.45    5276  254.16  5325.1  254.58  5756.8  256.14
    5762   254.7    5771  252.22  5785.1  255.89  5813.4  256.66  5898.3  256.39
  6265.9  262.53  6548.8  269.67  6620.1  273.73  6651.2  274.91  6704.4  276.64
#Mann= 12 ,-1 , 0
    3799     .07       0  4540.7      .1       0  4698.3     .07       0
  4819.4      .1       0  4957.5    .035       0  4962.1    .035       0
  4977.8    .035       0  5085.4      .1       0  5325.1     .12       0
    5762     .07       0  6620.1    .035       0  6651.2     .07       0
Bank Sta=4962.1,4977.8
XS Rating Curve= 0 ,0
Exp/Cntr=0.3,0.1

Type RM Length L Ch R = 1 ,10021   ,469,469,469
BEGIN DESCRIPTION:
PANTHER BRANCH 13.0
END DESCRIPTION:
XS GIS Cut Line= 3
      2409224.98       13632475.        2410425.       13632275.
      2411624.98     13631075.02
#Sta/Elev= 30
  3787.5  276.46    4161  262.36  4224.2  260.03  4489.6  253.15  4921.3  252.36
  4945.1  252.74  4963.5  249.72  4983.8  253.03    5063  252.57    5089  253.99
  5117.2  252.58  5273.4  254.34  5385.9  254.14  5400.1  252.95  5406.3  248.55
  5406.8  248.05  5422.1  248.55  5442.5  251.85  5458.4  251.28    5499  253.63
  5640.5  254.19  5654.6   251.1  5682.9  255.05  5778.9   253.8  5779.8  253.81
  5887.6  254.61  6121.3   255.7  6234.4  260.04  6592.8  266.48  6701.1  271.19
#Mann= 15 ,-1 , 0
  3787.5     .07       0    4161     .05       0  4224.2     .07       0
  4921.3      .1       0  4945.1     .12       0    5063    .035       0
    5089     .12       0  5273.4      .1       0  5406.3     .05       0
  5422.1      .1       0  5458.4     .12       0  5778.9     .07       0
  5779.8     .12       0  5887.6     .07       0  6592.8    .035       0
Bank Sta=5406.3,5422.1
XS Rating Curve= 0 ,0
Exp/Cntr=0.3,0.1

Type RM Length L Ch R = 1 ,9552    ,477,477,477
BEGIN DESCRIPTION:
PANTHER BRANCH 12.0
END DESCRIPTION:
XS GIS Cut Line= 3
      2409424.99       13632775.        2410625.       13632675.
      2411975.02     13630874.98
#Sta/Elev= 30
  3790.3  272.06  4030.6  263.61  4372.3  252.99  4547.6  251.48  4914.1  251.25
  5001.8  252.37  5016.3  248.64  5039.1  252.48  5201.9  251.69  5561.7  253.37
  5587.2  252.65  5600.1  247.49  5600.6  246.99  5615.9  247.49  5616.3  251.23
  5622.6  252.87  5710.7  251.93  5804.6  252.35  5830.9   252.3  5844.5   249.9
    5858  252.63  5891.8   252.7    6358  258.35  6416.3  257.04  6922.6  272.22
  6930.9  271.83  6944.5  266.41    6958  271.37  6972.6  273.52  7244.5  280.14
#Mann= 12 ,-1 , 0
  3790.3     .05       0  4030.6     .07       0  4547.6     .12       0
  4914.1      .1       0  5039.1    .035       0  5201.9     .12       0
  5561.7      .1       0  5600.1     .05       0  5615.9      .1       0
  5710.7     .12       0  5804.6      .1       0  5891.8     .07       0
Bank Sta=5600.1,5615.9
XS Rating Curve= 0 ,0
Exp/Cntr=0.3,0.1

Type RM Length L Ch R = 1 ,9075    ,428,428,428
BEGIN DESCRIPTION:
PANTHER BRANCH 11.0
END DESCRIPTION:
XS GIS Cut Line= 3
      2409525.02     13634074.98        2410725.       13633075.
      2412374.98     13631575.02
#Sta/Elev= 30
  3433.1  273.47  4029.9   257.9  4358.1  253.51  4373.4   253.2  4576.8  251.04
  4868.4  251.07  4952.8  251.79  4967.1  248.45  5012.6  251.41  5149.2   250.5
  5398.2  249.91  5435.8  250.31    5513  251.05  5656.4  250.89  5731.3  254.04
  5745.5  253.24  5758.6  247.53  5759.1  247.03  5774.4  247.53  5788.1  252.21
  5965.1  250.99  6070.1  256.16  6340.2  262.17  6460.4  256.71  6488.8  260.18
  6495.6  257.32  6517.2  259.89  6538.1     258  6580.7  264.41    7225  277.97
#Mann= 14 ,-1 , 0
  3433.1     .05       0  4358.1     .07       0  4373.4     .05       0
  4576.8     .07       0  4868.4     .12       0  5012.6    .035       0
  5149.2     .07       0  5398.2     .12       0  5435.8     .07       0
    5513     .12       0  5656.4      .1       0  5758.6     .05       0
  5774.4      .1       0  6070.1     .07       0
Bank Sta=5758.6,5774.4
XS Rating Curve= 0 ,0
Exp/Cntr=0.3,0.1

Type RM Length L Ch R = 1 ,8647    ,599,599,599
BEGIN DESCRIPTION:
PANTHER BRANCH 10.0
END DESCRIPTION:
XS GIS Cut Line= 3
        2410125.       13634375.        2411125.       13633175.
      2412224.98     13631975.03
#Sta/Elev= 30
  3437.9  270.15  3629.9  266.48  4168.8  250.85  4251.3  250.48    4297  248.28
  4318.5  248.55  4332.8  251.69  4396.6  248.05  4527.7  249.31  4686.9  249.29
  4700.4  249.21  5003.3   250.2    5007  248.01  5021.2  247.75  5035.4  250.38
    5078  248.94  5335.1  251.29    5467   251.6  5473.3  245.86  5473.8  245.36
  5489.2  245.86  5495.4  250.61  5502.2  251.31  5701.5  251.87  5813.9  260.49
  6012.1  266.91    6458  267.78  6486.3  266.08  6528.9  268.91  6627.8  270.16
#Mann= 9 ,-1 , 0
  3437.9     .05       0  4251.3     .07       0  4527.7    .035       0
  4686.9     .07       0  4700.4     .12       0  5335.1      .1       0
  5473.3     .05       0  5489.2      .1       0  5701.5     .07       0
Bank Sta=5473.3,5489.2
XS Rating Curve= 0 ,0
Exp/Cntr=0.3,0.1

Type RM Length L Ch R = 1 ,8048    ,553,553,553
BEGIN DESCRIPTION:
B19917
END DESCRIPTION:
XS GIS Cut Line= 4
      2410190.72     13634429.25      2410950.51     13633635.24
      2411415.97     13633512.03       2412093.6     13632971.29
#Sta/Elev= 30
  3675.4  269.78  3872.5  266.78    4042  260.28  4148.3  258.82  4339.2  251.43
  4445.2  250.58  4452.4  248.99  4551.5  250.25  4579.5  248.08  4726.3  248.28
  4945.9  248.36  4990.7  247.99  5006.6  246.03  5025.7  248.85  5055.9  247.68
  5121.2   248.1  5651.2  249.76    5702  251.39  5729.2  248.28  5735.7  244.82
  5736.2  244.32  5751.6  244.82  5751.7  248.87  5768.3  249.78  5807.7  250.17
  5836.5  252.43  5850.9  256.53  5897.2  258.27  6007.9  264.29  6122.8  264.14
#Mann= 10 ,-1 , 0
  3675.4     .05       0  4579.5    .035       0  4726.3     .07       0
  4945.9      .1       0  5055.9     .12       0  5121.2      .1       0
  5735.7     .05       0  5751.6      .1       0  5768.3     .12       0
  5897.2     .07       0
Bank Sta=5735.7,5751.6
XS Rating Curve= 0 ,0
Exp/Cntr=0.3,0.1

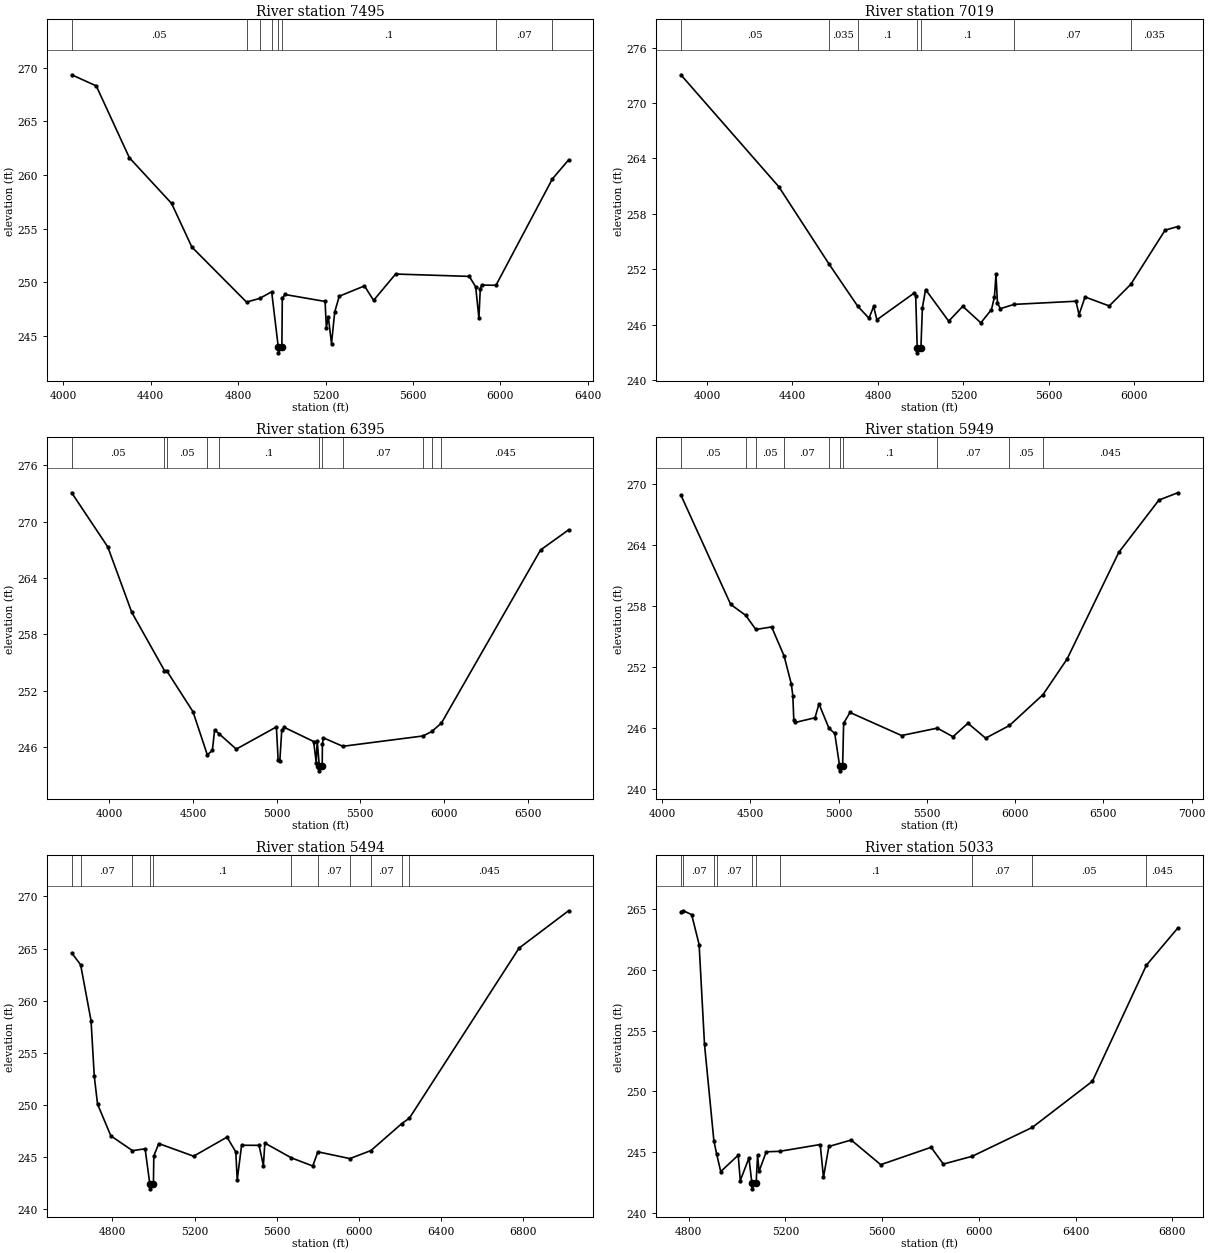
Type RM Length L Ch R = 1 ,7495    ,476,476,476
BEGIN DESCRIPTION:
B19916
END DESCRIPTION:
XS GIS Cut Line= 3
      2410307.06     13634518.25      2411320.14     13633943.26
       2412216.8     13633293.01
#Sta/Elev= 30
  4038.7  269.36  4151.1  268.32  4302.5  261.61  4495.8  257.34  4588.3  253.27
  4838.4  248.13  4898.1  248.47  4953.4  249.09  4983.8  243.89  4984.3  243.39
    5000  243.89    5002  248.47  5013.7  248.84  5197.7  248.19  5203.5  245.74
  5212.4  246.76  5227.1  244.25  5241.8  247.22  5262.7  248.68  5377.9  249.64
  5419.6  248.29  5520.2  250.75  5857.3  250.53  5886.6  249.55  5901.3  246.62
  5907.5  249.36  5913.7  249.72  5979.4   249.7  6237.5  259.64  6311.2   261.4
#Mann= 8 ,-1 , 0
  4038.7     .05       0  4838.4    .035       0  4898.1     .05       0
  4953.4      .1       0  4983.8     .05       0    5000      .1       0
  5979.4     .07       0  6237.5    .035       0
Bank Sta=4983.8,5000
XS Rating Curve= 0 ,0
Exp/Cntr=0.3,0.1

Type RM Length L Ch R = 1 ,7019    ,624,624,624
BEGIN DESCRIPTION:
B19915
END DESCRIPTION:
XS GIS Cut Line= 3
      2410526.08     13634812.61       2411648.7     13634155.46
      2412380.56     13633437.28
#Sta/Elev= 30
  3877.4  273.06  4335.8  260.94  4571.7  252.54  4705.2     248  4758.1  246.69
    4780  247.96  4795.2  246.52  4971.2  249.44    4977  249.11  4984.1  243.44
  4984.6  242.94  5001.3  243.44  5008.4  247.84  5023.3  249.79  5131.5  246.37
  5197.2  247.98    5282  246.19  5331.5  247.62  5345.6  248.98  5352.8  251.43
  5359.8  248.29  5373.9  247.73  5437.8  248.19  5727.5  248.53  5741.6  247.07
  5769.9  248.99  5883.1  248.02  5983.9  250.36  6144.7  256.23  6203.6  256.62
#Mann= 7 ,-1 , 0
  3877.4     .05       0  4571.7    .035       0  4705.2      .1       0
  4984.1     .05       0  5001.3      .1       0  5437.8     .07       0
  5983.9    .035       0
Bank Sta=4984.1,5001.3
XS Rating Curve= 0 ,0
Exp/Cntr=0.3,0.1

Type RM Length L Ch R = 1 ,6395    ,446,446,446
BEGIN DESCRIPTION:
PANTHER BRANCH 7.0
END DESCRIPTION:
XS GIS Cut Line= 3
      2410925.01     13635124.99        2411925.       13634425.
      2413424.98     13633525.01
#Sta/Elev= 30
  3774.7  273.07  3990.5  267.31  4133.5  260.37  4329.2  254.16  4341.7  254.17
  4499.7  249.79  4585.4   245.2  4615.6  245.67  4629.1  247.86  4653.9  247.47
  4758.6  245.81  4998.3  248.17  5008.9  244.61  5018.7  244.51  5030.3   247.8
  5045.9  248.12  5220.8  246.62  5236.4  244.38  5242.2   246.7    5255     244
  5255.5   243.5  5272.2     244  5273.3  246.31  5279.1  247.01  5395.4  246.11
  5875.4  247.21  5927.8  247.69  5984.8  248.58  6577.5  266.99  6744.6  269.12
#Mann= 11 ,-1 , 0
  3774.7     .05       0  4329.2    .035       0  4341.7     .05       0
  4585.4     .07       0  4653.9      .1       0    5255     .05       0
  5272.2      .1       0  5395.4     .07       0  5875.4     .05       0
  5927.8     .07       0  5984.8    .045       0
Bank Sta=5255,5272.2
XS Rating Curve= 0 ,0
Exp/Cntr=0.3,0.1

Type RM Length L Ch R = 1 ,5949    ,455,455,455
BEGIN DESCRIPTION:
PANTHER BRANCH 6.0
END DESCRIPTION:
XS GIS Cut Line= 3
      2411175.03     13635224.99        2411975.       13634825.
      2413474.97     13633625.02
#Sta/Elev= 30
  4105.7  268.96    4388  258.18  4473.2   257.1  4530.4  255.71    4620  255.96
  4690.7   253.1  4731.8  250.32  4740.2  249.18  4745.7   246.8  4754.1  246.55
  4865.9  247.01  4888.3  248.38  4945.1  245.97  4977.7  245.47  5005.1  242.28
  5005.6  241.78  5022.4  242.28  5028.1  246.47  5064.1  247.53  5356.3  245.26
  5559.1  245.99  5647.6  245.14  5732.5  246.47  5832.5     245  5967.8  246.25
  6158.3   249.3  6294.3   252.8  6587.3  263.31  6814.6  268.46    6921  269.18
#Mann= 10 ,-1 , 0
  4105.7     .05       0  4473.2    .035       0  4530.4     .05       0
  4690.7     .07       0  4945.1      .1       0  5005.1     .05       0
  5022.4      .1       0  5559.1     .07       0  5967.8     .05       0
  6158.3    .045       0
Bank Sta=5005.1,5022.4
XS Rating Curve= 0 ,0
Exp/Cntr=0.3,0.1

Type RM Length L Ch R = 1 ,5494    ,461,461,461
BEGIN DESCRIPTION:
PANTHER BRANCH 5.0
END DESCRIPTION:
XS GIS Cut Line= 3
        2411775.       13635425.        2412125.       13635225.
      2413475.03     13633724.96
#Sta/Elev= 30
  4601.5  264.59  4645.1  263.45  4695.8  258.09  4711.6  252.75  4727.5  250.09
  4792.3  247.05  4897.8  245.63  4959.3  245.81    4982  242.47  4982.5  241.97
  4999.8  242.47  5001.7  245.13  5025.9  246.31  5195.6   245.1  5358.5  246.93
  5401.1  245.51  5408.2  242.84  5429.5  246.15  5514.7  246.14  5535.7   244.2
  5542.8  246.36    5672  244.94  5776.3  244.16  5801.2  245.52  5957.3  244.87
  6059.6  245.64  6210.4  248.23  6247.3  248.75  6781.6  265.05  7022.7  268.63
#Mann= 11 ,-1 , 0
  4601.5    .035       0  4645.1     .07       0  4897.8      .1       0
    4982     .05       0  4999.8      .1       0    5672     .12       0
  5801.2     .07       0  5957.3     .05       0  6059.6     .07       0
  6210.4     .05       0  6247.3    .045       0
Bank Sta=4982,4999.8
XS Rating Curve= 0 ,0
Exp/Cntr=0.3,0.1

Type RM Length L Ch R = 1 ,5033    ,445,445,445
BEGIN DESCRIPTION:
PANTHER BRANCH 4.0
END DESCRIPTION:
XS GIS Cut Line= 3
      2411824.99       13635525.        2412025.       13635625.
        2413525.       13634575.
#Sta/Elev= 30
  4767.8  264.78  4778.5  264.86  4812.5  264.54  4843.3  262.08  4865.6  253.85
  4904.4  245.91  4915.9  244.82  4932.7  243.38  5004.9  244.73  5013.6  242.64
  5049.4   244.5  5061.4  242.46  5061.9  241.96  5079.2  242.46  5085.1  244.72
  5091.2   243.4  5120.9  245.01  5176.8  245.05  5344.1  245.61  5357.6   242.9
  5379.8  245.45  5472.3  245.98  5594.3  243.95  5802.7  245.38  5853.3     244
  5972.5  244.64  6221.2  247.02  6469.7  250.82  6693.1  260.38  6822.4  263.43
#Mann= 10 ,-1 , 0
  4767.8    .035       0  4778.5     .07       0  4904.4      .1       0
  4915.9     .07       0  5061.4     .05       0  5079.2     .07       0
  5176.8      .1       0  5972.5     .07       0  6221.2     .05       0
  6693.1    .045       0
Bank Sta=5061.4,5079.2
XS Rating Curve= 0 ,0
Exp/Cntr=0.3,0.1

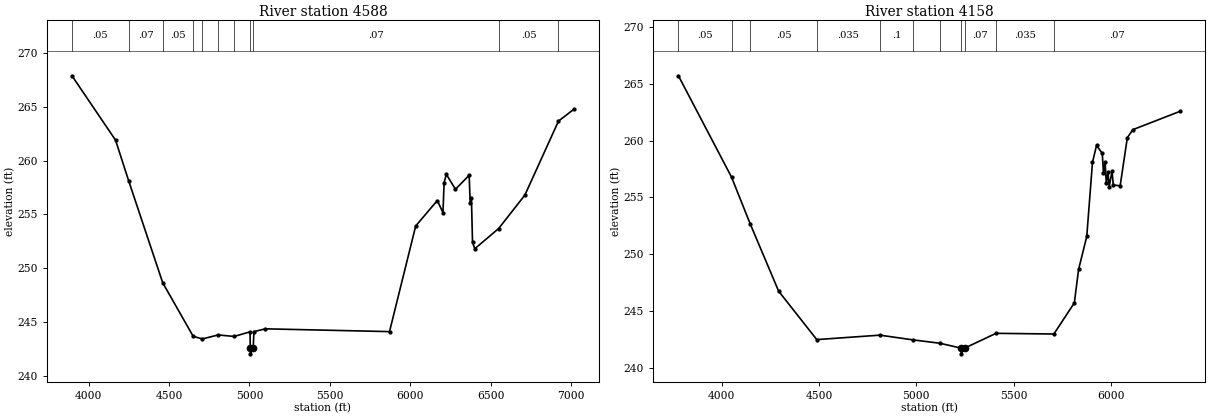
Type RM Length L Ch R = 1 ,4588    ,430,430,430
BEGIN DESCRIPTION:
PANTHER BRANCH 3.0
END DESCRIPTION:
XS GIS Cut Line= 3
      2411025.01       13636125.        2412125.       13636025.
      2413625.02     13634674.98
#Sta/Elev= 30
  3895.5  267.92  4166.6  261.93  4248.1  258.15  4460.2  248.64  4649.9  243.65
  4706.4  243.41  4805.4  243.78  4904.5  243.64  5003.4  244.07    5005  242.52
  5005.5  242.02  5022.8  242.52  5028.1  244.09  5099.1  244.35  5871.2  244.09
  6034.1  253.93  6168.6   256.3  6203.8  255.17  6210.9  257.97  6224.7  258.74
  6281.5  257.35  6366.7  258.65  6373.4  256.03  6380.9  256.53  6387.6   252.4
  6401.8  251.81  6550.1  253.69  6713.5  256.81  6922.5   263.7  7018.1   264.8
#Mann= 11 ,-1 , 0
  3895.5     .05       0  4248.1     .07       0  4460.2     .05       0
  4649.9    .035       0  4706.4     .05       0  4805.4    .035       0
  4904.5     .07       0    5005     .05       0  5022.8     .07       0
  6550.1     .05       0  6922.5    .045       0
Bank Sta=5005,5022.8
XS Rating Curve= 0 ,0
Exp/Cntr=0.3,0.1

Type RM Length L Ch R = 1 ,4158    ,431,431,431
BEGIN DESCRIPTION:
PANTHER BRANCH 2.0
END DESCRIPTION:
XS GIS Cut Line= 3
      2411125.03     13636175.01        2412325.       13636375.
      2413425.03     13635574.98
#Sta/Elev= 30
  3778.8  265.68  4051.4  256.79  4146.7  252.71  4293.3  246.78  4489.1  242.53
  4813.1  242.92  4985.4   242.5  5121.3  242.21  5230.2  241.78  5230.7  241.28
    5248  241.78  5409.5  243.08  5706.4  243.02  5811.4  245.75  5833.4   248.7
  5875.2  251.58  5904.5  258.08  5925.4  259.57  5954.8  258.87  5960.9  257.16
  5969.4  258.09  5975.6  256.23  5984.1   257.2  5990.3  255.95    6005  257.32
  6011.2  256.09  6046.7  256.03  6083.4  260.24  6111.6  260.95  6355.5  262.57
#Mann= 11 ,-1 , 0
  3778.8     .05       0  4051.4     .07       0  4146.7     .05       0
  4489.1    .035       0  4813.1      .1       0  4985.4    .035       0
  5121.3     .07       0  5230.2    .035       0    5248     .07       0
  5409.5    .035       0  5706.4     .07       0
Bank Sta=5230.2,5248
XS Rating Curve= 0 ,0
Exp/Cntr=0.3,0.1