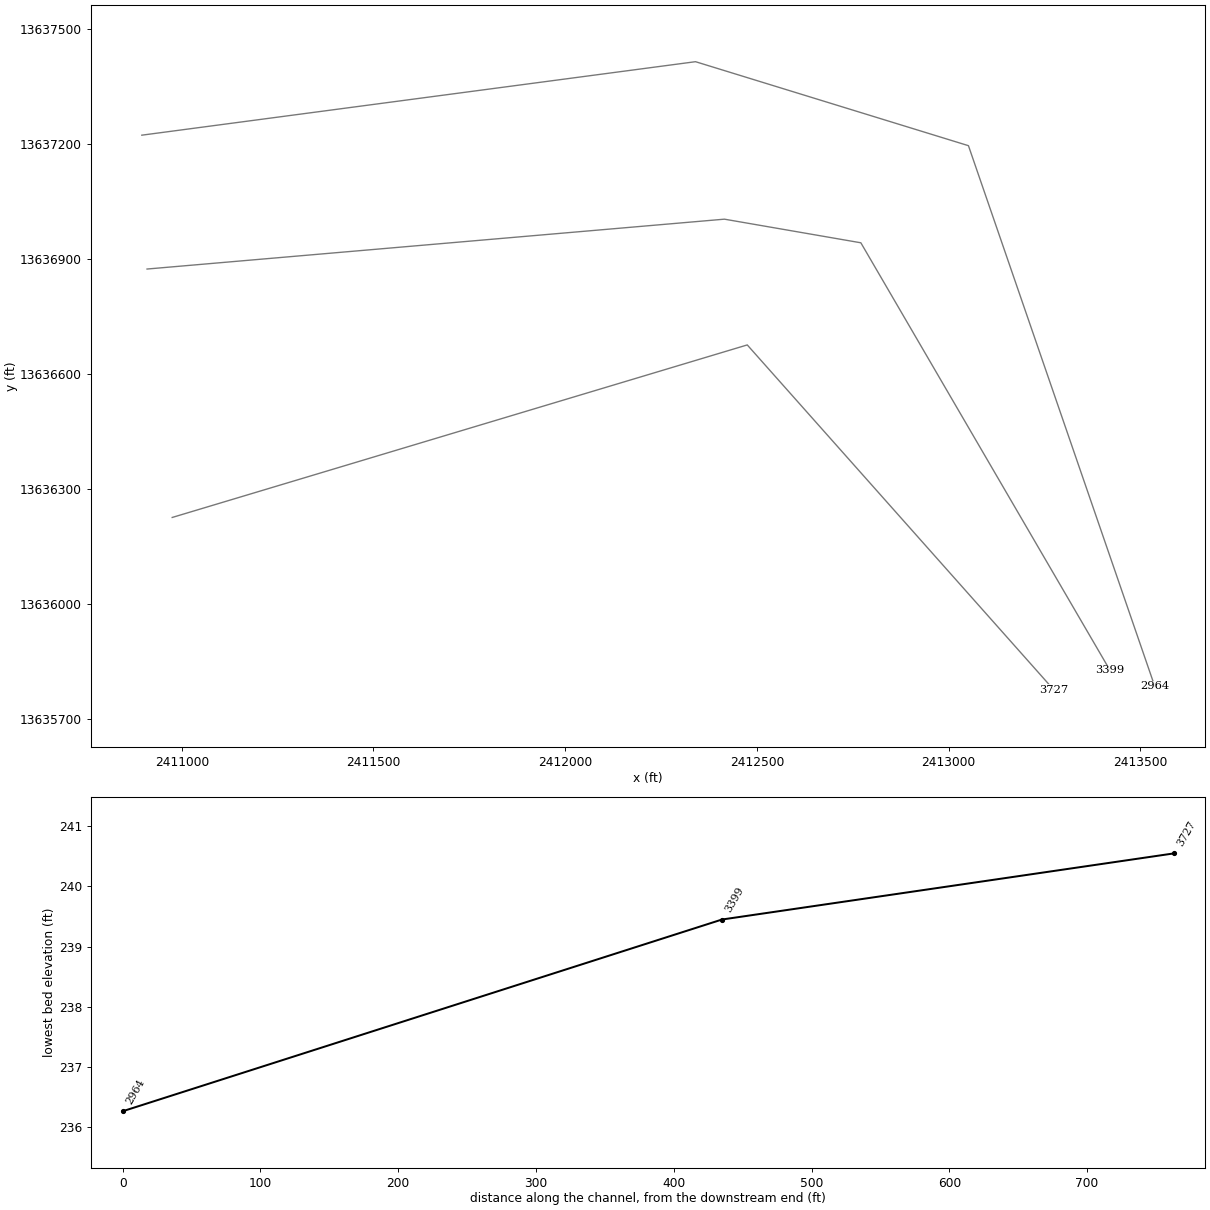
HEC-RAS study PANTHER BRANCH.prj: PANTHER BRANCH Base Level Engineering

--- PANTHER BRANCH.g01 (geometry) --- (continued)

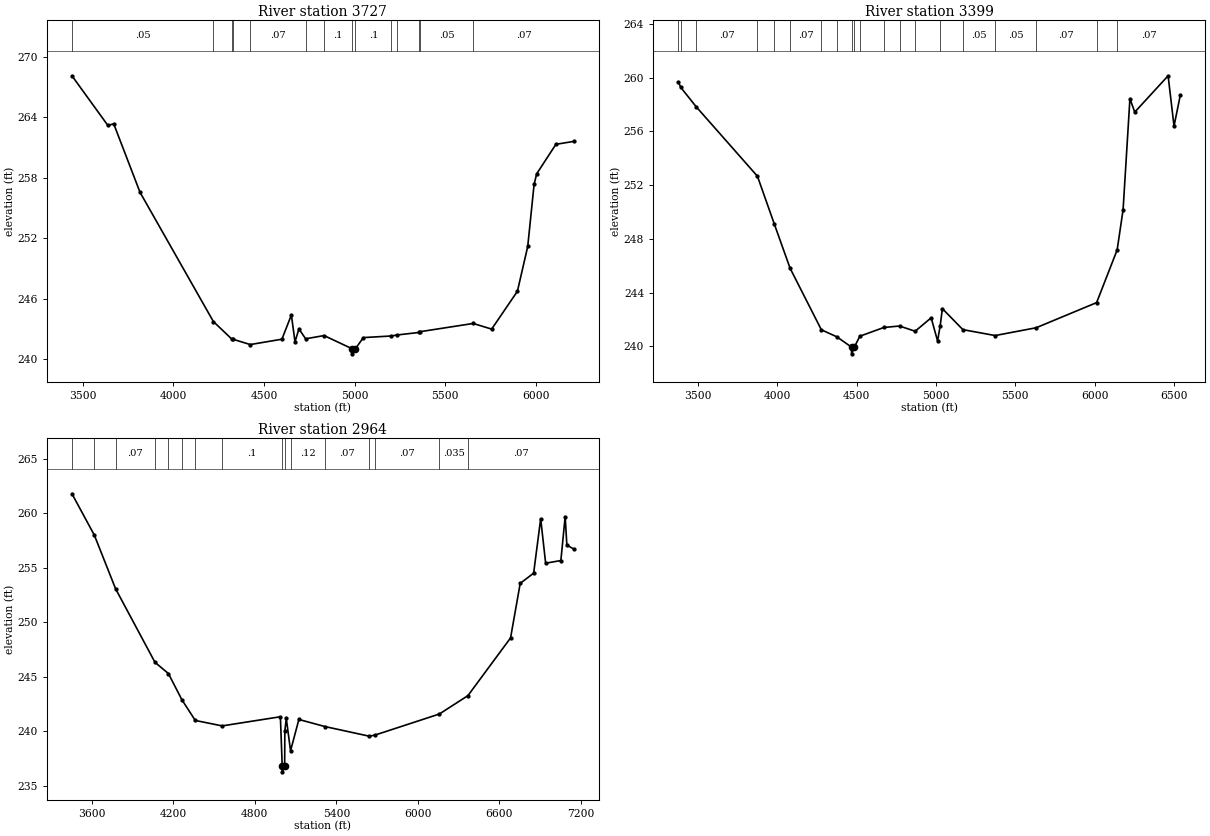
Type RM Length L Ch R = 1 ,3727    ,328,328,328
BEGIN DESCRIPTION:
PANTHER BRANCH 1.0
END DESCRIPTION:
XS GIS Cut Line= 3
      2410975.02     13636225.01        2412475.       13636675.
      2413275.01     13635774.99
#Sta/Elev= 30
  3439.6   268.1  3637.9  263.18  3670.1  263.34  3815.4  256.55  4220.2  243.75
    4322  242.01  4329.2  241.99  4423.9  241.47  4598.5     242  4650.7   244.4
  4670.7  241.74  4692.4  243.02  4729.4  242.04  4831.3  242.36  4986.2  241.05
  4986.7  240.55  5004.1  241.05  5047.9  242.16  5202.8  242.32  5234.8  242.42
  5355.9  242.67  5363.3  242.75  5654.3  243.56  5756.1     243  5898.3  246.75
  5955.2  251.19  5990.3  257.33  6004.5  258.38  6110.7  261.31  6209.8   261.6
#Mann= 14 ,-1 , 0
  3439.6     .05       0  4220.2    .035       0    4322     .07       0
  4329.2    .035       0  4423.9     .07       0  4729.4    .035       0
  4831.3      .1       0  4986.2     .05       0  5004.1      .1       0
  5202.8     .07       0  5234.8    .035       0  5355.9     .07       0
  5363.3     .05       0  5654.3     .07       0
Bank Sta=4986.2,5004.1
XS Rating Curve= 0 ,0
Exp/Cntr=0.3,0.1

Type RM Length L Ch R = 1 ,3399    ,435,435,435
BEGIN DESCRIPTION:
B19914
END DESCRIPTION:
XS GIS Cut Line= 4
      2410909.42     13636872.93      2412415.34     13637002.99
      2412771.29     13636941.39      2413420.77       13635827.
#Sta/Elev= 30
  3377.1  259.68    3391  259.28  3489.5  257.82    3875  252.66  3982.1  249.08
  4080.6  245.82  4277.7  241.24  4376.2  240.71  4467.8  239.95  4468.3  239.45
  4485.7  239.95  4520.1  240.76  4671.7  241.41  4770.3  241.52  4868.8  241.13
  4969.7  242.13  5010.1  240.41  5026.6  241.55  5040.5  242.81  5169.5  241.25
  5372.9  240.81  5631.2  241.39  6012.3  243.26  6141.7  247.18  6179.1  250.17
  6222.1  258.42  6252.7  257.43  6462.8  260.13    6500  256.39  6539.7  258.69
#Mann= 20 ,-1 , 0
  3377.1     .05       0    3391    .035       0  3489.5     .07       0
    3875     .07       0  3982.1     .05       0  4080.6     .07       0
  4277.7     .05       0  4376.2    .035       0  4467.8     .05       0
  4485.7    .035       0  4520.1     .07       0  4671.7      .1       0
  4770.3    .035       0  4868.8      .1       0  5026.6     .12       0
  5169.5     .05       0  5372.9     .05       0  5631.2     .07       0
  6012.3     .05       0  6141.7     .07       0
Bank Sta=4467.8,4485.7
XS Rating Curve= 0 ,0
Exp/Cntr=0.3,0.1

Type RM Length L Ch R = 1 ,2964    ,0,0,0
BEGIN DESCRIPTION:
B19913
END DESCRIPTION:
XS GIS Cut Line= 4
      2410895.78     13637222.04      2412340.05     13637413.69
      2413051.93     13637194.65      2413537.92     13635784.61
#Sta/Elev= 30
  3454.1   261.8  3618.9     258    3775  253.08    4065  246.32  4163.8  245.29
  4262.7  242.89  4361.6  240.98  4559.4  240.48  4987.9  241.32  5001.4  236.76
  5001.9  236.26  5019.3  236.76  5020.6  240.03  5031.3  241.16  5062.6  238.19
  5123.9  241.07  5315.8  240.42  5643.3  239.53  5687.2  239.65  6157.3  241.57
  6367.9  243.26  6681.5  248.56  6752.5  253.57  6851.4  254.51  6903.2  259.51
  6939.7  255.42  7051.7  255.67  7083.4  259.71  7095.8  257.09  7147.3  256.72
#Mann= 16 ,-1 , 0
  3454.1     .07       0  3618.9    .035       0    3775     .07       0
    4065     .05       0  4163.8     .07       0  4262.7     .05       0
  4361.6    .035       0  4559.4      .1       0  5001.4     .05       0
  5019.3      .1       0  5062.6     .12       0  5315.8     .07       0
  5643.3    .035       0  5687.2     .07       0  6157.3    .035       0
  6367.9     .07       0
Bank Sta=5001.4,5019.3
XS Rating Curve= 0 ,0
Exp/Cntr=0.3,0.1

Chan Stop Cuts=-1
Use User Specified Reach Order=0
Composite Channel Slope=5