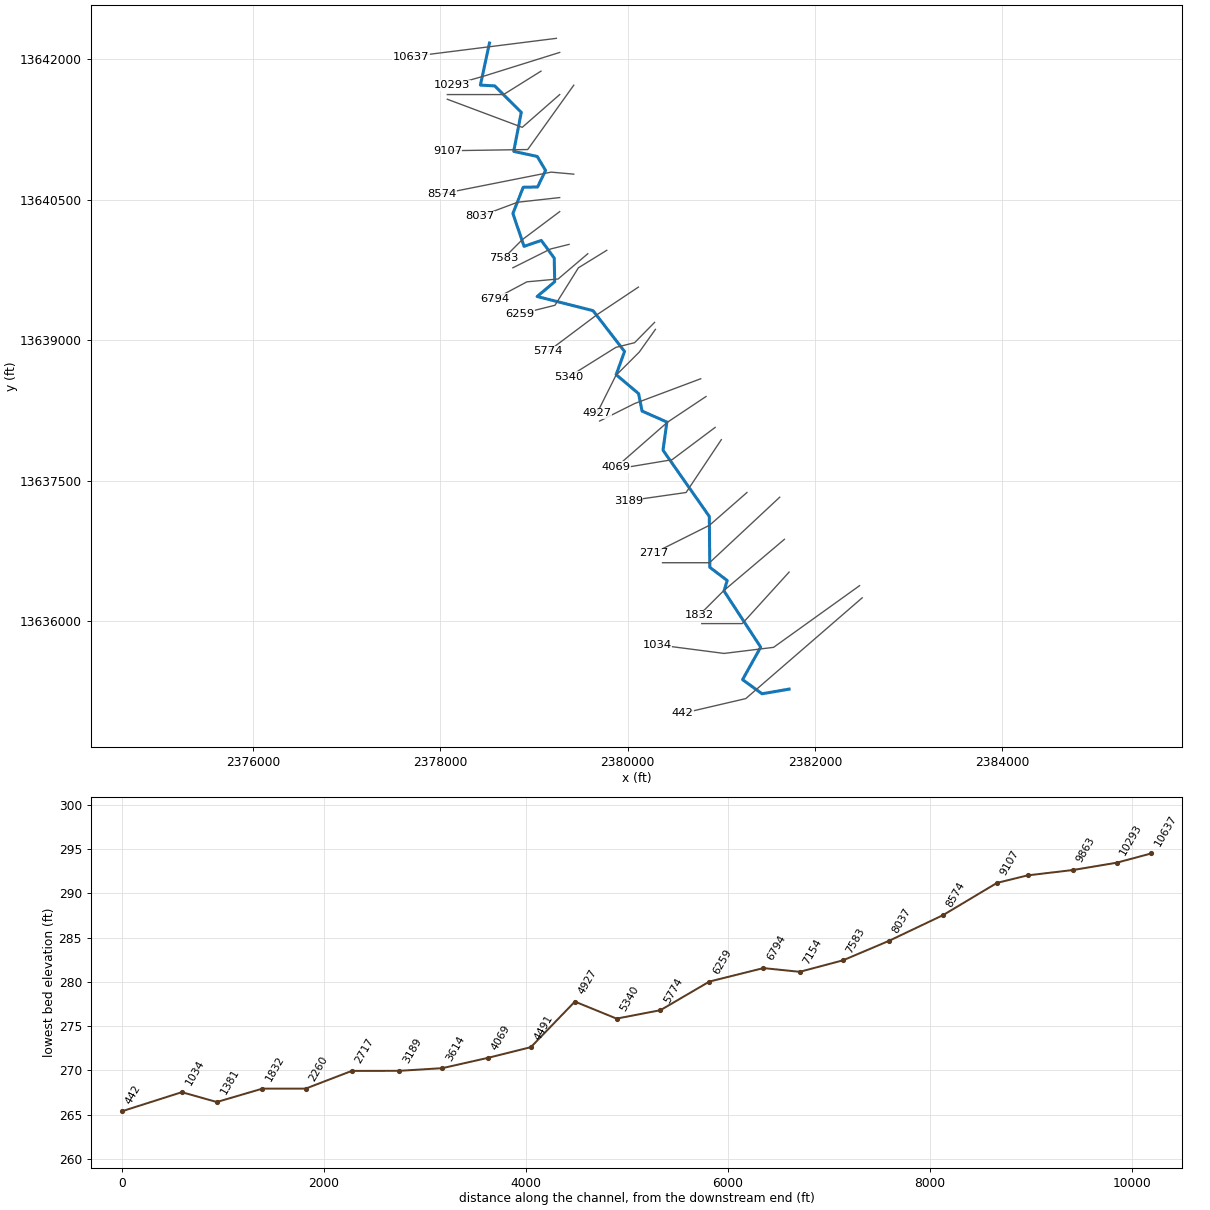
--- RACETRACK CREEK.prj (project) ---

Proj Title=RACETRACK CREEK Base Level Engineering
Current Plan=p01
Default Exp/Contr=0.3,0.1
English Units
Geom File=g01
Flow File=f01
Plan File=p01
BEGIN DESCRIPTION:
RACETRACK CREEK
END DESCRIPTION:

--- RACETRACK CREEK.p01 (plan) ---

Plan Title=Multiple Run
Short Identifier=Multiple
Geom File=g01
Flow File=f01
Subcritical Flow
K Sum by GR= 0
Std Step Tol= 0.01
Critical Tol= 0.01
Num of Std Step Trials= 20
Max Error Tol= 0.3
Flow Tol Ratio= 0.001
Split Flow NTrial= 30
Split Flow Tol= 0.02
Split Flow Ratio= 0.02
Log Output Level= 0
Friction Slope Method= 1
Unsteady Friction Slope Method= 2
Unsteady Bridges Friction Slope Method= 1
Parabolic Critical Depth
Global Vel Dist=  1 , 1 , 1
Global Log Level= 0
CheckData=True
Encroach Param= -1, 0, 0, 0
BEGIN DESCRIPTION:
Multiple Run
END DESCRIPTION:

--- RACETRACK CREEK.f01 (steady flow) ---

Flow Title=Multiple
Number of Profiles=7
Profile Names=10-year,25-year,50-year,1pct_min,100-year,1pct_plu,500-year
River Rch & RM= RACETRACK CREEK,Reach-1,10637
     641    1038    1397     910    1816    3624    3044
River Rch & RM= RACETRACK CREEK,Reach-1,9107
     834    1367    1854    1216    2427    4842    4123
River Rch & RM= RACETRACK CREEK,Reach-1,4491
    1142    1897    2596    1716    3424    6831    5907
Boundary for River Rch & Prof#=RACETRACK CREEK,Reach-1,1
Up Type=0
Dn Type=3
Dn Slope=0.005
Boundary for River Rch & Prof#=RACETRACK CREEK,Reach-1,2
Up Type=0
Dn Type=3
Dn Slope=0.005
Boundary for River Rch & Prof#=RACETRACK CREEK,Reach-1,3
Up Type=0
Dn Type=3
Dn Slope=0.005
Boundary for River Rch & Prof#=RACETRACK CREEK,Reach-1,4
Up Type=0
Dn Type=3
Dn Slope=0.005
Boundary for River Rch & Prof#=RACETRACK CREEK,Reach-1,5
Up Type=0
Dn Type=3
Dn Slope=0.005
Boundary for River Rch & Prof#=RACETRACK CREEK,Reach-1,6
Up Type=0
Dn Type=3
Dn Slope=0.005
Boundary for River Rch & Prof#=RACETRACK CREEK,Reach-1,7
Up Type=0
Dn Type=3
Dn Slope=0.005

--- RACETRACK CREEK.g01 (geometry) ---

Geom Title=Existing Conditions

River Reach=RACETRACK CREEK,Reach-1
Reach XY= 30
      2378525.00     13642175.00      2378428.12     13641726.16
      2378581.06     13641717.50      2378864.66     13641435.12
      2378783.96     13641018.31      2379035.38     13640964.03
      2379124.26     13640814.32      2379038.73     13640638.40
      2378885.63     13640635.12      2378775.05     13640354.96
      2378894.61     13640003.90      2379078.42     13640067.24
      2379216.76     13639878.23      2379221.57     13639626.23
      2379034.09     13639468.27      2379631.19     13639317.18
      2379967.66     13638881.31      2379878.06     13638633.31
      2380117.50     13638431.05      2380154.76     13638244.63
      2380419.65     13638127.70      2380378.46     13637826.48
      2380873.03     13637119.32      2380878.04     13636576.42
      2381063.89     13636435.08      2381030.12     13636322.71
      2381421.69     13635723.26      2381228.04     13635376.42
      2381435.64     13635225.56      2381725.00     13635275.00

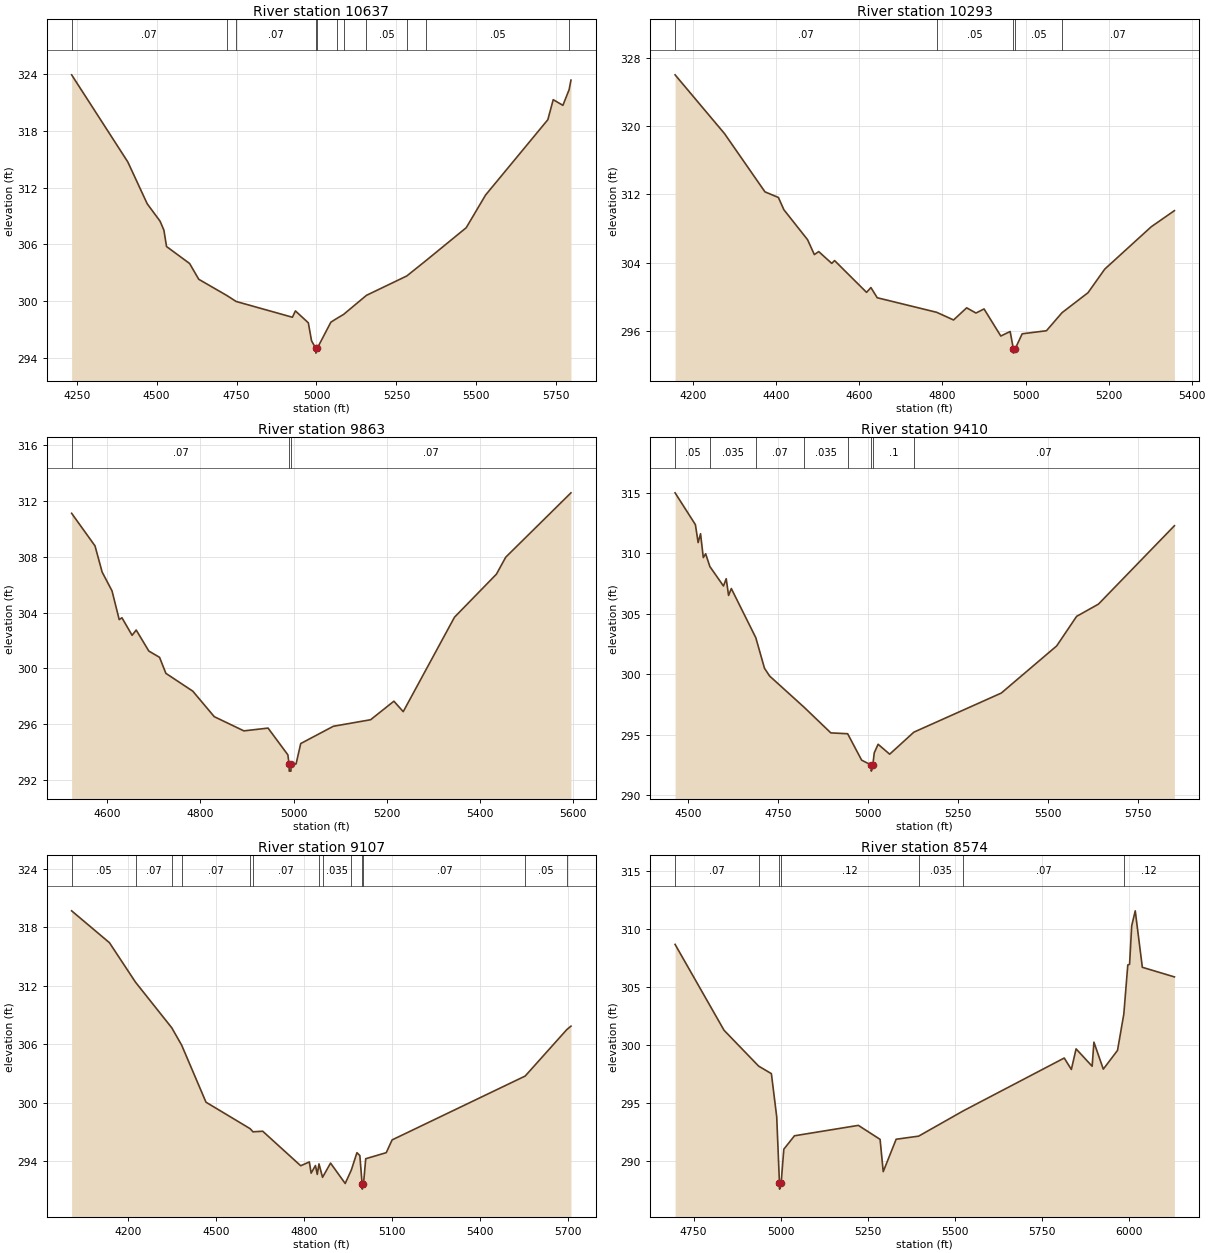
Type RM Length L Ch R = 1,10637,344,344,344
BEGIN DESCRIPTION:
B20140
END DESCRIPTION:
XS GIS Cut Line= 2
      2379239.47     13642225.61      2377689.97     13642030.76
#Sta/Elev= 30
  4234.2  323.96  4410.0  314.73  4470.5  310.31  4510.8  308.46  4522.8  307.51
  4531.0  305.78  4603.2  303.98  4631.8  302.31  4719.8  300.59  4748.7  299.96
  4924.7  298.29  4934.1  298.96  4974.5  297.70  4984.5  295.80  4998.0  294.99
  4998.2  294.49  5002.2  294.99  5045.0  297.77  5065.4  298.20  5084.8  298.59
  5156.3  300.61  5282.4  302.66  5342.9  304.30  5468.3  307.77  5528.8  311.23
  5723.6  319.21  5740.4  321.33  5770.7  320.73  5790.2  322.40  5795.9  323.40
#Mann=11,-1,0
  4234.2    0.07       0  4719.8    0.05       0  4748.7    0.07       0
  4998.0    0.05       0  5002.2    0.07       0  5065.4    0.05       0
  5084.8    0.07       0  5156.3    0.05       0  5282.4    0.07       0
  5342.9    0.05       0  5790.2    0.07       0
Bank Sta=4998,5002.2
Exp/Cntr=0.3,0.1

Type RM Length L Ch R = 1,10293,430,430,430
BEGIN DESCRIPTION:
RACETRACK CREEK 21.0
END DESCRIPTION:
XS GIS Cut Line= 3
      2379275.02     13642075.01      2378475.00     13641825.00
      2378124.98     13641724.99
#Sta/Elev= 30
  4156.3  326.00  4275.2  319.13  4372.7  312.31  4405.1  311.65  4418.2  310.22
  4475.3  306.71  4491.6  304.97  4502.1  305.32  4533.5  303.94  4540.3  304.27
  4617.3  300.55  4627.8  301.11  4643.0  299.92  4785.9  298.22  4826.8  297.32
  4858.3  298.74  4880.8  298.13  4900.2  298.61  4940.5  295.44  4963.0  295.97
  4970.8  293.94  4971.1  293.44  4975.1  293.94  4991.9  295.70  5050.4  296.06
  5087.9  298.17  5150.5  300.51  5190.8  303.27  5302.6  308.22  5358.5  310.11
#Mann=5,-1,0
  4156.3    0.07       0  4785.9    0.05       0  4970.8    0.05       0
  4975.1    0.05       0  5087.9    0.07       0
Bank Sta=4970.8,4975.1
Exp/Cntr=0.3,0.1

Type RM Length L Ch R = 1,9863,453,453,453
BEGIN DESCRIPTION:
RACETRACK CREEK 20.0
END DESCRIPTION:
XS GIS Cut Line= 3
      2379075.04     13641875.03      2378675.00     13641625.00
      2378075.05     13641625.00
#Sta/Elev= 30
  4523.5  311.13  4573.7  308.79  4589.0  306.91  4610.2  305.56  4625.6  303.50
  4631.5  303.63  4653.3  302.37  4662.1  302.75  4689.2  301.24  4712.2  300.79
  4725.8  299.64  4783.6  298.36  4829.6  296.53  4893.2  295.51  4945.1  295.71
  4987.6  293.79  4990.2  293.12  4990.5  292.62  4994.2  292.62  4994.5  293.12
  5005.2  293.14  5015.2  294.60  5085.2  295.84  5165.2  296.31  5215.2  297.64
  5235.2  296.89  5345.2  303.67  5435.2  306.76  5455.2  307.98  5595.2  312.60
#Mann=3,-1,0
  4523.5    0.07       0  4990.2    0.05       0  4994.5    0.07       0
Bank Sta=4990.2,4994.5
Exp/Cntr=0.3,0.1

Type RM Length L Ch R = 1,9410,303,303,303
BEGIN DESCRIPTION:
RACETRACK CREEK 19.0
END DESCRIPTION:
XS GIS Cut Line= 3
      2379274.98     13641624.98      2378875.00     13641275.00
      2378074.98     13641575.01
#Sta/Elev= 30
  4464.4  315.01  4520.8  312.38  4528.4  310.90  4535.1  311.63  4542.7  309.66
  4549.3  309.97  4560.9  308.92  4598.7  307.31  4606.3  307.91  4612.9  306.53
  4620.5  307.10  4688.4  303.04  4712.6  300.51  4726.8  299.87  4823.2  297.27
  4896.7  295.17  4943.4  295.10  4982.1  292.92  5008.9  292.51  5009.1  292.01
  5013.2  292.51  5017.2  293.52  5027.9  294.23  5060.0  293.41  5127.1  295.23
  5369.7  298.46  5523.6  302.36  5578.8  304.80  5639.4  305.81  5850.3  312.29
#Mann=8,-1,0
  4464.4    0.05       0  4560.9   0.035       0  4688.4    0.07       0
  4823.2   0.035       0  4943.4     0.1       0  5008.9    0.05       0
  5013.2     0.1       0  5127.1    0.07       0
Bank Sta=5008.9,5013.2
Exp/Cntr=0.3,0.1

Type RM Length L Ch R = 1,9107,533,533,533
BEGIN DESCRIPTION:
RACETRACK CREEK 18.0
END DESCRIPTION:
XS GIS Cut Line= 3
      2379425.02     13641725.03      2378933.30     13641037.94
      2378075.02     13641025.00
#Sta/Elev= 30
  4008.3  319.71  4137.3  316.44  4226.2  312.39  4349.9  307.71  4383.8  305.92
  4466.6  300.08  4617.2  297.36  4626.9  297.04  4660.1  297.10  4789.7  293.56
  4819.2  293.95  4825.3  292.80  4840.0  293.58  4846.2  292.67  4852.1  293.75
  4864.2  292.37  4891.5  293.83  4941.5  291.74  4962.5  293.13  4981.5  294.90
  4991.5  294.60  4999.3  291.66  4999.6  291.16  5003.8  291.66  5011.5  294.28
  5081.5  294.90  5101.5  296.21  5555.4  302.76  5697.5  307.53  5711.6  307.88
#Mann=13,-1,0
  4008.3    0.05       0  4226.2    0.07       0  4349.9    0.05       0
  4383.8    0.07       0  4617.2   0.035       0  4626.9    0.07       0
  4852.1    0.12       0  4864.2   0.035       0  4962.5    0.07       0
  4999.3    0.05       0  5003.8    0.07       0  5555.4    0.05       0
  5697.5    0.07       0
Bank Sta=4999.3,5003.8
Exp/Cntr=0.3,0.1

Type RM Length L Ch R = 1,8574,537,537,537
BEGIN DESCRIPTION:
RACETRACK CREEK 17.0
END DESCRIPTION:
XS GIS Cut Line= 3
      2379425.02     13640775.00      2379183.82     13640796.69
      2378014.69     13640564.72
#Sta/Elev= 30
  4696.9  308.68  4837.5  301.26  4936.9  298.16  4973.5  297.51  4988.8  293.78
  4996.7  288.03  4997.0  287.53  5001.4  288.03  5009.2  290.98  5039.8  292.14
  5223.3  293.04  5285.7  291.83  5294.7  289.04  5331.8  291.84  5396.5  292.11
  5525.0  294.30  5814.6  298.86  5835.0  297.87  5848.6  299.65  5894.7  298.15
  5899.8  300.23  5926.8  297.90  5967.6  299.52  5985.7  302.66  5997.1  306.90
  6002.2  306.96  6008.3  310.28  6018.5  311.58  6038.9  306.70  6131.0  305.87
#Mann=7,-1,0
  4696.9    0.07       0  4936.9    0.12       0  4996.7    0.05       0
  5001.4    0.12       0  5396.5   0.035       0  5525.0    0.07       0
  5985.7    0.12       0
Bank Sta=4996.7,5001.4
Exp/Cntr=0.3,0.1

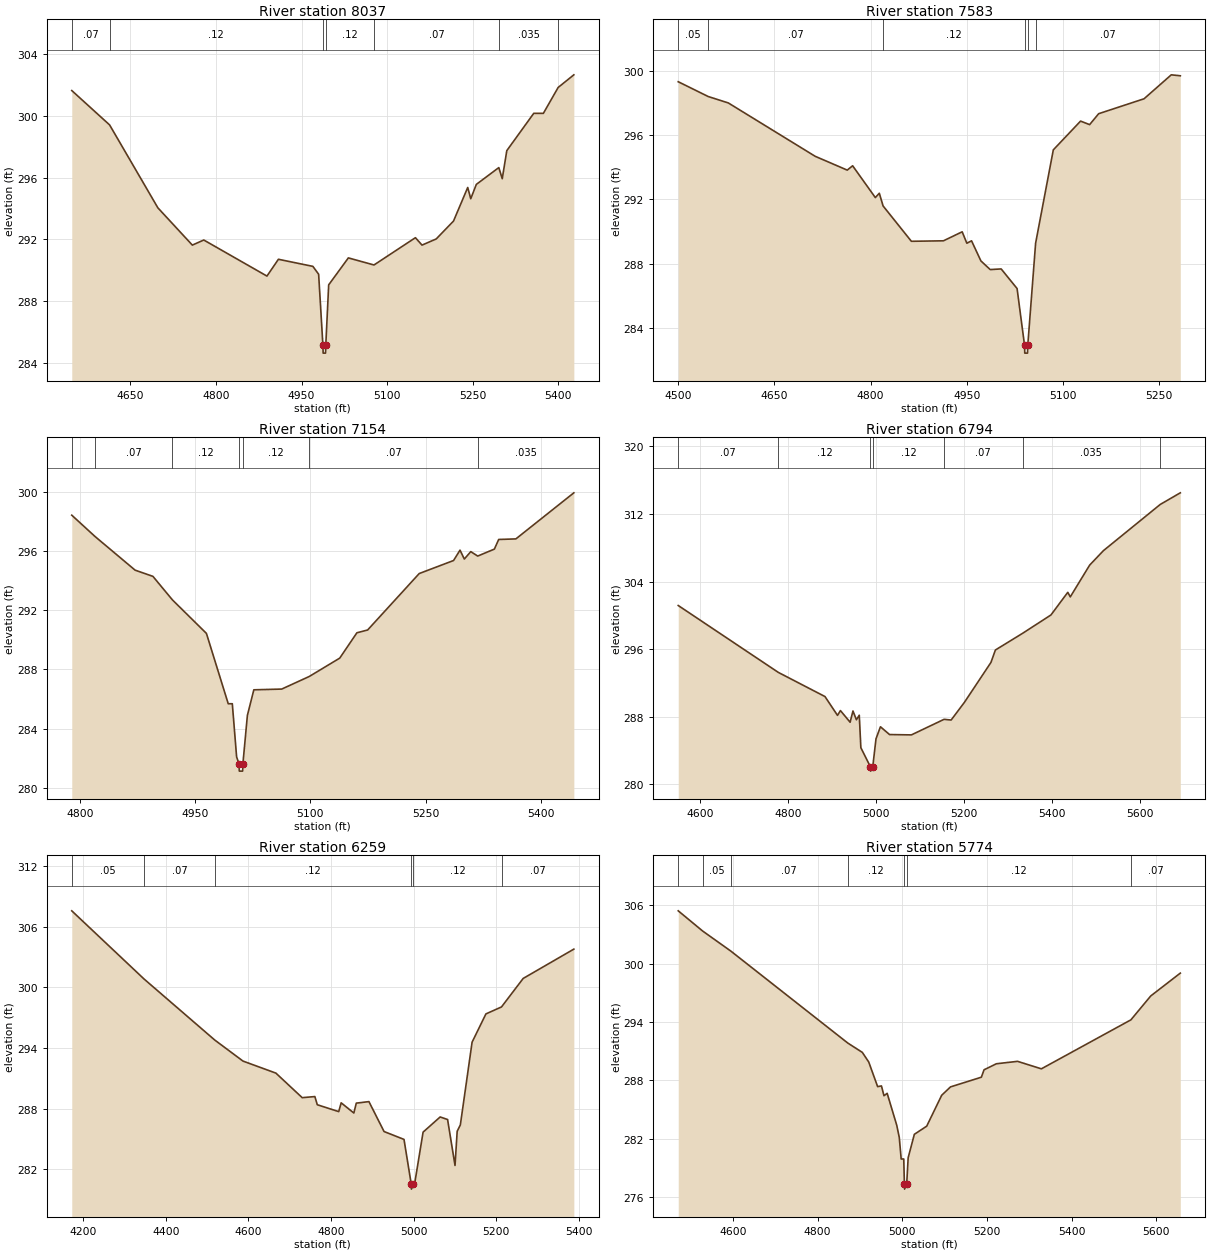
Type RM Length L Ch R = 1,8037,454,454,454
BEGIN DESCRIPTION:
RACETRACK CREEK 16.0
END DESCRIPTION:
XS GIS Cut Line= 3
      2379275.03     13640525.00      2378825.00     13640475.00
      2378425.00     13640325.00
#Sta/Elev= 30
  4547.2  301.66  4613.5  299.43  4698.1  294.05  4758.5  291.63  4778.6  291.96
  4889.3  289.62  4909.4  290.71  4969.8  290.25  4979.9  289.74  4987.4  285.12
  4987.8  284.62  4992.0  284.62  4992.4  285.12  4997.5  289.05  5032.0  290.80
  5076.9  290.34  5149.5  292.11  5161.1  291.63  5186.0  292.03  5216.3  293.19
  5241.2  295.37  5246.5  294.64  5256.3  295.57  5295.7  296.66  5301.7  295.94
  5309.7  297.76  5356.9  300.18  5373.8  300.18  5399.7  301.86  5427.2  302.68
#Mann=7,-1,0
  4547.2    0.07       0  4613.5    0.12       0  4987.4    0.05       0
  4992.4    0.12       0  5076.9    0.07       0  5295.7   0.035       0
  5399.7    0.07       0
Bank Sta=4987.4,4992.4
Exp/Cntr=0.3,0.1

Type RM Length L Ch R = 1,7583,429,429,429
BEGIN DESCRIPTION:
RACETRACK CREEK 15.0
END DESCRIPTION:
XS GIS Cut Line= 3
      2379274.98     13640374.99      2378875.00     13640075.00
      2378675.01     13639875.01
#Sta/Elev= 30
  4500.0  299.32  4546.7  298.40  4578.1  298.00  4713.5  294.68  4763.5  293.82
  4771.9  294.09  4807.3  292.11  4813.5  292.38  4819.4  291.59  4863.5  289.39
  4913.5  289.42  4942.7  289.98  4950.0  289.27  4957.3  289.42  4971.9  288.17
  4986.4  287.63  5003.5  287.67  5028.3  286.45  5039.9  282.93  5040.3  282.43
  5044.6  282.43  5045.0  282.93  5057.2  289.27  5084.8  295.08  5127.3  296.87
  5141.4  296.65  5155.5  297.33  5226.3  298.26  5268.7  299.75  5282.8  299.69
#Mann=6,-1,0
  4500.0    0.05       0  4546.7    0.07       0  4819.4    0.12       0
  5039.9    0.05       0  5045.0    0.12       0  5057.2    0.07       0
Bank Sta=5039.9,5045
Exp/Cntr=0.3,0.1

Type RM Length L Ch R = 1,7154,360,360,360
BEGIN DESCRIPTION:
RACETRACK CREEK 14.0
END DESCRIPTION:
XS GIS Cut Line= 3
      2379374.98     13640024.99      2379175.00     13639975.00
      2378775.04     13639775.02
#Sta/Elev= 30
  4789.6  298.41  4819.9  296.97  4872.0  294.70  4895.2  294.28  4920.6  292.69
  4964.8  290.43  4993.2  285.68  4998.5  285.68  5004.1  282.09  5007.2  281.63
  5007.6  281.13  5011.9  281.13  5012.3  281.63  5018.1  284.89  5026.5  286.62
  5062.8  286.67  5098.6  287.52  5138.3  288.76  5160.6  290.47  5174.6  290.66
  5241.7  294.47  5286.4  295.35  5294.8  296.05  5300.4  295.45  5308.8  295.95
  5317.8  295.65  5339.5  296.12  5345.1  296.77  5367.5  296.81  5442.9  299.92
#Mann=7,-1,0
  4789.6    0.05       0  4819.9    0.07       0  4920.6    0.12       0
  5007.2    0.05       0  5012.3    0.12       0  5098.6    0.07       0
  5317.8   0.035       0
Bank Sta=5007.2,5012.3
Exp/Cntr=0.3,0.1

Type RM Length L Ch R = 1,6794,535,535,535
BEGIN DESCRIPTION:
RACETRACK CREEK 13.0
END DESCRIPTION:
XS GIS Cut Line= 4
      2379574.96     13639924.97      2379258.05     13639655.41
      2378925.00     13639625.00      2378580.69     13639442.00
#Sta/Elev= 30
  4551.2  301.16  4778.5  293.24  4884.5  290.38  4913.0  288.15  4919.6  288.72
  4941.6  287.34  4948.1  288.67  4955.9  287.63  4962.4  288.17  4966.0  284.33
  4987.8  282.05  4988.2  281.55  4993.0  282.05  5000.4  285.38  5010.5  286.80
  5031.2  285.88  5080.8  285.84  5154.9  287.68  5171.1  287.60  5201.3  289.70
  5261.5  294.42  5271.6  295.89  5333.2  297.86  5397.8  300.04  5436.0  302.72
  5441.7  302.18  5485.7  305.94  5516.9  307.65  5645.9  313.12  5691.6  314.50
#Mann=7,-1,0
  4551.2    0.07       0  4778.5    0.12       0  4987.8    0.05       0
  4993.0    0.12       0  5154.9    0.07       0  5333.2   0.035       0
  5645.9    0.05       0
Bank Sta=4987.8,4993
Exp/Cntr=0.3,0.1

Type RM Length L Ch R = 1,6259,485,485,485
BEGIN DESCRIPTION:
RACETRACK CREEK 12.0
END DESCRIPTION:
XS GIS Cut Line= 5
      2379777.63     13639961.60      2379475.00     13639775.00
      2379225.00     13639375.00      2379025.00     13639325.00
      2378848.52     13639280.88
#Sta/Elev= 30
  4172.4  307.57  4347.2  300.83  4518.3  294.79  4586.9  292.70  4666.5  291.51
  4730.2  289.08  4760.8  289.19  4766.7  288.38  4818.6  287.70  4824.5  288.57
  4855.2  287.56  4861.1  288.54  4891.7  288.69  4928.3  285.73  4976.6  284.95
  4994.1  280.53  4994.5  280.03  4999.3  280.53  5002.2  280.53  5022.8  285.67
  5064.1  287.17  5082.1  286.92  5100.1  282.37  5105.3  285.75  5113.0  286.39
  5141.4  294.57  5174.9  297.37  5212.6  298.06  5265.1  300.88  5387.7  303.78
#Mann=6,-1,0
  4172.4    0.05       0  4347.2    0.07       0  4518.3    0.12       0
  4994.1    0.05       0  4999.3    0.12       0  5212.6    0.07       0
Bank Sta=4994.1,4999.3
Exp/Cntr=0.3,0.1

Type RM Length L Ch R = 1,5774,434,434,434
BEGIN DESCRIPTION:
RACETRACK CREEK 11.0
END DESCRIPTION:
XS GIS Cut Line= 5
      2380115.55     13639568.70      2379825.00     13639375.00
      2379675.00     13639275.00      2379275.00     13638975.00
      2379150.02     13638881.26
#Sta/Elev= 30
  4470.8  305.44  4528.5  303.36  4594.9  301.30  4871.0  291.84  4905.6  290.87
  4920.7  289.88  4941.7  287.35  4950.7  287.42  4956.7  286.41  4964.2  286.66
  4986.8  283.38  4992.8  282.12  4997.3  279.90  5003.4  279.90  5004.9  277.30
  5005.3  276.80  5010.3  277.30  5013.8  280.03  5028.4  282.44  5057.6  283.28
  5093.0  286.46  5113.8  287.32  5186.7  288.32  5193.0  289.08  5222.1  289.70
  5272.1  289.95  5328.4  289.18  5539.8  294.22  5586.7  296.68  5656.5  299.03
#Mann=7,-1,0
  4470.8    0.07       0  4528.5    0.05       0  4594.9    0.07       0
  4871.0    0.12       0  5004.9    0.05       0  5010.3    0.12       0
  5539.8    0.07       0
Bank Sta=5004.9,5010.3
Exp/Cntr=0.3,0.1

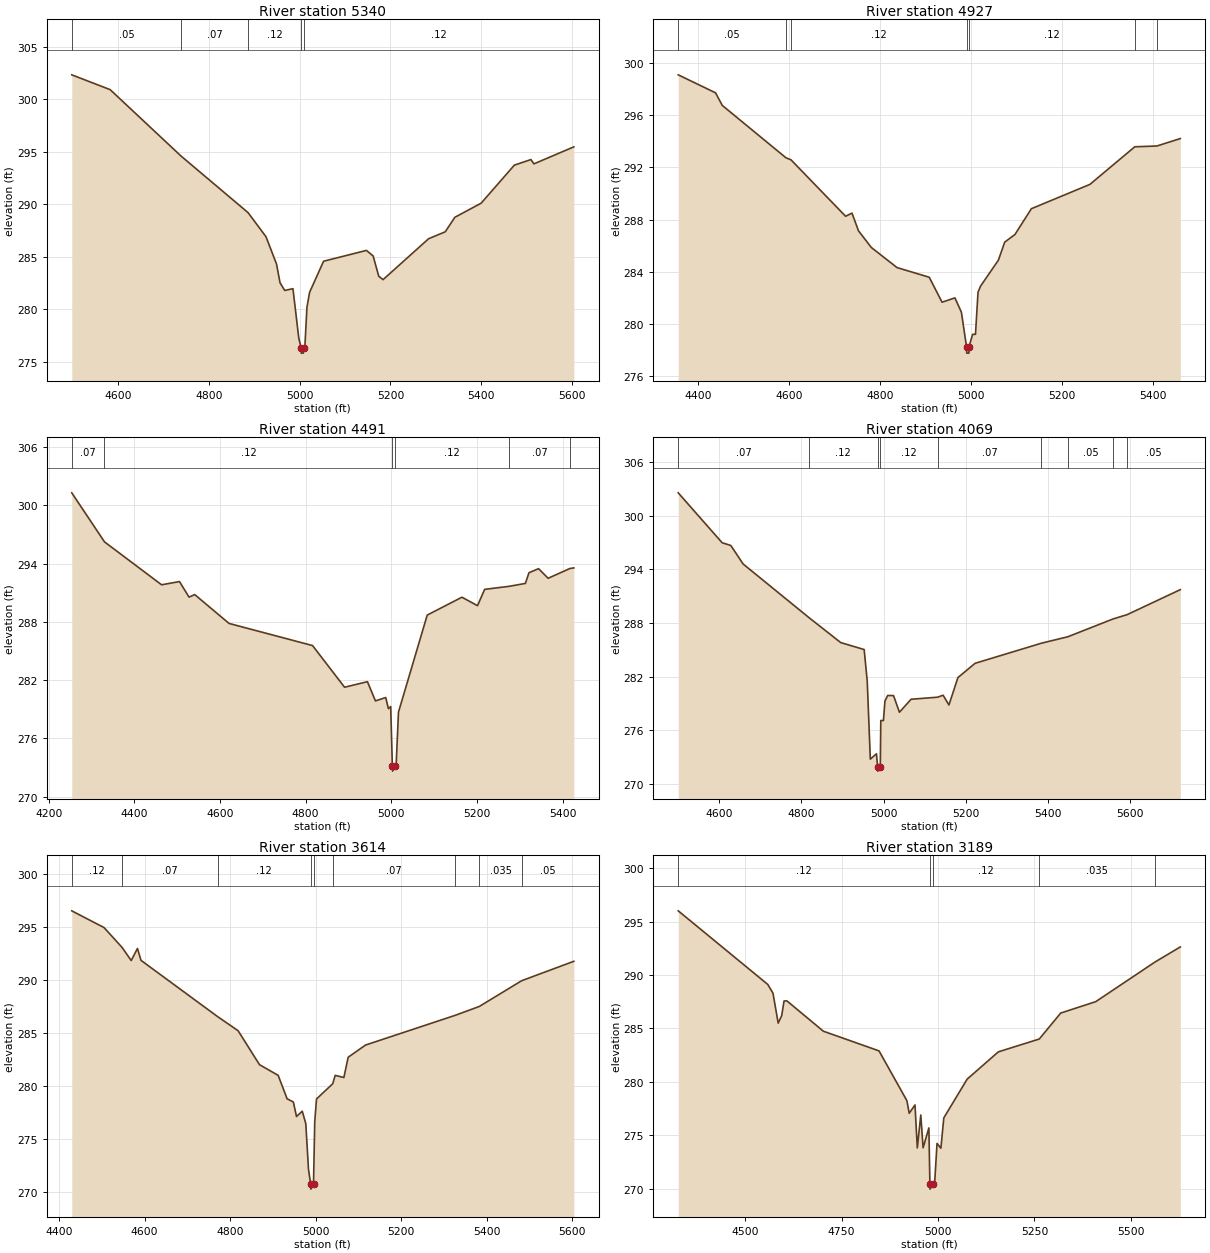
Type RM Length L Ch R = 1,5340,413,413,413
BEGIN DESCRIPTION:
RACETRACK CREEK 10.0
END DESCRIPTION:
XS GIS Cut Line= 5
      2380287.99     13639191.48      2380075.00     13638975.00
      2379875.00     13638925.00      2379475.00     13638675.00
      2379370.48     13638609.68
#Sta/Elev= 30
  4498.7  302.32  4583.2  300.91  4739.3  294.59  4886.7  289.21  4926.1  286.92
  4949.3  284.32  4957.0  282.54  4967.3  281.81  4985.4  281.98  4998.2  277.29
  5003.3  276.35  5003.7  275.85  5008.2  275.85  5008.7  276.35  5011.5  276.35
  5016.2  280.22  5022.1  281.64  5052.8  284.59  5147.1  285.62  5161.9  285.09
  5174.2  283.16  5183.7  282.84  5283.9  286.73  5320.5  287.39  5341.7  288.77
  5399.5  290.11  5472.6  293.73  5509.1  294.26  5515.6  293.85  5603.5  295.47
#Mann=5,-1,0
  4498.7    0.05       0  4739.3    0.07       0  4886.7    0.12       0
  5003.3    0.05       0  5008.7    0.12       0
Bank Sta=5003.3,5008.7
Exp/Cntr=0.3,0.1

Type RM Length L Ch R = 1,4927,436,436,436
BEGIN DESCRIPTION:
RACETRACK CREEK 9.0
END DESCRIPTION:
XS GIS Cut Line= 5
      2380297.29     13639117.28      2380125.00     13638875.00
      2379875.00     13638625.00      2379775.00     13638425.00
      2379672.34     13638219.69
#Sta/Elev= 30
  4356.7  299.08  4438.8  297.70  4453.5  296.74  4593.5  292.73  4604.7  292.57
  4724.7  288.25  4738.8  288.49  4753.0  287.14  4781.3  285.86  4837.8  284.32
  4908.6  283.58  4936.8  281.67  4965.1  282.00  4979.3  280.91  4990.6  278.27
  4991.1  277.77  4995.8  277.77  4996.2  278.27  5004.0  279.21  5010.3  279.21
  5015.9  282.43  5021.5  282.90  5060.7  284.89  5074.6  286.27  5097.0  286.85
  5133.3  288.83  5261.9  290.69  5360.6  293.57  5409.2  293.63  5460.7  294.20
#Mann=7,-1,0
  4356.7    0.05       0  4593.5    0.07       0  4604.7    0.12       0
  4990.6    0.05       0  4996.2    0.12       0  5360.6    0.07       0
  5409.2    0.05       0
Bank Sta=4990.6,4996.2
Exp/Cntr=0.3,0.1

Type RM Length L Ch R = 1,4491,422,422,422
BEGIN DESCRIPTION:
RACETRACK CREEK 8.0
END DESCRIPTION:
XS GIS Cut Line= 5
      2380781.36     13638589.89      2380475.00     13638475.00
      2380075.00     13638325.00      2379975.00     13638275.00
      2379701.31     13638138.15
#Sta/Elev= 30
  4254.0  301.29  4330.4  296.24  4463.7  291.82  4505.5  292.15  4527.8  290.55
  4541.1  290.81  4621.2  287.84  4816.2  285.56  4890.9  281.27  4944.3  281.84
  4963.0  279.86  4987.0  280.21  4993.3  279.06  4998.6  279.28  5002.5  273.13
  5003.0  272.63  5009.0  273.13  5011.2  273.13  5016.8  278.71  5083.9  288.70
  5164.9  290.54  5201.3  289.67  5218.0  291.35  5275.0  291.66  5313.1  291.96
  5321.4  293.06  5343.8  293.48  5366.2  292.49  5416.6  293.49  5426.2  293.56
#Mann=6,-1,0
  4254.0    0.07       0  4330.4    0.12       0  5002.5    0.05       0
  5009.0    0.12       0  5275.0    0.07       0  5416.6    0.05       0
Bank Sta=5002.5,5009
Exp/Cntr=0.3,0.1

Type RM Length L Ch R = 1,4069,455,455,455
BEGIN DESCRIPTION:
RACETRACK CREEK 7.0
END DESCRIPTION:
XS GIS Cut Line= 5
      2380837.64     13638400.09      2380575.00     13638225.00
      2380425.00     13638125.00      2380025.00     13637775.00
      2379878.80     13637647.08
#Sta/Elev= 30
  4500.1  302.56  4606.9  296.98  4628.0  296.67  4658.0  294.60  4818.3  288.60
  4895.4  285.81  4952.5  285.03  4960.0  281.51  4967.5  272.77  4982.5  273.37
  4985.2  271.93  4985.7  271.43  4991.8  271.93  4993.0  277.09  4999.4  277.09
  5003.1  279.27  5009.8  279.89  5024.0  279.88  5038.3  278.02  5066.7  279.47
  5131.2  279.70  5144.6  279.92  5158.8  278.83  5180.6  281.89  5222.4  283.49
  5383.9  285.74  5448.1  286.46  5558.7  288.46  5592.3  288.93  5721.8  291.73
#Mann=9,-1,0
  4500.1    0.07       0  4818.3    0.12       0  4985.2    0.05       0
  4991.8    0.12       0  5131.2    0.07       0  5383.9    0.12       0
  5448.1    0.05       0  5558.7    0.07       0  5592.3    0.05       0
Bank Sta=4985.2,4991.8
Exp/Cntr=0.3,0.1

Type RM Length L Ch R = 1,3614,425,425,425
BEGIN DESCRIPTION:
RACETRACK CREEK 6.0
END DESCRIPTION:
XS GIS Cut Line= 5
      2380935.37     13638070.27      2380675.00     13637875.00
      2380475.00     13637725.00      2380175.00     13637675.00
      2379884.50     13637626.58
#Sta/Elev= 30
  4429.8  296.51  4505.3  294.93  4547.4  293.06  4568.8  291.82  4583.4  292.96
  4591.7  291.84  4770.6  286.54  4818.8  285.20  4868.8  282.00  4912.5  280.99
  4933.4  278.78  4948.0  278.48  4955.3  277.11  4968.8  277.61  4977.1  276.43
  4983.4  272.12  4988.4  270.76  4988.9  270.26  4995.1  270.76  4998.0  276.61
  5002.1  278.76  5040.0  280.20  5045.8  280.99  5066.1  280.79  5076.2  282.70
  5116.8  283.85  5327.0  286.66  5382.8  287.49  5482.0  289.92  5603.9  291.75
#Mann=9,-1,0
  4429.8    0.12       0  4547.4    0.07       0  4770.6    0.12       0
  4988.4    0.05       0  4995.1    0.12       0  5040.0    0.07       0
  5327.0    0.12       0  5382.8   0.035       0  5482.0    0.05       0
Bank Sta=4988.4,4995.1
Exp/Cntr=0.3,0.1

Type RM Length L Ch R = 1,3189,472,472,472
BEGIN DESCRIPTION:
RACETRACK CREEK 5.0
END DESCRIPTION:
XS GIS Cut Line= 5
      2381001.25     13637939.37      2380825.00     13637675.00
      2380625.00     13637375.00      2380275.00     13637325.00
      2380008.15     13637286.88
#Sta/Elev= 30
  4326.8  296.01  4558.9  289.12  4572.4  288.30  4585.9  285.50  4595.0  286.20
  4601.0  287.57  4608.5  287.58  4703.1  284.74  4847.3  282.90  4919.5  278.24
  4925.5  277.06  4940.5  277.84  4946.5  273.82  4955.5  276.90  4961.5  273.83
  4976.5  275.69  4979.1  270.46  4979.6  269.96  4986.0  270.46  4991.6  270.63
  4997.6  274.24  5007.6  273.79  5015.2  276.63  5075.8  280.26  5156.6  282.81
  5262.6  284.01  5318.2  286.44  5409.1  287.51  5563.1  291.23  5628.2  292.63
#Mann=5,-1,0
  4326.8    0.12       0  4979.1    0.05       0  4986.0    0.12       0
  5262.6   0.035       0  5563.1    0.07       0
Bank Sta=4979.1,4986
Exp/Cntr=0.3,0.1

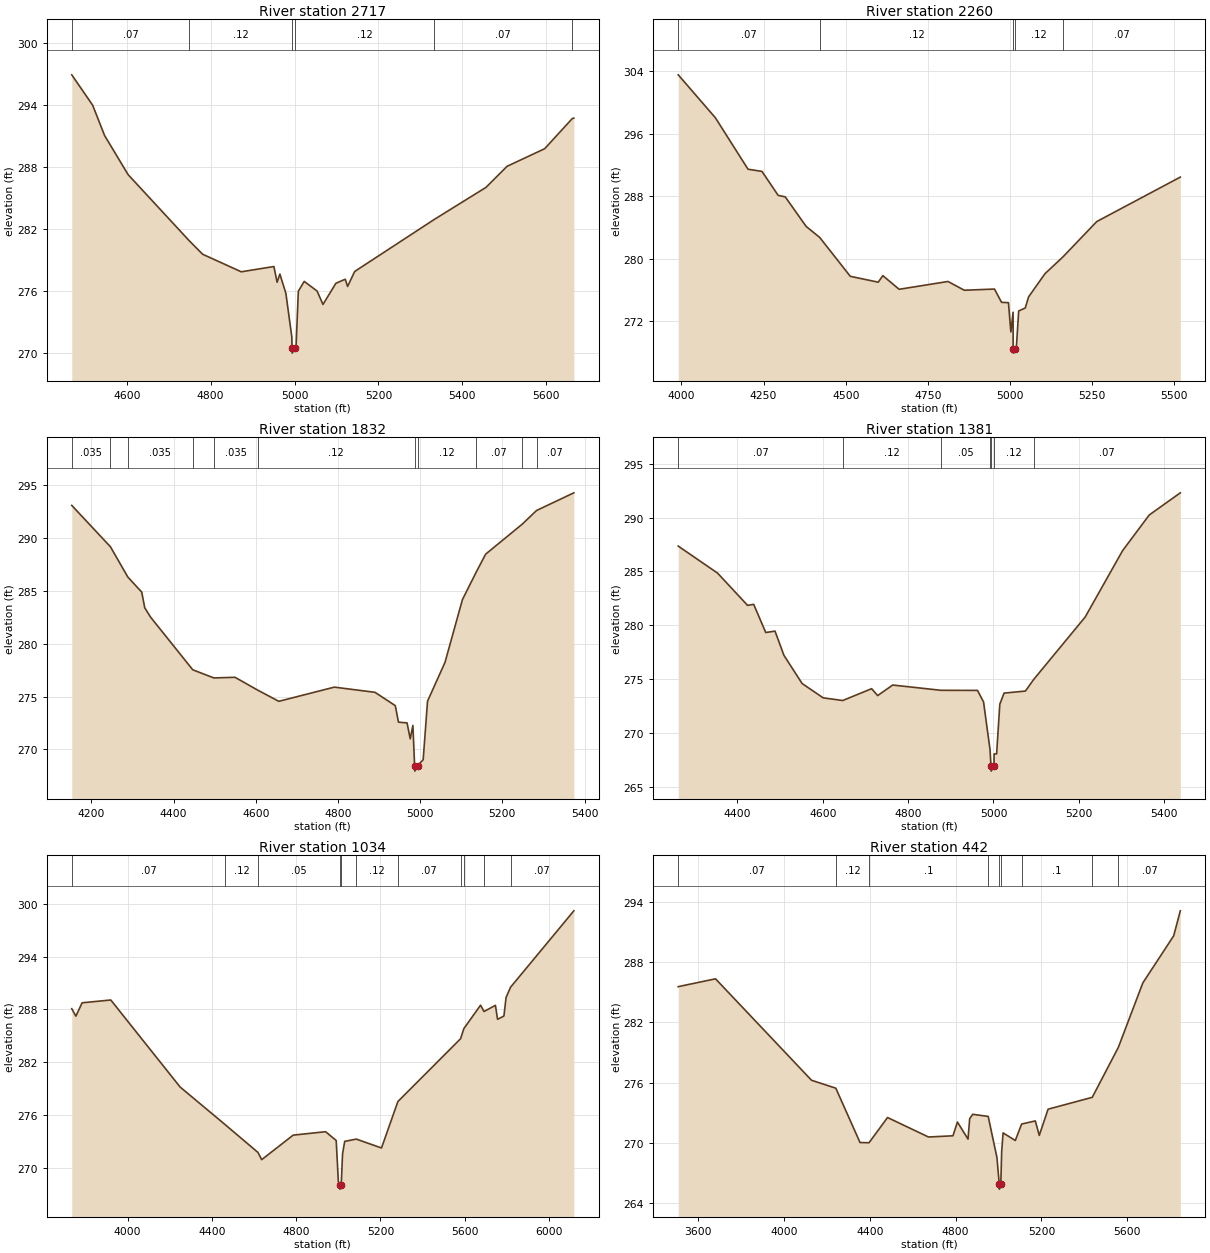
Type RM Length L Ch R = 1,2717,457,457,457
BEGIN DESCRIPTION:
RACETRACK CREEK 4.0
END DESCRIPTION:
XS GIS Cut Line= 4
      2381275.02     13637375.01      2380875.00     13637025.00
      2380475.00     13636825.00      2380280.32     13636727.66
#Sta/Elev= 30
  4469.1  296.88  4518.9  293.94  4547.4  291.00  4603.4  287.22  4748.7  280.84
  4780.9  279.52  4873.0  277.82  4950.8  278.33  4958.4  276.81  4965.0  277.60
  4979.3  275.74  4993.5  271.50  4993.9  270.45  4994.4  269.95  5000.8  270.45
  5003.4  270.45  5009.0  275.94  5023.0  276.89  5053.7  275.96  5067.7  274.66
  5098.5  276.71  5120.8  277.10  5126.4  276.40  5143.2  277.85  5332.7  282.88
  5456.2  285.99  5506.5  288.03  5596.0  289.73  5661.8  292.65  5665.5  292.69
#Mann=6,-1,0
  4469.1    0.07       0  4748.7    0.12       0  4993.9    0.05       0
  5000.8    0.12       0  5332.7    0.07       0  5661.8    0.05       0
Bank Sta=4993.9,5000.8
Exp/Cntr=0.3,0.1

Type RM Length L Ch R = 1,2260,428,428,428
BEGIN DESCRIPTION:
RACETRACK CREEK 3.0
END DESCRIPTION:
XS GIS Cut Line= 4
      2381625.00     13637325.00      2380875.00     13636625.00
      2380625.00     13636625.00      2380373.32     13636625.00
#Sta/Elev= 30
  3990.4  303.57  4103.5  298.07  4202.7  291.49  4245.2  291.21  4294.5  288.14
  4316.0  287.95  4379.5  284.17  4420.8  282.76  4513.9  277.78  4598.9  277.03
  4613.0  277.87  4662.4  276.12  4811.1  277.12  4860.7  276.00  4952.6  276.15
  4974.1  274.45  4995.1  274.41  5002.4  270.67  5009.2  273.19  5009.4  268.45
  5009.9  267.95  5016.4  268.45  5018.8  268.45  5026.3  273.35  5046.3  273.73
  5056.3  275.14  5106.3  278.12  5160.3  280.24  5263.8  284.79  5518.0  290.48
#Mann=5,-1,0
  3990.4    0.07       0  4420.8    0.12       0  5009.4    0.05       0
  5016.4    0.12       0  5160.3    0.07       0
Bank Sta=5009.4,5016.4
Exp/Cntr=0.3,0.1

Type RM Length L Ch R = 1,1832,451,451,451
BEGIN DESCRIPTION:
RACETRACK CREEK 2.0
END DESCRIPTION:
XS GIS Cut Line= 4
      2381675.01     13636875.01      2381025.00     13636325.00
      2380925.00     13636225.00      2380763.29     13636063.29
#Sta/Elev= 30
  4152.3  293.07  4246.4  289.16  4288.7  286.30  4322.6  284.87  4329.8  283.40
  4344.0  282.51  4446.7  277.53  4498.0  276.76  4549.5  276.82  4604.6  275.61
  4656.0  274.55  4791.2  275.89  4890.1  275.40  4939.5  274.14  4947.2  272.58
  4968.1  272.51  4975.8  271.00  4982.3  272.27  4986.5  268.45  4987.0  267.95
  4993.6  268.45  5007.3  269.03  5017.9  274.56  5060.4  278.23  5102.8  284.16
  5136.3  286.76  5159.3  288.46  5248.4  291.30  5283.2  292.59  5373.9  294.26
#Mann=11,-1,0
  4152.3   0.035       0  4246.4    0.07       0  4288.7   0.035       0
  4446.7    0.12       0  4498.0   0.035       0  4604.6    0.12       0
  4986.5    0.05       0  4993.6    0.12       0  5136.3    0.07       0
  5248.4    0.12       0  5283.2    0.07       0
Bank Sta=4986.5,4993.6
Exp/Cntr=0.3,0.1

Type RM Length L Ch R = 1,1381,347,347,347
BEGIN DESCRIPTION:
RACETRACK CREEK 1.0
END DESCRIPTION:
XS GIS Cut Line= 4
      2381724.97     13636524.97      2381225.00     13635975.00
      2380925.00     13635975.00      2380792.16     13635975.00
#Sta/Elev= 30
  4261.6  287.35  4353.8  284.84  4424.1  281.84  4438.3  281.94  4466.6  279.32
  4488.3  279.45  4509.2  277.20  4551.8  274.58  4601.1  273.25  4646.8  273.00
  4714.6  274.10  4728.8  273.46  4764.0  274.44  4877.2  273.95  4962.6  273.94
  4976.8  272.87  4992.0  268.43  4994.2  266.94  4994.7  266.44  5001.3  266.94
  5001.5  268.04  5007.4  268.04  5014.9  272.66  5024.9  273.69  5074.9  273.88
  5094.3  274.96  5214.9  280.76  5302.4  286.92  5364.9  290.24  5437.7  292.30
#Mann=7,-1,0
  4261.6    0.07       0  4646.8    0.12       0  4877.2    0.05       0
  4992.0    0.12       0  4994.2    0.05       0  5001.3    0.12       0
  5094.3    0.07       0
Bank Sta=4994.2,5001.3
Exp/Cntr=0.3,0.1

Type RM Length L Ch R = 1,1034,592,592,592
BEGIN DESCRIPTION:
B20139
END DESCRIPTION:
XS GIS Cut Line= 4
      2382477.75     13636380.04      2381559.17     13635721.25
      2381030.28     13635656.30      2380315.84     13635749.08
#Sta/Elev= 30
  3734.8  288.07  3754.3  287.22  3783.8  288.74  3920.1  289.06  4249.3  279.16
  4462.8  274.89  4618.9  271.72  4636.5  270.90  4785.9  273.69  4939.9  274.08
  4990.3  273.08  5000.4  268.42  5006.9  268.05  5007.4  267.55  5014.0  268.05
  5020.5  271.57  5030.6  272.98  5085.5  273.24  5205.3  272.23  5283.1  277.51
  5580.9  284.66  5596.4  285.81  5675.7  288.47  5691.9  287.75  5746.2  288.45
  5756.3  286.86  5786.6  287.24  5796.7  289.35  5818.3  290.52  6118.5  299.20
#Mann=11,-1,0
  3734.8    0.07       0  4462.8    0.12       0  4618.9    0.05       0
  5006.9    0.05       0  5014.0    0.05       0  5085.5    0.12       0
  5283.1    0.07       0  5580.9   0.035       0  5596.4    0.07       0
  5691.9   0.035       0  5818.3    0.07       0
Bank Sta=5006.9,5014
Exp/Cntr=0.3,0.1

Type RM Length L Ch R = 1,442,0,0,0
BEGIN DESCRIPTION:
B20138
END DESCRIPTION:
XS GIS Cut Line= 3
      2382505.59     13636250.13      2381262.25     13635173.81
      2380584.87     13635016.06
#Sta/Elev= 30
  3507.1  285.56  3680.9  286.34  4128.3  276.24  4241.5  275.45  4354.4  270.04
  4396.4  270.02  4482.6  272.53  4673.5  270.59  4787.5  270.71  4808.3  272.08
  4857.7  270.38  4865.4  272.41  4879.6  272.85  4951.7  272.64  4992.6  268.53
  5003.3  265.90  5003.8  265.40  5010.5  265.90  5014.5  269.13  5021.1  271.00
  5078.1  270.24  5107.4  271.88  5171.4  272.19  5189.8  270.75  5230.9  273.36
  5436.7  274.54  5558.2  279.51  5672.4  285.93  5816.2  290.62  5847.1  293.11
#Mann=9,-1,0
  3507.1    0.07       0  4241.5    0.12       0  4396.4     0.1       0
  4951.7   0.035       0  5003.3   0.035       0  5010.5   0.035       0
  5107.4     0.1       0  5436.7    0.12       0  5558.2    0.07       0
Bank Sta=5003.3,5010.5
Exp/Cntr=0.3,0.1

Chan Stop Cuts=-1