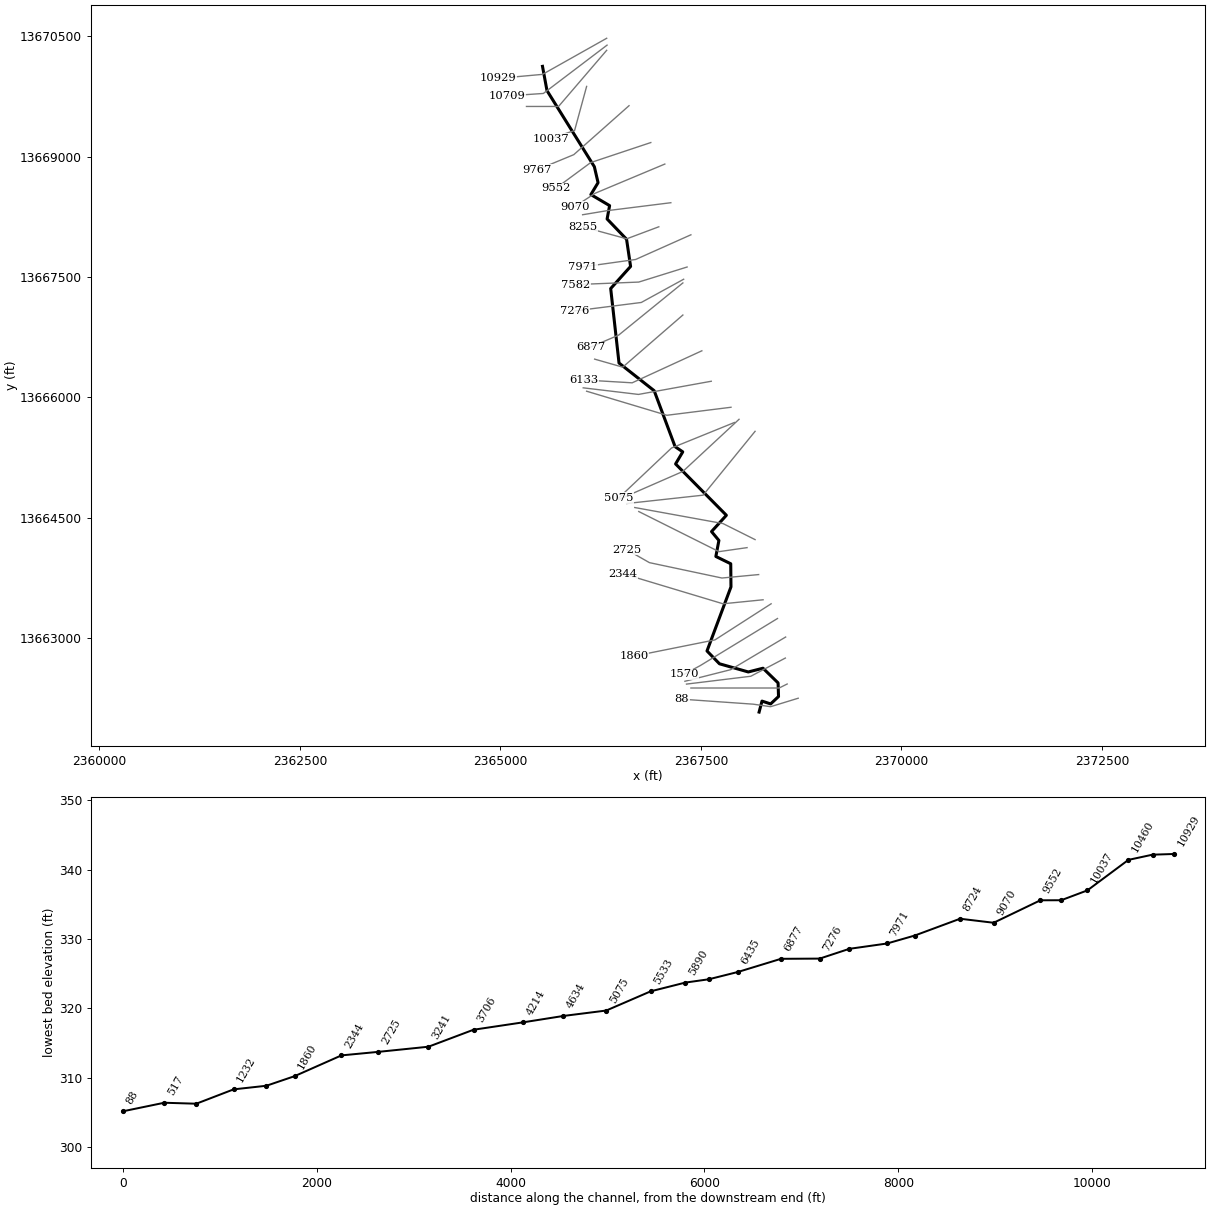
--- RED BRANCH.prj (project) ---

Proj Title=RED BRANCH Base Level Engineering
Current Plan=p01
Default Exp/Contr=0.3,0.1
English Units
Geom File=g01
Flow File=f01
Plan File=p01
Y Axis Title=Elevation
X Axis Title(PF)=Main Channel Distance
X Axis Title(XS)=Station
BEGIN DESCRIPTION:
RED BRANCH
END DESCRIPTION:
DSS Export Rating Curves= 0
DSS Export Rating Curve Sorted= 0
DSS Export Volume Flow Curves= 0
DXF OffsetX= 0
DXF OffsetY= 0
DXF ScaleX= 1
DXF ScaleY= 10

--- RED BRANCH.p01 (plan) ---

Plan Title=Multiple Run
Short Identifier=Multiple
Geom File=g01
Flow File=f01
Subcritical Flow
K Sum by GR= 0
Std Step Tol= 0.01
Critical Tol= 0.01
Num of Std Step Trials= 20
Max Error Tol= 0.3
Flow Tol Ratio= 0.001
Split Flow NTrial= 30
Split Flow Tol= 0.02
Split Flow Ratio= 0.02
Log Output Level= 0
Friction Slope Method= 1
Unsteady Friction Slope Method= 2
Unsteady Bridges Friction Slope Method= 1
Parabolic Critical Depth
Global Vel Dist=  1 , 1 , 1
Global Log Level= 0
CheckData=True
Encroach Param= -1, 0, 0, 0
BEGIN DESCRIPTION:
Multiple Run
END DESCRIPTION:

--- RED BRANCH.f01 (steady flow) ---

Flow Title=Multiple
Number of Profiles=7
Profile Names=10-year,25-year,50-year,1pct_min,100-year,1pct_plu,500-year
River Rch & RM= RED BRANCH,Reach-1,10929
     796    1310    1783    1175    2344    4678    4017
River Rch & RM= RED BRANCH,Reach-1,10460
     964    1596    2180    1439    2872    5730    4944
River Rch & RM= RED BRANCH,Reach-1,1570
    1386    2335    3226    2152    4293    8566    7546
Boundary for River Rch & Prof#=RED BRANCH,Reach-1,1
Up Type=0
Dn Type=3
Dn Slope=0.005
Boundary for River Rch & Prof#=RED BRANCH,Reach-1,2
Up Type=0
Dn Type=3
Dn Slope=0.005
Boundary for River Rch & Prof#=RED BRANCH,Reach-1,3
Up Type=0
Dn Type=3
Dn Slope=0.005
Boundary for River Rch & Prof#=RED BRANCH,Reach-1,4
Up Type=0
Dn Type=3
Dn Slope=0.005
Boundary for River Rch & Prof#=RED BRANCH,Reach-1,5
Up Type=0
Dn Type=3
Dn Slope=0.005
Boundary for River Rch & Prof#=RED BRANCH,Reach-1,6
Up Type=0
Dn Type=3
Dn Slope=0.005
Boundary for River Rch & Prof#=RED BRANCH,Reach-1,7
Up Type=0
Dn Type=3
Dn Slope=0.005

--- RED BRANCH.g01 (geometry) ---

Geom Title=Existing Conditions
Program Version=4.10

River Reach=RED BRANCH      ,Reach-1
Reach XY= 30
        2365525.       13670125.      2365580.83      13669822.7
      2366171.46     13668873.53      2366217.67      13668674.9
      2366128.01     13668526.43      2366361.62     13668388.74
       2366330.3     13668222.33      2366572.93     13667969.14
      2366623.03     13667630.68      2366375.06     13667354.97
      2366478.82     13666426.58      2366917.18     13666081.19
      2367178.19     13665383.35      2367273.47     13665319.12
      2367183.96     13665168.33      2367817.23     13664528.41
        2367632.     13664325.22      2367723.95     13664214.56
       2367686.1     13664014.89      2367871.54     13663923.97
      2367874.39     13663635.63      2367575.59     13662836.84
      2367730.85     13662677.06      2368090.39     13662575.08
      2368273.72     13662621.63      2368461.78     13662438.67
       2368467.2     13662268.79      2368368.96     13662176.65
      2368261.22     13662211.69        2368225.       13662075.

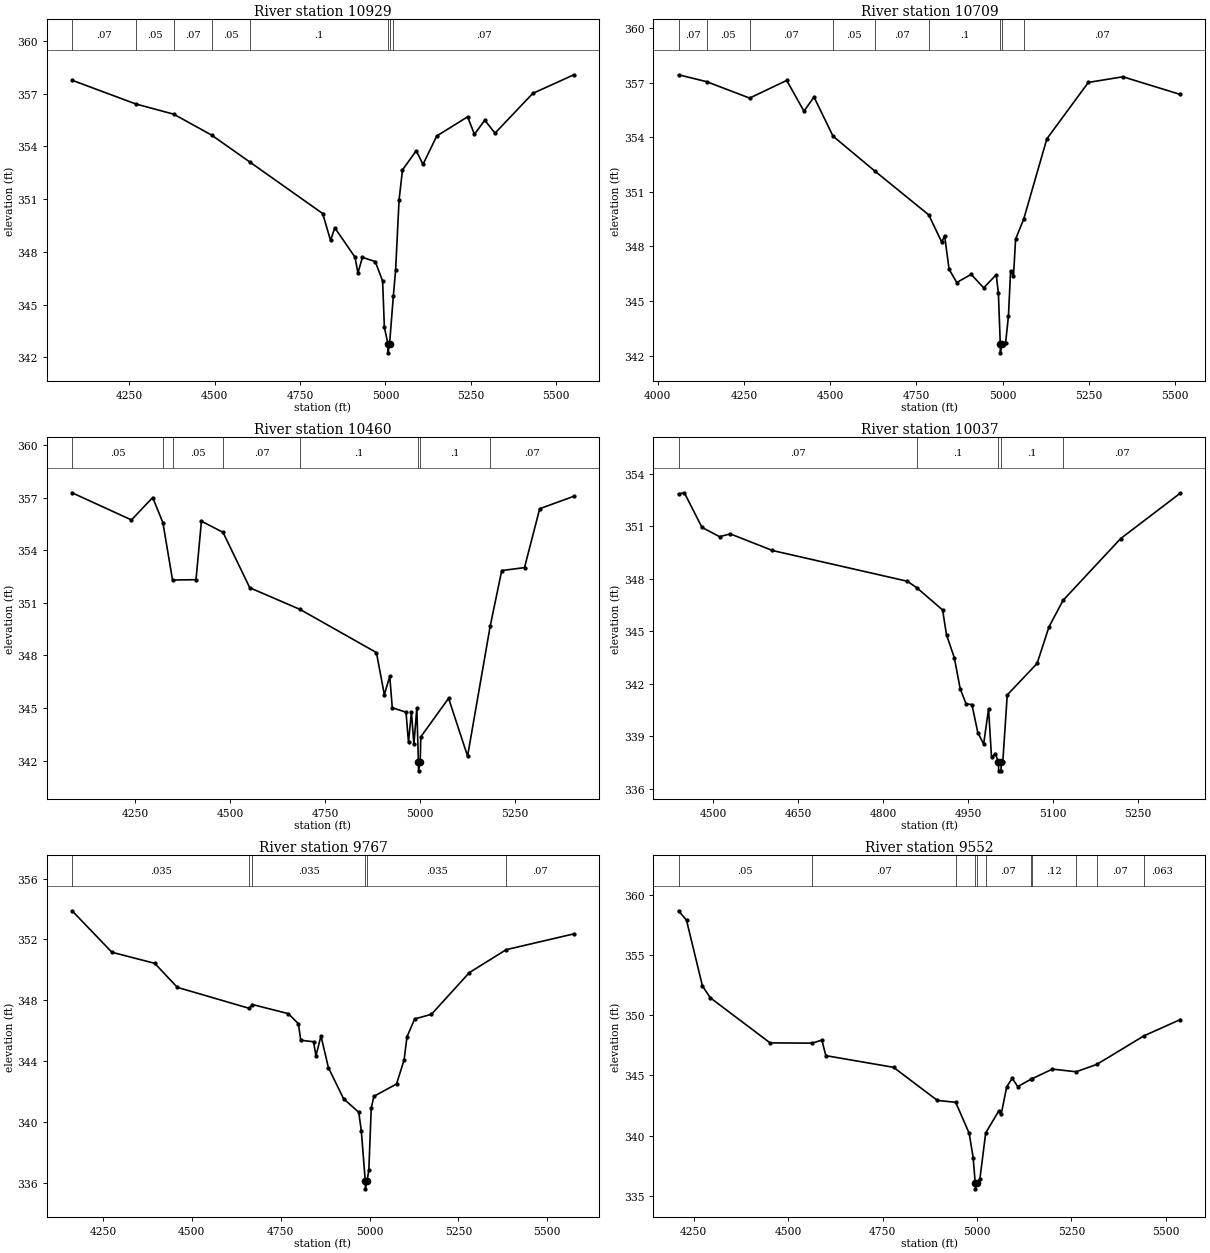
Type RM Length L Ch R = 1 ,10929   ,220,220,220
BEGIN DESCRIPTION:
RED BRANCH 21.0
END DESCRIPTION:
XS GIS Cut Line= 3
      2366325.01     13670475.01        2365525.       13670025.
      2364974.96       13669975.
#Sta/Elev= 30
    4082  357.76  4268.7  356.41  4379.8  355.83  4490.9  354.64    4602  353.12
  4816.3  350.18  4839.3  348.65  4851.7  349.37    4911   347.7  4919.6  346.79
  4932.6  347.69  4970.3  347.45  4991.9  346.34    4997  343.71  5007.6  342.76
  5007.9  342.26  5012.2  342.76  5023.4  345.51    5030  346.98  5040.1  350.96
  5050.1  352.66  5090.3  353.75  5110.3  352.98  5150.5  354.59  5240.9  355.68
    5261  354.68  5291.1  355.49  5321.2  354.75  5431.7  357.01  5552.2  358.07
#Mann= 8 ,-1 , 0
    4082     .07       0  4268.7     .05       0  4379.8     .07       0
  4490.9     .05       0    4602      .1       0  5007.6     .05       0
  5012.2      .1       0  5023.4     .07       0
Bank Sta=5007.6,5012.2
XS Rating Curve= 0 ,0
Exp/Cntr=0.3,0.1

Type RM Length L Ch R = 1 ,10709   ,249,249,249
BEGIN DESCRIPTION:
B20150
END DESCRIPTION:
XS GIS Cut Line= 3
      2366329.87     13670389.63      2365535.63      13669787.1
      2365078.92     13669755.87
#Sta/Elev= 30
  4060.5  357.43  4142.2  357.05  4266.5  356.15  4374.2  357.12  4424.1  355.43
  4453.2  356.21  4508.3  354.06  4629.1  352.15  4785.7  349.74  4823.5  348.24
  4831.8   348.6  4844.8  346.75  4867.1  346.02  4908.8  346.47  4945.2  345.73
  4981.5  346.45  4987.8  345.43  4993.2  342.66  4993.5  342.16  4997.8  342.66
  5008.6   342.7  5016.9  344.17  5023.2  346.67  5031.5  346.36  5037.7  348.41
  5061.3  349.51  5128.2  353.91  5248.5  357.01  5348.7  357.32  5515.2  356.35
#Mann= 9 ,-1 , 0
  4060.5     .07       0  4142.2     .05       0  4266.5     .07       0
  4508.3     .05       0  4629.1     .07       0  4785.7      .1       0
  4993.2     .05       0  4997.8      .1       0  5061.3     .07       0
Bank Sta=4993.2,4997.8
XS Rating Curve= 0 ,0
Exp/Cntr=0.3,0.1

Type RM Length L Ch R = 1 ,10460   ,423,423,423
BEGIN DESCRIPTION:
RED BRANCH 20.0
END DESCRIPTION:
XS GIS Cut Line= 3
      2366324.99     13670324.99        2365725.       13669625.
      2365325.04       13669625.
#Sta/Elev= 30
  4083.1  357.28  4239.5  355.73  4295.5  357.01  4322.4  355.57  4347.8   352.3
  4409.6  352.32  4423.9  355.66  4480.8  355.02  4551.2  351.86  4683.9  350.62
  4884.9  348.16  4905.7  345.76    4920   346.8  4926.6  345.01  4962.8  344.76
  4969.4  343.04  4977.1  344.76  4983.6  342.93  4991.3     345  4995.5  341.91
  4995.9  341.41  5000.3  341.91  5001.8  343.35    5075  345.55    5125  342.25
  5184.5  349.66    5215  352.84    5275  353.01    5315  356.37    5405  357.08
#Mann= 8 ,-1 , 0
  4083.1     .05       0  4322.4     .07       0  4347.8     .05       0
  4480.8     .07       0  4683.9      .1       0  4995.5     .05       0
  5000.3      .1       0  5184.5     .07       0
Bank Sta=4995.5,5000.3
XS Rating Curve= 0 ,0
Exp/Cntr=0.3,0.1

Type RM Length L Ch R = 1 ,10037   ,270,270,270
BEGIN DESCRIPTION:
RED BRANCH 19.0
END DESCRIPTION:
XS GIS Cut Line= 3
      2366074.99     13669874.96        2365925.       13669325.
      2365624.97     13669224.99
#Sta/Elev= 30
  4438.6  352.85  4448.9  352.91    4480  350.93  4511.1   350.4  4530.1  350.56
  4604.4  349.61  4842.8  347.85  4859.8  347.47    4905  346.21  4911.9  344.79
  4925.7  343.48  4936.1   341.7  4946.5  340.84  4956.8   340.8  4967.2   339.2
  4977.5  338.54  4986.2  340.55  4991.4   337.8  4998.3  337.98  5003.7  337.51
    5004  337.01  5008.1  337.01  5008.5  337.51  5011.3  337.51  5019.2  341.35
  5071.9  343.15    5093  345.25  5117.8  346.76  5219.5  350.29  5324.9  352.89
#Mann= 5 ,-1 , 0
  4438.6     .07       0  4859.8      .1       0  5003.7     .05       0
  5008.5      .1       0  5117.8     .07       0
Bank Sta=5003.7,5008.5
XS Rating Curve= 0 ,0
Exp/Cntr=0.3,0.1

Type RM Length L Ch R = 1 ,9767    ,215,215,215
BEGIN DESCRIPTION:
B20149
END DESCRIPTION:
XS GIS Cut Line= 3
      2366603.75     13669634.51      2365915.14     13669024.16
      2365461.33     13668836.37
#Sta/Elev= 30
  4163.2  353.89  4275.3  351.16  4395.8  350.43  4459.3  348.85  4661.4  347.47
  4670.5  347.72  4771.3  347.12  4799.7  346.46  4806.4  345.37  4842.4  345.27
  4849.1  344.35  4863.3  345.65  4884.2  343.56  4926.8  341.52  4969.5  340.63
  4976.7  339.41  4987.9  336.09  4988.3  335.59  4992.8  336.09  4997.9  336.84
  5004.6   340.9  5012.2  341.68  5075.7  342.49    5097  344.07  5105.2   345.6
  5126.8  346.77  5174.1  347.08  5280.5  349.82  5384.2  351.33  5574.5  352.37
#Mann= 6 ,-1 , 0
  4163.2    .035       0  4661.4     .07       0  4670.5    .035       0
  4987.9    .035       0  4992.8    .035       0  5384.2     .07       0
Bank Sta=4987.9,4992.8
XS Rating Curve= 0 ,0
Exp/Cntr=0.3,0.1

Type RM Length L Ch R = 1 ,9552    ,482,482,482
BEGIN DESCRIPTION:
RED BRANCH 18.0
END DESCRIPTION:
XS GIS Cut Line= 3
      2366875.03     13669175.01        2366125.       13668925.
      2365692.13     13668605.52
#Sta/Elev= 30
  4209.7  358.69  4230.8  357.91    4273  352.44  4294.1  351.45  4452.2  347.71
  4563.6  347.69  4589.2  347.94  4599.7  346.65  4778.9  345.68  4894.9  342.93
  4943.6  342.77  4979.2   340.2  4989.8  338.17  4995.2  336.08  4995.6  335.58
  5000.2  336.08  5007.6   336.4    5023  340.23  5057.7  342.06  5063.9  341.76
  5078.6  344.06  5093.2  344.76  5107.9  344.08  5142.8  344.69  5144.3  344.71
  5199.7  345.53  5262.5  345.31    5317  345.92  5442.3   348.3  5538.3  349.65
#Mann= 11 ,-1 , 0
  4209.7     .05       0  4563.6     .07       0  4943.6     .12       0
  4995.2     .05       0  5000.2     .12       0    5023     .07       0
  5142.8    .035       0  5144.3     .12       0  5262.5    .035       0
    5317     .07       0  5442.3    .063       0
Bank Sta=4995.2,5000.2
XS Rating Curve= 0 ,0
Exp/Cntr=0.3,0.1

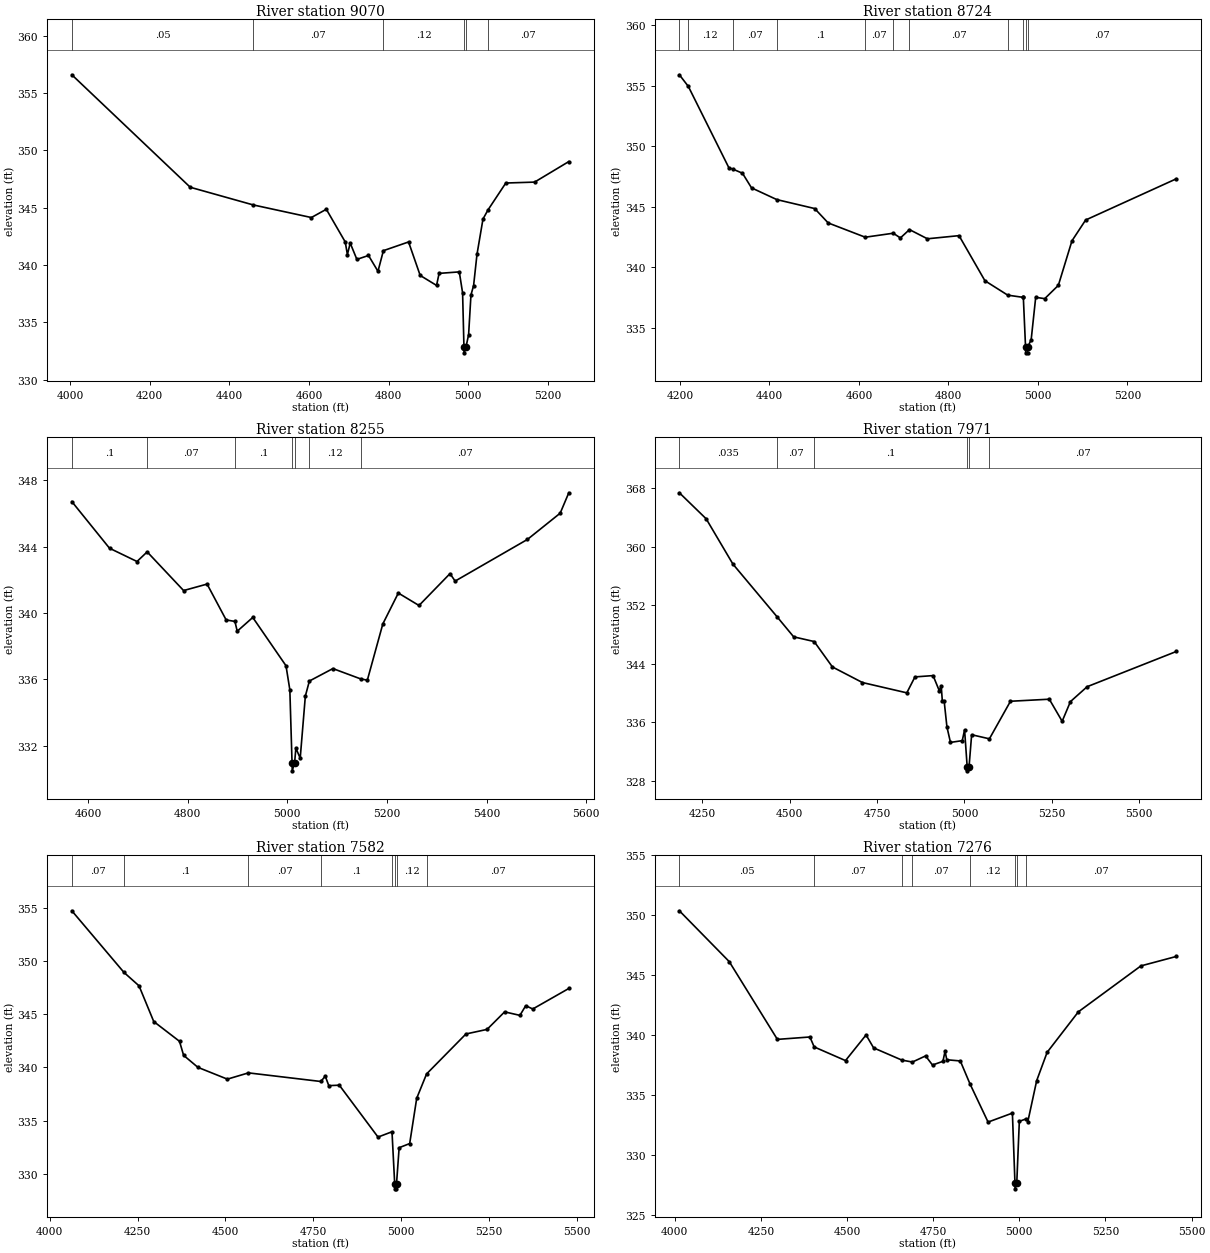
Type RM Length L Ch R = 1 ,9070    ,346,346,346
BEGIN DESCRIPTION:
RED BRANCH 17.0
END DESCRIPTION:
XS GIS Cut Line= 3
      2367049.76     13668906.78      2366181.19     13668542.92
      2365925.02     13668375.01
#Sta/Elev= 30
  4004.6  356.59    4302  346.78  4460.1  345.24  4606.1  344.14  4643.7  344.86
  4691.2  342.01  4696.6  340.91  4703.7  341.91  4720.4  340.49  4749.6  340.83
  4773.4  339.45    4787  341.25  4850.2  342.01  4879.4  339.09  4920.5  338.22
  4926.9  339.27  4977.6   339.4  4985.9  337.57  4989.3  332.84  4989.7  332.34
  4994.4  332.84    5001  333.93  5006.9  337.39  5013.5   338.2    5022  340.92
  5037.1  344.01  5049.8  344.81  5094.4  347.15  5166.7  347.23  5252.6  349.02
#Mann= 6 ,-1 , 0
  4004.6     .05       0  4460.1     .07       0    4787     .12       0
  4989.3     .05       0  4994.4     .12       0  5049.8     .07       0
Bank Sta=4989.3,4994.4
XS Rating Curve= 0 ,0
Exp/Cntr=0.3,0.1

Type RM Length L Ch R = 1 ,8724    ,469,469,469
BEGIN DESCRIPTION:
RED BRANCH 16.0
END DESCRIPTION:
XS GIS Cut Line= 3
      2367124.96     13668424.99        2366325.       13668325.
      2366025.02       13668275.
#Sta/Elev= 30
  4198.9  355.91  4218.9  354.95  4309.7  348.21  4317.7  348.12  4339.9  347.77
  4360.1  346.56  4416.6  345.59  4501.2  344.85  4531.4  343.66  4614.2  342.48
  4676.8  342.81  4692.7  342.42    4713  343.11  4753.1  342.35  4823.7  342.61
  4881.6  338.88  4932.5  337.69  4966.4  337.51  4967.3  337.57  4972.3  333.42
  4972.7  332.92    4977  332.92  4977.4  333.42  4984.9  334.01    4995  337.51
  5015.2   337.4  5045.6   338.5    5076  342.18  5106.5   343.9  5309.2  347.31
#Mann= 11 ,-1 , 0
  4198.9     .07       0  4218.9     .12       0  4317.7     .07       0
  4416.6      .1       0  4614.2     .07       0  4676.8     .12       0
    4713     .07       0  4932.5     .12       0  4966.4     .07       0
  4972.3     .05       0  4977.4     .07       0
Bank Sta=4972.3,4977.4
XS Rating Curve= 0 ,0
Exp/Cntr=0.3,0.1

Type RM Length L Ch R = 1 ,8255    ,284,284,284
BEGIN DESCRIPTION:
RED BRANCH 15.0
END DESCRIPTION:
XS GIS Cut Line= 3
      2366974.98     13668124.99        2366575.       13667975.
      2366024.97     13668125.01
#Sta/Elev= 30
  4567.7  346.71  4643.3   343.9  4698.5   343.1  4718.9  343.68    4792  341.35
  4839.1  341.74  4877.4  339.58    4895  339.49  4899.6   338.9  4930.8  339.73
  4997.5  336.82  5005.2  335.37  5009.6  330.99    5010  330.49  5014.8  330.99
  5017.3  331.86    5026  331.25  5036.3  334.99  5044.4   335.9  5091.6  336.65
  5147.2  336.03  5160.7  335.95  5191.8  339.34  5222.9   341.2  5264.4  340.45
  5326.6  342.37  5336.9  341.92    5482  344.43  5547.7  346.01    5565  347.24
#Mann= 7 ,-1 , 0
  4567.7      .1       0  4718.9     .07       0    4895      .1       0
  5009.6     .05       0  5014.8      .1       0  5044.4     .12       0
  5147.2     .07       0
Bank Sta=5009.6,5014.8
XS Rating Curve= 0 ,0
Exp/Cntr=0.3,0.1

Type RM Length L Ch R = 1 ,7971    ,389,389,389
BEGIN DESCRIPTION:
RED BRANCH 14.0
END DESCRIPTION:
XS GIS Cut Line= 3
        2367375.       13668025.      2366685.91     13667717.38
      2366024.97       13667625.
#Sta/Elev= 30
  4184.3  367.39    4261  363.83  4337.6  357.63  4463.6  350.44  4511.4  347.68
    4570  347.04  4622.3  343.56  4708.1  341.43  4835.1  340.02  4858.4   342.2
  4910.3  342.38    4928  340.31  4933.5     341  4936.7  338.92  4941.9  338.92
  4949.9  335.36    4960  333.24  4993.8  333.48  5000.4  334.96  5007.9  329.85
  5008.3  329.35  5013.1  329.85  5020.6  334.29  5071.4  333.73  5131.7  338.87
  5242.8  339.15  5279.6  336.13  5303.3  338.82  5351.1  340.86  5606.3  345.68
#Mann= 6 ,-1 , 0
  4184.3    .035       0  4463.6     .07       0    4570      .1       0
  5007.9     .05       0  5013.1      .1       0  5071.4     .07       0
Bank Sta=5007.9,5013.1
XS Rating Curve= 0 ,0
Exp/Cntr=0.3,0.1

Type RM Length L Ch R = 1 ,7582    ,306,306,306
BEGIN DESCRIPTION:
B20148
END DESCRIPTION:
XS GIS Cut Line= 3
      2367327.53     13667623.47      2366725.03     13667435.68
      2365942.54     13667404.38
#Sta/Elev= 30
  4062.8  354.74  4211.2  348.94    4254  347.68  4295.9  344.32  4369.2  342.46
  4380.9  341.14  4421.6  340.01  4505.4   338.9  4565.4  339.49  4771.3  338.68
    4784  339.18    4794  338.29    4824  338.33  4934.1  333.45  4973.9  333.95
  4981.5  329.08  4981.9  328.58  4986.3  328.58  4986.8  329.08  4994.2  332.45
  5024.2  332.84  5044.2   337.1  5072.3  339.39  5184.3  343.15  5244.4  343.58
  5294.4  345.23  5337.9   344.9  5354.4  345.81  5374.5   345.5    5477  347.43
#Mann= 8 ,-1 , 0
  4062.8     .07       0  4211.2      .1       0  4565.4     .07       0
  4771.3      .1       0  4973.9     .12       0  4981.5     .05       0
  4986.8     .12       0  5072.3     .07       0
Bank Sta=4981.5,4986.8
XS Rating Curve= 0 ,0
Exp/Cntr=0.3,0.1

Type RM Length L Ch R = 1 ,7276    ,399,399,399
BEGIN DESCRIPTION:
RED BRANCH 13.0
END DESCRIPTION:
XS GIS Cut Line= 3
      2367284.52     13667470.89      2366756.33     13667181.37
      2365922.94     13667075.72
#Sta/Elev= 30
  4013.2  350.37  4157.9  346.13  4297.7  339.64  4392.1  339.84  4404.5  339.01
  4495.4  337.87  4555.1  340.01    4577  338.93  4659.1  337.91  4689.6  337.75
  4727.8  338.26  4747.9   337.5  4778.2  337.81  4784.3  338.65  4789.4  337.94
  4828.6  337.84  4856.8  335.92  4909.2  332.74  4979.8  333.49  4987.2  327.67
  4987.6  327.17  4992.5  327.67  4999.9   332.8  5019.7  333.01  5024.6  332.78
  5050.3   336.2  5080.6  338.56  5171.3  341.94  5352.7  345.77  5455.6  346.56
#Mann= 8 ,-1 , 0
  4013.2     .05       0  4404.5     .07       0  4659.1    .035       0
  4689.6     .07       0  4856.8     .12       0  4987.2     .05       0
  4992.5     .12       0  5019.7     .07       0
Bank Sta=4987.2,4992.5
XS Rating Curve= 0 ,0
Exp/Cntr=0.3,0.1

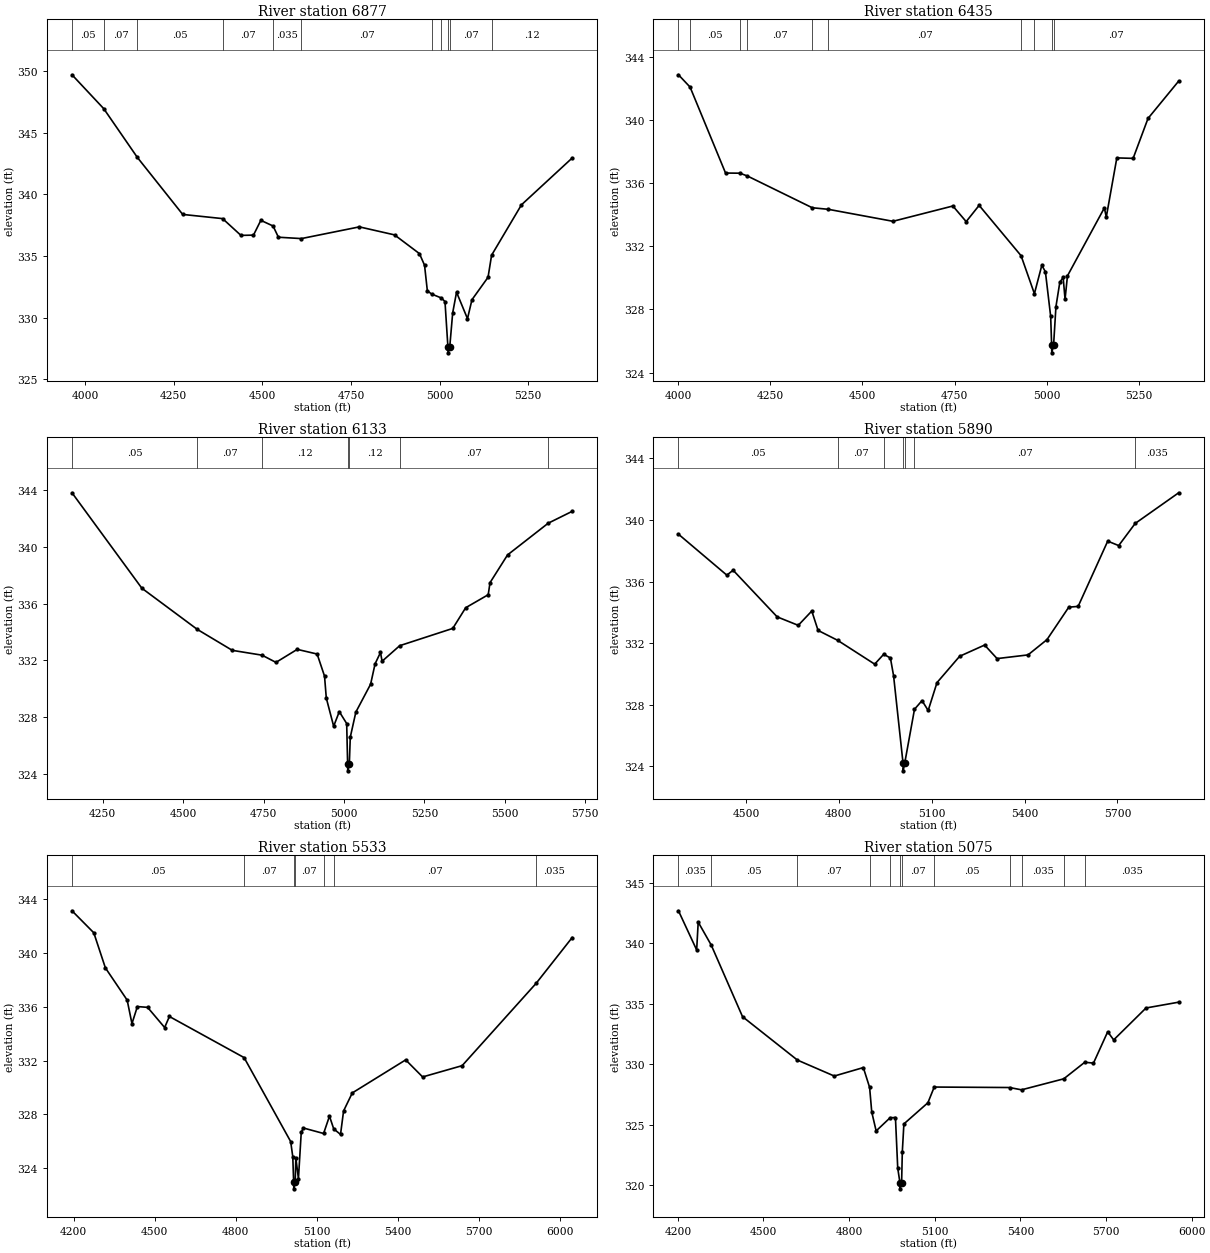
Type RM Length L Ch R = 1 ,6877    ,442,442,442
BEGIN DESCRIPTION:
RED BRANCH 12.0
END DESCRIPTION:
XS GIS Cut Line= 3
      2367274.96     13667424.97        2366475.       13666775.
      2366125.02     13666625.01
#Sta/Elev= 30
  3962.9   349.7  4052.5  346.95  4147.2     343  4275.3  338.37  4387.9  338.03
  4439.6  336.67    4475  336.69  4495.8  337.89  4530.3  337.43  4545.4  336.52
  4610.2  336.41  4773.8  337.36    4873  336.71  4943.3  335.19  4957.7  334.25
  4965.6  332.18  4977.6  331.91  5005.3  331.59  5015.4   331.3  5023.6  327.64
    5024  327.14  5028.9  327.64  5037.1  330.38    5048  332.06  5078.9  329.91
  5091.5  331.45  5136.9  333.27  5146.9  335.06  5231.2  339.15  5374.4  342.95
#Mann= 11 ,-1 , 0
  3962.9     .05       0  4052.5     .07       0  4147.2     .05       0
  4387.9     .07       0  4530.3    .035       0  4610.2     .07       0
  4977.6     .12       0  5005.3     .07       0  5023.6     .05       0
  5028.9     .07       0  5146.9     .12       0
Bank Sta=5023.6,5028.9
XS Rating Curve= 0 ,0
Exp/Cntr=0.3,0.1

Type RM Length L Ch R = 1 ,6435    ,302,302,302
BEGIN DESCRIPTION:
RED BRANCH 11.0
END DESCRIPTION:
XS GIS Cut Line= 3
      2367274.97     13667024.98        2366525.       13666375.
      2366175.04     13666474.99
#Sta/Elev= 30
  4001.4  342.88  4032.9   342.1  4129.1  336.65  4168.2  336.64  4188.6  336.46
  4364.1  334.45  4407.7  334.35  4583.1  333.59  4745.5  334.56  4781.6  333.57
  4816.7   334.6  4930.4  331.41  4966.6     329  4986.7   330.8  4996.4  330.39
  5010.7  327.56  5013.3  325.75  5013.7  325.25  5018.6  325.75    5025  328.18
  5035.4  329.71  5044.5  330.04  5049.7  328.65  5056.2  330.13  5156.3  334.44
  5161.5  333.86  5190.1  337.61  5234.3  337.58  5274.6  340.11  5357.8  342.48
#Mann= 10 ,-1 , 0
  4001.4     .12       0  4032.9     .05       0  4168.2     .12       0
  4188.6     .07       0  4364.1     .12       0  4407.7     .07       0
  4930.4     .12       0  4966.6     .07       0  5013.3     .05       0
  5018.6     .07       0
Bank Sta=5013.3,5018.6
XS Rating Curve= 0 ,0
Exp/Cntr=0.3,0.1

Type RM Length L Ch R = 1 ,6133    ,243,243,243
BEGIN DESCRIPTION:
B20147
END DESCRIPTION:
XS GIS Cut Line= 3
      2367511.41     13666578.82      2366642.87     13666179.76
      2366044.24     13666214.98
#Sta/Elev= 30
  4154.3  343.83  4371.5  337.09    4544  334.18  4652.8   332.7  4745.2  332.36
  4788.6  331.85  4854.7  332.77  4916.6  332.44  4939.6  330.88  4945.1  329.33
    4968  327.34  4985.5  328.37  5008.5  327.53  5011.4  324.69  5011.8  324.19
  5016.7  324.69  5019.7  326.57    5037  328.34  5082.9  330.31  5096.8  331.75
  5113.6  332.55  5118.6  331.93  5173.4  333.03  5338.4  334.25  5378.5  335.71
  5448.6  336.63  5454.2  337.48  5508.7  339.44  5635.1  341.68  5709.8  342.52
#Mann= 7 ,-1 , 0
  4154.3     .05       0    4544     .07       0  4745.2     .12       0
  5011.4     .05       0  5016.7     .12       0  5173.4     .07       0
  5635.1    .035       0
Bank Sta=5011.4,5016.7
XS Rating Curve= 0 ,0
Exp/Cntr=0.3,0.1

Type RM Length L Ch R = 1 ,5890    ,357,357,357
BEGIN DESCRIPTION:
B20146
END DESCRIPTION:
XS GIS Cut Line= 3
      2367628.79     13666199.32      2366721.12       13666035.
      2366032.53     13666117.16
#Sta/Elev= 30
  4281.9  339.08  4438.2  336.42  4458.5  336.74  4600.8  333.71  4668.9  333.16
  4712.6  334.09  4732.9  332.83  4795.9  332.19  4915.8  330.64  4944.9  331.28
  4966.6  331.04  4976.8  329.89  5007.4  324.21  5007.8  323.71  5012.8  324.21
  5044.4  327.71  5068.7  328.27  5088.6  327.63  5117.1  329.44  5190.2  331.15
  5270.9  331.88  5311.2     331  5411.1  331.24  5472.3  332.23  5542.8  334.34
    5573  334.39  5668.6  338.63    5704  338.34  5757.4  339.78  5897.8  341.77
#Mann= 7 ,-1 , 0
  4281.9     .05       0  4795.9     .07       0  4944.9     .12       0
  5007.4     .05       0  5012.8     .12       0  5044.4     .07       0
  5757.4    .035       0
Bank Sta=5007.4,5012.8
XS Rating Curve= 0 ,0
Exp/Cntr=0.3,0.1

Type RM Length L Ch R = 1 ,5533    ,458,458,458
BEGIN DESCRIPTION:
RED BRANCH 10.0
END DESCRIPTION:
XS GIS Cut Line= 3
      2367875.04     13665875.01        2367075.       13665775.
        2366075.       13666075.
#Sta/Elev= 30
  4193.8  343.15  4274.5  341.51  4317.3   338.9  4397.9   336.5  4415.6  334.75
  4435.7  336.02  4473.5  335.96  4536.5  334.46  4554.1  335.28  4830.4  332.22
  5002.7  325.97  5010.5  324.84  5013.7  322.95  5014.2  322.45  5019.4  322.95
  5021.8  324.76  5031.4  323.21  5041.8  326.65  5049.7  326.98  5124.5  326.57
  5146.2  327.86    5162  326.91  5187.1   326.5  5198.4  328.25  5230.6  329.59
  5428.1  332.05  5490.8  330.78  5636.9  331.62  5910.7  337.75  6044.1  341.16
#Mann= 7 ,-1 , 0
  4193.8     .05       0  4830.4     .07       0  5013.7     .05       0
  5019.4     .07       0  5124.5     .12       0    5162     .07       0
  5910.7    .035       0
Bank Sta=5013.7,5019.4
XS Rating Curve= 0 ,0
Exp/Cntr=0.3,0.1

Type RM Length L Ch R = 1 ,5075    ,441,441,441
BEGIN DESCRIPTION:
RED BRANCH 9.0
END DESCRIPTION:
XS GIS Cut Line= 3
       2367916.8     13665684.92      2367133.31     13665366.94
      2366474.44     13664743.69
#Sta/Elev= 30
  4202.2  342.68    4266  339.44  4271.4  341.74  4317.1  339.84  4426.7  333.92
    4619  330.33  4748.1  329.01  4849.9  329.71  4871.9  328.07  4879.4  326.03
  4894.8  324.47  4943.7  325.56  4962.4  325.58  4970.4   321.4  4978.2  320.18
  4978.7  319.68    4984  320.18  4986.5  322.75    4992  325.05  5076.1   326.8
  5098.3   328.1    5362  328.06  5404.2  327.87  5552.1  328.78  5625.7  330.15
  5656.2  330.08    5706  332.67    5727     332  5840.3  334.64  5954.7  335.12
#Mann= 12 ,-1 , 0
  4202.2    .035       0  4317.1     .05       0    4619     .07       0
  4871.9     .12       0  4943.7     .07       0  4978.2     .05       0
    4984     .07       0  5098.3     .05       0    5362     .07       0
  5404.2    .035       0  5552.1     .05       0  5625.7    .035       0
Bank Sta=4978.2,4984
XS Rating Curve= 0 ,0
Exp/Cntr=0.3,0.1

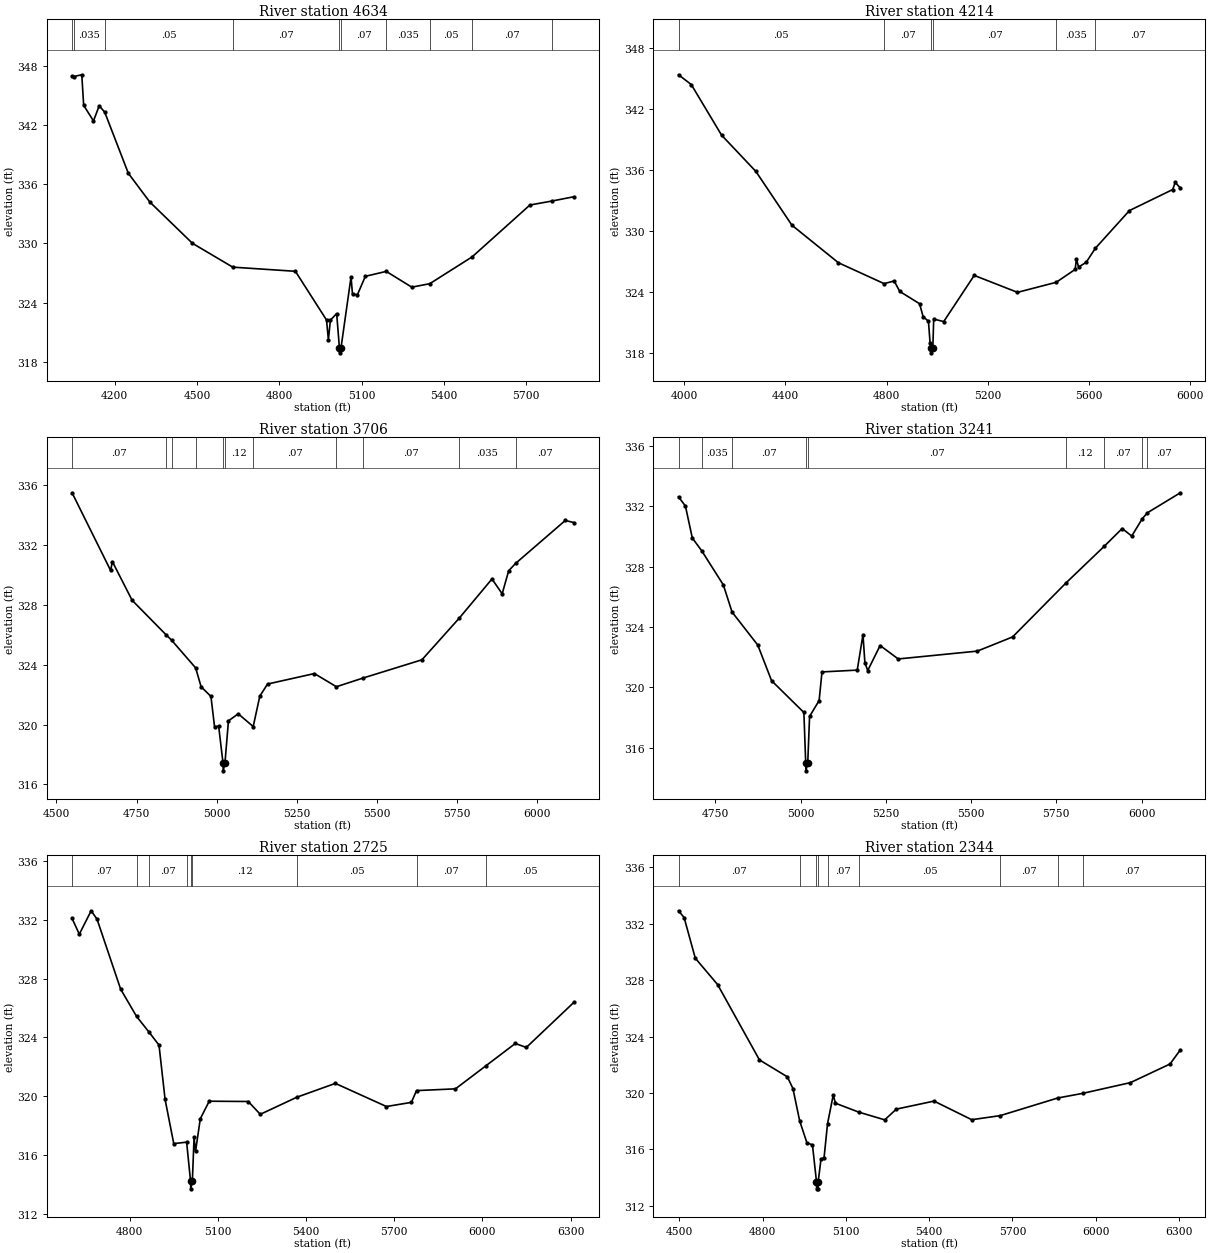
Type RM Length L Ch R = 1 ,4634    ,420,420,420
BEGIN DESCRIPTION:
RED BRANCH 8.0
END DESCRIPTION:
XS GIS Cut Line= 3
      2367975.02     13665725.01        2367275.       13665075.
      2366474.98     13664724.99
#Sta/Elev= 30
  4044.7  346.94  4050.2  346.92  4080.1   347.1    4087     344  4122.7  342.42
  4143.7  343.96  4163.8   343.3  4249.7  337.11  4327.9   334.2  4483.2  330.01
  4630.3  327.59  4858.5  327.17  4971.9  322.23  4978.7  320.23  4986.1  322.22
  5008.9  322.88  5018.9   319.4  5019.4   318.9  5024.7   319.4  5061.2  326.59
  5066.6  324.84  5084.6   324.8  5113.4  326.66  5189.5  327.16  5282.6  325.56
    5348  325.91  5502.4  328.63    5713  333.89  5792.2  334.29  5873.2  334.73
#Mann= 10 ,-1 , 0
  4044.7     .05       0  4050.2    .035       0  4163.8     .05       0
  4630.3     .07       0  5018.9     .05       0  5024.7     .07       0
  5189.5    .035       0    5348     .05       0  5502.4     .07       0
  5792.2    .035       0
Bank Sta=5018.9,5024.7
XS Rating Curve= 0 ,0
Exp/Cntr=0.3,0.1

Type RM Length L Ch R = 1 ,4214    ,508,508,508
BEGIN DESCRIPTION:
RED BRANCH 7.0
END DESCRIPTION:
XS GIS Cut Line= 3
        2368175.     13665575.01       2367527.1     13664779.08
      2366574.96       13664675.
#Sta/Elev= 30
  3977.2  345.37  4027.5  344.41  4147.4  339.42  4283.2  335.84  4425.4  330.55
  4609.2  326.85    4790  324.79  4829.7  325.05    4852  324.02  4930.2  322.81
  4944.3  321.54  4965.4  321.08  4971.9  318.92  4976.9  318.47  4977.3  317.97
  4982.7  318.47  4986.2   321.3  5025.7  321.05  5146.4   325.6  5317.4  323.93
  5470.5  324.92  5545.5  326.19  5550.5  327.23  5558.9  326.42  5589.1  326.89
  5625.2  328.27  5760.1  331.99  5931.1  334.06  5941.1  334.76  5961.3  334.22
#Mann= 6 ,-1 , 0
  3977.2     .05       0    4790     .07       0  4976.9     .05       0
  4982.7     .07       0  5470.5    .035       0  5625.2     .07       0
Bank Sta=4976.9,4982.7
XS Rating Curve= 0 ,0
Exp/Cntr=0.3,0.1

Type RM Length L Ch R = 1 ,3706    ,465,465,465
BEGIN DESCRIPTION:
RED BRANCH 6.0
END DESCRIPTION:
XS GIS Cut Line= 3
      2368174.97     13664225.01        2367775.       13664425.
      2366675.02       13664625.
#Sta/Elev= 30
  4548.6  335.49  4668.8   330.3  4674.4  330.89  4735.8  328.31  4842.3  325.99
    4859  325.64    4934  323.79  4951.1  322.53  4981.8  321.88    4993  319.86
  5005.9  319.89  5019.5  317.41    5020  316.91  5025.4  317.41  5036.4  320.25
  5066.9  320.72  5113.6  319.87  5134.3  321.91  5158.4  322.71  5304.5  323.41
  5373.1  322.53  5454.6   323.1  5639.9  324.33  5756.2  327.11  5858.4  329.73
  5890.2  328.74  5910.5  330.28    5932  330.77  6087.1  333.64  6113.8   333.5
#Mann= 11 ,-1 , 0
  4548.6     .07       0  4842.3    .035       0    4859     .07       0
    4934     .12       0  5019.5     .05       0  5025.4     .12       0
  5113.6     .07       0  5373.1    .035       0  5454.6     .07       0
  5756.2    .035       0    5932     .07       0
Bank Sta=5019.5,5025.4
XS Rating Curve= 0 ,0
Exp/Cntr=0.3,0.1

Type RM Length L Ch R = 1 ,3241    ,516,516,516
BEGIN DESCRIPTION:
RED BRANCH 5.0
END DESCRIPTION:
XS GIS Cut Line= 3
      2368075.04     13664125.01        2367725.       13664075.
      2366725.02     13664574.99
#Sta/Elev= 30
  4642.1  332.63  4662.3  332.02  4682.5   329.9  4709.9  329.06  4773.5  326.79
  4799.1  324.99  4874.5   322.8  4914.9  320.44  5009.7  318.33  5015.1  314.96
  5015.6  314.46    5021  314.96  5026.4  318.07  5054.4  319.12  5062.8  321.02
  5166.2  321.14    5183  323.49  5188.6  321.64  5196.9  321.11  5233.3  322.77
  5286.4  321.88  5518.4   322.4  5621.8  323.34  5778.8  326.93  5890.5  329.35
  5943.2  330.53  5971.2  330.03  6002.1  331.18  6016.9  331.57  6113.7   332.9
#Mann= 9 ,-1 , 0
  4642.1     .07       0  4709.9    .035       0  4799.1     .07       0
  5015.1     .05       0    5021     .07       0  5778.8     .12       0
  5890.5     .07       0  6002.1    .035       0  6016.9     .07       0
Bank Sta=5015.1,5021
XS Rating Curve= 0 ,0
Exp/Cntr=0.3,0.1

Type RM Length L Ch R = 1 ,2725    ,381,381,381
BEGIN DESCRIPTION:
B20145
END DESCRIPTION:
XS GIS Cut Line= 4
      2368219.62     13663789.22      2367761.85     13663746.18
      2366858.06      13663937.9      2366576.32     13664098.33
#Sta/Elev= 30
  4603.3  332.08    4628  331.01  4668.2   332.6  4688.3  332.03  4768.6  327.28
  4822.7  325.43  4864.5  324.38  4899.2  323.48  4919.9  319.79  4949.4  316.79
  4993.2  316.89  5006.7  314.22  5007.2  313.72  5012.7  314.22  5018.5  317.21
  5023.5  316.27  5039.8  318.48  5070.1  319.67    5203  319.65  5243.9  318.78
  5368.3  319.94  5499.4  320.88  5673.2  319.31  5758.1  319.59  5775.7  320.39
  5908.3  320.51  6010.9  322.06  6111.9  323.59  6149.4  323.32  6311.2  326.38
#Mann= 9 ,-1 , 0
  4603.3     .07       0  4822.7    .035       0  4864.5     .07       0
  4993.2     .12       0  5006.7     .05       0  5012.7     .12       0
  5368.3     .05       0  5775.7     .07       0  6010.9     .05       0
Bank Sta=5006.7,5012.7
XS Rating Curve= 0 ,0
Exp/Cntr=0.3,0.1

Type RM Length L Ch R = 1 ,2344    ,484,484,484
BEGIN DESCRIPTION:
RED BRANCH 4.0
END DESCRIPTION:
XS GIS Cut Line= 3
      2368274.99       13663475.        2367775.       13663425.
      2366525.52     13663800.95
#Sta/Elev= 30
  4497.5  332.92  4517.6  332.44  4557.8  329.56  4638.2  327.69  4788.9  322.35
  4889.4  321.15  4909.5  320.32  4933.9  318.02  4959.8  316.48  4979.9  316.32
  4994.4  313.71  4994.9  313.21    5000  313.21  5000.5  313.71  5010.4  315.29
  5021.7  315.43  5034.2  317.83  5054.7  319.86  5062.6  319.28  5146.3  318.65
  5240.2   318.1  5281.9  318.86  5417.7  319.43  5553.5  318.11  5656.2   318.4
  5863.6  319.65  5953.7  319.98  6125.3  320.74  6267.8  322.06  6304.8  323.06
#Mann= 9 ,-1 , 0
  4497.5     .07       0  4933.9     .12       0  4994.4     .05       0
  5000.5     .12       0  5034.2     .07       0  5146.3     .05       0
  5656.2     .07       0  5863.6     .12       0  5953.7     .07       0
Bank Sta=4994.4,5000.5
XS Rating Curve= 0 ,0
Exp/Cntr=0.3,0.1

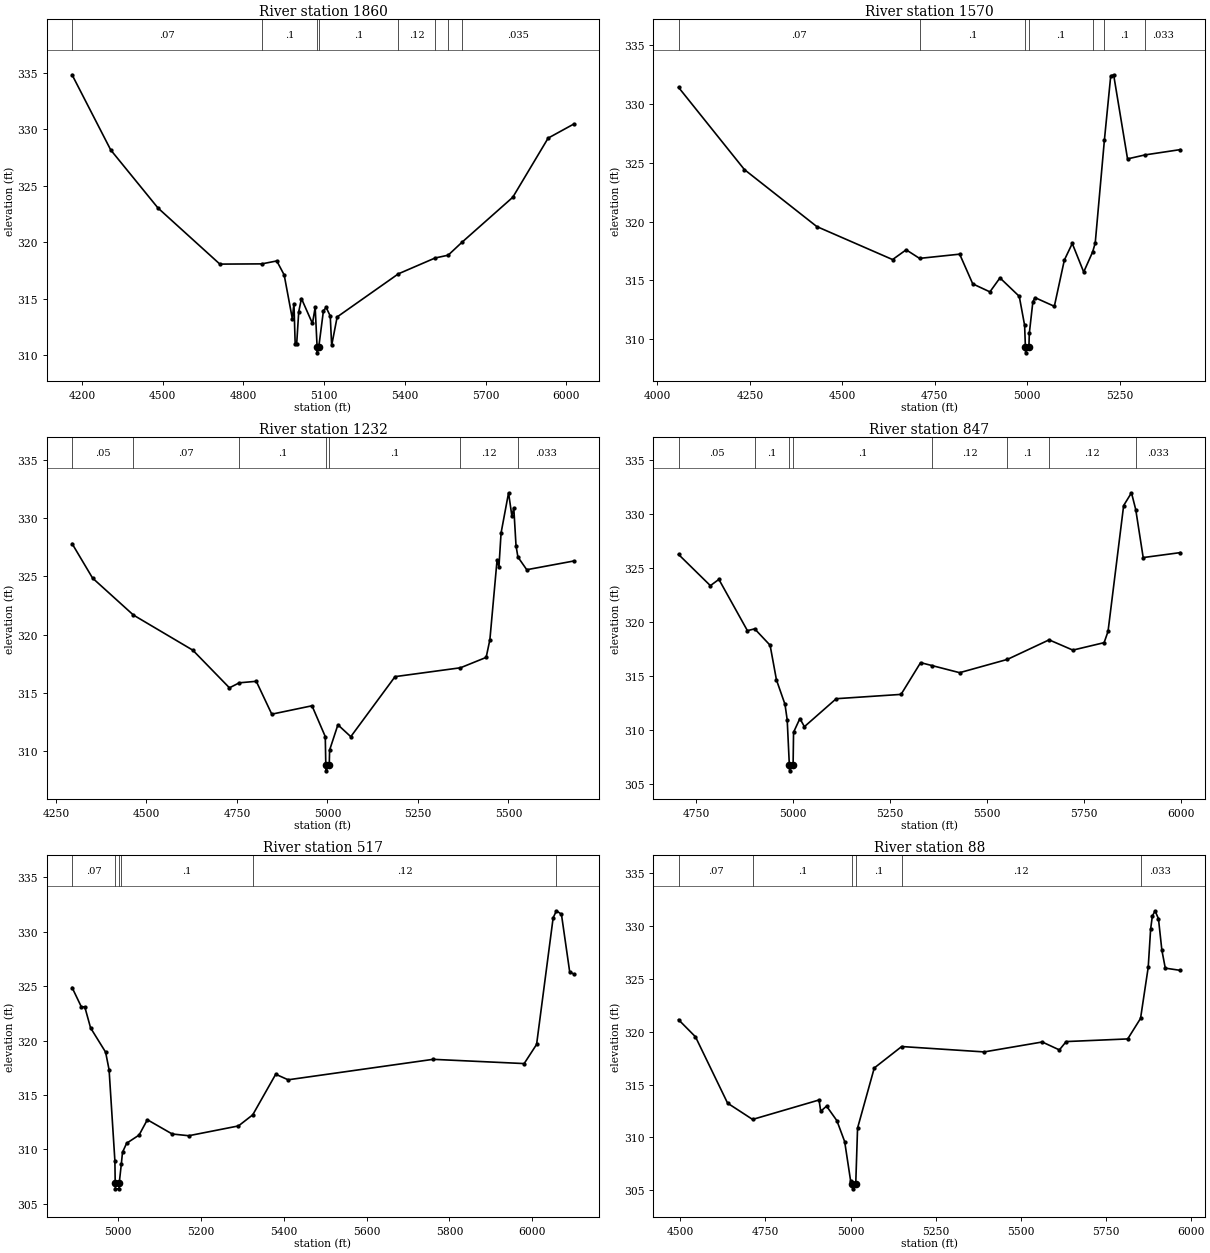
Type RM Length L Ch R = 1 ,1860    ,290,290,290
BEGIN DESCRIPTION:
RED BRANCH 3.0
END DESCRIPTION:
XS GIS Cut Line= 3
        2368375.       13663425.        2367675.       13662975.
      2366662.43     13662771.97
#Sta/Elev= 30
    4163  334.84  4306.7  328.18  4482.3  323.04  4712.2  318.07  4868.3  318.09
  4923.8  318.35  4951.3  317.11  4981.6  313.24  4987.6  314.57  4992.2  310.99
  4997.7  310.99  5005.4  313.85  5015.5  315.02  5056.4  312.81  5066.5  314.24
  5073.7  310.71  5074.2  310.21  5079.8  310.71  5097.2  313.94  5107.4  314.23
  5122.5  313.47  5127.8  310.87  5148.2  313.39  5375.9  317.21  5512.1  318.61
  5560.8  318.86  5611.9     320  5800.9  323.99  5932.3  329.23  6027.9  330.48
#Mann= 8 ,-1 , 0
    4163     .07       0  4868.3      .1       0  5073.7     .05       0
  5079.8      .1       0  5375.9     .12       0  5512.1      .1       0
  5560.8     .12       0  5611.9    .035       0
Bank Sta=5073.7,5079.8
XS Rating Curve= 0 ,0
Exp/Cntr=0.3,0.1

Type RM Length L Ch R = 1 ,1570    ,338,338,338
BEGIN DESCRIPTION:
B20144
END DESCRIPTION:
XS GIS Cut Line= 3
      2368454.32     13663241.45      2367491.88     13662654.59
      2367289.24     13662545.48
#Sta/Elev= 30
  4057.1  331.43  4235.3  324.43  4431.1  319.58  4636.1  316.77  4672.9   317.6
  4709.1  316.87  4817.6  317.23    4853   314.7  4899.4  314.02  4926.6  315.21
  4978.8  313.64  4993.3  311.17  4995.4  309.33  4995.9  308.83  5004.9  309.33
    5006  310.49  5015.6  313.18  5021.4  313.53  5073.7  312.79  5100.8  316.73
  5122.2  318.14  5153.1  315.71  5177.3  317.42  5184.3  318.18  5209.1  326.94
  5226.2   332.4  5234.1   332.5  5271.7  325.34  5319.2  325.68  5414.5  326.13
#Mann= 7 ,-1 , 0
  4057.1     .07       0  4709.1      .1       0  4995.4     .05       0
  5004.9      .1       0  5177.3     .12       0  5209.1      .1       0
  5319.2    .033       0
Bank Sta=4995.4,5004.9
XS Rating Curve= 0 ,0
Exp/Cntr=0.3,0.1

Type RM Length L Ch R = 1 ,1232    ,385,385,385
BEGIN DESCRIPTION:
B20143
END DESCRIPTION:
XS GIS Cut Line= 3
      2368556.05     13663010.61       2367871.4     13662603.73
      2367300.18     13662458.97
#Sta/Elev= 30
  4294.8   327.8  4351.5  324.84  4464.3  321.67  4628.2  318.66  4729.4  315.43
  4756.5  315.86  4803.5  315.99  4846.3  313.17  4957.4  313.89    4994  311.25
  4995.5  308.81    4996  308.31    5005  308.81    5006  310.09  5028.9  312.26
  5064.5  311.24  5186.7  316.39  5367.4  317.15  5438.3  318.04  5448.6  319.56
  5468.4  326.38  5473.6   325.8  5479.5  328.71  5500.2  332.16  5509.4  330.15
  5514.6  330.87  5520.8  327.61    5526  326.65  5550.4  325.56  5680.5  326.31
#Mann= 7 ,-1 , 0
  4294.8     .05       0  4464.3     .07       0  4756.5      .1       0
  4995.5     .05       0    5005      .1       0  5367.4     .12       0
    5526    .033       0
Bank Sta=4995.5,5005
XS Rating Curve= 0 ,0
Exp/Cntr=0.3,0.1

Type RM Length L Ch R = 1 ,847     ,330,330,330
BEGIN DESCRIPTION:
B20142
END DESCRIPTION:
XS GIS Cut Line= 3
      2368552.18      13662748.5       2368121.8     13662521.57
      2367319.88     13662423.77
#Sta/Elev= 30
  4703.9  326.28    4786  323.39    4808  323.97  4881.6  319.22  4900.3  319.39
  4940.1  317.87  4956.5  314.66  4978.5   312.4  4984.2  310.96  4989.8  306.74
  4990.3  306.24  4999.4  306.74  5000.6  309.81  5016.9  311.08  5028.6  310.33
  5110.7  312.92  5277.9  313.32  5328.3  316.26  5357.6  315.99    5429  315.33
  5552.2  316.56  5659.8  318.37  5721.1  317.42  5801.7  318.11  5811.8  319.15
  5852.1  330.81  5872.3  331.99  5883.3  330.43  5902.5  325.99  5998.3  326.45
#Mann= 8 ,-1 , 0
  4703.9     .05       0  4900.3      .1       0  4989.8     .05       0
  4999.4      .1       0  5357.6     .12       0  5552.2      .1       0
  5659.8     .12       0  5883.3    .033       0
Bank Sta=4989.8,4999.4
XS Rating Curve= 0 ,0
Exp/Cntr=0.3,0.1

Type RM Length L Ch R = 1 ,517     ,429,429,429
BEGIN DESCRIPTION:
RED BRANCH 1.0
END DESCRIPTION:
XS GIS Cut Line= 3
      2368574.99     13662424.99        2368475.       13662375.
      2367374.99       13662375.
#Sta/Elev= 30
  4888.8  324.88  4911.1  323.11  4919.5   323.1  4933.5  321.17  4969.8  318.94
  4978.2  317.32  4992.2  308.96    4993  306.88  4993.5  306.38  5002.1  306.38
  5002.6  306.88  5007.8  308.67  5010.6  309.74  5020.6  310.57  5050.6  311.32
  5070.6  312.73  5130.6  311.42  5170.6  311.26  5290.6  312.16  5325.1  313.18
  5380.6  316.91  5410.6   316.4  5760.6  318.28  5980.6  317.89  6010.6  319.65
  6050.6  331.29  6058.5  331.93  6070.6  331.61  6090.6   326.3  6100.6  326.12
#Mann= 6 ,-1 , 0
  4888.8     .07       0    4993     .05       0  5002.6     .07       0
  5007.8      .1       0  5325.1     .12       0  6058.5    .033       0
Bank Sta=4993,5002.6
XS Rating Curve= 0 ,0
Exp/Cntr=0.3,0.1

Type RM Length L Ch R = 1 ,88      ,0,0,0
BEGIN DESCRIPTION:
B20141
END DESCRIPTION:
XS GIS Cut Line= 4
      2368712.54     13662247.68      2368368.29     13662142.05
       2368153.1     13662173.35      2367261.04     13662235.95
#Sta/Elev= 30
  4495.6  321.15  4545.3  319.53  4639.5  313.25  4712.8  311.71  4907.7  313.55
  4912.7  312.48  4929.8  312.97  4960.1  311.59  4982.9  309.61  5000.5  305.86
  5005.8  305.64  5006.3  305.14  5015.4  305.64  5020.7  310.89  5069.7  316.58
  5150.1  318.61    5392   318.1  5562.4  319.04  5612.6  318.29  5632.6  319.08
  5813.1  319.33  5850.7  321.27  5873.2  326.11  5880.3  329.72  5885.3  330.95
  5893.3  331.46  5903.3   330.7  5913.3  327.72  5923.3  326.03  5967.4  325.82
#Mann= 6 ,-1 , 0
  4495.6     .07       0  4712.8      .1       0  5005.8     .05       0
  5015.4      .1       0  5150.1     .12       0  5850.7    .033       0
Bank Sta=5005.8,5015.4
XS Rating Curve= 0 ,0
Exp/Cntr=0.3,0.1

Chan Stop Cuts=-1
Use User Specified Reach Order=0
Composite Channel Slope=5