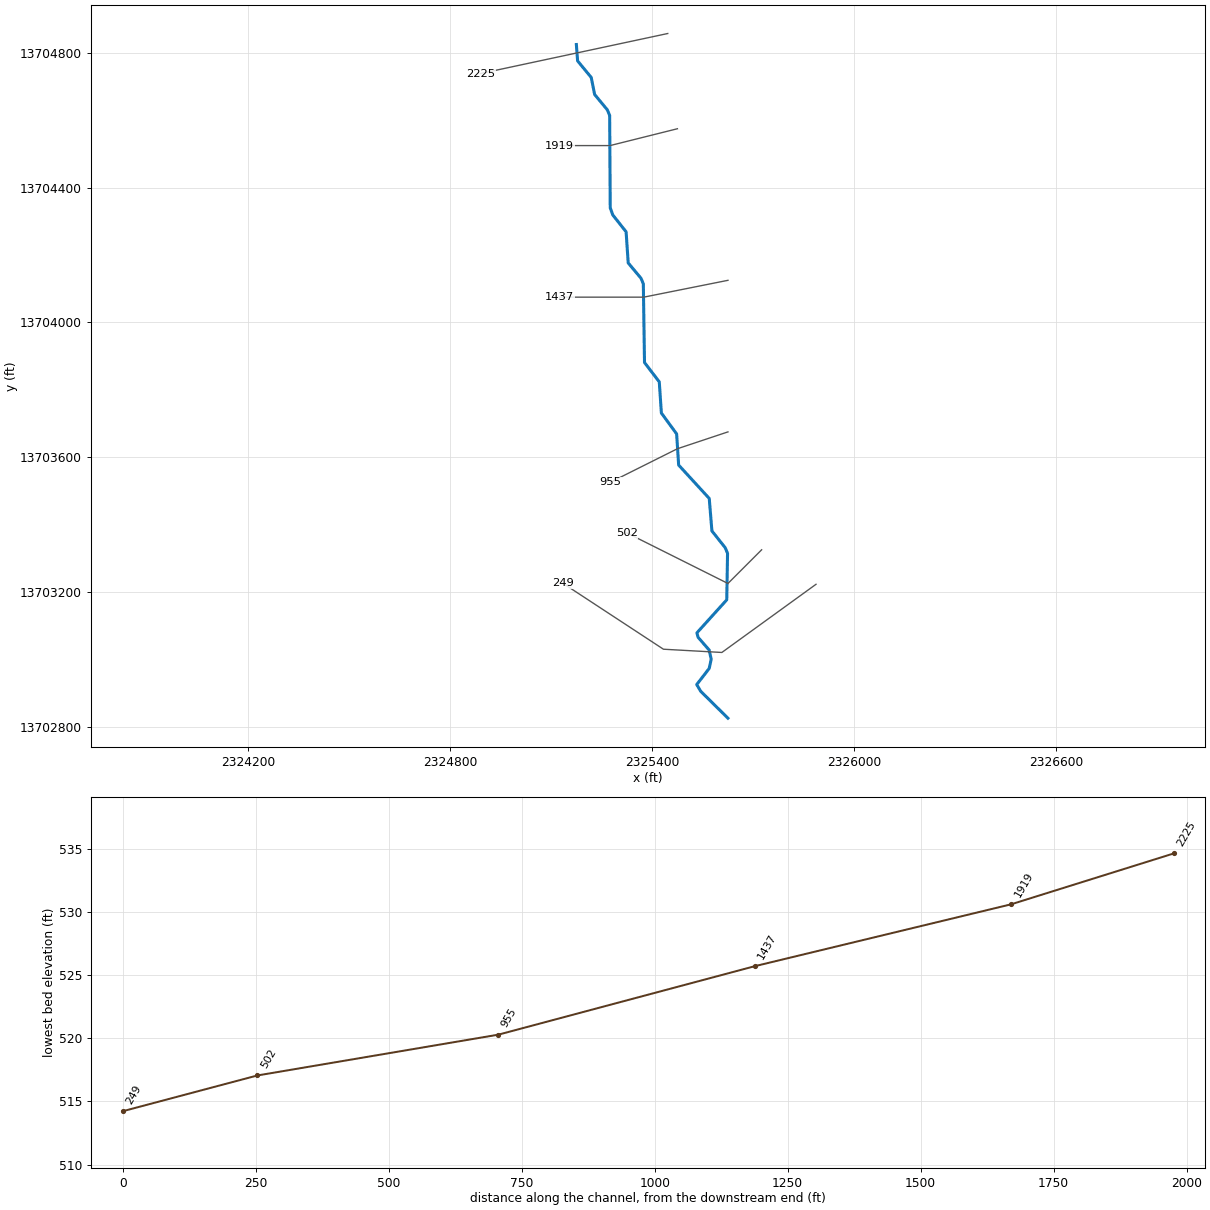
--- SANDIES TRIBUTARY 10.prj (project) ---

Proj Title=SANDIES TRIBUTARY 10 Base Level Engineering
Current Plan=p01
Default Exp/Contr=0.3,0.1
English Units
Geom File=g01
Flow File=f01
Plan File=p01
BEGIN DESCRIPTION:
SANDIES TRIBUTARY 10
END DESCRIPTION:

--- SANDIES TRIBUTARY 10.p01 (plan) ---

Plan Title=Multiple Run
Short Identifier=Multiple
Geom File=g01
Flow File=f01
Subcritical Flow
K Sum by GR= 0
Std Step Tol= 0.01
Critical Tol= 0.01
Num of Std Step Trials= 20
Max Error Tol= 0.3
Flow Tol Ratio= 0.001
Split Flow NTrial= 30
Split Flow Tol= 0.02
Split Flow Ratio= 0.02
Log Output Level= 0
Friction Slope Method= 1
Unsteady Friction Slope Method= 2
Unsteady Bridges Friction Slope Method= 1
Parabolic Critical Depth
Global Vel Dist=  1 , 1 , 1
Global Log Level= 0
CheckData=True
Encroach Param= -1, 0, 0, 0
BEGIN DESCRIPTION:
Multiple Run
END DESCRIPTION:

--- SANDIES TRIBUTARY 10.f01 (steady flow) ---

Flow Title=Multiple
Number of Profiles=7
Profile Names=10-year,25-year,50-year,1pct_min,100-year,1pct_plu,500-year
River Rch & RM= SANDIES TRIBUTAR,Reach-1,2225
     347     549     728     470     938    1871    1537
Boundary for River Rch & Prof#=SANDIES TRIBUTAR,Reach-1,1
Up Type=0
Dn Type=3
Dn Slope=0.005
Boundary for River Rch & Prof#=SANDIES TRIBUTAR,Reach-1,2
Up Type=0
Dn Type=3
Dn Slope=0.005
Boundary for River Rch & Prof#=SANDIES TRIBUTAR,Reach-1,3
Up Type=0
Dn Type=3
Dn Slope=0.005
Boundary for River Rch & Prof#=SANDIES TRIBUTAR,Reach-1,4
Up Type=0
Dn Type=3
Dn Slope=0.005
Boundary for River Rch & Prof#=SANDIES TRIBUTAR,Reach-1,5
Up Type=0
Dn Type=3
Dn Slope=0.005
Boundary for River Rch & Prof#=SANDIES TRIBUTAR,Reach-1,6
Up Type=0
Dn Type=3
Dn Slope=0.005
Boundary for River Rch & Prof#=SANDIES TRIBUTAR,Reach-1,7
Up Type=0
Dn Type=3
Dn Slope=0.005

--- SANDIES TRIBUTARY 10.g01 (geometry) ---

Geom Title=Existing Conditions

River Reach=SANDIES TRIBUTAR,Reach-1
Reach XY= 30
      2325175.00     13704825.00      2325178.60     13704776.49
      2325219.05     13704727.25      2325229.17     13704676.73
      2325266.91     13704631.08      2325273.80     13704614.50
      2325275.52     13704340.22      2325283.14     13704318.94
      2325322.64     13704269.02      2325328.86     13704176.60
      2325366.86     13704131.06      2325373.78     13704114.50
      2325377.26     13703880.94      2325421.14     13703823.40
      2325427.35     13703730.97      2325472.64     13703669.02
      2325478.62     13703576.50      2325569.46     13703477.42
      2325577.36     13703380.98      2325616.87     13703331.06
      2325623.80     13703314.49      2325621.45     13703176.47
      2325532.83     13703078.40      2325536.39     13703065.13
      2325569.31     13703027.29      2325575.22     13703000.00
      2325569.32     13702972.71      2325532.26     13702924.91
      2325544.09     13702904.97      2325625.00     13702825.00

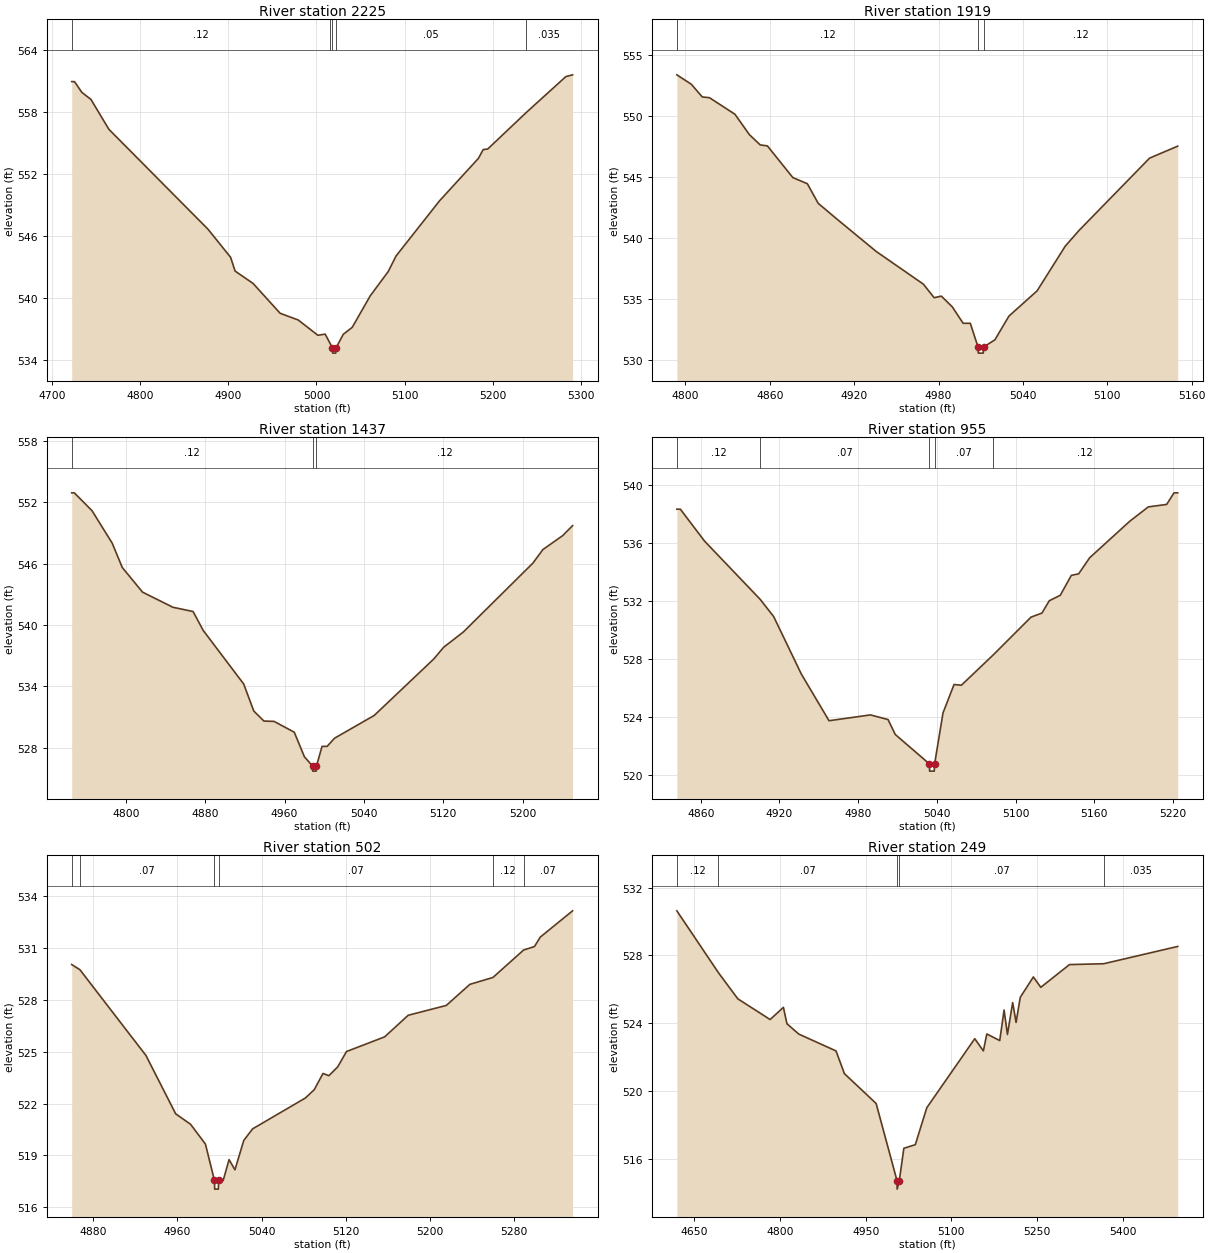
Type RM Length L Ch R = 1,2225,306,306,306
BEGIN DESCRIPTION:
21648
END DESCRIPTION:
XS GIS Cut Line= 2
      2325446.28     13704857.72      2324890.55     13704738.86
#Sta/Elev= 30
  4722.3  560.93  4725.5  560.93  4733.8  559.89  4744.1  559.21  4764.5  556.31
  4877.0  546.63  4902.6  543.91  4907.7  542.58  4928.1  541.38  4958.8  538.49
  4979.3  537.84  5001.6  536.36  5009.9  536.47  5015.9  535.50  5018.2  535.13
  5018.4  534.63  5021.9  534.63  5022.2  535.13  5030.4  536.45  5040.6  537.13
  5061.1  540.19  5081.5  542.54  5090.3  544.04  5139.7  549.39  5183.8  553.50
  5189.2  554.35  5194.3  554.40  5237.8  557.92  5283.0  561.42  5290.6  561.59
#Mann=5,-1,0
  4722.3    0.12       0  5015.9    0.05       0  5018.2    0.05       0
  5022.2    0.05       0  5237.8   0.035       0
Bank Sta=5018.2,5022.2
Exp/Cntr=0.3,0.1

Type RM Length L Ch R = 1,1919,482,482,482
BEGIN DESCRIPTION:
SANDIES TRIBUTARY 10 4.0
END DESCRIPTION:
XS GIS Cut Line= 3
      2325475.02     13704575.01      2325275.00     13704525.00
      2325124.98     13704525.00
#Sta/Elev= 30
  4793.9  553.35  4804.2  552.58  4812.0  551.54  4817.1  551.48  4835.2  550.13
  4845.5  548.46  4853.2  547.62  4858.3  547.54  4876.4  544.95  4886.7  544.45
  4894.4  542.85  4907.3  541.60  4935.7  538.91  4969.2  536.24  4976.9  535.13
  4982.0  535.26  4989.8  534.38  4997.5  533.04  5002.6  533.04  5008.1  531.10
  5008.3  530.60  5011.8  530.60  5012.1  531.10  5020.1  531.69  5030.1  533.63
  5050.1  535.69  5070.1  539.34  5080.1  540.65  5130.1  546.54  5150.1  547.52
#Mann=3,-1,0
  4793.9    0.12       0  5008.1    0.05       0  5012.1    0.12       0
Bank Sta=5008.1,5012.1
Exp/Cntr=0.3,0.1

Type RM Length L Ch R = 1,1437,482,482,482
BEGIN DESCRIPTION:
SANDIES TRIBUTARY 10 3.0
END DESCRIPTION:
XS GIS Cut Line= 3
      2325625.04     13704125.01      2325375.00     13704075.00
      2325124.99     13704075.00
#Sta/Elev= 30
  4745.4  552.94  4748.0  552.94  4765.8  551.20  4786.2  548.02  4796.4  545.63
  4816.8  543.22  4847.4  541.74  4867.8  541.32  4878.0  539.47  4918.8  534.23
  4929.0  531.58  4939.2  530.60  4949.4  530.57  4969.8  529.51  4980.0  527.11
  4988.2  526.20  4988.4  525.70  4991.9  525.70  4992.2  526.20  4997.8  528.12
  5002.9  528.12  5010.4  528.92  5050.4  531.15  5110.4  536.67  5120.4  537.82
  5140.4  539.33  5210.4  546.06  5220.4  547.38  5240.4  548.75  5250.4  549.73
#Mann=3,-1,0
  4745.4    0.12       0  4988.2    0.05       0  4992.2    0.12       0
Bank Sta=4988.2,4992.2
Exp/Cntr=0.3,0.1

Type RM Length L Ch R = 1,955,453,453,453
BEGIN DESCRIPTION:
SANDIES TRIBUTARY 10 2.0
END DESCRIPTION:
XS GIS Cut Line= 3
      2325625.04     13703675.01      2325475.00     13703625.00
      2325274.97     13703524.98
#Sta/Elev= 30
  4841.8  538.36  4844.5  538.36  4862.9  536.16  4905.3  532.14  4915.6  530.95
  4936.7  526.98  4957.8  523.76  4989.4  524.16  5002.8  523.84  5008.3  522.81
  5034.3  520.78  5034.5  520.28  5038.0  520.28  5038.3  520.78  5044.7  524.30
  5053.1  526.26  5058.7  526.21  5082.6  528.27  5111.8  530.91  5120.1  531.19
  5125.7  532.04  5134.1  532.42  5142.5  533.79  5148.1  533.90  5156.5  535.01
  5187.2  537.54  5201.2  538.52  5215.2  538.69  5220.8  539.49  5223.6  539.49
#Mann=5,-1,0
  4841.8    0.12       0  4905.3    0.07       0  5034.3    0.05       0
  5038.3    0.07       0  5082.6    0.12       0
Bank Sta=5034.3,5038.3
Exp/Cntr=0.3,0.1

Type RM Length L Ch R = 1,502,253,253,253
BEGIN DESCRIPTION:
SANDIES TRIBUTARY 10 1.0
END DESCRIPTION:
XS GIS Cut Line= 3
      2325725.00     13703325.00      2325625.00     13703225.00
      2325325.02     13703374.99
#Sta/Elev= 30
  4859.3  530.06  4867.1  529.76  4930.0  524.79  4958.3  521.41  4972.4  520.81
  4986.6  519.66  4995.2  517.55  4995.4  517.05  4998.9  517.05  4999.2  517.55
  5003.5  517.55  5009.1  518.76  5014.7  518.17  5023.1  519.87  5031.5  520.54
  5081.8  522.33  5090.2  522.81  5098.5  523.75  5104.1  523.62  5112.5  524.13
  5120.9  525.02  5157.2  525.87  5179.6  527.12  5215.9  527.69  5238.3  528.91
  5260.3  529.31  5289.5  530.90  5299.8  531.10  5305.4  531.65  5336.1  533.17
#Mann=6,-1,0
  4859.3    0.12       0  4867.1    0.07       0  4995.2    0.05       0
  4999.2    0.07       0  5260.3    0.12       0  5289.5    0.07       0
Bank Sta=4995.2,4999.2
Exp/Cntr=0.3,0.1

Type RM Length L Ch R = 1,249,0,0,0
BEGIN DESCRIPTION:
21647
END DESCRIPTION:
XS GIS Cut Line= 4
      2325886.45     13703222.58      2325606.93     13703020.18
      2325433.46     13703029.81      2325134.73     13703225.75
#Sta/Elev= 30
  4619.7  530.63  4692.5  526.98  4726.4  525.44  4782.9  524.22  4806.1  524.94
  4812.3  523.97  4833.1  523.36  4898.1  522.37  4912.8  521.03  4968.3  519.27
  5004.8  514.72  5005.1  514.22  5008.8  514.72  5016.8  516.63  5036.8  516.84
  5056.9  519.02  5140.8  523.09  5155.9  522.37  5161.9  523.37  5184.5  522.98
  5192.1  524.78  5198.0  523.34  5207.1  525.22  5213.1  524.05  5220.4  525.53
  5243.3  526.73  5256.3  526.12  5306.5  527.46  5366.3  527.51  5495.8  528.53
#Mann=5,-1,0
  4619.7    0.12       0  4692.5    0.07       0  5004.8    0.05       0
  5008.8    0.07       0  5366.3   0.035       0
Bank Sta=5004.8,5008.8
Exp/Cntr=0.3,0.1

Chan Stop Cuts=-1