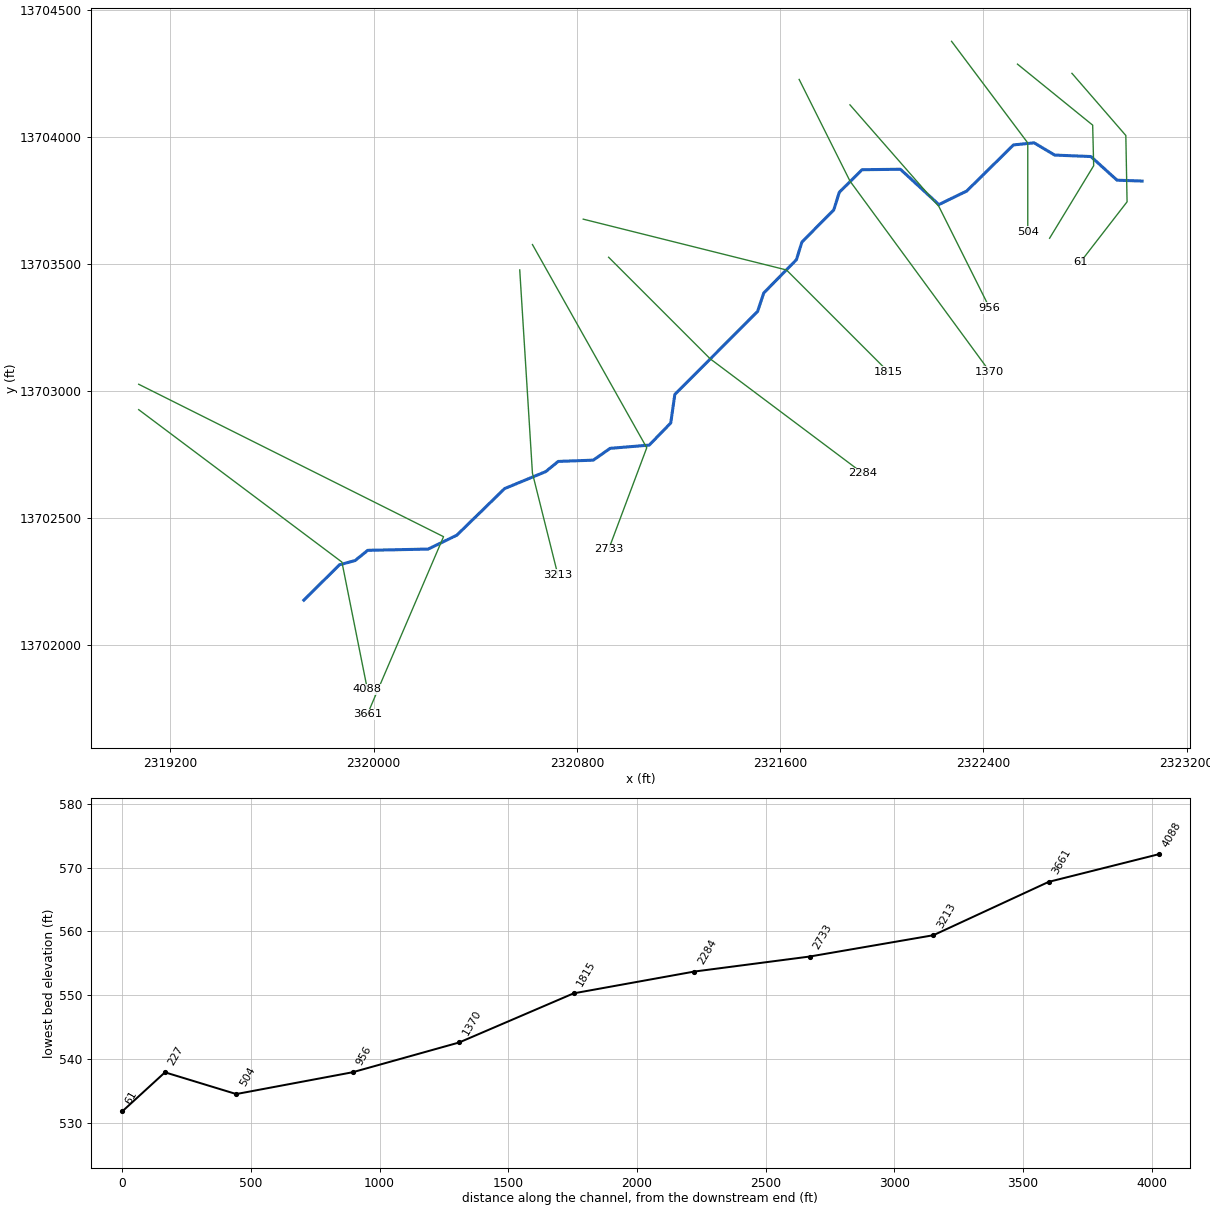
--- SANDIES TRIBUTARY 11.prj (project) ---

Proj Title=SANDIES TRIBUTARY 11 Base Level Engineering
Current Plan=p01
Default Exp/Contr=0.3,0.1
English Units
Geom File=g01
Flow File=f01
Plan File=p01
BEGIN DESCRIPTION:
SANDIES TRIBUTARY 11
END DESCRIPTION:

--- SANDIES TRIBUTARY 11.p01 (plan) ---

Plan Title=Multiple Run
Short Identifier=Multiple
Geom File=g01
Flow File=f01
Subcritical Flow
K Sum by GR= 0
Std Step Tol= 0.01
Critical Tol= 0.01
Num of Std Step Trials= 20
Max Error Tol= 0.3
Flow Tol Ratio= 0.001
Split Flow NTrial= 30
Split Flow Tol= 0.02
Split Flow Ratio= 0.02
Log Output Level= 0
Friction Slope Method= 1
Unsteady Friction Slope Method= 2
Unsteady Bridges Friction Slope Method= 1
Parabolic Critical Depth
Global Vel Dist=  1 , 1 , 1
Global Log Level= 0
CheckData=True
Encroach Param= -1, 0, 0, 0
BEGIN DESCRIPTION:
Multiple Run
END DESCRIPTION:

--- SANDIES TRIBUTARY 11.f01 (steady flow) ---

Flow Title=Multiple
Number of Profiles=7
Profile Names=10-year,25-year,50-year,1pct_min,100-year,1pct_plu,500-year
River Rch & RM= SANDIES TRIBUTAR,Reach-1,4088
     688    1126    1526    1002    1999    3989    3400
River Rch & RM= SANDIES TRIBUTAR,Reach-1,1815
    1118    1881    2599    1736    3464    6912    6106
River Rch & RM= SANDIES TRIBUTAR,Reach-1,956
    1294    2195    3049    2047    4084    8149    7271
Boundary for River Rch & Prof#=SANDIES TRIBUTAR,Reach-1,1
Up Type=0
Dn Type=3
Dn Slope=0.005
Boundary for River Rch & Prof#=SANDIES TRIBUTAR,Reach-1,2
Up Type=0
Dn Type=3
Dn Slope=0.005
Boundary for River Rch & Prof#=SANDIES TRIBUTAR,Reach-1,3
Up Type=0
Dn Type=3
Dn Slope=0.005
Boundary for River Rch & Prof#=SANDIES TRIBUTAR,Reach-1,4
Up Type=0
Dn Type=3
Dn Slope=0.005
Boundary for River Rch & Prof#=SANDIES TRIBUTAR,Reach-1,5
Up Type=0
Dn Type=3
Dn Slope=0.005
Boundary for River Rch & Prof#=SANDIES TRIBUTAR,Reach-1,6
Up Type=0
Dn Type=3
Dn Slope=0.005
Boundary for River Rch & Prof#=SANDIES TRIBUTAR,Reach-1,7
Up Type=0
Dn Type=3
Dn Slope=0.005

--- SANDIES TRIBUTARY 11.g01 (geometry) ---

Geom Title=Existing Conditions

River Reach=SANDIES TRIBUTAR,Reach-1
Reach XY= 30
      2319725.00     13702175.00      2319865.31     13702314.24
      2319927.17     13702331.14      2319976.55     13702371.25
      2320214.50     13702376.20      2320327.30     13702430.83
      2320515.32     13702614.24      2320677.18     13702681.12
      2320726.56     13702721.24      2320864.49     13702726.23
      2320930.94     13702772.73      2321084.82     13702785.47
      2321169.48     13702872.56      2321185.52     13702984.79
      2321511.37     13703311.79      2321535.78     13703384.68
      2321664.22     13703515.32      2321685.78     13703584.68
      2321811.37     13703711.79      2321833.15     13703781.07
      2321922.54     13703869.55      2322073.53     13703871.47
      2322224.91     13703732.28      2322334.68     13703785.75
      2322518.83     13703967.24      2322600.00     13703975.41
      2322680.94     13703927.27      2322823.53     13703921.45
      2322926.41     13703828.39      2323025.00     13703825.00

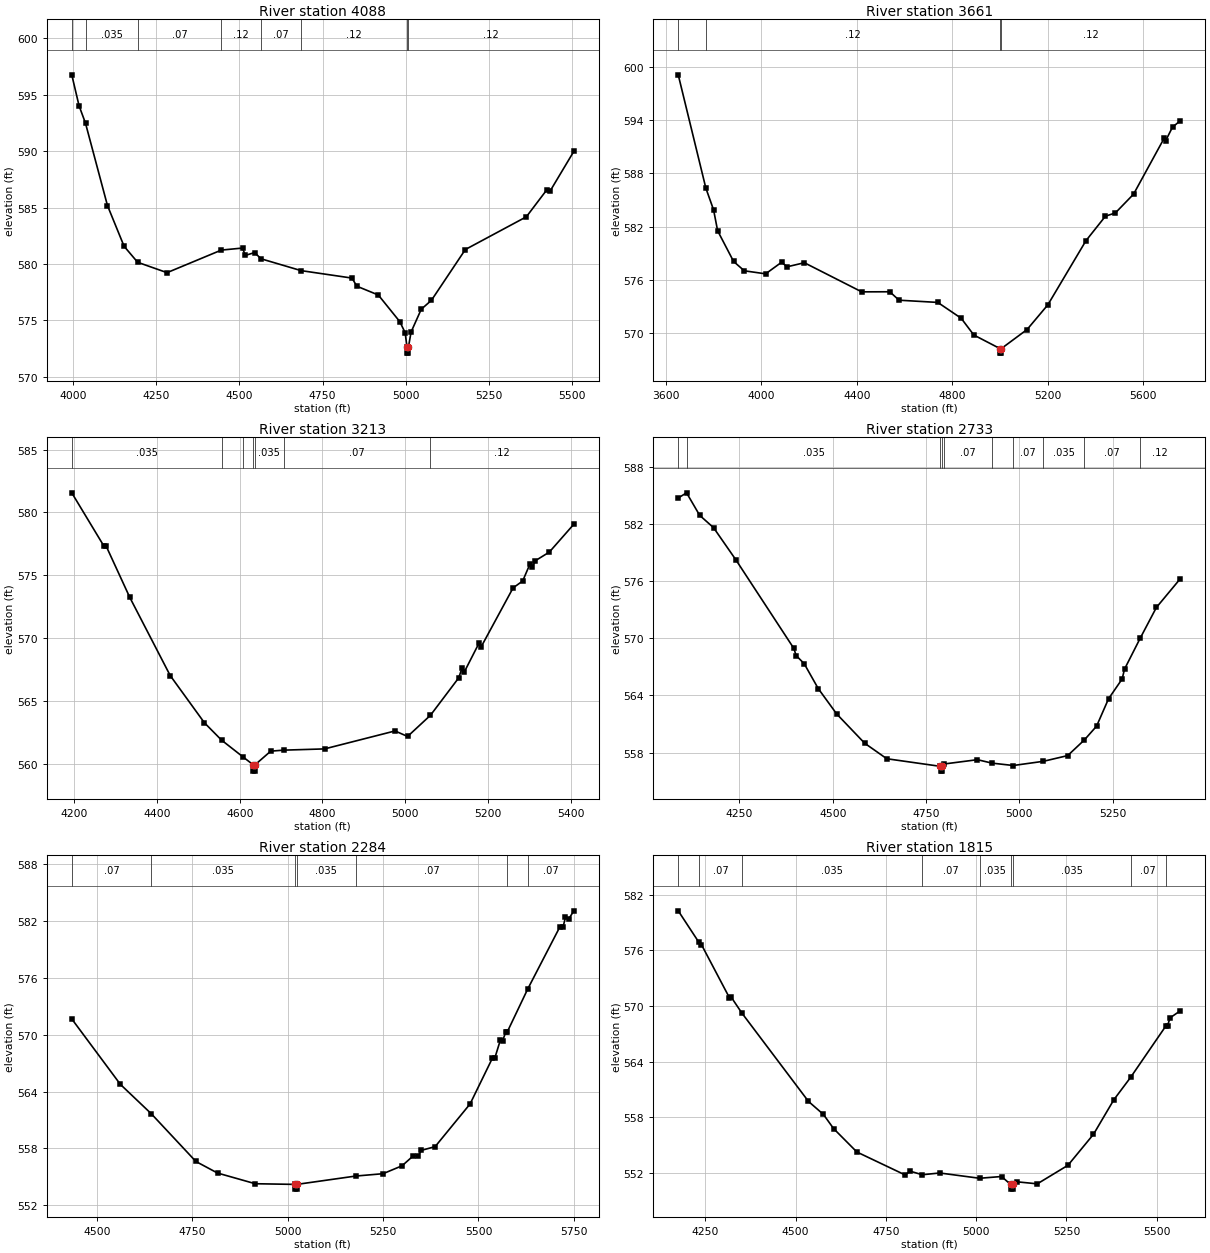
Type RM Length L Ch R = 1,4088,427,427,427
BEGIN DESCRIPTION:
SANDIES TRIBUTARY 11 9.0
END DESCRIPTION:
XS GIS Cut Line= 3
      2319075.00     13702925.00      2319875.00     13702325.00
      2319975.00     13701825.01
#Sta/Elev= 30
  3995.6  596.76  4017.5  594.02  4036.9  592.47  4102.9  585.18  4152.9  581.57
  4193.7  580.15  4282.1  579.23  4445.3  581.23  4509.1  581.41  4517.5  580.76
  4545.6  581.01  4564.7  580.46  4685.3  579.41  4838.3  578.75  4852.9  578.03
  4917.5  577.25  4982.1  574.89  4998.2  573.91  5003.8  572.60  5004.0  572.10
  5007.6  572.10  5007.9  572.60  5016.0  573.97  5046.6  575.99  5077.2  576.78
  5179.2  581.28  5362.7  584.18  5423.9  586.56  5434.1  586.46  5505.5  589.98
#Mann=8,-1,0
  3995.6    0.07       0  4036.9   0.035       0  4193.7    0.07       0
  4445.3    0.12       0  4564.7    0.07       0  4685.3    0.12       0
  5003.8    0.05       0  5007.9    0.12       0
Bank Sta=5003.8,5007.9
Exp/Cntr=0.3,0.1

Type RM Length L Ch R = 1,3661,448,448,448
BEGIN DESCRIPTION:
SANDIES TRIBUTARY 11 8.0
END DESCRIPTION:
XS GIS Cut Line= 3
      2319074.96     13703025.02      2320275.00     13702425.00
      2319974.99     13701724.97
#Sta/Elev= 30
  3651.2  599.11  3766.8  586.36  3799.4  583.89  3816.2  581.55  3883.2  578.09
  3928.0  577.04  4017.4  576.70  4084.5  578.01  4106.8  577.49  4179.5  577.95
  4419.9  574.67  4537.3  574.68  4576.4  573.73  4738.5  573.48  4836.4  571.70
  4889.5  569.81  4999.9  568.27  5000.2  567.77  5003.8  567.77  5004.1  568.27
  5112.6  570.43  5199.6  573.21  5359.2  580.43  5440.8  583.19  5482.5  583.56
  5558.6  585.67  5687.4  592.00  5692.8  591.68  5721.8  593.22  5754.5  593.94
#Mann=4,-1,0
  3651.2    0.07       0  3766.8    0.12       0  4999.9    0.05       0
  5004.1    0.12       0
Bank Sta=4999.9,5004.1
Exp/Cntr=0.3,0.1

Type RM Length L Ch R = 1,3213,480,480,480
BEGIN DESCRIPTION:
SANDIES TRIBUTARY 11 7.0
END DESCRIPTION:
XS GIS Cut Line= 3
      2320575.00     13703475.05      2320625.00     13702675.00
      2320725.00     13702275.02
#Sta/Elev= 30
  4193.8  581.56  4271.5  577.32  4276.5  577.35  4334.1  573.23  4431.8  567.01
  4514.5  563.25  4555.9  561.87  4607.5  560.54  4632.6  559.90  4632.9  559.40
  4636.5  559.40  4636.8  559.90  4674.8  560.99  4706.0  561.07  4805.0  561.17
  4975.4  562.60  5005.7  562.16  5061.1  563.85  5129.4  566.83  5137.1  567.59
  5142.3  567.26  5178.4  569.59  5183.5  569.29  5260.8  573.99  5284.0  574.54
  5302.1  575.93  5307.2  575.64  5314.9  576.16  5348.4  576.84  5407.7  579.06
#Mann=7,-1,0
  4193.8   0.035       0  4555.9    0.07       0  4607.5   0.035       0
  4632.6    0.05       0  4636.8   0.035       0  4706.0    0.07       0
  5061.1    0.12       0
Bank Sta=4632.6,4636.8
Exp/Cntr=0.3,0.1

Type RM Length L Ch R = 1,2733,449,449,449
BEGIN DESCRIPTION:
SANDIES TRIBUTARY 11 6.0
END DESCRIPTION:
XS GIS Cut Line= 3
      2320625.00     13703575.01      2321075.00     13702775.00
      2320925.00     13702374.99
#Sta/Elev= 30
  4086.0  584.72  4108.3  585.26  4143.4  582.90  4180.7  581.60  4239.9  578.26
  4395.8  568.93  4401.8  568.19  4423.5  567.33  4461.1  564.72  4510.5  562.06
  4585.4  558.99  4644.7  557.36  4788.6  556.56  4788.8  556.06  4792.5  556.06
  4792.8  556.56  4798.5  556.81  4887.6  557.26  4926.5  556.90  4983.5  556.65
  5064.2  557.09  5129.4  557.69  5174.0  559.33  5206.8  560.78  5238.8  563.65
  5275.3  565.73  5281.6  566.76  5323.3  569.98  5367.0  573.23  5431.1  576.25
#Mann=10,-1,0
  4086.0    0.07       0  4108.3   0.035       0  4788.6    0.05       0
  4792.8   0.035       0  4798.5    0.07       0  4926.5   0.035       0
  4983.5    0.07       0  5064.2   0.035       0  5174.0    0.07       0
  5323.3    0.12       0
Bank Sta=4788.6,4792.8
Exp/Cntr=0.3,0.1

Type RM Length L Ch R = 1,2284,469,469,469
BEGIN DESCRIPTION:
SANDIES TRIBUTARY 11 5.0
END DESCRIPTION:
XS GIS Cut Line= 3
      2320924.98     13703525.02      2321325.00     13703125.00
      2321924.99     13702675.01
#Sta/Elev= 30
  4434.3  571.68  4561.6  564.77  4642.5  561.67  4759.6  556.62  4816.2  555.40
  4915.2  554.27  5019.8  554.20  5020.0  553.70  5023.7  553.70  5024.0  554.20
  5178.1  555.08  5250.0  555.33  5300.0  556.17  5328.1  557.18  5342.7  557.23
  5350.0  557.79  5386.5  558.19  5478.1  562.70  5536.5  567.53  5542.7  567.52
  5557.3  569.43  5563.6  569.40  5571.9  570.33  5575.9  570.34  5629.0  574.83
  5713.6  581.42  5721.9  581.42  5728.1  582.42  5736.5  582.23  5750.0  583.10
#Mann=7,-1,0
  4434.3    0.07       0  4642.5   0.035       0  5019.8   0.035       0
  5024.0   0.035       0  5178.1    0.07       0  5575.9   0.035       0
  5629.0    0.07       0
Bank Sta=5019.8,5024
Exp/Cntr=0.3,0.1

Type RM Length L Ch R = 1,1815,445,445,445
BEGIN DESCRIPTION:
SANDIES TRIBUTARY 11 4.0
END DESCRIPTION:
XS GIS Cut Line= 3
      2320825.03     13703674.99      2321625.00     13703475.00
      2322025.02     13703074.98
#Sta/Elev= 30
  4175.2  580.27  4232.0  576.90  4239.6  576.62  4316.9  570.91  4322.1  570.95
  4351.7  569.24  4535.9  559.73  4577.2  558.33  4605.5  556.80  4669.9  554.28
  4803.9  551.80  4816.8  552.22  4850.9  551.83  4899.3  552.02  5009.6  551.45
  5070.5  551.64  5095.8  550.78  5096.3  550.28  5101.3  550.28  5101.8  550.78
  5112.9  551.07  5169.5  550.85  5254.4  552.85  5325.1  556.19  5381.6  559.92
  5427.8  562.32  5524.6  567.81  5530.1  567.90  5537.2  568.74  5565.5  569.50
#Mann=9,-1,0
  4175.2    0.12       0  4232.0    0.07       0  4351.7   0.035       0
  4850.9    0.07       0  5009.6   0.035       0  5095.8    0.05       0
  5101.8   0.035       0  5427.8    0.07       0  5524.6   0.035       0
Bank Sta=5095.8,5101.8
Exp/Cntr=0.3,0.1

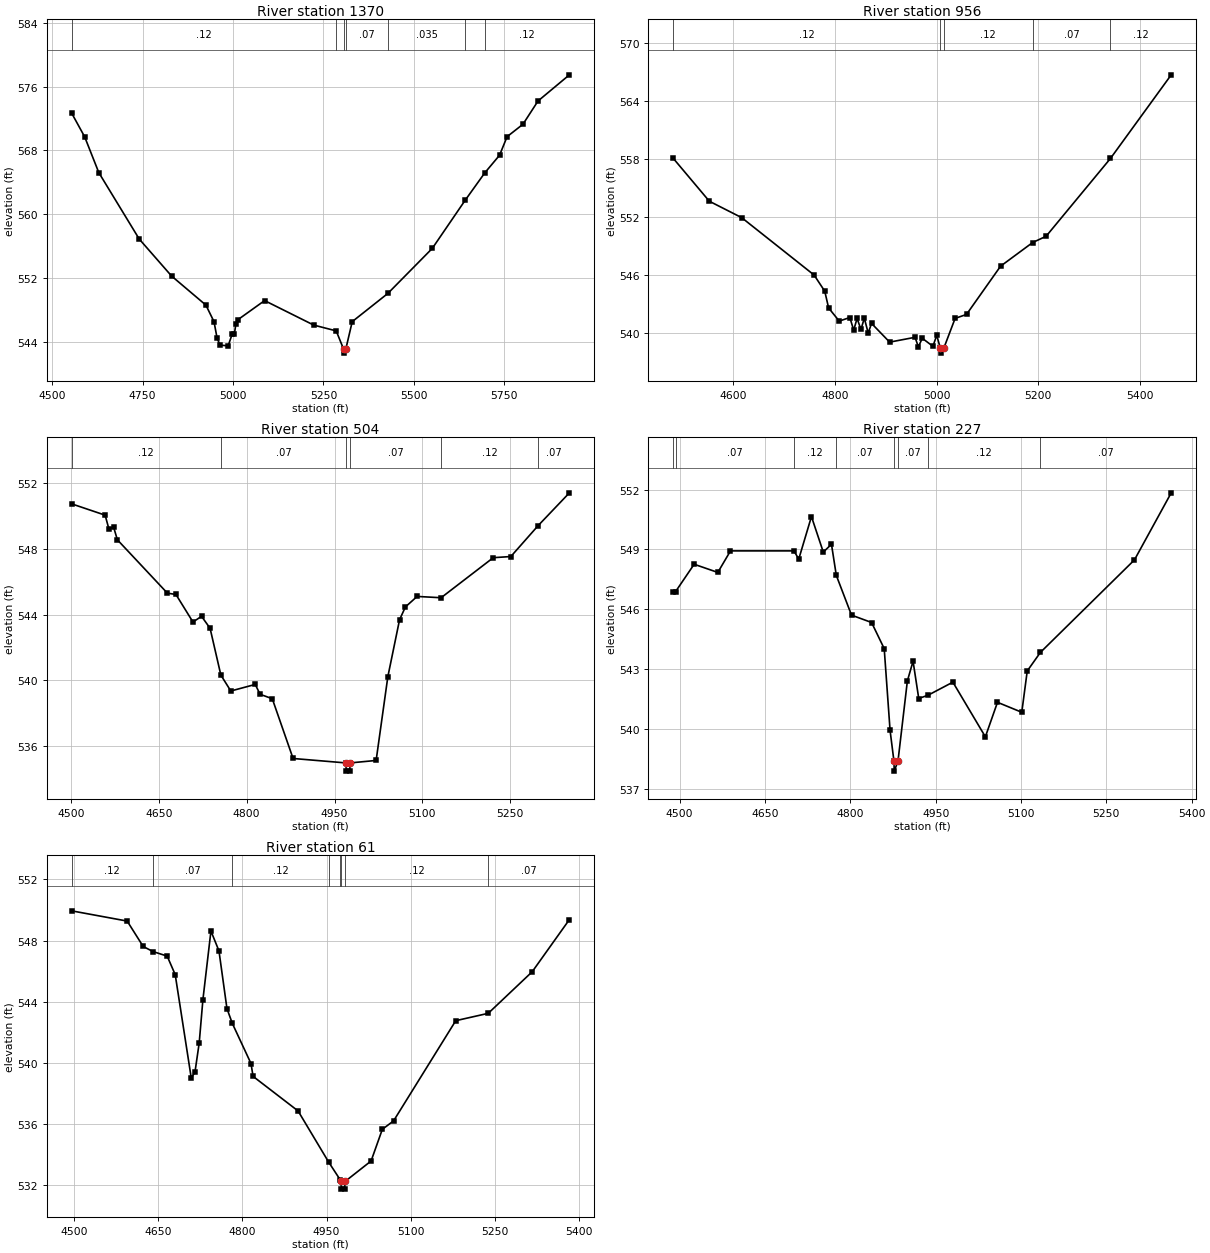
Type RM Length L Ch R = 1,1370,414,414,414
BEGIN DESCRIPTION:
SANDIES TRIBUTARY 11 3.0
END DESCRIPTION:
XS GIS Cut Line= 3
      2321675.01     13704224.97      2321875.00     13703825.00
      2322424.98     13703075.03
#Sta/Elev= 30
  4553.3  572.70  4589.6  569.70  4628.7  565.21  4740.5  556.88  4830.0  552.24
  4925.0  548.59  4947.4  546.51  4955.8  544.47  4964.1  543.57  4986.5  543.49
  4997.7  544.97  5003.6  544.97  5007.8  546.19  5014.0  546.78  5087.3  549.16
  5223.1  546.09  5285.4  545.36  5305.8  543.07  5306.3  542.57  5311.9  543.07
  5329.7  546.52  5428.3  550.06  5551.2  555.71  5641.9  561.73  5696.7  565.20
  5737.2  567.39  5758.1  569.72  5802.0  571.28  5843.7  574.20  5930.5  577.48
#Mann=7,-1,0
  4553.3    0.12       0  5285.4    0.07       0  5305.8    0.05       0
  5311.9    0.07       0  5428.3   0.035       0  5641.9    0.07       0
  5696.7    0.12       0
Bank Sta=5305.8,5311.9
Exp/Cntr=0.3,0.1

Type RM Length L Ch R = 1,956,452,452,452
BEGIN DESCRIPTION:
SANDIES TRIBUTARY 11 2.0
END DESCRIPTION:
XS GIS Cut Line= 3
      2321874.98     13704125.02      2322225.00     13703725.00
      2322425.02     13703324.96
#Sta/Elev= 30
  4482.6  558.07  4553.3  553.64  4616.9  551.94  4759.3  545.99  4780.2  544.32
  4787.8  542.58  4808.7  541.22  4829.5  541.59  4837.1  540.29  4843.8  541.49
  4851.4  540.35  4858.0  541.53  4865.6  539.98  4872.2  540.98  4907.8  539.04
  4957.7  539.54  4964.3  538.55  4971.9  539.44  4992.8  538.61  5000.4  539.74
  5007.5  538.40  5008.0  537.90  5014.2  538.40  5036.5  541.50  5058.9  541.91
  5125.9  546.91  5188.9  549.36  5215.4  550.01  5342.0  558.08  5461.4  566.74
#Mann=5,-1,0
  4482.6    0.12       0  5007.5    0.05       0  5014.2    0.12       0
  5188.9    0.07       0  5342.0    0.12       0
Bank Sta=5007.5,5014.2
Exp/Cntr=0.3,0.1

Type RM Length L Ch R = 1,504,277,277,277
BEGIN DESCRIPTION:
SANDIES TRIBUTARY 11 1.0
END DESCRIPTION:
XS GIS Cut Line= 3
      2322274.98     13704375.03      2322575.00     13703975.00
      2322575.00     13703625.04
#Sta/Elev= 30
  4501.0  550.76  4558.3  550.07  4564.6  549.25  4572.9  549.33  4579.2  548.57
  4664.6  545.32  4679.2  545.24  4708.3  543.56  4722.9  543.91  4737.5  543.18
  4755.9  540.33  4772.9  539.36  4814.6  539.76  4822.9  539.16  4843.7  538.89
  4879.2  535.25  4969.4  534.98  4969.9  534.48  4976.0  534.48  4976.5  534.98
  5021.0  535.13  5041.0  540.23  5061.0  543.70  5071.0  544.48  5091.0  545.12
  5131.9  545.04  5221.0  547.48  5251.0  547.55  5297.8  549.44  5351.0  551.43
#Mann=6,-1,0
  4501.0    0.12       0  4755.9    0.07       0  4969.4    0.05       0
  4976.5    0.07       0  5131.9    0.12       0  5297.8    0.07       0
Bank Sta=4969.4,4976.5
Exp/Cntr=0.3,0.1

Type RM Length L Ch R = 1,227,166,166,166
BEGIN DESCRIPTION:
SANDIES TRIBUTARY 11 0.7
END DESCRIPTION:
XS GIS Cut Line= 4
      2322534.44     13704285.24      2322830.48     13704045.09
      2322834.41     13703885.27      2322660.90     13703599.84
#Sta/Elev= 30
  4489.0  546.88  4492.9  546.89  4525.5  548.26  4567.1  547.85  4589.4  548.93
  4700.9  548.93  4709.4  548.52  4731.7  550.65  4752.5  548.87  4766.9  549.26
  4775.4  547.70  4802.1  545.71  4837.4  545.34  4859.6  544.03  4869.9  539.93
  4876.7  538.39  4877.2  537.89  4883.8  538.39  4900.3  542.41  4910.3  543.40
  4920.3  541.53  4937.0  541.70  4980.3  542.35  5037.4  539.61  5058.7  541.34
  5101.4  540.84  5111.0  542.91  5134.1  543.84  5299.5  548.48  5364.1  551.84
#Mann=8,-1,0
  4489.0    0.12       0  4492.9    0.07       0  4700.9    0.12       0
  4775.4    0.07       0  4876.7    0.05       0  4883.8    0.07       0
  4937.0    0.12       0  5134.1    0.07       0
Bank Sta=4876.7,4883.8
Exp/Cntr=0.3,0.1

Type RM Length L Ch R = 1,61,0,0,0
BEGIN DESCRIPTION:
SANDIES TRIBUTARY 11 0.4
END DESCRIPTION:
XS GIS Cut Line= 4
      2322748.88     13704249.06      2322961.00     13704004.30
      2322965.90     13703743.26      2322781.53     13703505.05
#Sta/Elev= 30
  4496.0  549.95  4595.0  549.28  4623.5  547.62  4640.8  547.29  4666.2  546.99
  4680.5  545.78  4709.0  539.04  4715.6  539.39  4723.2  541.31  4729.8  544.14
  4744.1  548.63  4758.4  547.33  4772.6  543.56  4782.2  542.59  4815.4  539.97
  4819.1  539.13  4899.2  536.87  4953.6  533.53  4974.2  532.37  4975.7  532.26
  4976.2  531.76  4982.3  531.76  4982.8  532.26  5029.2  533.60  5049.2  535.67
  5069.2  536.22  5179.9  542.77  5237.7  543.25  5316.0  545.97  5382.2  549.38
#Mann=8,-1,0
  4496.0    0.12       0  4640.8    0.07       0  4782.2    0.12       0
  4953.6    0.07       0  4974.2    0.12       0  4975.7    0.05       0
  4982.8    0.12       0  5237.7    0.07       0
Bank Sta=4975.7,4982.8
Exp/Cntr=0.3,0.1

Chan Stop Cuts=-1