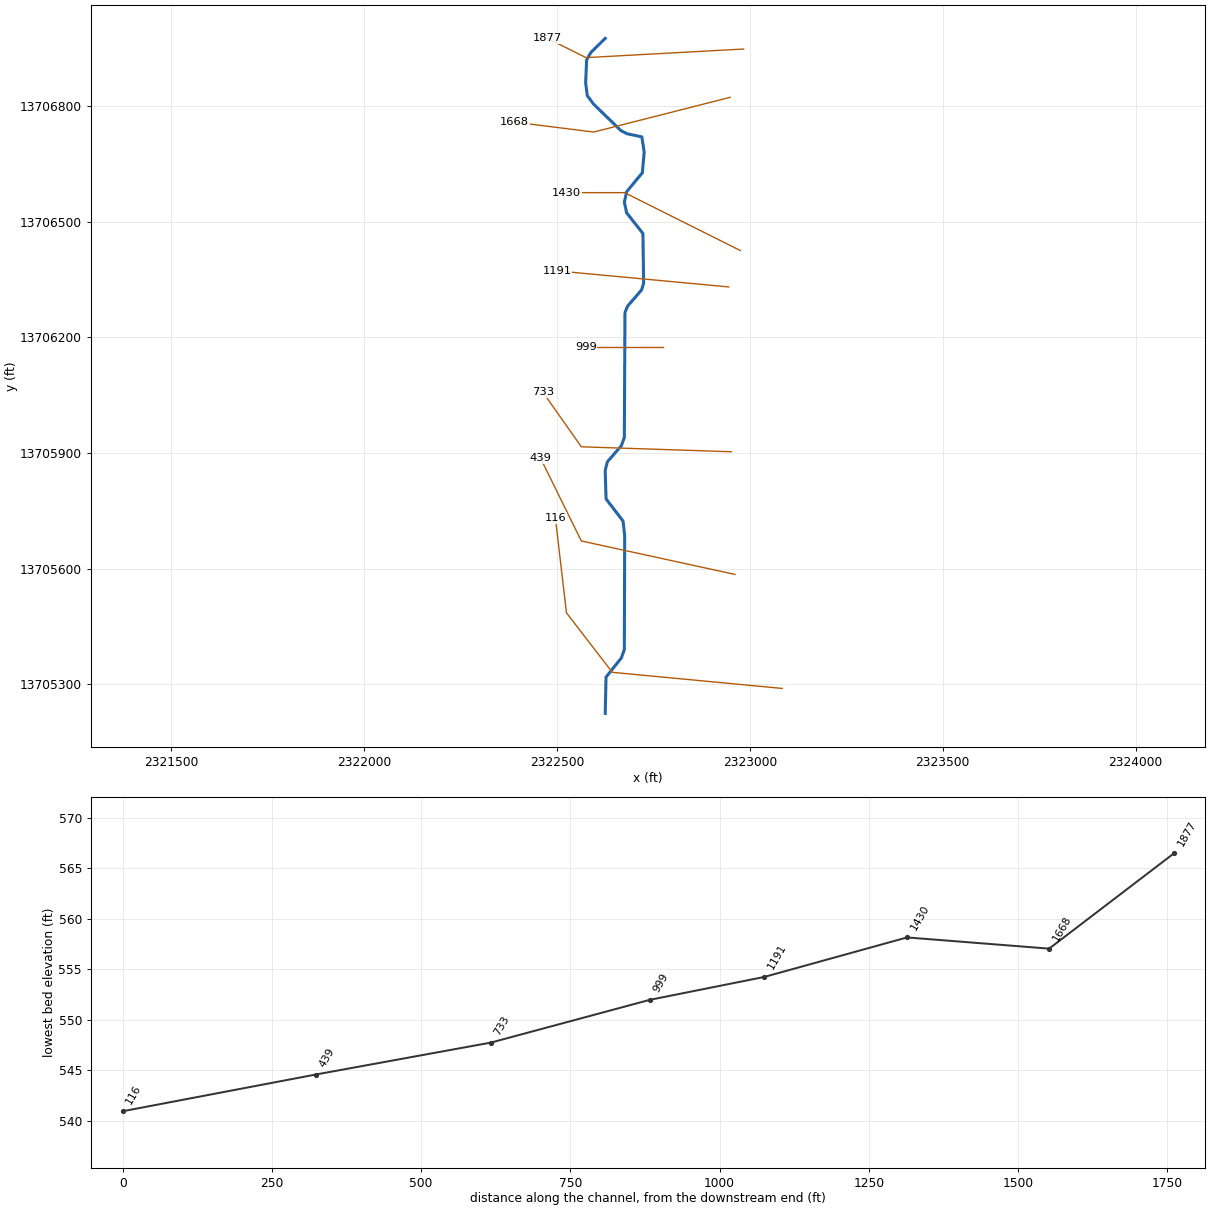
--- SANDIES TRIBUTARY 13.prj (project) ---

Proj Title=SANDIES TRIBUTARY 13 Base Level Engineering
Current Plan=p01
Default Exp/Contr=0.3,0.1
English Units
Geom File=g01
Flow File=f01
Plan File=p01
BEGIN DESCRIPTION:
SANDIES TRIBUTARY 13
END DESCRIPTION:

--- SANDIES TRIBUTARY 13.p01 (plan) ---

Plan Title=Multiple Run
Short Identifier=Multiple
Geom File=g01
Flow File=f01
Subcritical Flow
K Sum by GR= 0
Std Step Tol= 0.01
Critical Tol= 0.01
Num of Std Step Trials= 20
Max Error Tol= 0.3
Flow Tol Ratio= 0.001
Split Flow NTrial= 30
Split Flow Tol= 0.02
Split Flow Ratio= 0.02
Log Output Level= 0
Friction Slope Method= 1
Unsteady Friction Slope Method= 2
Unsteady Bridges Friction Slope Method= 1
Parabolic Critical Depth
Global Vel Dist=  1 , 1 , 1
Global Log Level= 0
CheckData=True
Encroach Param= -1, 0, 0, 0
BEGIN DESCRIPTION:
Multiple Run
END DESCRIPTION:

--- SANDIES TRIBUTARY 13.f01 (steady flow) ---

Flow Title=Multiple
Number of Profiles=7
Profile Names=10-year,25-year,50-year,1pct_min,100-year,1pct_plu,500-year
River Rch & RM= SANDIES TRIBUTAR,Reach-1,1877
     428     686     919     598    1193    2381    1990
Boundary for River Rch & Prof#=SANDIES TRIBUTAR,Reach-1,1
Up Type=0
Dn Type=3
Dn Slope=0.005
Boundary for River Rch & Prof#=SANDIES TRIBUTAR,Reach-1,2
Up Type=0
Dn Type=3
Dn Slope=0.005
Boundary for River Rch & Prof#=SANDIES TRIBUTAR,Reach-1,3
Up Type=0
Dn Type=3
Dn Slope=0.005
Boundary for River Rch & Prof#=SANDIES TRIBUTAR,Reach-1,4
Up Type=0
Dn Type=3
Dn Slope=0.005
Boundary for River Rch & Prof#=SANDIES TRIBUTAR,Reach-1,5
Up Type=0
Dn Type=3
Dn Slope=0.005
Boundary for River Rch & Prof#=SANDIES TRIBUTAR,Reach-1,6
Up Type=0
Dn Type=3
Dn Slope=0.005
Boundary for River Rch & Prof#=SANDIES TRIBUTAR,Reach-1,7
Up Type=0
Dn Type=3
Dn Slope=0.005

--- SANDIES TRIBUTARY 13.g01 (geometry) ---

Geom Title=Existing Conditions

River Reach=SANDIES TRIBUTAR,Reach-1
Reach XY= 30
      2322625.00     13706975.00      2322587.87     13706938.48
      2322576.77     13706919.16      2322574.22     13706859.88
      2322578.45     13706826.47      2322594.57     13706804.80
      2322665.61     13706735.89      2322681.53     13706727.73
      2322719.89     13706719.53      2322726.00     13706680.43
      2322721.30     13706626.66      2322680.38     13706577.19
      2322674.60     13706550.00      2322680.38     13706522.82
      2322722.72     13706469.07      2322724.49     13706340.22
      2322719.26     13706322.67      2322683.14     13706281.06
      2322676.22     13706264.50      2322674.48     13705940.22
      2322666.85     13705918.94      2322630.68     13705877.31
      2322624.91     13705854.90      2322627.17     13705780.98
      2322671.22     13705723.44      2322675.45     13705685.19
      2322674.49     13705390.21      2322666.90     13705368.93
      2322627.10     13705319.13      2322625.00     13705225.00

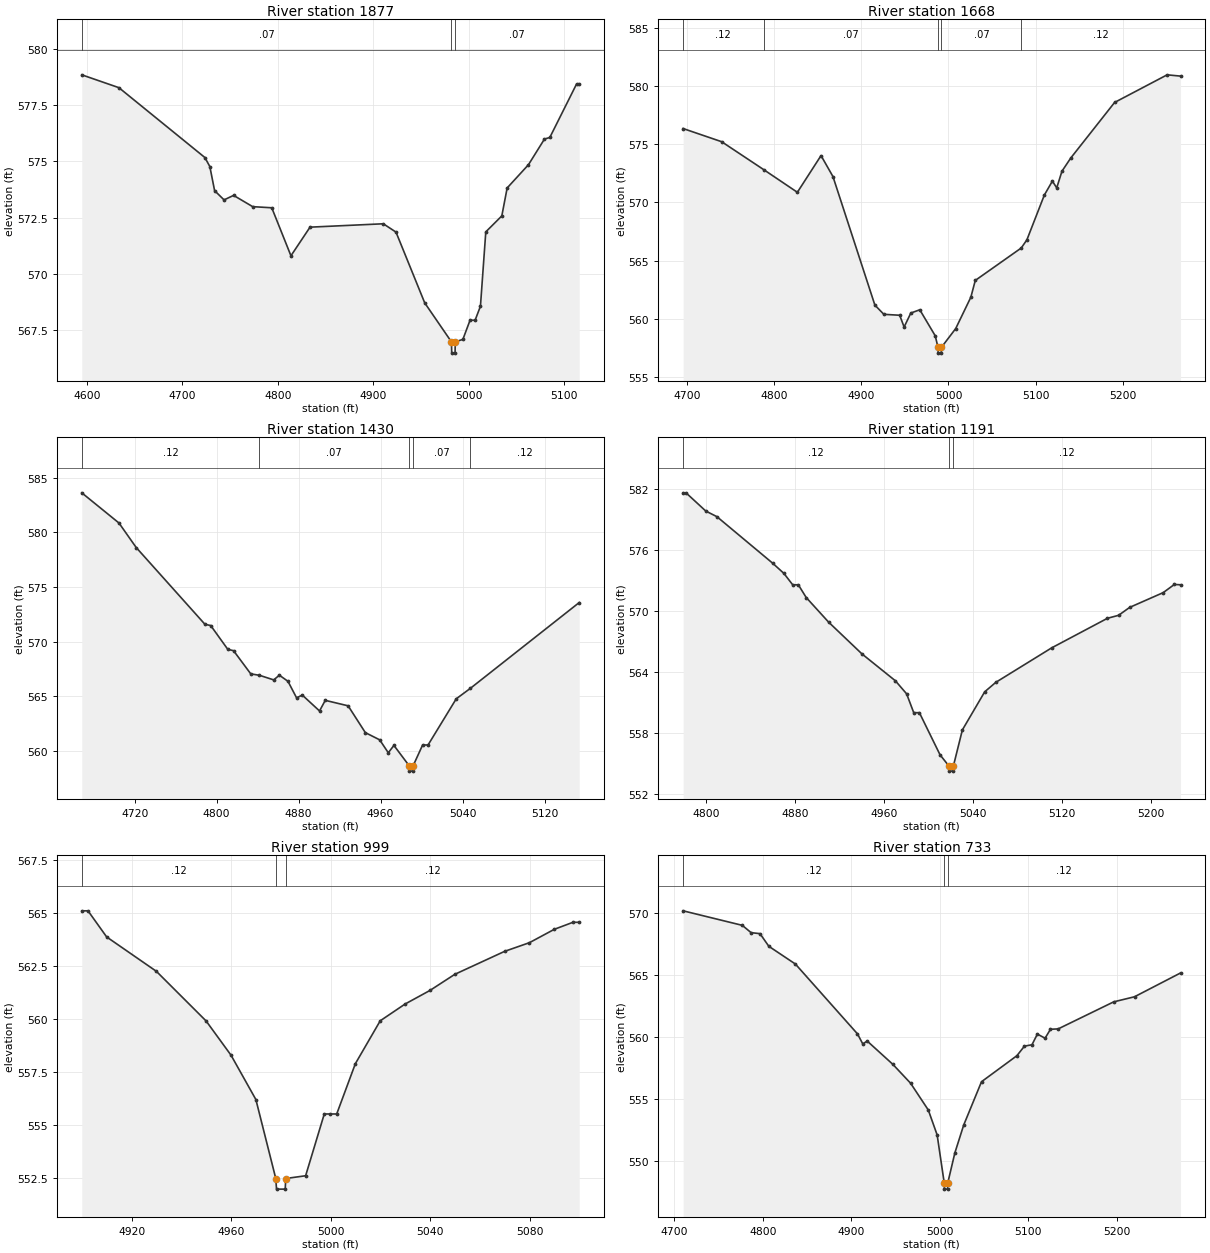
Type RM Length L Ch R = 1,1877,209,209,209
BEGIN DESCRIPTION:
SANDIES TRIBUTARY 13 4.0
END DESCRIPTION:
XS GIS Cut Line= 3
      2322983.84     13706947.33      2322575.00     13706925.00
      2322474.96     13706975.02
#Sta/Elev= 30
  4594.5  578.84  4633.4  578.27  4723.5  575.17  4728.7  574.77  4733.7  573.70
  4743.6  573.29  4753.6  573.49  4773.6  572.99  4793.6  572.94  4813.7  570.81
  4833.7  572.08  4910.5  572.23  4923.8  571.86  4953.9  568.72  4981.9  566.99
  4982.2  566.49  4985.7  566.49  4985.9  566.99  4993.9  567.10  5001.4  567.95
  5006.7  567.95  5012.3  568.57  5017.9  571.87  5034.7  572.58  5040.3  573.82
  5062.6  574.85  5079.4  575.99  5085.0  576.06  5113.0  578.43  5115.8  578.43
#Mann=3,-1,0
  4594.5    0.07       0  4981.9    0.05       0  4985.9    0.07       0
Bank Sta=4981.9,4985.9
Exp/Cntr=0.3,0.1

Type RM Length L Ch R = 1,1668,238,238,238
BEGIN DESCRIPTION:
21653
END DESCRIPTION:
XS GIS Cut Line= 3
      2322948.57     13706822.05      2322595.17     13706732.09
      2322389.74     13706757.77
#Sta/Elev= 30
  4695.0  576.33  4739.3  575.20  4787.5  572.81  4826.3  570.86  4853.5  574.01
  4867.2  572.21  4915.4  561.18  4925.7  560.39  4943.9  560.31  4949.0  559.30
  4956.7  560.50  4967.0  560.78  4984.8  558.54  4987.9  557.56  4988.2  557.06
  4991.7  557.06  4991.9  557.56  5008.3  559.17  5025.7  561.86  5030.8  563.30
  5083.6  566.08  5090.1  566.78  5110.2  570.63  5119.4  571.82  5124.4  571.24
  5130.4  572.67  5140.5  573.80  5190.9  578.57  5251.3  580.94  5266.7  580.83
#Mann=5,-1,0
  4695.0    0.12       0  4787.5    0.07       0  4987.9    0.05       0
  4991.9    0.07       0  5083.6    0.12       0
Bank Sta=4987.9,4991.9
Exp/Cntr=0.3,0.1

Type RM Length L Ch R = 1,1430,239,239,239
BEGIN DESCRIPTION:
SANDIES TRIBUTARY 13 3.0
END DESCRIPTION:
XS GIS Cut Line= 3
      2322974.99     13706425.01      2322675.00     13706575.00
      2322524.99     13706575.00
#Sta/Elev= 30
  4668.4  583.61  4704.7  580.85  4721.5  578.61  4788.6  571.59  4794.2  571.48
  4810.9  569.30  4816.5  569.18  4833.3  567.06  4841.8  566.93  4855.7  566.51
  4861.2  566.94  4869.6  566.38  4878.0  564.87  4883.6  565.12  4900.4  563.67
  4906.0  564.64  4928.3  564.14  4945.1  561.69  4959.1  561.03  4967.5  559.85
  4973.0  560.52  4987.8  558.67  4988.1  558.17  4991.6  558.17  4991.8  558.67
  5001.0  560.56  5006.3  560.56  5033.8  564.78  5047.5  565.73  5153.8  573.58
#Mann=5,-1,0
  4668.4    0.12       0  4841.8    0.07       0  4987.8    0.05       0
  4991.8    0.07       0  5047.5    0.12       0
Bank Sta=4987.8,4991.8
Exp/Cntr=0.3,0.1

Type RM Length L Ch R = 1,1191,192,192,192
BEGIN DESCRIPTION:
21652
END DESCRIPTION:
XS GIS Cut Line= 2
      2322945.30     13706330.53      2322499.44     13706372.23
#Sta/Elev= 30
  4779.0  581.59  4781.6  581.59  4799.4  579.80  4809.4  579.25  4859.6  574.68
  4869.7  573.68  4877.7  572.55  4882.7  572.56  4889.8  571.31  4909.9  568.90
  4940.0  565.77  4970.1  563.13  4980.2  561.85  4986.6  560.00  4991.7  560.00
  5010.3  555.86  5018.3  554.76  5018.6  554.26  5022.1  554.26  5022.3  554.76
  5030.4  558.31  5050.5  562.05  5060.5  562.98  5110.7  566.36  5161.0  569.27
  5171.0  569.56  5181.0  570.34  5211.2  571.79  5221.2  572.59  5226.8  572.56
#Mann=3,-1,0
  4779.0    0.12       0  5018.3    0.05       0  5022.3    0.12       0
Bank Sta=5018.3,5022.3
Exp/Cntr=0.3,0.1

Type RM Length L Ch R = 1,999,266,266,266
BEGIN DESCRIPTION:
SANDIES TRIBUTARY 13 2.0
END DESCRIPTION:
XS GIS Cut Line= 3
      2322775.01     13706175.00      2322675.00     13706175.00
      2322575.01     13706175.00
#Sta/Elev= 25
  4899.9  565.10  4902.4  565.10  4909.9  563.87  4929.9  562.25  4949.9  559.91
  4959.9  558.30  4969.9  556.21  4977.9  552.49  4978.2  551.99  4981.7  551.99
  4981.9  552.49  4989.9  552.62  4997.4  555.53  4999.9  555.53  5002.4  555.53
  5009.9  557.90  5019.9  559.92  5029.9  560.71  5039.9  561.35  5049.9  562.11
  5069.9  563.19  5079.9  563.60  5089.9  564.23  5097.4  564.56  5099.9  564.56
#Mann=3,-1,0
  4899.9    0.12       0  4977.9    0.05       0  4981.9    0.12       0
Bank Sta=4977.9,4981.9
Exp/Cntr=0.3,0.1

Type RM Length L Ch R = 1,733,294,294,294
BEGIN DESCRIPTION:
21651
END DESCRIPTION:
XS GIS Cut Line= 3
      2322951.77     13705903.26      2322563.05     13705916.11
      2322463.49     13706057.43
#Sta/Elev= 30
  4710.1  570.20  4776.9  569.03  4786.9  568.44  4796.9  568.36  4806.9  567.34
  4836.9  565.91  4907.0  560.28  4913.0  559.47  4918.0  559.70  4947.0  557.82
  4967.0  556.30  4987.0  554.14  4997.0  552.13  5005.0  548.26  5005.3  547.76
  5008.8  547.76  5009.0  548.26  5017.0  550.68  5027.0  552.93  5047.1  556.42
  5087.1  558.52  5095.6  559.29  5104.1  559.40  5110.2  560.26  5118.9  559.93
  5125.0  560.65  5133.7  560.68  5196.4  562.86  5219.9  563.27  5271.9  565.19
#Mann=3,-1,0
  4710.1    0.12       0  5005.0    0.05       0  5009.0    0.12       0
Bank Sta=5005,5009
Exp/Cntr=0.3,0.1

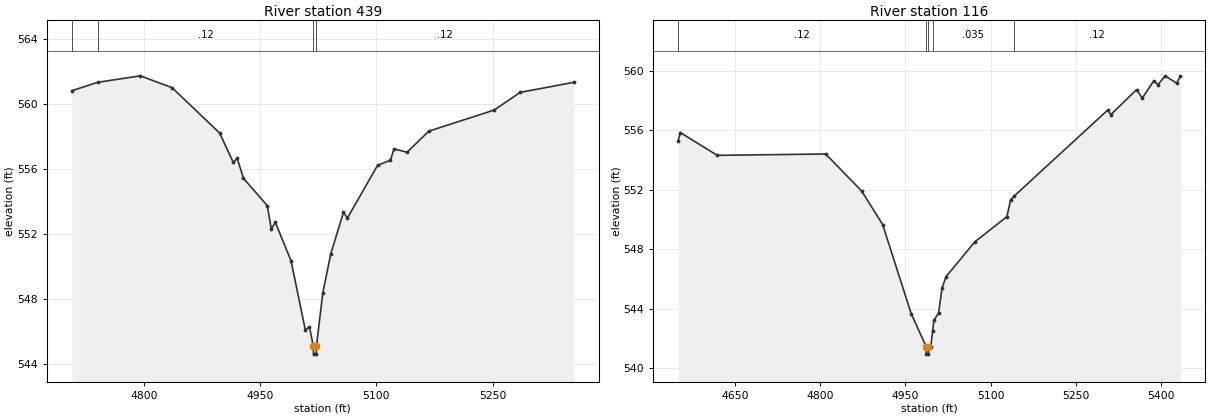
Type RM Length L Ch R = 1,439,323,323,323
BEGIN DESCRIPTION:
21650
END DESCRIPTION:
XS GIS Cut Line= 3
      2322961.41     13705585.22      2322563.05     13705671.96
      2322457.05     13705887.18
#Sta/Elev= 30
  4707.1  560.82  4740.6  561.34  4795.5  561.74  4836.5  561.01  4897.9  558.21
  4915.4  556.40  4920.5  556.65  4928.6  555.42  4959.3  553.74  4964.5  552.29
  4969.6  552.72  4990.0  550.33  5008.4  546.07  5013.6  546.28  5018.7  545.09
  5018.9  544.59  5022.4  544.59  5022.7  545.09  5030.9  548.36  5041.2  550.77
  5057.5  553.32  5062.7  552.98  5101.5  556.22  5118.2  556.54  5122.7  557.24
  5139.6  557.03  5167.7  558.33  5251.9  559.63  5285.5  560.72  5354.7  561.34
#Mann=4,-1,0
  4707.1   0.035       0  4740.6    0.12       0  5018.7    0.05       0
  5022.7    0.12       0
Bank Sta=5018.7,5022.7
Exp/Cntr=0.3,0.1

Type RM Length L Ch R = 1,116,0,0,0
BEGIN DESCRIPTION:
21649
END DESCRIPTION:
XS GIS Cut Line= 4
      2323083.52     13705289.67      2322643.36     13705331.44
      2322524.50     13705485.64      2322495.76     13705731.54
#Sta/Elev= 30
  4549.9  555.30  4553.4  555.84  4618.7  554.31  4809.6  554.40  4872.9  551.92
  4910.0  549.66  4960.3  543.67  4986.7  541.46  4987.0  540.96  4990.5  540.96
  4990.7  541.46  4994.8  541.46  4998.1  542.54  5000.2  543.22  5008.4  543.72
  5014.7  545.42  5021.8  546.17  5072.3  548.50  5128.8  550.19  5135.4  551.32
  5141.5  551.57  5306.7  557.36  5311.8  557.04  5357.2  558.72  5367.3  558.15
  5387.4  559.31  5395.1  559.06  5407.6  559.65  5427.7  559.16  5434.3  559.62
#Mann=5,-1,0
  4549.9    0.12       0  4986.7   0.035       0  4990.7    0.12       0
  4998.1   0.035       0  5141.5    0.12       0
Bank Sta=4986.7,4990.7
Exp/Cntr=0.3,0.1

Chan Stop Cuts=-1