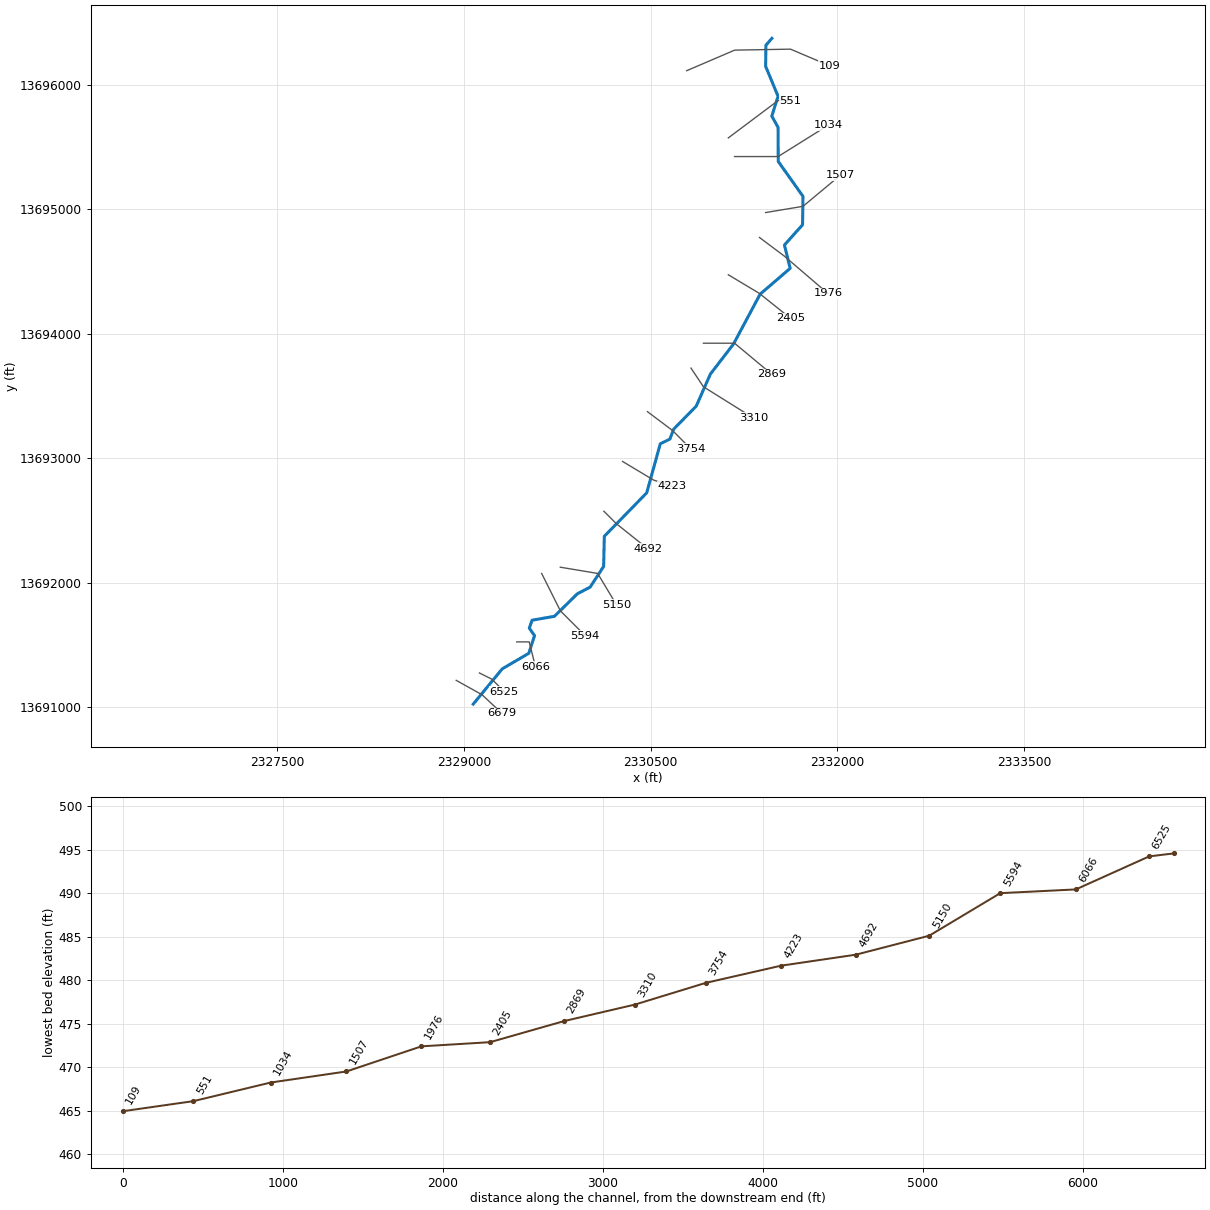
--- SANDIES TRIBUTARY 14.prj (project) ---

Proj Title=SANDIES TRIBUTARY 14 Base Level Engineering
Current Plan=p01
Default Exp/Contr=0.3,0.1
English Units
Geom File=g01
Flow File=f01
Plan File=p01
BEGIN DESCRIPTION:
SANDIES TRIBUTARY 14
END DESCRIPTION:

--- SANDIES TRIBUTARY 14.p01 (plan) ---

Plan Title=Multiple Run
Short Identifier=Multiple
Geom File=g01
Flow File=f01
Subcritical Flow
K Sum by GR= 0
Std Step Tol= 0.01
Critical Tol= 0.01
Num of Std Step Trials= 20
Max Error Tol= 0.3
Flow Tol Ratio= 0.001
Split Flow NTrial= 30
Split Flow Tol= 0.02
Split Flow Ratio= 0.02
Log Output Level= 0
Friction Slope Method= 1
Unsteady Friction Slope Method= 2
Unsteady Bridges Friction Slope Method= 1
Parabolic Critical Depth
Global Vel Dist=  1 , 1 , 1
Global Log Level= 0
CheckData=True
Encroach Param= -1, 0, 0, 0
BEGIN DESCRIPTION:
Multiple Run
END DESCRIPTION:

--- SANDIES TRIBUTARY 14.f01 (steady flow) ---

Flow Title=Multiple
Number of Profiles=7
Profile Names=10-year,25-year,50-year,1pct_min,100-year,1pct_plu,500-year
River Rch & RM= SANDIES TRIBUTAR,Reach-1,6679
     821    1362    1864    1236    2466    4920    4276
River Rch & RM= SANDIES TRIBUTAR,Reach-1,5594
    1088    1824    2514    1675    3342    6669    5861
Boundary for River Rch & Prof#=SANDIES TRIBUTAR,Reach-1,1
Up Type=0
Dn Type=3
Dn Slope=0.005
Boundary for River Rch & Prof#=SANDIES TRIBUTAR,Reach-1,2
Up Type=0
Dn Type=3
Dn Slope=0.005
Boundary for River Rch & Prof#=SANDIES TRIBUTAR,Reach-1,3
Up Type=0
Dn Type=3
Dn Slope=0.005
Boundary for River Rch & Prof#=SANDIES TRIBUTAR,Reach-1,4
Up Type=0
Dn Type=3
Dn Slope=0.005
Boundary for River Rch & Prof#=SANDIES TRIBUTAR,Reach-1,5
Up Type=0
Dn Type=3
Dn Slope=0.005
Boundary for River Rch & Prof#=SANDIES TRIBUTAR,Reach-1,6
Up Type=0
Dn Type=3
Dn Slope=0.005
Boundary for River Rch & Prof#=SANDIES TRIBUTAR,Reach-1,7
Up Type=0
Dn Type=3
Dn Slope=0.005

--- SANDIES TRIBUTARY 14.g01 (geometry) ---

Geom Title=Existing Conditions

River Reach=SANDIES TRIBUTAR,Reach-1
Reach XY= 30
      2329075.00     13691025.00      2329308.29     13691308.36
      2329521.84     13691433.34      2329567.41     13691575.01
      2329525.86     13691635.69      2329547.51     13691698.97
      2329727.45     13691730.47      2329911.80     13691911.36
      2330014.35     13691965.00      2330122.94     13692130.86
      2330128.54     13692373.54      2330469.17     13692722.70
      2330578.19     13693116.65      2330655.26     13693154.57
      2330685.78     13693234.66      2330866.86     13693418.94
      2330980.85     13693677.29      2331166.84     13693918.95
      2331380.62     13694319.38      2331621.87     13694526.63
      2331575.93     13694714.52      2331721.46     13694876.46
      2331725.04     13695105.02      2331526.20     13695385.50
      2331524.46     13695659.79      2331474.60     13695750.00
      2331524.62     13695909.73      2331424.79     13696149.92
      2331426.89     13696319.22      2331475.00     13696375.00

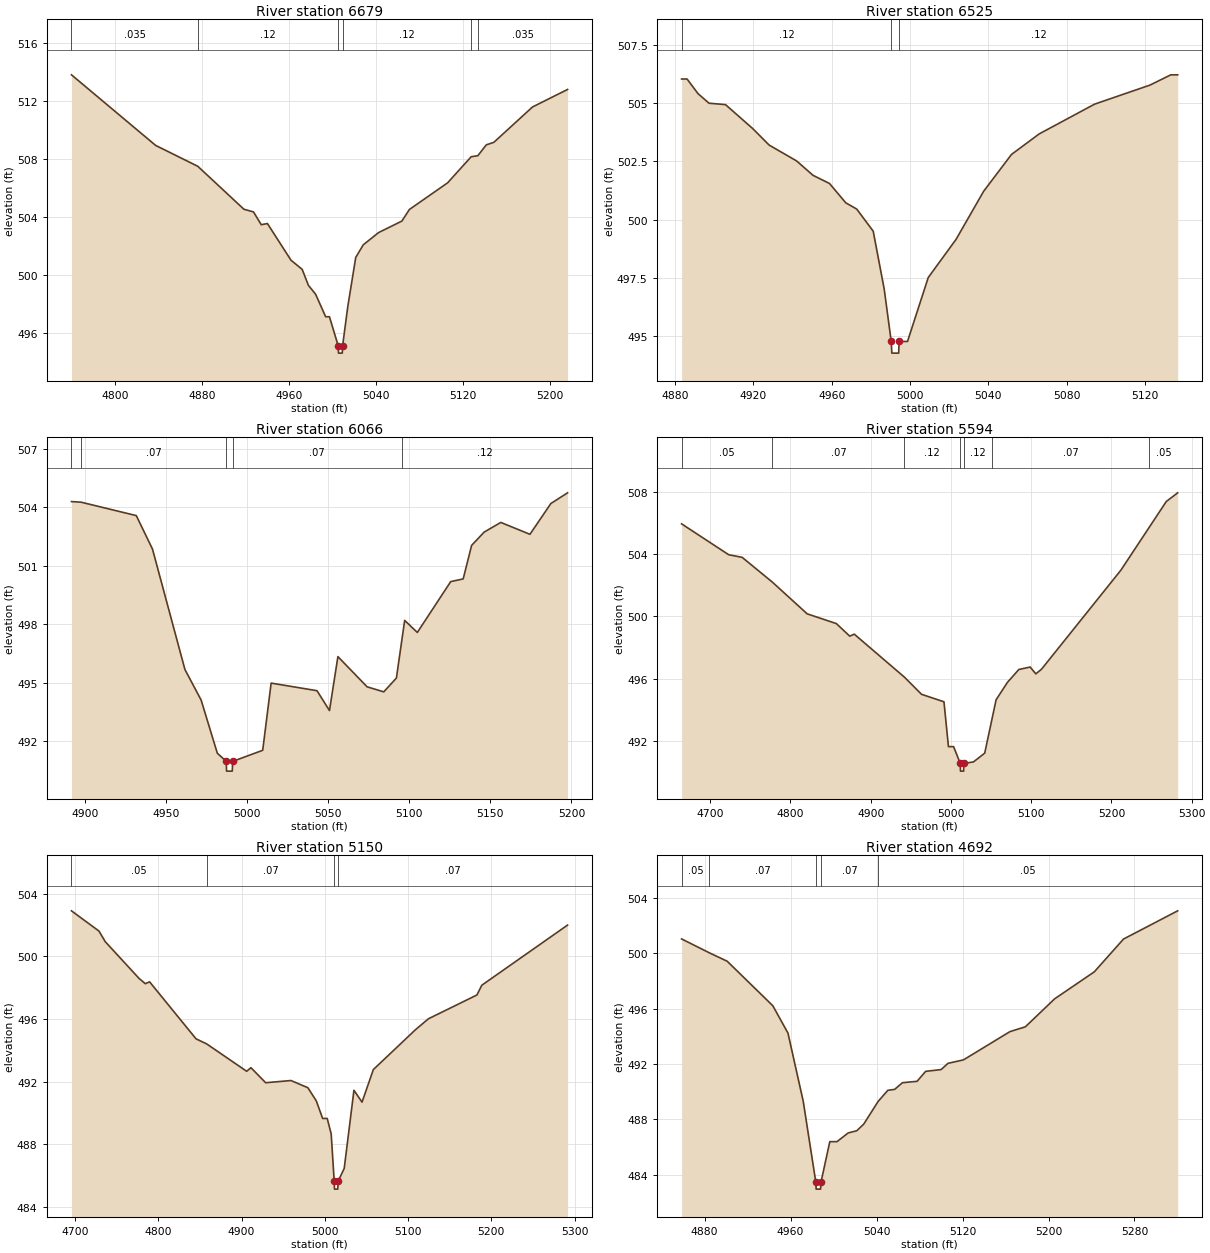
Type RM Length L Ch R = 1,6679,154,154,154
BEGIN DESCRIPTION:
Z21512
END DESCRIPTION:
XS GIS Cut Line= 3
      2328938.62     13691215.69      2329146.09     13691100.13
      2329306.26     13690950.47
#Sta/Elev= 30
  4759.6  513.80  4837.1  508.93  4875.9  507.49  4918.3  504.53  4927.2  504.34
  4934.3  503.46  4940.0  503.54  4961.7  501.01  4972.0  500.38  4977.7  499.28
  4984.4  498.66  4993.6  497.11  4997.1  497.11  5005.2  495.10  5005.4  494.60
  5008.9  494.60  5009.2  495.10  5014.0  497.82  5021.3  501.20  5028.2  502.07
  5042.4  502.92  5063.8  503.71  5070.7  504.51  5105.9  506.35  5127.6  508.15
  5133.7  508.22  5141.5  508.97  5148.4  509.14  5184.0  511.58  5216.3  512.79
#Mann=6,-1,0
  4759.6   0.035       0  4875.9    0.12       0  5005.2    0.05       0
  5009.2    0.12       0  5127.6    0.07       0  5133.7   0.035       0
Bank Sta=5005.2,5009.2
Exp/Cntr=0.3,0.1

Type RM Length L Ch R = 1,6525,459,459,459
BEGIN DESCRIPTION:
SANDIES TRIBUTARY 14 14.0
END DESCRIPTION:
XS GIS Cut Line= 3
      2329125.00     13691275.00      2329225.00     13691225.00
      2329324.99     13691125.01
#Sta/Elev= 28
  4883.4  506.04  4886.2  506.04  4891.8  505.41  4897.4  505.00  4905.8  504.94
  4919.7  503.91  4928.1  503.20  4942.1  502.52  4950.5  501.90  4958.9  501.55
  4967.2  500.72  4972.8  500.45  4981.2  499.50  4986.8  497.02  4990.4  494.76
  4990.7  494.26  4994.2  494.26  4994.4  494.76  4998.7  494.76  5009.3  497.51
  5023.5  499.15  5037.6  501.22  5051.8  502.80  5065.9  503.68  5094.2  504.96
  5122.5  505.78  5133.1  506.22  5136.6  506.22
#Mann=3,-1,0
  4883.4    0.12       0  4990.4    0.05       0  4994.4    0.12       0
Bank Sta=4990.4,4994.4
Exp/Cntr=0.3,0.1

Type RM Length L Ch R = 1,6066,472,472,472
BEGIN DESCRIPTION:
SANDIES TRIBUTARY 14 13.0
END DESCRIPTION:
XS GIS Cut Line= 3
      2329425.03     13691525.00      2329525.00     13691525.00
      2329574.99     13691325.02
#Sta/Elev= 30
  4891.5  504.30  4897.4  504.27  4931.5  503.58  4941.5  501.86  4961.5  495.68
  4971.5  494.11  4981.5  491.38  4987.0  490.96  4987.2  490.46  4990.7  490.46
  4991.0  490.96  5009.5  491.53  5014.7  494.98  5043.0  494.59  5050.7  493.57
  5055.9  496.34  5073.9  494.79  5084.2  494.53  5092.0  495.24  5095.2  497.10
  5097.1  498.20  5104.9  497.58  5125.5  500.19  5133.2  500.33  5138.4  502.05
  5146.1  502.73  5156.4  503.23  5174.4  502.62  5187.3  504.20  5197.6  504.75
#Mann=5,-1,0
  4891.5    0.12       0  4897.4    0.07       0  4987.0    0.05       0
  4991.0    0.07       0  5095.2    0.12       0
Bank Sta=4987,4991
Exp/Cntr=0.3,0.1

Type RM Length L Ch R = 1,5594,444,444,444
BEGIN DESCRIPTION:
SANDIES TRIBUTARY 14 12.0
END DESCRIPTION:
XS GIS Cut Line= 3
      2329624.99     13692075.01      2329775.00     13691775.00
      2329975.02     13691574.98
#Sta/Elev= 30
  4664.3  505.97  4723.0  503.98  4739.8  503.81  4777.3  502.22  4820.8  500.17
  4857.2  499.54  4873.9  498.73  4879.5  498.86  4942.0  496.09  4963.4  494.98
  4991.3  494.50  4996.9  491.61  5003.3  491.61  5011.6  490.53  5011.9  490.03
  5015.8  490.03  5016.1  490.53  5028.0  490.62  5042.1  491.19  5051.6  493.49
  5056.3  494.63  5070.4  495.75  5084.6  496.58  5098.7  496.74  5105.8  496.30
  5112.9  496.60  5211.9  502.99  5246.8  505.72  5268.4  507.41  5282.6  507.97
#Mann=7,-1,0
  4664.3    0.05       0  4777.3    0.07       0  4942.0    0.12       0
  5011.6    0.05       0  5016.1    0.12       0  5051.6    0.07       0
  5246.8    0.05       0
Bank Sta=5011.6,5016.1
Exp/Cntr=0.3,0.1

Type RM Length L Ch R = 1,5150,458,458,458
BEGIN DESCRIPTION:
SANDIES TRIBUTARY 14 11.0
END DESCRIPTION:
XS GIS Cut Line= 3
      2329774.97     13692125.00      2330075.00     13692075.00
      2330224.99     13691825.01
#Sta/Elev= 30
  4695.8  502.90  4728.8  501.61  4736.4  500.93  4776.9  498.59  4784.5  498.25
  4789.6  498.37  4845.4  494.73  4858.1  494.41  4906.2  492.66  4911.3  492.89
  4929.0  491.93  4959.4  492.07  4979.7  491.61  4989.8  490.77  4997.4  489.65
  5002.9  489.65  5007.7  488.66  5011.3  485.64  5011.6  485.14  5015.6  485.14
  5015.9  485.64  5023.3  486.46  5035.0  491.45  5044.7  490.69  5058.3  492.77
  5108.8  495.31  5124.4  496.01  5182.7  497.53  5188.5  498.15  5291.5  501.99
#Mann=4,-1,0
  4695.8    0.05       0  4858.1    0.07       0  5011.3    0.05       0
  5015.9    0.07       0
Bank Sta=5011.3,5015.9
Exp/Cntr=0.3,0.1

Type RM Length L Ch R = 1,4692,469,469,469
BEGIN DESCRIPTION:
SANDIES TRIBUTARY 14 10.0
END DESCRIPTION:
XS GIS Cut Line= 3
      2330124.99     13692575.01      2330225.00     13692475.00
      2330475.01     13692275.00
#Sta/Elev= 30
  4858.6  501.04  4884.3  500.04  4901.0  499.43  4943.5  496.21  4957.6  494.23
  4971.8  489.30  4983.5  483.46  4983.8  482.96  4987.9  482.96  4988.3  483.46
  4996.5  486.39  5003.2  486.39  5013.6  487.02  5021.6  487.18  5028.1  487.66
  5041.5  489.30  5050.5  490.10  5056.9  490.17  5064.1  490.65  5077.7  490.75
  5085.7  491.47  5100.1  491.60  5106.5  492.05  5120.9  492.30  5164.1  494.34
  5178.5  494.69  5205.7  496.71  5242.6  498.66  5269.8  501.03  5320.2  503.07
#Mann=5,-1,0
  4858.6    0.05       0  4884.3    0.07       0  4983.5    0.05       0
  4988.3    0.07       0  5041.5    0.05       0
Bank Sta=4983.5,4988.3
Exp/Cntr=0.3,0.1

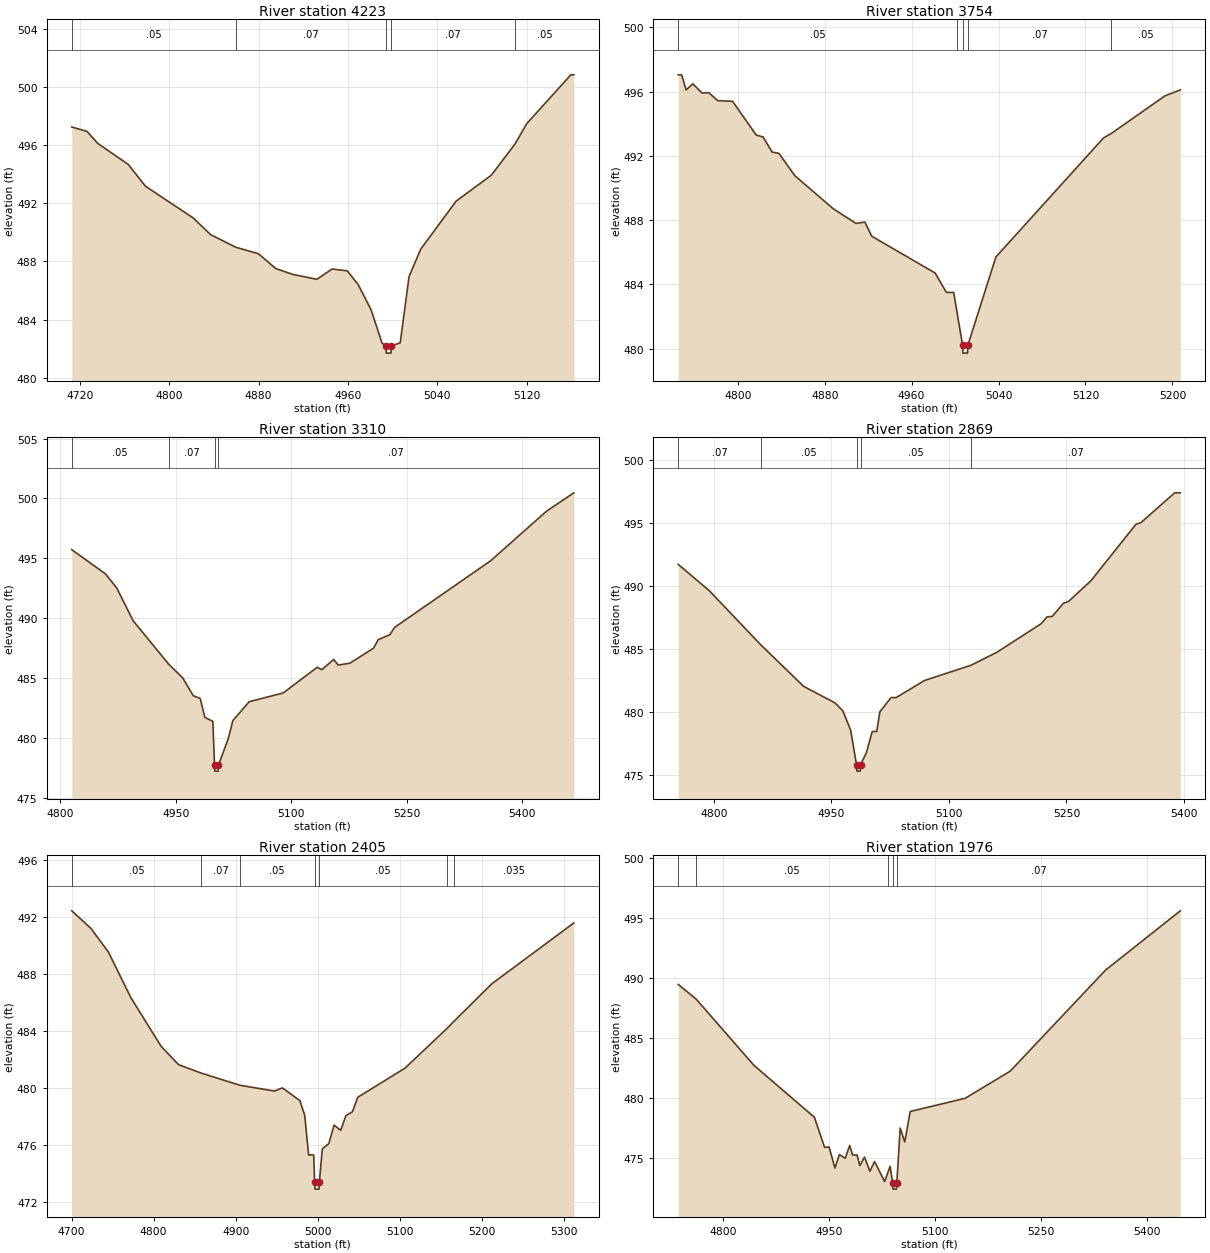
Type RM Length L Ch R = 1,4223,469,469,469
BEGIN DESCRIPTION:
SANDIES TRIBUTARY 14 9.0
END DESCRIPTION:
XS GIS Cut Line= 3
      2330275.00     13692975.00      2330525.00     13692825.00
      2330675.04     13692774.99
#Sta/Elev= 30
  4712.6  497.25  4726.2  496.95  4735.9  496.12  4763.1  494.68  4778.7  493.17
  4821.4  490.99  4837.0  489.84  4859.7  488.97  4879.8  488.53  4895.3  487.51
  4910.9  487.10  4932.2  486.77  4945.8  487.48  4959.4  487.35  4969.2  486.40
  4980.8  484.65  4990.5  482.38  4993.9  482.19  4994.3  481.69  4998.5  481.69
  4998.8  482.19  5006.8  482.40  5014.7  486.96  5025.2  488.85  5056.9  492.15
  5088.5  493.94  5109.8  496.10  5120.1  497.48  5159.6  500.84  5162.3  500.84
#Mann=5,-1,0
  4712.6    0.05       0  4859.7    0.07       0  4993.9    0.05       0
  4998.8    0.07       0  5109.8    0.05       0
Bank Sta=4993.9,4998.8
Exp/Cntr=0.3,0.1

Type RM Length L Ch R = 1,3754,444,444,444
BEGIN DESCRIPTION:
SANDIES TRIBUTARY 14 8.0
END DESCRIPTION:
XS GIS Cut Line= 3
      2330475.03     13693374.98      2330675.00     13693225.00
      2330825.00     13693075.00
#Sta/Elev= 30
  4745.2  497.05  4748.3  497.05  4752.5  496.11  4758.7  496.49  4767.0  495.92
  4773.3  495.94  4781.6  495.44  4795.2  495.40  4817.0  493.30  4823.3  493.18
  4831.6  492.24  4837.9  492.16  4852.5  490.77  4887.9  488.71  4908.7  487.80
  4917.0  487.88  4923.3  487.00  4981.6  484.71  4992.0  483.50  4998.7  483.50
  5001.7  482.30  5006.9  480.22  5007.2  479.72  5011.4  479.72  5011.8  480.22
  5037.6  485.71  5136.6  493.12  5143.8  493.40  5193.2  495.74  5207.3  496.11
#Mann=5,-1,0
  4745.2    0.05       0  5001.7    0.07       0  5006.9    0.05       0
  5011.8    0.07       0  5143.8    0.05       0
Bank Sta=5006.9,5011.8
Exp/Cntr=0.3,0.1

Type RM Length L Ch R = 1,3310,441,441,441
BEGIN DESCRIPTION:
SANDIES TRIBUTARY 14 7.0
END DESCRIPTION:
XS GIS Cut Line= 3
      2330825.00     13693725.00      2330925.00     13693575.00
      2331325.02     13693324.99
#Sta/Elev= 30
  4815.1  495.72  4858.7  493.71  4873.7  492.50  4894.7  489.79  4940.9  486.16
  4959.3  485.00  4972.8  483.52  4981.9  483.29  4987.9  481.71  4998.3  481.38
  5000.5  477.72  5000.9  477.22  5005.2  477.22  5005.6  477.72  5018.4  479.95
  5024.3  481.44  5045.5  483.02  5089.7  483.75  5133.9  485.90  5139.8  485.69
  5155.2  486.55  5161.1  486.08  5176.4  486.24  5207.1  487.50  5213.0  488.20
  5228.3  488.62  5234.2  489.22  5359.2  494.80  5431.7  498.94  5467.1  500.47
#Mann=4,-1,0
  4815.1    0.05       0  4940.9    0.07       0  5000.5    0.05       0
  5005.6    0.07       0
Bank Sta=5000.5,5005.6
Exp/Cntr=0.3,0.1

Type RM Length L Ch R = 1,2869,464,464,464
BEGIN DESCRIPTION:
SANDIES TRIBUTARY 14 6.0
END DESCRIPTION:
XS GIS Cut Line= 3
      2330924.95     13693925.00      2331175.00     13693925.00
      2331475.03     13693674.97
#Sta/Elev= 30
  4754.7  491.72  4794.7  489.61  4860.2  485.33  4914.7  482.05  4954.7  480.74
  4964.7  480.11  4974.7  478.58  4982.2  475.83  4982.6  475.33  4986.9  475.33
  4987.3  475.83  4994.7  476.78  5002.2  478.47  5008.0  478.47  5011.9  480.02
  5026.2  481.16  5032.7  481.16  5069.2  482.52  5128.1  483.72  5161.0  484.74
  5217.6  487.01  5225.4  487.56  5231.9  487.59  5246.2  488.64  5252.7  488.78
  5281.4  490.43  5338.6  494.89  5345.1  495.03  5388.1  497.39  5395.3  497.39
#Mann=5,-1,0
  4754.7    0.07       0  4860.2    0.05       0  4982.2    0.05       0
  4987.3    0.05       0  5128.1    0.07       0
Bank Sta=4982.2,4987.3
Exp/Cntr=0.3,0.1

Type RM Length L Ch R = 1,2405,429,429,429
BEGIN DESCRIPTION:
SANDIES TRIBUTARY 14 5.0
END DESCRIPTION:
XS GIS Cut Line= 3
      2331124.99     13694475.00      2331375.00     13694325.00
      2331624.99     13694125.01
#Sta/Elev= 30
  4700.3  492.45  4723.6  491.22  4745.0  489.55  4772.2  486.36  4809.2  482.93
  4830.5  481.64  4858.1  481.05  4904.9  480.20  4947.1  479.79  4956.9  480.01
  4978.2  479.12  4984.1  478.09  4988.9  475.30  4995.1  475.30  4996.2  473.40
  4996.7  472.90  5001.5  472.90  5002.0  473.40  5005.5  475.72  5013.5  476.10
  5019.9  477.40  5027.9  477.03  5034.3  478.06  5042.3  478.34  5048.7  479.35
  5106.3  481.40  5157.3  484.18  5165.8  484.68  5212.0  487.32  5312.0  491.60
#Mann=7,-1,0
  4700.3    0.05       0  4858.1    0.07       0  4904.9    0.05       0
  4996.2    0.05       0  5002.0    0.05       0  5157.3    0.07       0
  5165.8   0.035       0
Bank Sta=4996.2,5002
Exp/Cntr=0.3,0.1

Type RM Length L Ch R = 1,1976,469,469,469
BEGIN DESCRIPTION:
SANDIES TRIBUTARY 14 4.0
END DESCRIPTION:
XS GIS Cut Line= 3
      2331374.96     13694775.03      2331575.00     13694625.00
      2331924.98     13694325.01
#Sta/Elev= 30
  4736.6  489.48  4762.2  488.24  4843.9  482.73  4929.4  478.41  4943.9  475.90
  4950.2  475.93  4958.5  474.18  4964.8  475.30  4973.1  474.99  4979.4  476.06
  4983.5  475.26  4989.9  475.26  4993.8  474.38  5000.4  475.09  5008.0  473.91
  5014.6  474.72  5028.9  473.05  5034.0  473.89  5036.6  474.32  5040.3  472.92
  5040.8  472.42  5045.6  472.42  5046.1  472.92  5050.9  477.51  5057.4  476.35
  5065.1  478.89  5143.0  479.99  5206.7  482.25  5341.7  490.67  5447.6  495.61
#Mann=5,-1,0
  4736.6    0.07       0  4762.2    0.05       0  5034.0    0.07       0
  5040.3    0.05       0  5046.1    0.07       0
Bank Sta=5040.3,5046.1
Exp/Cntr=0.3,0.1

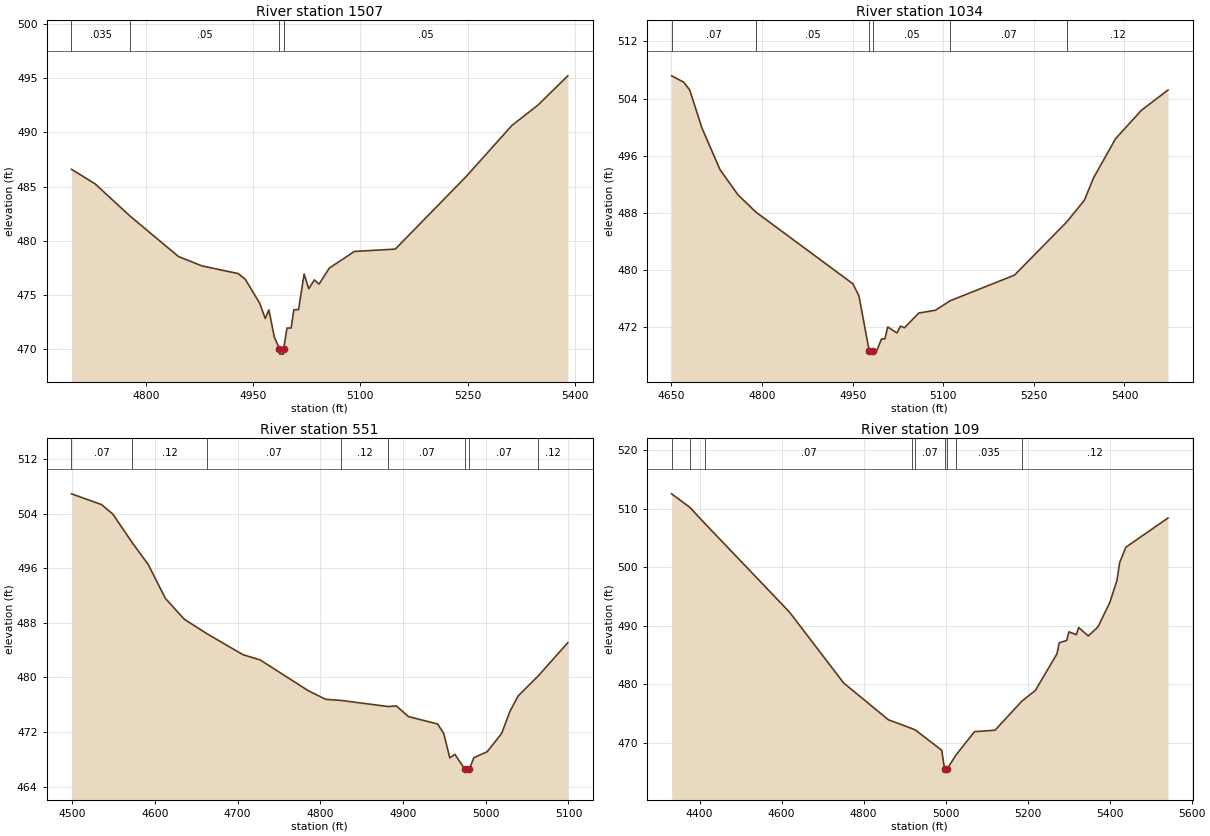
Type RM Length L Ch R = 1,1507,473,473,473
BEGIN DESCRIPTION:
SANDIES TRIBUTARY 14 3.0
END DESCRIPTION:
XS GIS Cut Line= 3
      2331424.98     13694975.00      2331725.00     13695025.00
      2332025.02     13695275.02
#Sta/Elev= 30
  4695.7  486.60  4728.7  485.26  4777.3  482.30  4845.3  478.55  4878.2  477.68
  4928.9  476.97  4939.0  476.44  4959.3  474.21  4966.9  472.82  4972.0  473.61
  4979.6  471.11  4986.8  470.03  4987.2  469.53  4992.2  469.53  4992.7  470.03
  4997.3  471.94  5003.1  471.94  5007.0  473.63  5013.5  473.64  5021.3  476.93
  5027.8  475.57  5035.7  476.39  5042.2  475.99  5056.5  477.47  5091.6  479.01
  5148.9  479.23  5247.8  485.91  5312.3  490.66  5348.1  492.50  5390.4  495.23
#Mann=4,-1,0
  4695.7   0.035       0  4777.3    0.05       0  4986.8    0.05       0
  4992.7    0.05       0
Bank Sta=4986.8,4992.7
Exp/Cntr=0.3,0.1

Type RM Length L Ch R = 1,1034,483,483,483
BEGIN DESCRIPTION:
SANDIES TRIBUTARY 14 2.0
END DESCRIPTION:
XS GIS Cut Line= 3
      2331174.99     13695425.00      2331525.00     13695425.00
      2331924.99     13695675.00
#Sta/Elev= 30
  4650.4  507.18  4670.4  506.29  4680.4  505.18  4700.4  499.92  4730.4  494.07
  4760.4  490.52  4789.9  488.12  4950.4  478.10  4960.4  476.42  4977.4  468.76
  4977.9  468.26  4982.9  468.26  4983.4  468.76  4990.4  468.84  4997.9  470.39
  5003.4  470.39  5008.1  472.06  5023.4  471.22  5029.3  472.18  5035.8  471.94
  5059.4  474.00  5087.1  474.40  5111.4  475.72  5218.0  479.31  5304.6  486.76
  5333.5  489.76  5348.9  492.92  5385.4  498.40  5427.9  502.35  5472.1  505.19
#Mann=6,-1,0
  4650.4    0.07       0  4789.9    0.05       0  4977.4    0.05       0
  4983.4    0.05       0  5111.4    0.07       0  5304.6    0.12       0
Bank Sta=4977.4,4983.4
Exp/Cntr=0.3,0.1

Type RM Length L Ch R = 1,551,442,442,442
BEGIN DESCRIPTION:
SANDIES TRIBUTARY 14 1.0
END DESCRIPTION:
XS GIS Cut Line= 3
      2331125.01     13695575.01      2331525.00     13695875.00
      2331625.01     13695875.00
#Sta/Elev= 30
  4499.2  506.90  4535.6  505.32  4549.2  503.93  4572.9  499.70  4591.9  496.56
  4612.7  491.58  4635.6  488.52  4663.0  486.40  4706.5  483.33  4727.3  482.56
  4785.6  478.04  4806.5  476.79  4825.5  476.62  4882.1  475.73  4891.9  475.82
  4906.5  474.26  4941.9  473.17  4949.2  471.79  4956.5  468.21  4962.7  468.73
  4974.3  466.62  4974.8  466.12  4980.3  466.62  4985.6  468.23  5001.7  469.11
  5019.2  471.79  5029.2  475.02  5039.2  477.30  5063.2  480.19  5099.2  485.09
#Mann=8,-1,0
  4499.2    0.07       0  4572.9    0.12       0  4663.0    0.07       0
  4825.5    0.12       0  4882.1    0.07       0  4974.3    0.05       0
  4980.3    0.07       0  5063.2    0.12       0
Bank Sta=4974.3,4980.3
Exp/Cntr=0.3,0.1

Type RM Length L Ch R = 1,109,0,0,0
BEGIN DESCRIPTION:
21654
END DESCRIPTION:
XS GIS Cut Line= 4
      2330790.35     13696114.91      2331176.04     13696280.21
      2331624.74     13696288.08      2331939.59     13696154.27
#Sta/Elev= 30
  4331.8  512.51  4376.0  510.21  4412.7  507.45  4619.1  492.31  4751.2  480.20
  4860.4  473.90  4918.9  472.38  4926.2  472.16  4990.4  468.70  4997.4  465.46
  4997.9  464.96  5003.5  465.46  5024.6  467.83  5070.4  471.87  5120.4  472.12
  5185.6  477.07  5218.8  478.92  5271.5  485.17  5277.0  487.06  5295.2  487.45
  5300.6  488.93  5318.8  488.45  5324.3  489.67  5347.9  488.23  5371.6  489.78
  5400.6  493.99  5417.8  497.71  5424.3  500.75  5439.5  503.39  5542.3  508.38
#Mann=9,-1,0
  4331.8    0.07       0  4376.0    0.12       0  4412.7    0.07       0
  4918.9    0.12       0  4926.2    0.07       0  4997.4    0.05       0
  5003.5    0.07       0  5024.6   0.035       0  5185.6    0.12       0
Bank Sta=4997.4,5003.5
Exp/Cntr=0.3,0.1

Chan Stop Cuts=-1