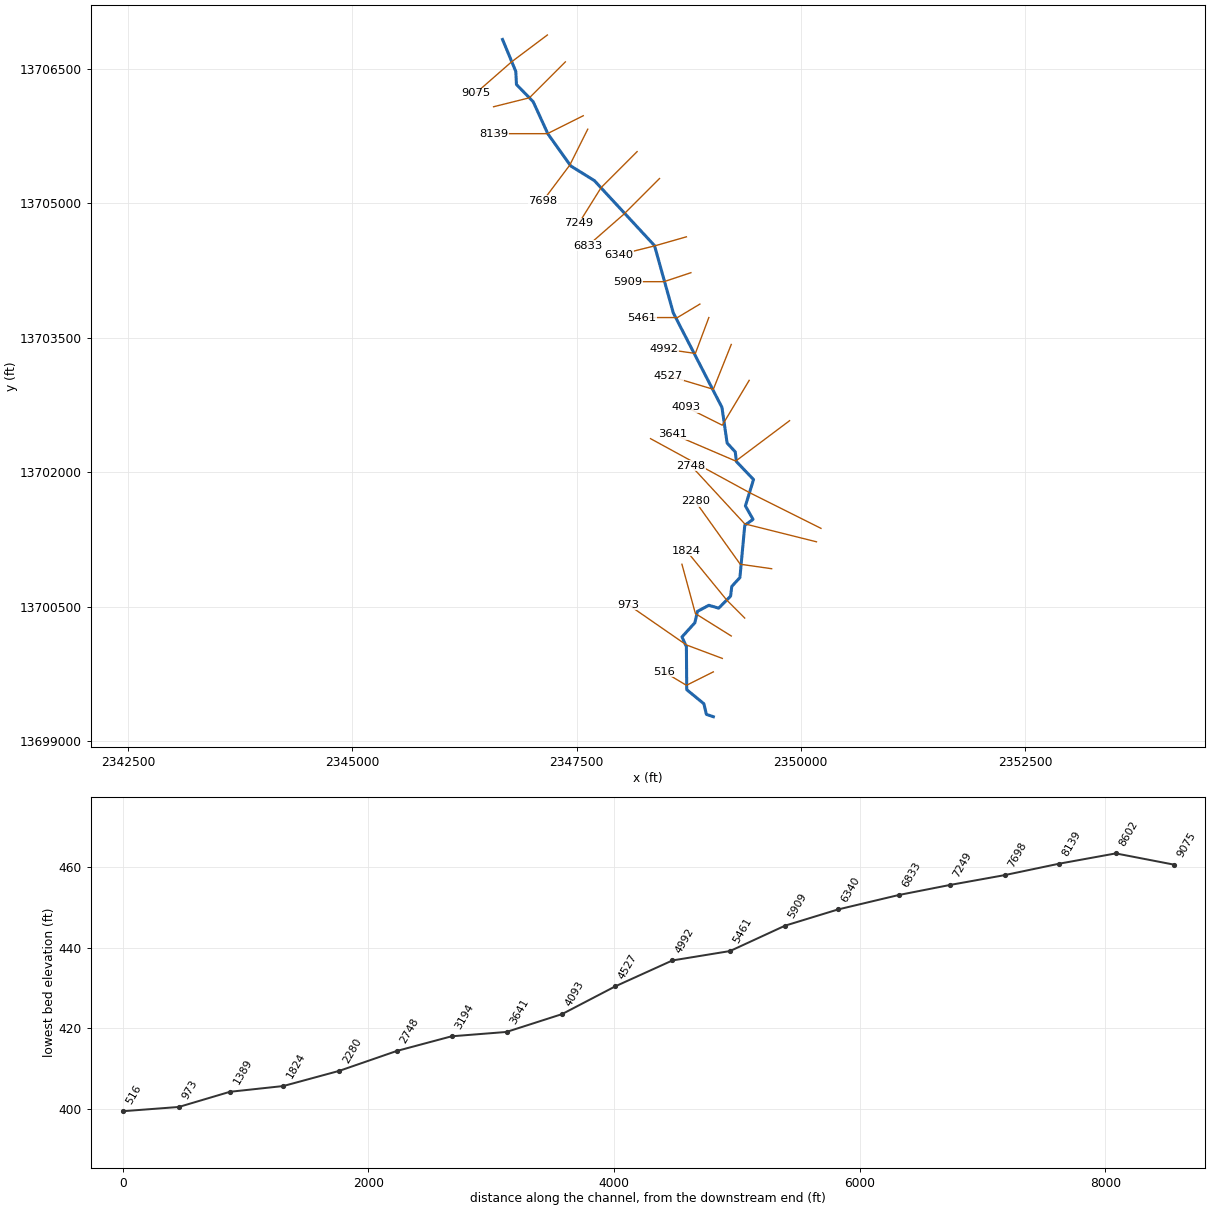
--- SANDIES TRIBUTARY 2.prj (project) ---

Proj Title=SANDIES TRIBUTARY 2 Base Level Engineering
Current Plan=p01
Default Exp/Contr=0.3,0.1
English Units
Geom File=g01
Flow File=f01
Plan File=p01
BEGIN DESCRIPTION:
SANDIES TRIBUTARY 2
END DESCRIPTION:

--- SANDIES TRIBUTARY 2.p01 (plan) ---

Plan Title=Multiple Run
Short Identifier=Multiple
Geom File=g01
Flow File=f01
Subcritical Flow
K Sum by GR= 0
Std Step Tol= 0.01
Critical Tol= 0.01
Num of Std Step Trials= 20
Max Error Tol= 0.3
Flow Tol Ratio= 0.001
Split Flow NTrial= 30
Split Flow Tol= 0.02
Split Flow Ratio= 0.02
Log Output Level= 0
Friction Slope Method= 1
Unsteady Friction Slope Method= 2
Unsteady Bridges Friction Slope Method= 1
Parabolic Critical Depth
Global Vel Dist=  1 , 1 , 1
Global Log Level= 0
CheckData=True
Encroach Param= -1, 0, 0, 0
BEGIN DESCRIPTION:
Multiple Run
END DESCRIPTION:

--- SANDIES TRIBUTARY 2.f01 (steady flow) ---

Flow Title=Multiple
Number of Profiles=7
Profile Names=10-year,25-year,50-year,1pct_min,100-year,1pct_plu,500-year
River Rch & RM= SANDIES TRIBUTAR,Reach-1,9075
     736    1207    1640    1079    2154    4297    3680
River Rch & RM= SANDIES TRIBUTAR,Reach-1,8139
    1124    1883    2592    1726    3444    6872    6028
River Rch & RM= SANDIES TRIBUTAR,Reach-1,973
    1181    1991    2754    1842    3674    7331    6489
Boundary for River Rch & Prof#=SANDIES TRIBUTAR,Reach-1,1
Up Type=0
Dn Type=3
Dn Slope=0.005
Boundary for River Rch & Prof#=SANDIES TRIBUTAR,Reach-1,2
Up Type=0
Dn Type=3
Dn Slope=0.005
Boundary for River Rch & Prof#=SANDIES TRIBUTAR,Reach-1,3
Up Type=0
Dn Type=3
Dn Slope=0.005
Boundary for River Rch & Prof#=SANDIES TRIBUTAR,Reach-1,4
Up Type=0
Dn Type=3
Dn Slope=0.005
Boundary for River Rch & Prof#=SANDIES TRIBUTAR,Reach-1,5
Up Type=0
Dn Type=3
Dn Slope=0.005
Boundary for River Rch & Prof#=SANDIES TRIBUTAR,Reach-1,6
Up Type=0
Dn Type=3
Dn Slope=0.005
Boundary for River Rch & Prof#=SANDIES TRIBUTAR,Reach-1,7
Up Type=0
Dn Type=3
Dn Slope=0.005

--- SANDIES TRIBUTARY 2.g01 (geometry) ---

Geom Title=Existing Conditions

River Reach=SANDIES TRIBUTAR,Reach-1
Reach XY= 30
      2346675.00     13706825.00      2346822.75     13706469.07
      2346830.47     13706322.55      2347016.86     13706131.06
      2347180.83     13705772.70      2347435.65     13705415.00
      2347698.51     13705252.01      2348369.17     13704527.30
      2348578.83     13703776.58      2349121.25     13702723.45
      2349178.62     13702326.50      2349269.46     13702227.42
      2349282.86     13702118.83      2349473.38     13701918.97
      2349382.53     13701624.99      2349467.77     13701474.71
      2349375.69     13701409.17      2349321.45     13700826.47
      2349230.54     13700727.42      2349217.14     13700618.83
      2349084.68     13700485.20      2348975.00     13700517.44
      2348847.72     13700448.90      2348819.47     13700322.58
      2348675.60     13700164.38      2348724.91     13700054.97
      2348728.54     13699576.46      2348919.74     13699419.53
      2348947.56     13699301.10      2349025.00     13699275.00

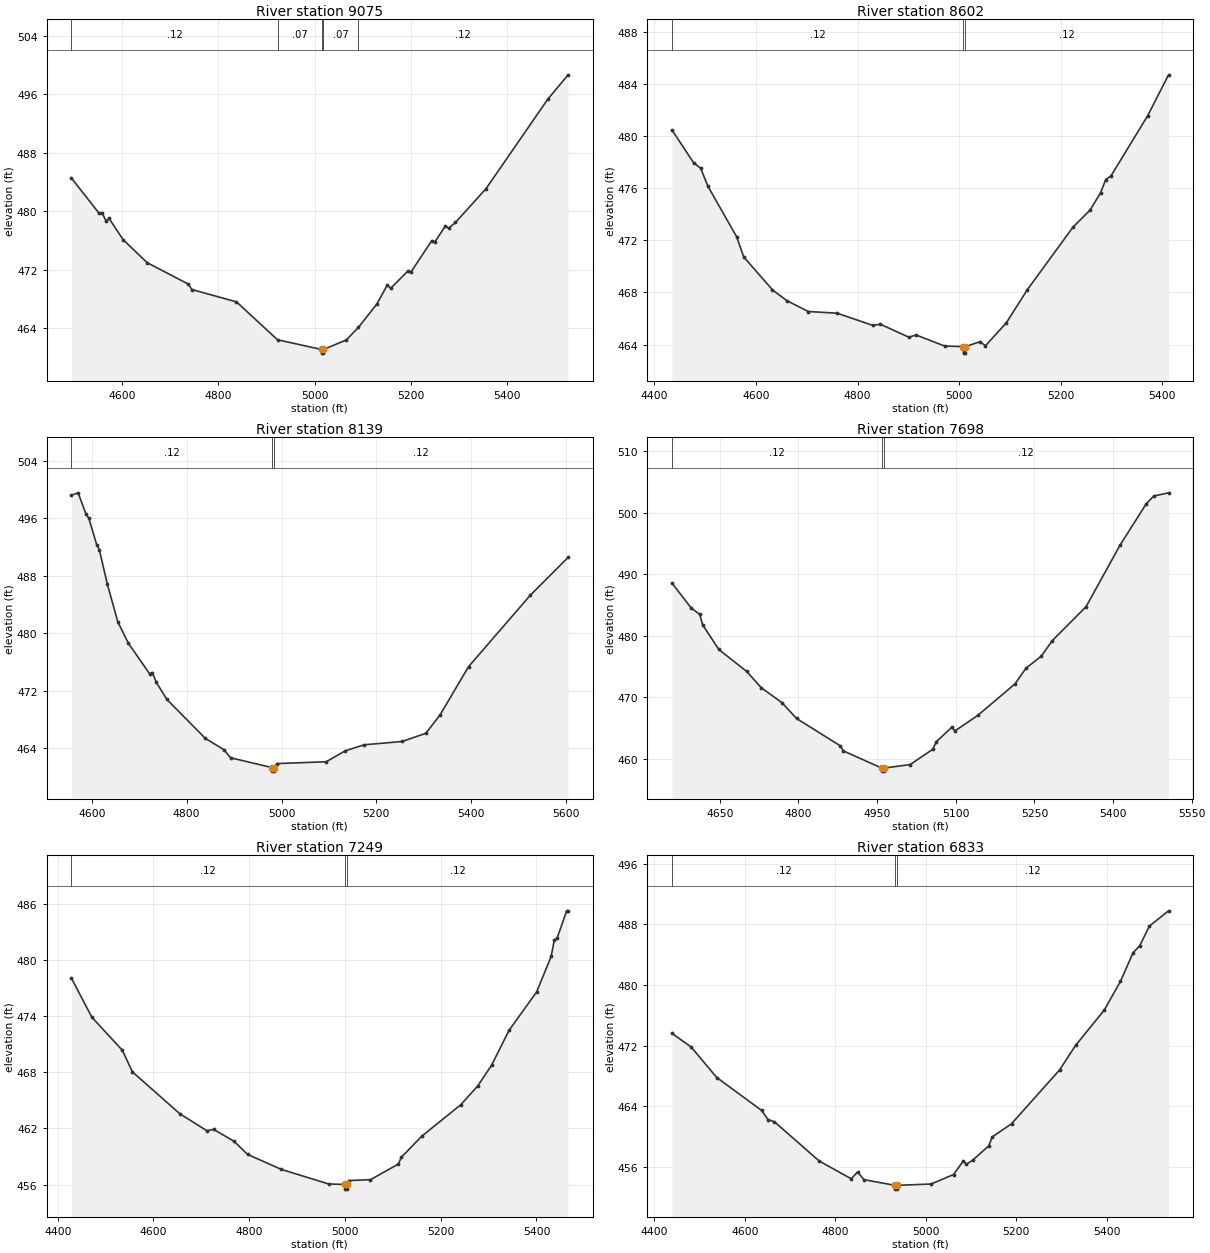
Type RM Length L Ch R = 1,9075,473,473,473
BEGIN DESCRIPTION:
SANDIES TRIBUTARY 2 20.0
END DESCRIPTION:
XS GIS Cut Line= 3
      2347175.01     13706875.00      2346775.00     13706575.00
      2346375.01     13706225.01
#Sta/Elev= 30
  4495.1  484.53  4552.4  479.72  4558.6  479.77  4567.0  478.67  4573.2  479.01
  4602.4  476.10  4652.4  472.95  4737.8  470.02  4745.1  469.28  4837.8  467.59
  4923.0  462.40  5014.4  461.07  5014.7  460.57  5018.3  460.57  5018.5  461.07
  5065.8  462.37  5091.2  464.10  5129.4  467.30  5151.2  469.91  5157.9  469.44
  5193.9  471.81  5200.6  471.71  5243.3  475.96  5249.9  475.80  5271.8  477.98
  5278.4  477.67  5292.7  478.47  5356.2  483.10  5484.4  495.34  5526.6  498.68
#Mann=5,-1,0
  4495.1    0.12       0  4923.0    0.07       0  5014.4    0.05       0
  5018.5    0.07       0  5091.2    0.12       0
Bank Sta=5014.4,5018.5
Exp/Cntr=0.3,0.1

Type RM Length L Ch R = 1,8602,463,463,463
BEGIN DESCRIPTION:
SANDIES TRIBUTARY 2 19.0
END DESCRIPTION:
XS GIS Cut Line= 3
      2347375.02     13706575.02      2346975.00     13706175.00
      2346575.02     13706075.01
#Sta/Elev= 30
  4434.5  480.46  4477.0  477.95  4491.1  477.52  4505.2  476.15  4561.8  472.28
  4575.9  470.72  4632.5  468.20  4660.8  467.37  4703.2  466.54  4759.8  466.41
  4830.5  465.47  4844.6  465.57  4901.2  464.57  4915.4  464.74  4971.9  463.89
  5008.5  463.85  5008.7  463.35  5012.3  463.35  5012.6  463.85  5041.4  464.23
  5051.8  463.91  5093.0  465.67  5134.2  468.20  5224.4  473.01  5257.9  474.31
  5278.5  475.63  5288.8  476.65  5299.1  476.93  5371.3  481.54  5412.5  484.68
#Mann=3,-1,0
  4434.5    0.12       0  5008.5    0.05       0  5012.6    0.12       0
Bank Sta=5008.5,5012.6
Exp/Cntr=0.3,0.1

Type RM Length L Ch R = 1,8139,441,441,441
BEGIN DESCRIPTION:
SANDIES TRIBUTARY 2 18.0
END DESCRIPTION:
XS GIS Cut Line= 3
      2347574.99     13705975.00      2347175.00     13705775.00
      2346575.01     13705775.00
#Sta/Elev= 30
  4557.1  499.24  4571.1  499.57  4587.8  496.58  4593.4  496.06  4610.2  492.36
  4615.8  491.65  4632.6  486.86  4654.9  481.57  4677.3  478.59  4722.0  474.34
  4727.6  474.53  4736.0  473.15  4758.3  470.78  4839.4  465.35  4878.5  463.78
  4892.5  462.65  4979.7  461.29  4980.0  460.79  4983.8  460.79  4984.2  461.29
  4990.3  461.84  5094.3  462.10  5134.3  463.62  5174.3  464.46  5254.3  464.92
  5304.3  466.06  5334.3  468.62  5394.3  475.34  5524.3  485.28  5604.3  490.57
#Mann=3,-1,0
  4557.1    0.12       0  4979.7    0.05       0  4984.2    0.12       0
Bank Sta=4979.7,4984.2
Exp/Cntr=0.3,0.1

Type RM Length L Ch R = 1,7698,449,449,449
BEGIN DESCRIPTION:
SANDIES TRIBUTARY 2 17.0
END DESCRIPTION:
XS GIS Cut Line= 3
      2347625.00     13705825.00      2347425.00     13705425.00
      2347125.01     13705025.01
#Sta/Elev= 30
  4558.7  488.58  4595.0  484.56  4611.8  483.46  4617.4  481.76  4648.1  477.76
  4701.3  474.19  4729.2  471.53  4768.3  469.13  4796.3  466.54  4880.1  462.07
  4885.7  461.26  4958.9  458.47  4959.2  457.97  4963.1  457.97  4963.4  458.47
  5013.2  459.04  5055.9  461.51  5063.2  462.78  5092.4  465.09  5098.6  464.51
  5142.4  467.06  5213.2  472.18  5234.0  474.72  5263.2  476.67  5284.0  479.19
  5348.6  484.73  5413.2  494.71  5463.2  501.45  5477.8  502.73  5505.9  503.25
#Mann=3,-1,0
  4558.7    0.12       0  4958.9    0.05       0  4963.4    0.12       0
Bank Sta=4958.9,4963.4
Exp/Cntr=0.3,0.1

Type RM Length L Ch R = 1,7249,416,416,416
BEGIN DESCRIPTION:
SANDIES TRIBUTARY 2 16.0
END DESCRIPTION:
XS GIS Cut Line= 3
      2348175.00     13705575.00      2347775.00     13705175.00
      2347524.99     13704774.99
#Sta/Elev= 30
  4428.7  478.08  4471.1  473.92  4534.8  470.38  4556.0  468.06  4655.0  463.58
  4711.5  461.76  4725.7  461.90  4768.1  460.64  4796.4  459.23  4867.1  457.62
  4966.1  456.06  4999.8  456.01  5000.1  455.51  5004.0  455.51  5004.4  456.01
  5007.9  456.43  5053.3  456.52  5111.7  458.20  5117.6  458.91  5160.1  461.16
  5242.0  464.55  5277.4  466.56  5306.3  468.78  5342.9  472.52  5400.6  476.64
  5430.7  480.42  5437.2  482.16  5443.1  482.37  5463.1  485.30  5466.1  485.30
#Mann=3,-1,0
  4428.7    0.12       0  4999.8    0.05       0  5004.4    0.12       0
Bank Sta=4999.8,5004.4
Exp/Cntr=0.3,0.1

Type RM Length L Ch R = 1,6833,493,493,493
BEGIN DESCRIPTION:
SANDIES TRIBUTARY 2 15.0
END DESCRIPTION:
XS GIS Cut Line= 3
      2348425.02     13705275.02      2348025.00     13704875.00
      2347625.01     13704525.01
#Sta/Elev= 30
  4439.1  473.61  4481.6  471.80  4538.1  467.77  4637.1  463.43  4651.3  462.21
  4665.4  461.93  4764.4  456.74  4835.1  454.39  4849.2  455.28  4863.4  454.27
  4931.8  453.52  4932.1  453.02  4936.1  453.02  4936.4  453.52  5011.9  453.70
  5061.3  454.95  5083.1  456.76  5089.8  456.30  5104.0  456.87  5139.1  458.74
  5146.7  459.92  5189.4  461.66  5295.7  468.78  5330.8  472.01  5394.4  476.69
  5430.0  480.47  5458.0  484.27  5472.3  485.16  5494.1  487.79  5536.3  489.80
#Mann=3,-1,0
  4439.1    0.12       0  4931.8    0.05       0  4936.4    0.12       0
Bank Sta=4931.8,4936.4
Exp/Cntr=0.3,0.1

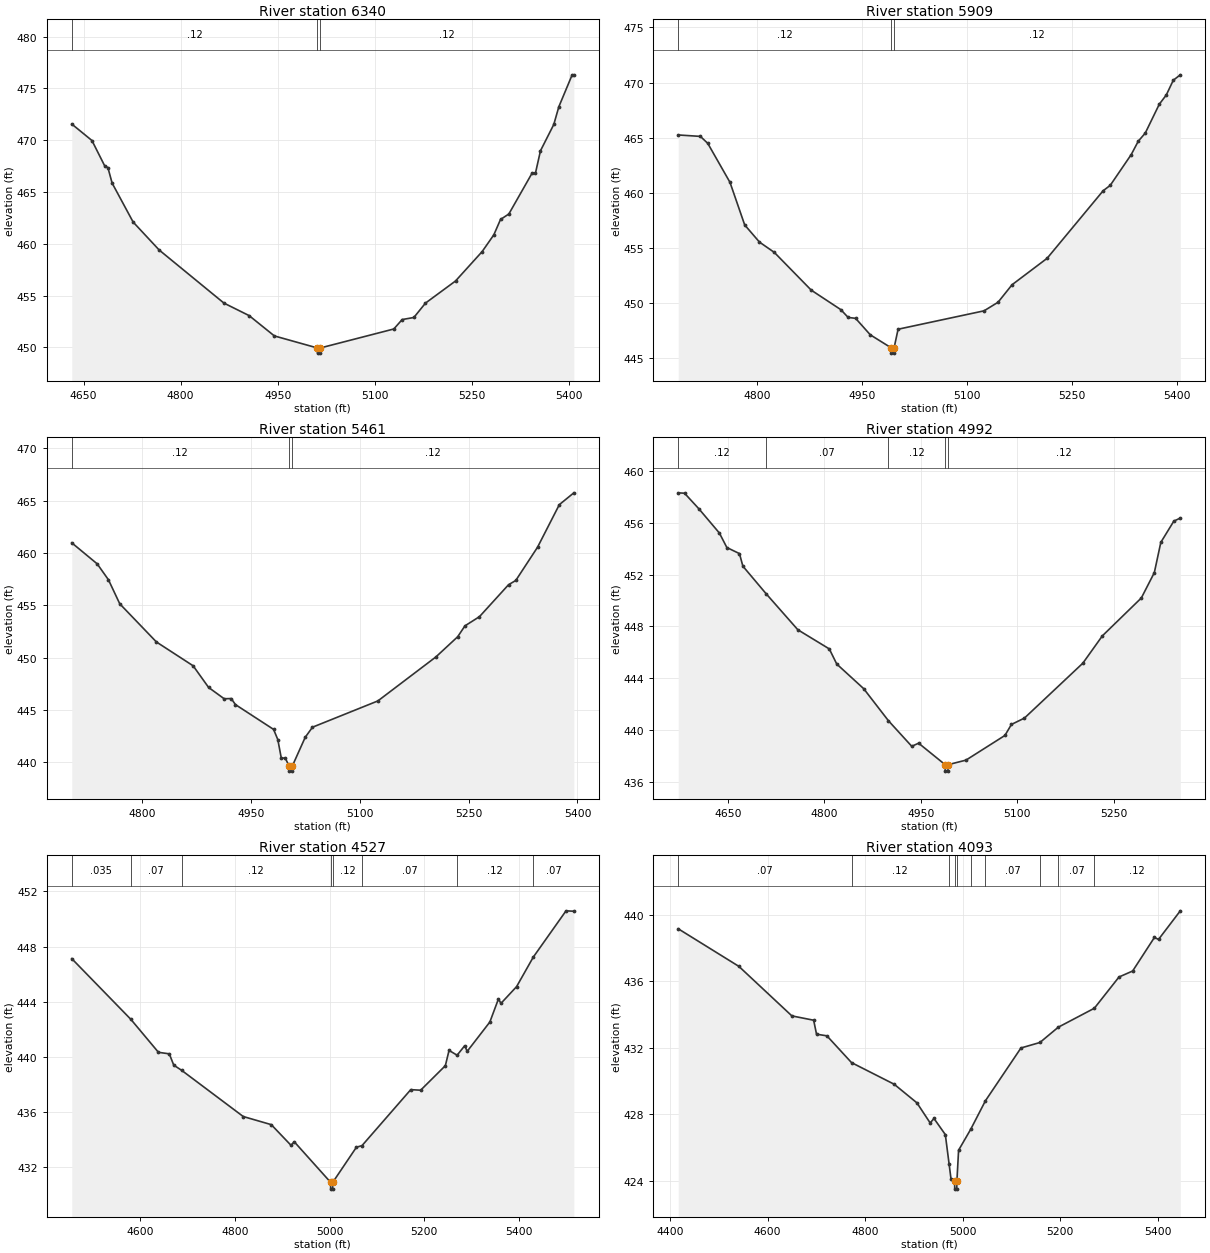
Type RM Length L Ch R = 1,6340,431,431,431
BEGIN DESCRIPTION:
SANDIES TRIBUTARY 2 14.0
END DESCRIPTION:
XS GIS Cut Line= 3
      2348725.04     13704625.01      2348375.00     13704525.00
      2347974.96     13704424.99
#Sta/Elev= 30
  4631.6  471.56  4662.8  469.97  4682.3  467.55  4687.5  467.35  4694.0  465.86
  4726.5  462.10  4766.8  459.40  4866.9  454.28  4905.9  453.07  4944.9  451.11
  5011.3  449.95  5011.7  449.45  5015.7  449.45  5016.0  449.95  5129.6  451.78
  5142.5  452.69  5160.6  452.89  5178.6  454.28  5225.0  456.41  5266.2  459.25
  5284.3  460.87  5294.6  462.35  5307.5  462.88  5343.5  466.83  5348.7  466.84
  5356.4  468.98  5377.0  471.52  5384.8  473.23  5405.4  476.31  5408.0  476.31
#Mann=3,-1,0
  4631.6    0.12       0  5011.3    0.05       0  5016.0    0.12       0
Bank Sta=5011.3,5016
Exp/Cntr=0.3,0.1

Type RM Length L Ch R = 1,5909,448,448,448
BEGIN DESCRIPTION:
SANDIES TRIBUTARY 2 13.0
END DESCRIPTION:
XS GIS Cut Line= 3
      2348774.98     13704224.99      2348475.00     13704125.00
      2348075.01     13704125.00
#Sta/Elev= 30
  4688.0  465.24  4719.6  465.11  4730.1  464.48  4761.8  460.94  4782.8  457.07
  4803.9  455.51  4825.0  454.58  4877.7  451.15  4919.9  449.38  4930.4  448.67
  4941.0  448.59  4962.0  447.09  4991.3  445.93  4991.7  445.43  4995.7  445.43
  4996.0  445.93  5001.6  447.60  5124.2  449.27  5144.2  450.05  5164.2  451.64
  5214.2  454.04  5294.2  460.18  5304.2  460.66  5334.2  463.46  5344.2  464.67
  5354.2  465.41  5374.2  468.03  5384.2  468.87  5394.2  470.21  5404.2  470.70
#Mann=3,-1,0
  4688.0    0.12       0  4991.3    0.05       0  4996.0    0.12       0
Bank Sta=4991.3,4996
Exp/Cntr=0.3,0.1

Type RM Length L Ch R = 1,5461,469,469,469
BEGIN DESCRIPTION:
SANDIES TRIBUTARY 2 12.0
END DESCRIPTION:
XS GIS Cut Line= 3
      2348875.01     13703875.00      2348625.00     13703725.00
      2348224.96     13703725.00
#Sta/Elev= 30
  4703.4  460.97  4738.4  458.96  4753.9  457.44  4769.5  455.14  4820.0  451.49
  4870.6  449.21  4891.9  447.14  4913.3  446.06  4923.0  446.08  4928.9  445.50
  4981.4  443.13  4987.2  442.16  4992.0  440.39  4997.5  440.39  5002.6  439.64
  5003.0  439.14  5007.0  439.14  5007.3  439.64  5025.0  442.38  5035.0  443.34
  5125.0  445.85  5205.0  450.06  5235.0  451.99  5245.0  453.03  5265.0  453.91
  5305.0  456.96  5315.0  457.37  5345.0  460.55  5375.0  464.62  5395.0  465.75
#Mann=3,-1,0
  4703.4    0.12       0  5002.6    0.05       0  5007.3    0.12       0
Bank Sta=5002.6,5007.3
Exp/Cntr=0.3,0.1

Type RM Length L Ch R = 1,4992,465,465,465
BEGIN DESCRIPTION:
SANDIES TRIBUTARY 2 11.0
END DESCRIPTION:
XS GIS Cut Line= 3
      2348974.99     13703724.97      2348825.00     13703325.00
      2348475.02     13703375.00
#Sta/Elev= 30
  4572.8  458.33  4582.6  458.30  4604.8  457.10  4636.8  455.22  4648.4  454.10
  4668.0  453.63  4673.3  452.66  4709.4  450.53  4758.8  447.74  4807.7  446.26
  4819.3  445.09  4861.1  443.19  4899.6  440.71  4935.9  438.73  4946.6  438.97
  4987.8  437.31  4988.1  436.81  4992.2  436.81  4992.5  437.31  5020.2  437.66
  5080.8  439.57  5090.9  440.42  5111.1  440.91  5202.0  445.16  5232.3  447.27
  5292.9  450.20  5313.1  452.16  5323.2  454.50  5343.4  456.14  5353.5  456.38
#Mann=5,-1,0
  4572.8    0.12       0  4709.4    0.07       0  4899.6    0.12       0
  4987.8    0.05       0  4992.5    0.12       0
Bank Sta=4987.8,4992.5
Exp/Cntr=0.3,0.1

Type RM Length L Ch R = 1,4527,434,434,434
BEGIN DESCRIPTION:
SANDIES TRIBUTARY 2 10.0
END DESCRIPTION:
XS GIS Cut Line= 3
      2349225.00     13703425.01      2349025.00     13702925.00
      2348525.04     13703074.99
#Sta/Elev= 30
  4455.3  447.12  4580.2  442.71  4638.4  440.32  4661.3  440.21  4670.7  439.39
  4687.5  439.01  4817.5  435.66  4876.7  435.07  4918.4  433.57  4925.2  433.83
  5001.9  430.89  5002.2  430.39  5006.3  430.39  5006.7  430.89  5056.5  433.43
  5068.4  433.55  5171.3  437.61  5192.2  437.57  5244.4  439.35  5252.2  440.46
  5269.2  440.11  5285.3  440.80  5290.5  440.39  5338.4  442.52  5356.6  444.20
  5361.8  443.87  5394.9  445.09  5430.1  447.23  5499.3  450.59  5515.8  450.56
#Mann=8,-1,0
  4455.3   0.035       0  4580.2    0.07       0  4687.5    0.12       0
  5001.9    0.05       0  5006.7    0.12       0  5068.4    0.07       0
  5269.2    0.12       0  5430.1    0.07       0
Bank Sta=5001.9,5006.7
Exp/Cntr=0.3,0.1

Type RM Length L Ch R = 1,4093,452,452,452
BEGIN DESCRIPTION:
SANDIES TRIBUTARY 2 9.0
END DESCRIPTION:
XS GIS Cut Line= 3
      2349424.99     13703024.98      2349125.00     13702525.00
      2348724.99     13702725.01
#Sta/Elev= 30
  4416.5  439.16  4540.9  436.90  4649.7  433.92  4694.4  433.66  4700.3  432.82
  4721.6  432.72  4772.1  431.11  4859.6  429.81  4906.3  428.69  4933.5  427.48
  4941.3  427.75  4964.6  426.78  4972.3  425.02  4976.3  424.10  4983.6  424.00
  4983.9  423.50  4988.0  423.50  4988.4  424.00  4991.8  425.84  5016.7  427.10
  5047.0  428.82  5119.8  431.99  5158.7  432.32  5196.4  433.24  5270.4  434.38
  5321.0  436.26  5349.0  436.62  5393.7  438.64  5402.1  438.52  5446.8  440.24
#Mann=10,-1,0
  4416.5    0.07       0  4772.1    0.12       0  4972.3    0.07       0
  4983.6    0.05       0  4988.4    0.07       0  5016.7    0.12       0
  5047.0    0.07       0  5158.7   0.035       0  5196.4    0.07       0
  5270.4    0.12       0
Bank Sta=4983.6,4988.4
Exp/Cntr=0.3,0.1

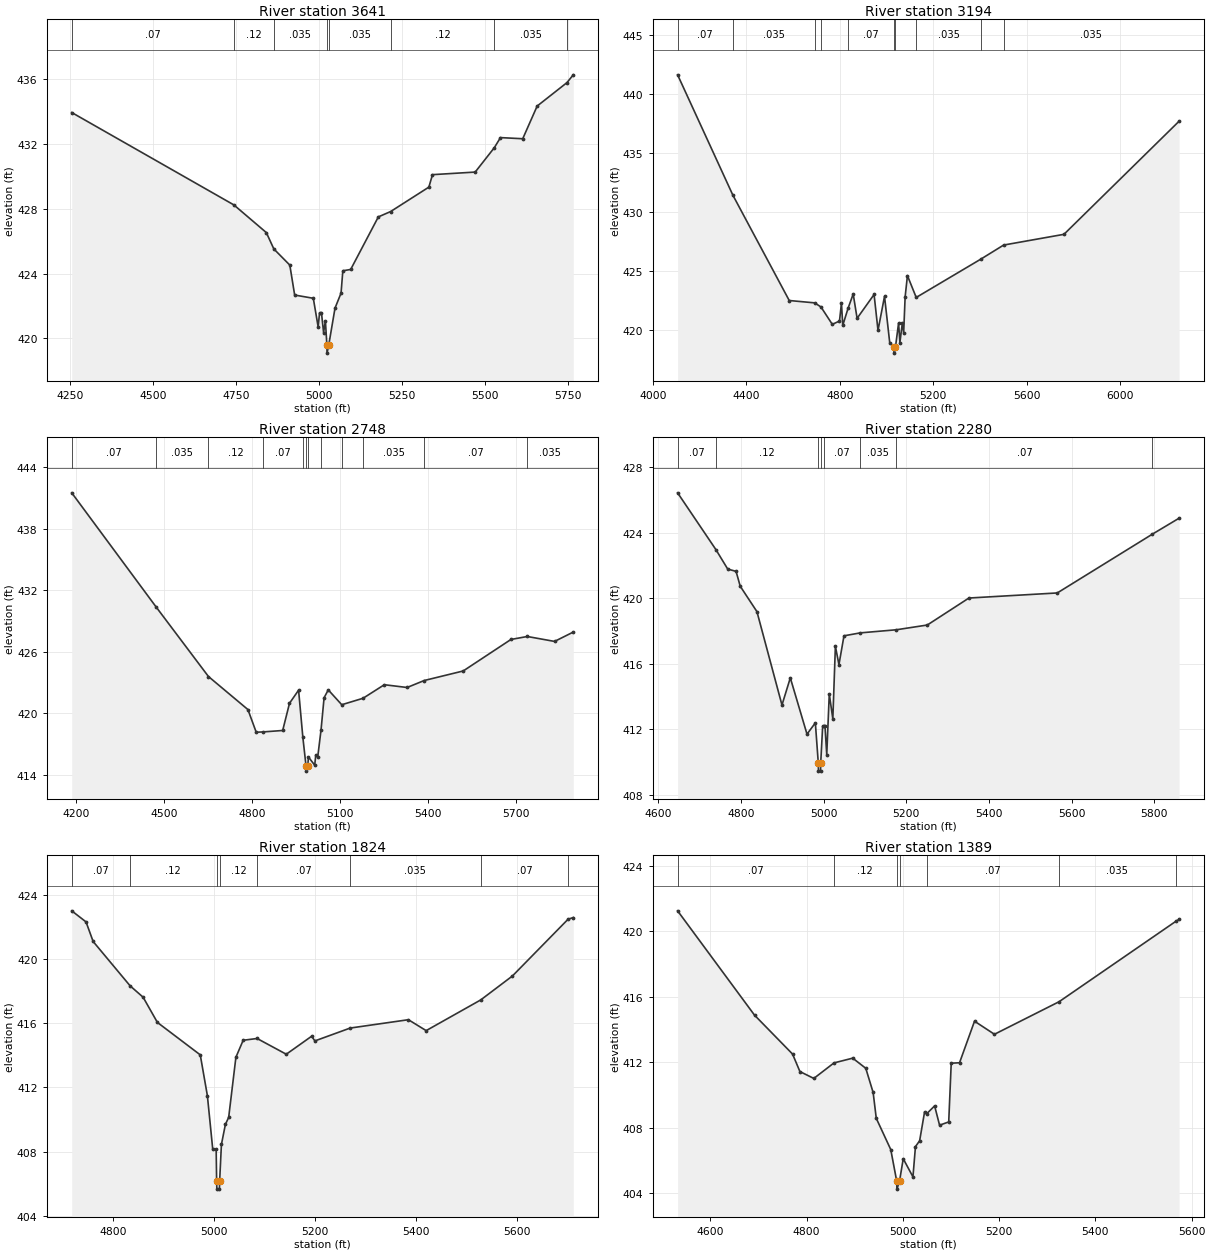
Type RM Length L Ch R = 1,3641,447,447,447
BEGIN DESCRIPTION:
SANDIES TRIBUTARY 2 8.0
END DESCRIPTION:
XS GIS Cut Line= 3
      2349875.01     13702575.01      2349275.00     13702125.00
      2348574.99     13702425.00
#Sta/Elev= 30
  4254.1  433.95  4742.8  428.24  4840.6  426.53  4863.2  425.52  4911.4  424.52
  4926.0  422.67  4982.2  422.47  4996.8  420.70  5001.0  421.57  5006.8  421.57
  5013.2  420.35  5018.6  421.08  5023.1  419.58  5023.5  419.08  5028.7  419.58
  5047.6  421.86  5065.8  422.79  5071.2  424.17  5094.8  424.25  5178.2  427.50
  5215.2  427.83  5330.5  429.34  5341.4  430.11  5470.1  430.27  5527.9  431.78
  5546.3  432.40  5613.4  432.33  5656.9  434.35  5746.8  435.80  5765.7  436.28
#Mann=8,-1,0
  4254.1    0.07       0  4742.8    0.12       0  4863.2   0.035       0
  5023.1   0.035       0  5028.7   0.035       0  5215.2    0.12       0
  5527.9   0.035       0  5746.8    0.12       0
Bank Sta=5023.1,5028.7
Exp/Cntr=0.3,0.1

Type RM Length L Ch R = 1,3194,446,446,446
BEGIN DESCRIPTION:
SANDIES TRIBUTARY 2 7.0
END DESCRIPTION:
XS GIS Cut Line= 3
      2350224.99     13701375.00      2349425.00     13701775.00
      2348325.02     13702374.99
#Sta/Elev= 30
  4105.2  441.59  4342.1  431.38  4583.2  422.46  4692.4  422.26  4719.2  421.91
  4767.6  420.44  4798.4  420.72  4806.8  422.24  4812.4  420.35  4835.3  421.81
  4857.1  423.01  4873.8  420.95  4946.5  422.97  4963.3  419.93  4991.2  422.81
  5013.4  418.90  5032.4  418.50  5032.9  418.00  5038.0  418.50  5051.4  420.55
  5057.1  418.90  5067.5  420.56  5073.2  419.73  5079.4  422.75  5089.3  424.57
  5126.9  422.72  5403.8  425.97  5501.2  427.16  5759.5  428.07  6252.6  437.66
#Mann=10,-1,0
  4105.2    0.07       0  4342.1   0.035       0  4692.4    0.12       0
  4719.2   0.035       0  4835.3    0.07       0  5032.4    0.05       0
  5038.0    0.07       0  5126.9   0.035       0  5403.8    0.07       0
  5501.2   0.035       0
Bank Sta=5032.4,5038
Exp/Cntr=0.3,0.1

Type RM Length L Ch R = 1,2748,468,468,468
BEGIN DESCRIPTION:
SANDIES TRIBUTARY 2 6.0
END DESCRIPTION:
XS GIS Cut Line= 3
      2350174.98     13701225.01      2349375.00     13701425.00
      2348774.99     13702075.01
#Sta/Elev= 30
  4186.0  441.49  4474.0  430.35  4651.9  423.59  4786.4  420.37  4814.7  418.16
  4837.2  418.19  4904.9  418.33  4928.1  420.98  4959.1  422.26  4973.6  417.67
  4984.5  414.87  4985.0  414.37  4990.4  414.87  4992.6  415.75  5014.0  414.95
  5017.7  415.93  5024.5  415.79  5035.6  418.38  5046.0  421.52  5060.2  422.29
  5106.2  420.84  5178.8  421.47  5251.3  422.79  5329.0  422.52  5387.2  423.20
  5520.1  424.13  5682.8  427.20  5738.6  427.49  5831.4  427.01  5895.2  427.92
#Mann=12,-1,0
  4186.0    0.07       0  4474.0   0.035       0  4651.9    0.12       0
  4837.2    0.07       0  4973.6    0.12       0  4984.5    0.05       0
  4990.4    0.12       0  5035.6   0.035       0  5106.2    0.07       0
  5178.8   0.035       0  5387.2    0.07       0  5738.6   0.035       0
Bank Sta=4984.5,4990.4
Exp/Cntr=0.3,0.1

Type RM Length L Ch R = 1,2280,456,456,456
BEGIN DESCRIPTION:
SANDIES TRIBUTARY 2 5.0
END DESCRIPTION:
XS GIS Cut Line= 3
      2349675.03     13700925.00      2349325.00     13700975.00
      2348825.01     13701674.98
#Sta/Elev= 30
  4646.4  426.45  4739.1  422.98  4767.7  421.79  4787.9  421.65  4798.0  420.74
  4838.4  419.19  4899.0  413.48  4919.2  415.14  4959.6  411.70  4979.8  412.39
  4986.9  409.94  4987.4  409.44  4992.3  409.44  4992.8  409.94  4997.5  412.19
  4999.6  412.19  5003.1  412.19  5007.4  410.45  5013.5  414.16  5022.1  412.63
  5028.3  417.07  5036.9  415.95  5049.1  417.71  5088.5  417.89  5175.9  418.08
  5250.7  418.37  5351.5  420.02  5565.3  420.33  5795.2  423.92  5860.2  424.90
#Mann=8,-1,0
  4646.4    0.07       0  4739.1    0.12       0  4986.9    0.05       0
  4992.8    0.12       0  4999.6    0.07       0  5088.5   0.035       0
  5175.9    0.07       0  5795.2   0.035       0
Bank Sta=4986.9,4992.8
Exp/Cntr=0.3,0.1

Type RM Length L Ch R = 1,1824,435,435,435
BEGIN DESCRIPTION:
SANDIES TRIBUTARY 2 4.0
END DESCRIPTION:
XS GIS Cut Line= 3
      2349375.01     13700374.99      2349175.00     13700575.00
      2348724.99     13701125.01
#Sta/Elev= 30
  4717.4  423.00  4745.7  422.31  4759.8  421.09  4833.0  418.33  4858.8  417.62
  4887.1  416.05  4972.0  414.03  4986.1  411.49  4996.7  408.16  5003.5  408.16
  5004.4  406.17  5004.9  405.67  5009.9  405.67  5010.4  406.17  5013.9  408.45
  5021.8  409.70  5028.3  410.14  5042.6  413.88  5057.0  414.94  5084.6  415.05
  5142.4  414.07  5192.6  415.19  5199.1  414.90  5269.0  415.70  5384.3  416.22
  5419.5  415.54  5527.5  417.45  5590.3  418.94  5700.7  422.48  5710.9  422.58
#Mann=8,-1,0
  4717.4    0.07       0  4833.0    0.12       0  5004.4    0.05       0
  5010.4    0.12       0  5084.6    0.07       0  5269.0   0.035       0
  5527.5    0.07       0  5700.7   0.035       0
Bank Sta=5004.4,5010.4
Exp/Cntr=0.3,0.1

Type RM Length L Ch R = 1,1389,416,416,416
BEGIN DESCRIPTION:
SANDIES TRIBUTARY 2 3.0
END DESCRIPTION:
XS GIS Cut Line= 3
      2349224.97     13700175.02      2348825.00     13700425.00
      2348674.99     13700975.05
#Sta/Elev= 30
  4532.2  421.26  4692.0  414.88  4771.0  412.50  4786.3  411.43  4815.2  411.01
  4857.1  411.96  4896.0  412.25  4923.1  411.63  4938.4  410.15  4944.9  408.57
  4975.0  406.66  4987.3  404.74  4987.8  404.24  4993.3  404.74  5000.9  406.10
  5021.1  404.99  5026.3  406.84  5035.0  407.20  5045.3  408.97  5050.0  408.86
  5066.1  409.33  5076.4  408.15  5095.4  408.35  5100.6  411.94  5117.9  411.97
  5149.0  414.51  5190.4  413.71  5324.6  415.70  5566.8  420.61  5574.0  420.74
#Mann=7,-1,0
  4532.2    0.07       0  4857.1    0.12       0  4987.3    0.05       0
  4993.3    0.12       0  5050.0    0.07       0  5324.6   0.035       0
  5566.8    0.07       0
Bank Sta=4987.3,4993.3
Exp/Cntr=0.3,0.1

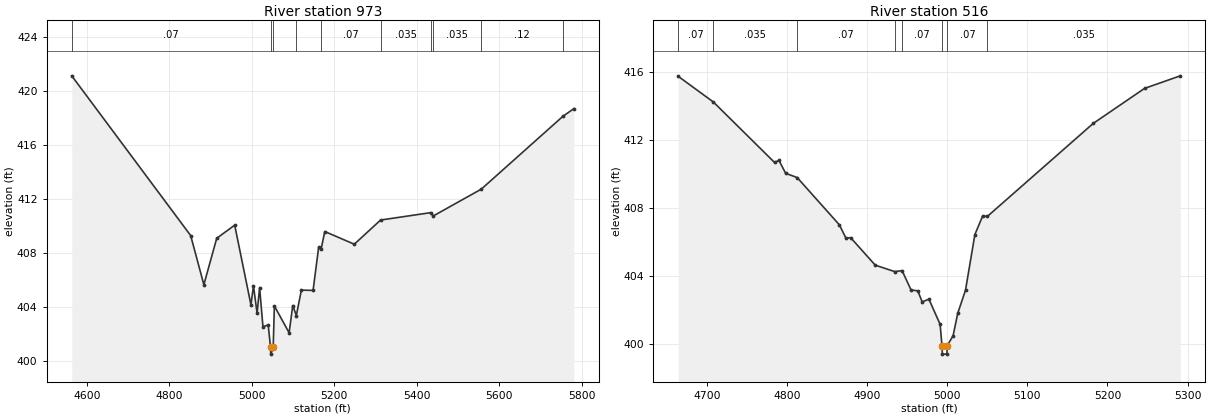
Type RM Length L Ch R = 1,973,457,457,457
BEGIN DESCRIPTION:
SANDIES TRIBUTARY 2 2.0
END DESCRIPTION:
XS GIS Cut Line= 3
      2349125.01     13699925.00      2348725.00     13700075.00
      2348074.99     13700525.01
#Sta/Elev= 30
  4563.4  421.09  4851.8  409.26  4883.8  405.62  4915.0  409.06  4958.6  410.03
  4998.0  404.13  5004.1  405.54  5012.9  403.51  5019.0  405.41  5027.1  402.51
  5039.9  402.64  5045.5  400.98  5046.0  400.48  5052.0  400.98  5054.8  404.05
  5090.6  402.06  5099.4  404.08  5108.1  403.34  5120.3  405.22  5148.7  405.20
  5162.2  408.39  5168.0  408.23  5177.1  409.56  5248.7  408.62  5312.4  410.41
  5434.6  410.96  5440.1  410.71  5556.8  412.70  5754.6  418.09  5781.2  418.66
#Mann=10,-1,0
  4563.4    0.07       0  5045.5    0.05       0  5052.0    0.07       0
  5108.1    0.12       0  5168.0    0.07       0  5312.4   0.035       0
  5434.6    0.12       0  5440.1   0.035       0  5556.8    0.12       0
  5754.6    0.07       0
Bank Sta=5045.5,5052
Exp/Cntr=0.3,0.1

Type RM Length L Ch R = 1,516,0,0,0
BEGIN DESCRIPTION:
SANDIES TRIBUTARY 2 1.0
END DESCRIPTION:
XS GIS Cut Line= 3
      2349024.99     13699774.99      2348725.00     13699625.00
      2348475.04     13699774.98
#Sta/Elev= 30
  4664.1  415.75  4708.0  414.24  4784.3  410.69  4789.9  410.81  4798.2  410.05
  4812.6  409.80  4865.3  407.02  4873.7  406.22  4879.3  406.27  4910.1  404.65
  4934.5  404.27  4943.6  404.33  4954.8  403.19  4963.2  403.14  4968.7  402.49
  4977.1  402.65  4991.1  401.17  4993.4  399.92  4993.9  399.42  4999.5  399.42
  5000.0  399.92  5007.3  400.50  5013.1  401.82  5022.8  403.18  5034.5  406.45
  5044.2  407.54  5050.2  407.52  5182.2  412.98  5246.3  415.04  5291.0  415.78
#Mann=8,-1,0
  4664.1    0.07       0  4708.0   0.035       0  4812.6    0.07       0
  4934.5   0.035       0  4943.6    0.07       0  4993.4    0.05       0
  5000.0    0.07       0  5050.2   0.035       0
Bank Sta=4993.4,5000
Exp/Cntr=0.3,0.1

Chan Stop Cuts=-1