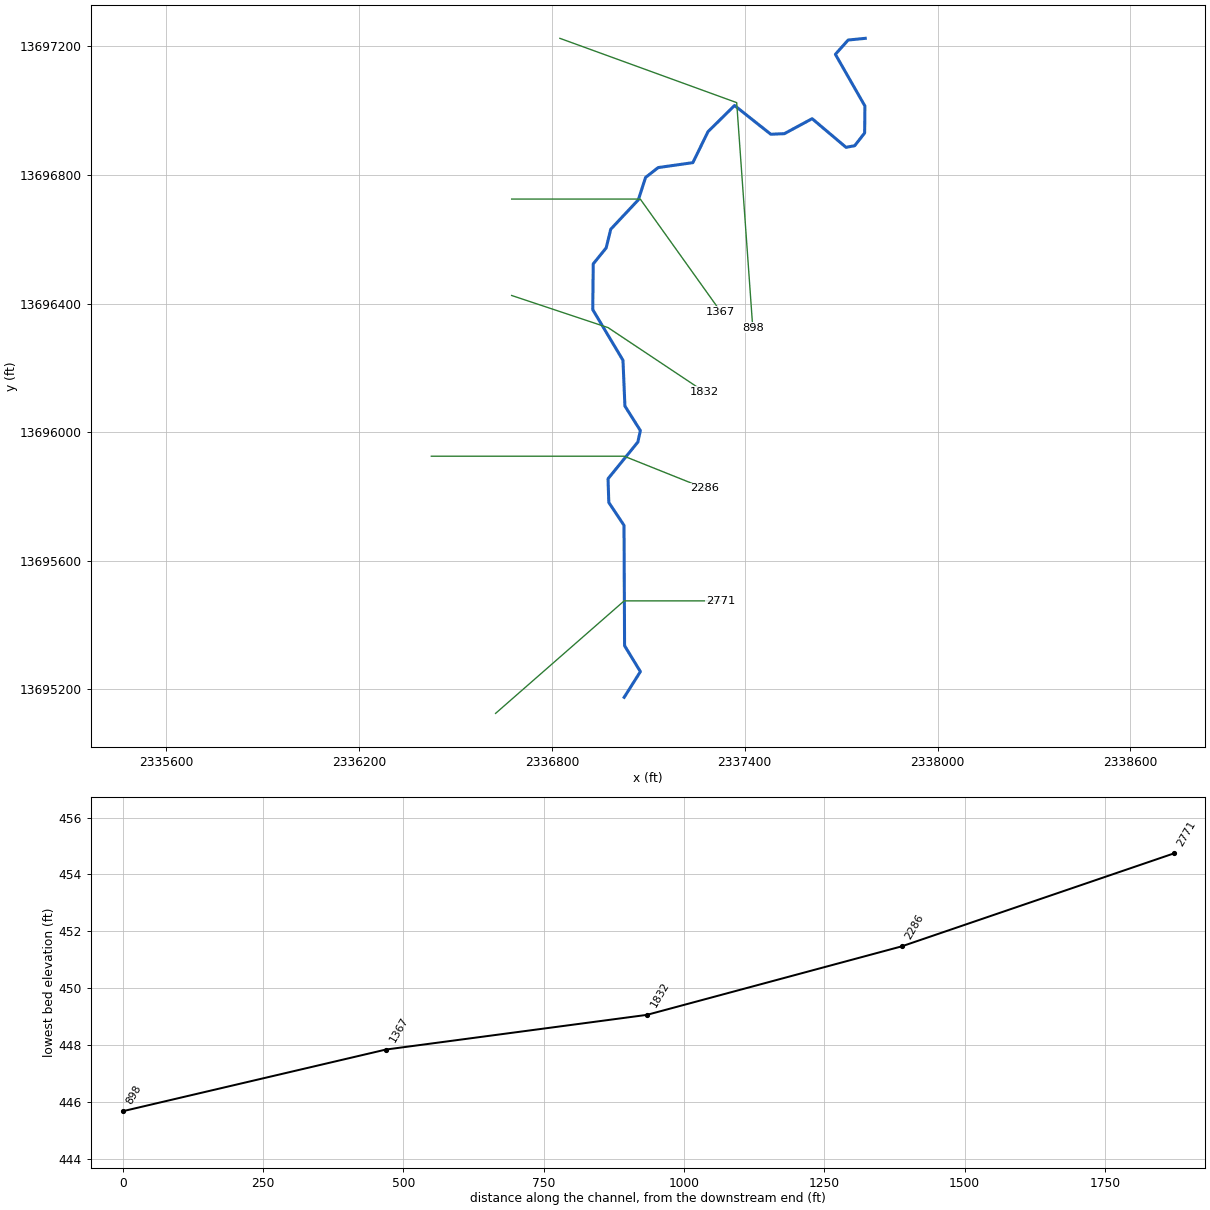
--- SANDIES TRIBUTARY 4.prj (project) ---

Proj Title=SANDIES TRIBUTARY 4 Base Level Engineering
Current Plan=p01
Default Exp/Contr=0.3,0.1
English Units
Geom File=g01
Flow File=f01
Plan File=p01
BEGIN DESCRIPTION:
SANDIES TRIBUTARY 4
END DESCRIPTION:

--- SANDIES TRIBUTARY 4.p01 (plan) ---

Plan Title=Multiple Run
Short Identifier=Multiple
Geom File=g01
Flow File=f01
Subcritical Flow
K Sum by GR= 0
Std Step Tol= 0.01
Critical Tol= 0.01
Num of Std Step Trials= 20
Max Error Tol= 0.3
Flow Tol Ratio= 0.001
Split Flow NTrial= 30
Split Flow Tol= 0.02
Split Flow Ratio= 0.02
Log Output Level= 0
Friction Slope Method= 1
Unsteady Friction Slope Method= 2
Unsteady Bridges Friction Slope Method= 1
Parabolic Critical Depth
Global Vel Dist=  1 , 1 , 1
Global Log Level= 0
CheckData=True
Encroach Param= -1, 0, 0, 0
BEGIN DESCRIPTION:
Multiple Run
END DESCRIPTION:

--- SANDIES TRIBUTARY 4.f01 (steady flow) ---

Flow Title=Multiple
Number of Profiles=7
Profile Names=10-year,25-year,50-year,1pct_min,100-year,1pct_plu,500-year
River Rch & RM= SANDIES TRIBUTAR,Reach-1,2771
     730    1194    1617    1060    2115    4219    3586
Boundary for River Rch & Prof#=SANDIES TRIBUTAR,Reach-1,1
Up Type=0
Dn Type=3
Dn Slope=0.005
Boundary for River Rch & Prof#=SANDIES TRIBUTAR,Reach-1,2
Up Type=0
Dn Type=3
Dn Slope=0.005
Boundary for River Rch & Prof#=SANDIES TRIBUTAR,Reach-1,3
Up Type=0
Dn Type=3
Dn Slope=0.005
Boundary for River Rch & Prof#=SANDIES TRIBUTAR,Reach-1,4
Up Type=0
Dn Type=3
Dn Slope=0.005
Boundary for River Rch & Prof#=SANDIES TRIBUTAR,Reach-1,5
Up Type=0
Dn Type=3
Dn Slope=0.005
Boundary for River Rch & Prof#=SANDIES TRIBUTAR,Reach-1,6
Up Type=0
Dn Type=3
Dn Slope=0.005
Boundary for River Rch & Prof#=SANDIES TRIBUTAR,Reach-1,7
Up Type=0
Dn Type=3
Dn Slope=0.005

--- SANDIES TRIBUTARY 4.g01 (geometry) ---

Geom Title=Existing Conditions

River Reach=SANDIES TRIBUTAR,Reach-1
Reach XY= 30
      2337025.00     13695175.00      2337075.44     13695254.89
      2337026.23     13695335.49      2337024.48     13695709.78
      2336977.16     13695780.98      2336974.79     13695854.95
      2337067.50     13695968.95      2337075.36     13696004.79
      2337027.30     13696080.93      2337021.24     13696223.44
      2336927.23     13696380.93      2336928.74     13696523.44
      2336968.86     13696572.83      2336983.16     13696631.05
      2337069.12     13696722.74      2337091.46     13696792.13
      2337130.71     13696822.92      2337238.65     13696838.26
      2337285.79     13696934.71      2337368.31     13697016.04
      2337481.04     13696926.64      2337523.26     13696928.37
      2337609.66     13696975.03      2337715.16     13696885.92
      2337742.14     13696891.01      2337773.04     13696930.48
      2337773.92     13697014.44      2337682.05     13697175.26
      2337721.65     13697219.70      2337775.00     13697225.00

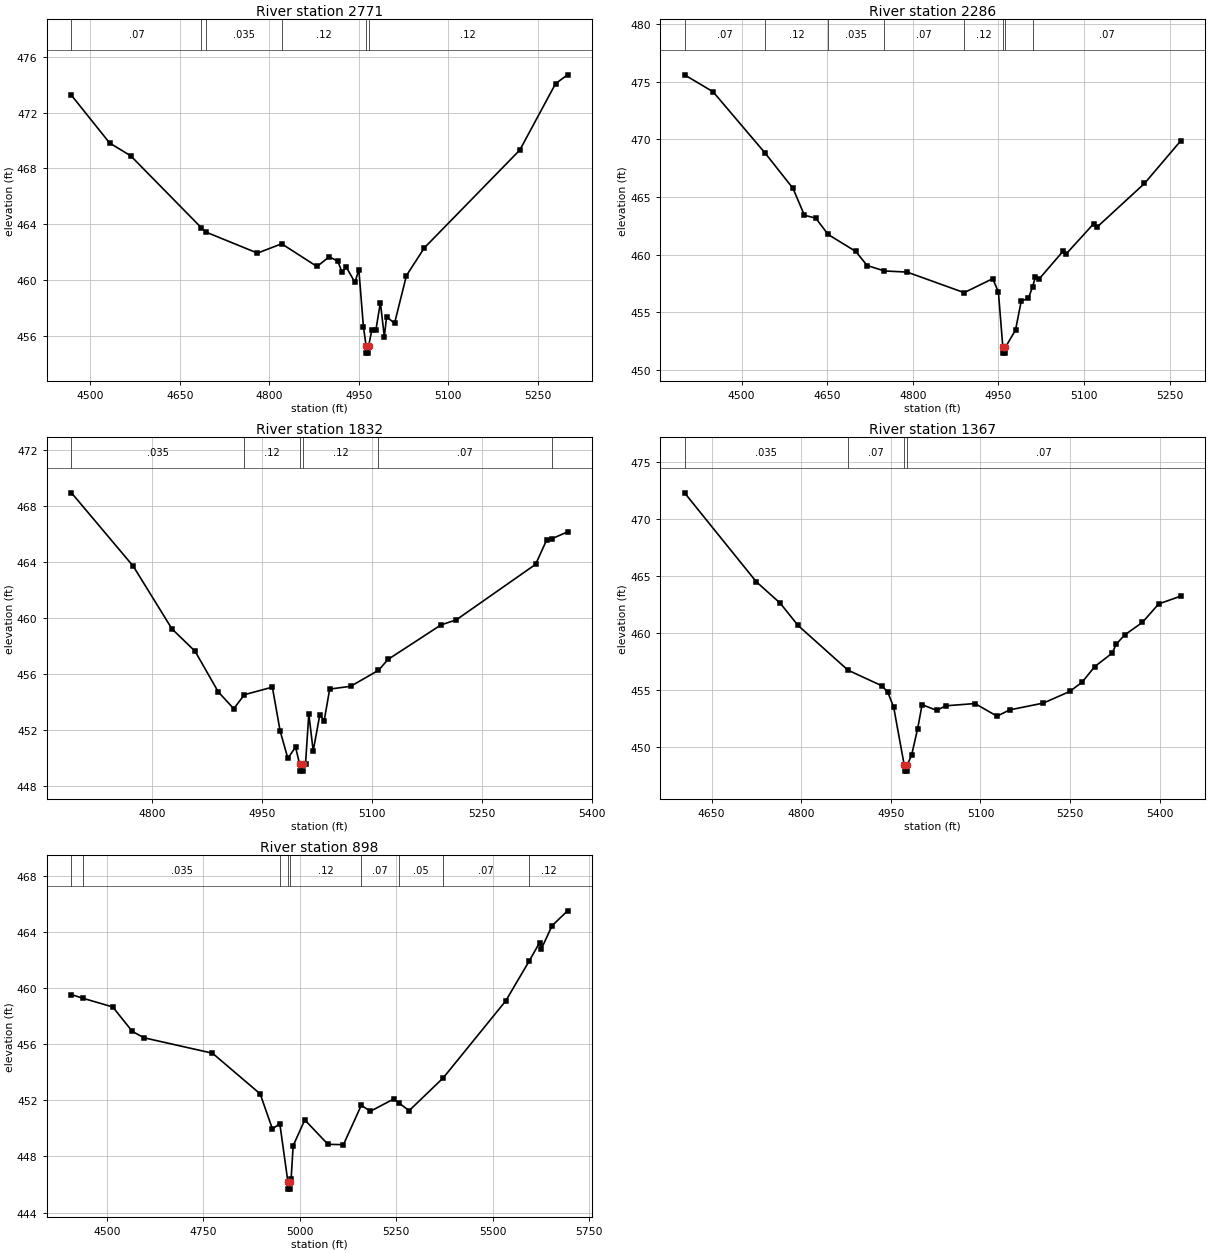
Type RM Length L Ch R = 1,2771,485,485,485
BEGIN DESCRIPTION:
SANDIES TRIBUTARY 4 5.0
END DESCRIPTION:
XS GIS Cut Line= 3
      2336624.99     13695124.99      2337025.00     13695475.00
      2337324.97     13695475.00
#Sta/Elev= 30
  4468.5  473.25  4532.6  469.82  4567.7  468.91  4686.0  463.75  4693.3  463.44
  4780.3  461.92  4820.8  462.59  4880.0  460.96  4900.8  461.66  4915.1  461.33
  4921.7  460.57  4929.3  460.90  4943.6  459.82  4950.2  460.73  4957.8  456.65
  4962.4  455.24  4962.6  454.74  4966.2  454.74  4966.5  455.24  4972.0  456.41
  4978.7  456.40  4986.3  458.36  4992.9  455.91  4996.7  457.36  5010.0  456.88
  5030.0  460.31  5060.0  462.30  5220.0  469.32  5280.0  474.09  5300.0  474.72
#Mann=6,-1,0
  4468.5    0.07       0  4686.0    0.12       0  4693.3   0.035       0
  4820.8    0.12       0  4962.4    0.05       0  4966.5    0.12       0
Bank Sta=4962.4,4966.5
Exp/Cntr=0.3,0.1

Type RM Length L Ch R = 1,2286,454,454,454
BEGIN DESCRIPTION:
SANDIES TRIBUTARY 4 4.0
END DESCRIPTION:
XS GIS Cut Line= 3
      2336425.00     13695925.00      2337025.00     13695925.00
      2337275.04     13695824.98
#Sta/Elev= 30
  4400.0  475.58  4450.0  474.11  4541.4  468.79  4590.0  465.75  4610.0  463.42
  4630.0  463.16  4651.6  461.75  4700.0  460.28  4720.0  459.06  4750.1  458.59
  4790.0  458.49  4890.0  456.71  4940.0  457.92  4950.0  456.77  4957.8  451.97
  4958.1  451.47  4961.9  451.47  4962.2  451.97  4980.0  453.47  4990.0  455.98
  5002.7  456.23  5010.0  457.24  5014.8  458.05  5021.5  457.90  5063.3  460.30
  5068.7  460.06  5117.1  462.69  5122.5  462.37  5206.0  466.17  5269.3  469.85
#Mann=8,-1,0
  4400.0    0.07       0  4541.4    0.12       0  4651.6   0.035       0
  4750.1    0.07       0  4890.0    0.12       0  4957.8    0.05       0
  4962.2    0.12       0  5010.0    0.07       0
Bank Sta=4957.8,4962.2
Exp/Cntr=0.3,0.1

Type RM Length L Ch R = 1,1832,465,465,465
BEGIN DESCRIPTION:
SANDIES TRIBUTARY 4 3.0
END DESCRIPTION:
XS GIS Cut Line= 3
      2336674.97     13696425.01      2336975.00     13696325.00
      2337274.99     13696125.01
#Sta/Elev= 30
  4690.1  468.94  4774.5  463.69  4827.2  459.22  4858.8  457.62  4890.4  454.72
  4911.5  453.52  4926.1  454.52  4964.2  455.06  4974.7  451.95  4985.3  449.97
  4995.8  450.78  5001.4  449.56  5001.8  449.06  5005.7  449.06  5006.0  449.56
  5009.4  449.56  5013.9  453.15  5019.9  450.50  5028.9  453.08  5034.9  452.67
  5042.4  454.92  5071.0  455.12  5108.9  456.26  5122.0  457.04  5194.1  459.50
  5215.2  459.87  5323.3  463.83  5338.4  465.57  5345.5  465.66  5366.9  466.15
#Mann=6,-1,0
  4690.1   0.035       0  4926.1    0.12       0  5001.4    0.05       0
  5006.0    0.12       0  5108.9    0.07       0  5345.5    0.12       0
Bank Sta=5001.4,5006
Exp/Cntr=0.3,0.1

Type RM Length L Ch R = 1,1367,469,469,469
BEGIN DESCRIPTION:
SANDIES TRIBUTARY 4 2.0
END DESCRIPTION:
XS GIS Cut Line= 3
      2336675.00     13696725.00      2337075.00     13696725.00
      2337324.99     13696375.02
#Sta/Elev= 30
  4604.8  472.26  4724.8  464.46  4764.8  462.58  4794.8  460.62  4878.3  456.70
  4934.8  455.33  4944.8  454.78  4954.8  453.44  4972.5  448.34  4972.9  447.84
  4976.8  447.84  4977.1  448.34  4984.8  449.25  4994.8  451.55  5002.3  453.67
  5026.9  453.17  5041.7  453.57  5090.8  453.77  5127.7  452.66  5148.6  453.21
  5205.1  453.81  5249.4  454.83  5270.2  455.65  5291.1  457.01  5320.6  458.20
  5326.8  458.96  5341.5  459.80  5371.0  460.89  5398.1  462.51  5434.9  463.19
#Mann=4,-1,0
  4604.8   0.035       0  4878.3    0.07       0  4972.5    0.05       0
  4977.1    0.07       0
Bank Sta=4972.5,4977.1
Exp/Cntr=0.3,0.1

Type RM Length L Ch R = 1,898,0,0,0
BEGIN DESCRIPTION:
SANDIES TRIBUTARY 4 1.0
END DESCRIPTION:
XS GIS Cut Line= 3
      2336825.01     13697224.99      2337375.00     13697025.00
      2337425.00     13696325.00
#Sta/Elev= 30
  4407.6  459.55  4438.7  459.28  4514.7  458.67  4565.2  456.93  4595.8  456.47
  4773.4  455.37  4897.1  452.47  4929.0  449.96  4948.1  450.35  4969.2  446.17
  4969.5  445.67  4973.5  445.67  4973.8  446.17  4977.5  446.42  4982.8  448.77
  5012.9  450.61  5073.0  448.87  5113.1  448.84  5159.5  451.65  5183.3  451.23
  5243.5  452.10  5258.0  451.80  5283.6  451.27  5371.8  453.60  5534.2  459.10
  5595.8  461.98  5621.9  463.25  5626.9  462.83  5654.5  464.47  5694.6  465.53
#Mann=9,-1,0
  4407.6    0.05       0  4438.7   0.035       0  4948.1    0.12       0
  4969.2    0.05       0  4973.8    0.12       0  5159.5    0.07       0
  5258.0    0.05       0  5371.8    0.07       0  5595.8    0.12       0
Bank Sta=4969.2,4973.8
Exp/Cntr=0.3,0.1

Chan Stop Cuts=-1