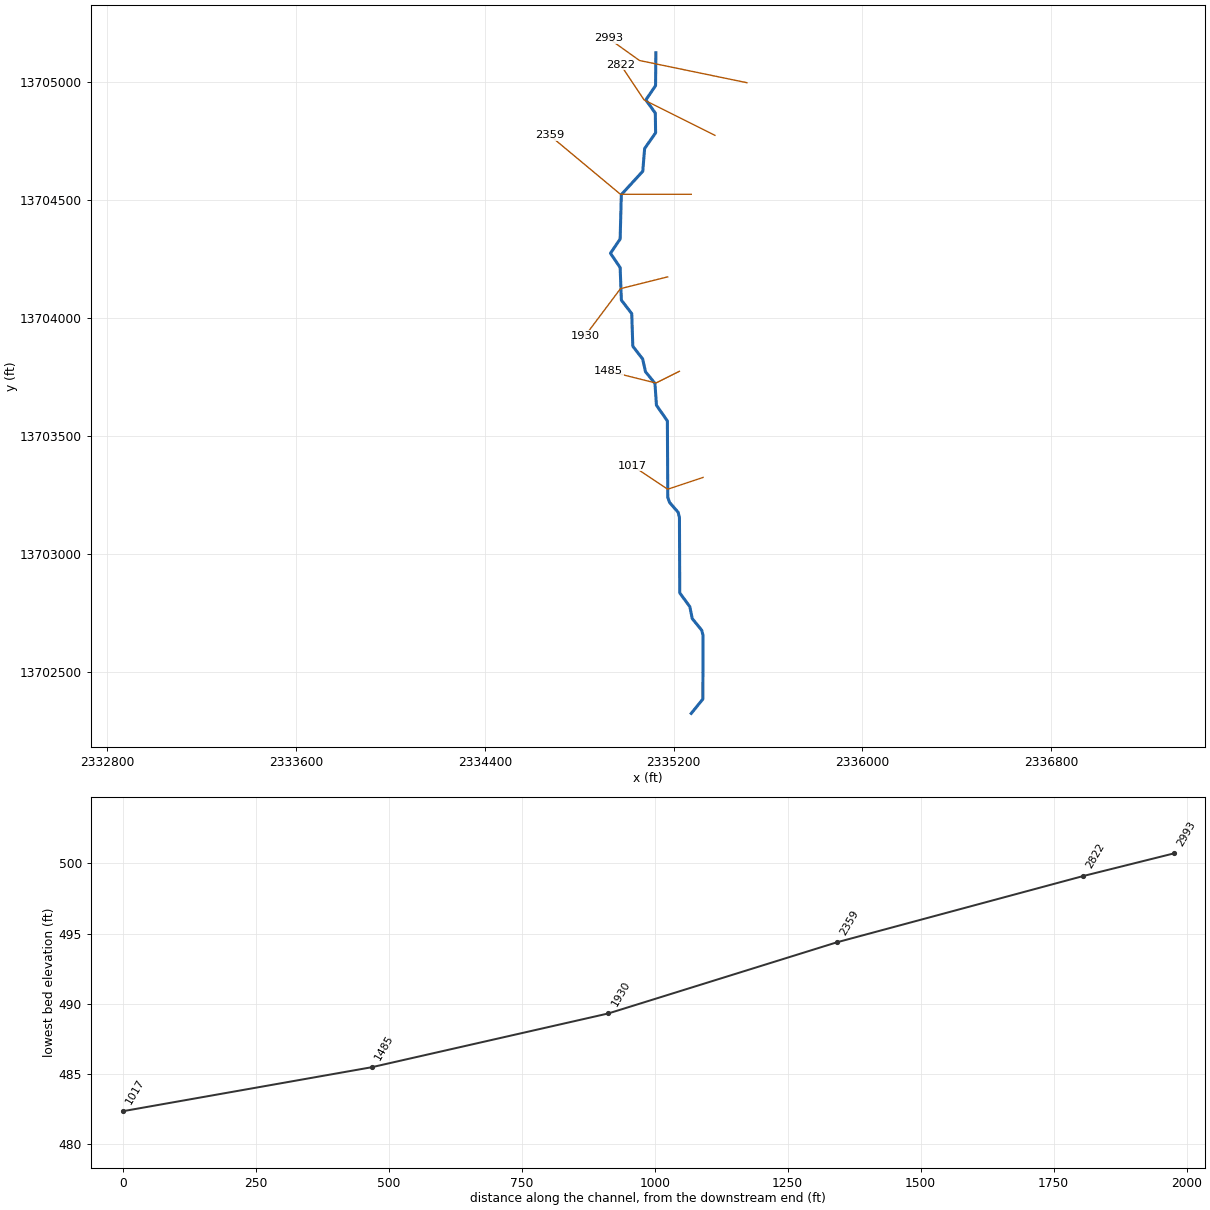
--- SANDIES TRIBUTARY 6.prj (project) ---

Proj Title=SANDIES TRIBUTARY 6 Base Level Engineering
Current Plan=p01
Default Exp/Contr=0.3,0.1
English Units
Geom File=g01
Flow File=f01
Plan File=p01
BEGIN DESCRIPTION:
SANDIES TRIBUTARY 6
END DESCRIPTION:

--- SANDIES TRIBUTARY 6.p01 (plan) ---

Plan Title=Multiple Run
Short Identifier=Multiple
Geom File=g01
Flow File=f01
Subcritical Flow
K Sum by GR= 0
Std Step Tol= 0.01
Critical Tol= 0.01
Num of Std Step Trials= 20
Max Error Tol= 0.3
Flow Tol Ratio= 0.001
Split Flow NTrial= 30
Split Flow Tol= 0.02
Split Flow Ratio= 0.02
Log Output Level= 0
Friction Slope Method= 1
Unsteady Friction Slope Method= 2
Unsteady Bridges Friction Slope Method= 1
Parabolic Critical Depth
Global Vel Dist=  1 , 1 , 1
Global Log Level= 0
CheckData=True
Encroach Param= -1, 0, 0, 0
BEGIN DESCRIPTION:
Multiple Run
END DESCRIPTION:

--- SANDIES TRIBUTARY 6.f01 (steady flow) ---

Flow Title=Multiple
Number of Profiles=7
Profile Names=10-year,25-year,50-year,1pct_min,100-year,1pct_plu,500-year
River Rch & RM= SANDIES TRIBUTAR,Reach-1,2993
     307     481     633     405     808    1613    1304
Boundary for River Rch & Prof#=SANDIES TRIBUTAR,Reach-1,1
Up Type=0
Dn Type=3
Dn Slope=0.005
Boundary for River Rch & Prof#=SANDIES TRIBUTAR,Reach-1,2
Up Type=0
Dn Type=3
Dn Slope=0.005
Boundary for River Rch & Prof#=SANDIES TRIBUTAR,Reach-1,3
Up Type=0
Dn Type=3
Dn Slope=0.005
Boundary for River Rch & Prof#=SANDIES TRIBUTAR,Reach-1,4
Up Type=0
Dn Type=3
Dn Slope=0.005
Boundary for River Rch & Prof#=SANDIES TRIBUTAR,Reach-1,5
Up Type=0
Dn Type=3
Dn Slope=0.005
Boundary for River Rch & Prof#=SANDIES TRIBUTAR,Reach-1,6
Up Type=0
Dn Type=3
Dn Slope=0.005
Boundary for River Rch & Prof#=SANDIES TRIBUTAR,Reach-1,7
Up Type=0
Dn Type=3
Dn Slope=0.005

--- SANDIES TRIBUTARY 6.g01 (geometry) ---

Geom Title=Existing Conditions

River Reach=SANDIES TRIBUTAR,Reach-1
Reach XY= 30
      2335125.00     13705125.00      2335123.66     13704985.41
      2335082.56     13704925.00      2335122.64     13704869.11
      2335123.89     13704785.55      2335077.36     13704719.02
      2335069.46     13704622.58      2334978.55     13704523.53
      2334973.62     13704335.44      2334932.56     13704275.00
      2334973.60     13704214.56      2334978.79     13704076.57
      2335022.73     13704019.06      2335027.25     13703880.93
      2335068.88     13703827.18      2335081.11     13703772.82
      2335121.17     13703723.42      2335127.36     13703630.98
      2335173.78     13703564.50      2335175.52     13703240.22
      2335183.14     13703218.94      2335219.25     13703177.33
      2335224.93     13703154.97      2335226.20     13702835.50
      2335268.88     13702777.18      2335279.19     13702726.74
      2335319.29     13702677.35      2335324.94     13702654.97
      2335324.04     13702385.40      2335275.00     13702325.00

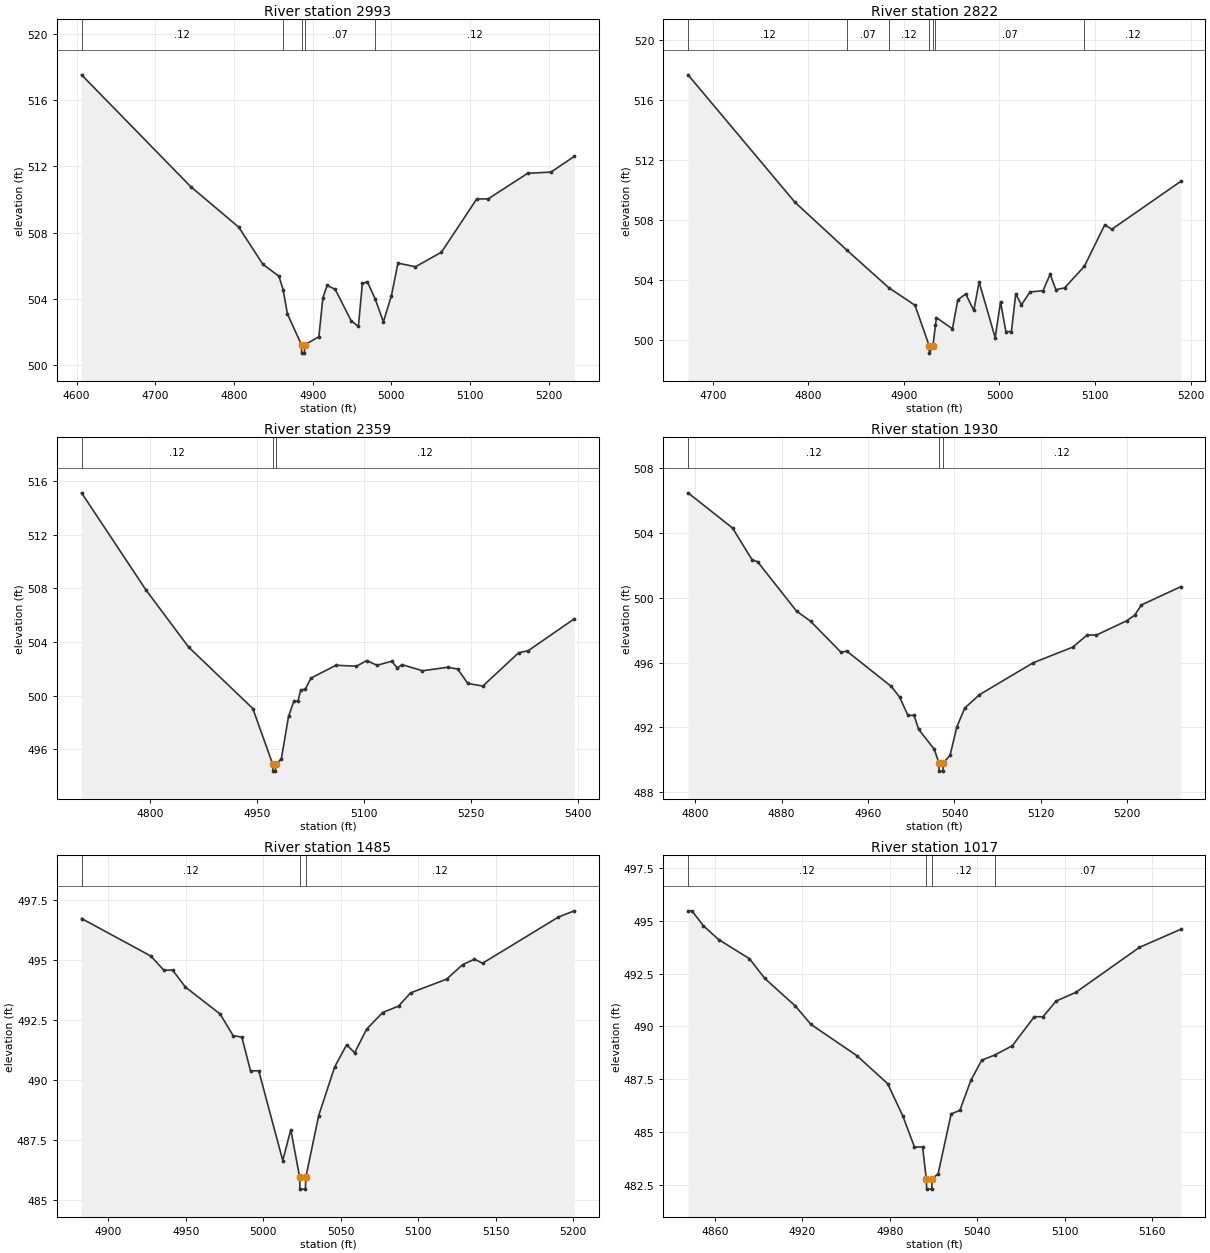
Type RM Length L Ch R = 1,2993,171,171,171
BEGIN DESCRIPTION:
Z21511
END DESCRIPTION:
XS GIS Cut Line= 3
      2335510.76     13704997.98      2335055.68     13705092.01
      2334924.09     13705186.00
#Sta/Elev= 30
  4606.2  517.54  4744.8  510.79  4806.1  508.33  4836.7  506.09  4857.1  505.37
  4862.4  504.56  4867.9  503.09  4885.8  501.22  4886.0  500.72  4889.5  500.72
  4889.8  501.22  4907.9  501.71  4913.0  504.07  4918.4  504.81  4928.6  504.58
  4949.0  502.67  4958.1  502.33  4963.2  504.93  4969.5  505.03  4979.4  504.01
  4989.9  502.61  5000.1  504.19  5008.4  506.16  5030.7  505.94  5063.7  506.82
  5108.6  510.04  5123.0  510.04  5173.4  511.59  5202.9  511.66  5232.6  512.61
#Mann=5,-1,0
  4606.2    0.12       0  4862.4    0.07       0  4885.8    0.05       0
  4889.8    0.07       0  4979.4    0.12       0
Bank Sta=4885.8,4889.8
Exp/Cntr=0.3,0.1

Type RM Length L Ch R = 1,2822,463,463,463
BEGIN DESCRIPTION:
SANDIES TRIBUTARY 6 5.0
END DESCRIPTION:
XS GIS Cut Line= 3
      2335374.96     13704775.02      2335075.00     13704925.00
      2334975.03     13705074.96
#Sta/Elev= 30
  4674.1  517.70  4785.9  509.19  4840.7  505.96  4884.2  503.47  4911.6  502.30
  4926.4  499.60  4926.7  499.10  4930.4  499.60  4933.0  500.95  4934.0  501.47
  4950.8  500.73  4956.4  502.66  4964.7  503.06  4973.1  501.95  4978.7  503.85
  4995.5  500.13  5001.1  502.52  5006.7  500.54  5012.5  500.54  5017.0  503.06
  5023.0  502.33  5032.0  503.19  5045.5  503.27  5053.0  504.37  5059.0  503.34
  5068.1  503.46  5088.8  504.90  5110.1  507.67  5117.6  507.38  5189.7  510.58
#Mann=7,-1,0
  4674.1    0.12       0  4840.7    0.07       0  4884.2    0.12       0
  4926.4    0.05       0  4930.4    0.12       0  4933.0    0.07       0
  5088.8    0.12       0
Bank Sta=4926.4,4930.4
Exp/Cntr=0.3,0.1

Type RM Length L Ch R = 1,2359,429,429,429
BEGIN DESCRIPTION:
SANDIES TRIBUTARY 6 4.0
END DESCRIPTION:
XS GIS Cut Line= 3
      2335274.97     13704525.00      2334975.00     13704525.00
      2334674.99     13704775.01
#Sta/Elev= 30
  4704.3  515.14  4794.3  507.91  4854.3  503.63  4944.3  499.04  4972.3  494.87
  4972.5  494.37  4976.0  494.37  4976.3  494.87  4984.3  495.28  4994.3  498.45
  5001.8  499.59  5007.5  499.59  5011.4  500.42  5017.9  500.49  5025.7  501.31
  5060.9  502.27  5089.5  502.20  5103.9  502.62  5118.2  502.27  5139.0  502.57
  5146.8  502.06  5153.3  502.32  5182.0  501.86  5217.1  502.12  5231.4  501.99
  5245.7  500.91  5266.6  500.72  5316.7  503.20  5330.3  503.36  5394.8  505.74
#Mann=3,-1,0
  4704.3    0.12       0  4972.3    0.05       0  4976.3    0.12       0
Bank Sta=4972.3,4976.3
Exp/Cntr=0.3,0.1

Type RM Length L Ch R = 1,1930,445,445,445
BEGIN DESCRIPTION:
SANDIES TRIBUTARY 6 3.0
END DESCRIPTION:
XS GIS Cut Line= 3
      2335175.01     13704175.00      2334975.00     13704125.00
      2334824.98     13703924.97
#Sta/Elev= 30
  4793.3  506.47  4834.5  504.30  4852.6  502.34  4857.7  502.22  4893.8  499.17
  4906.7  498.55  4935.0  496.63  4940.2  496.71  4981.4  494.53  4989.2  493.87
  4996.9  492.74  5002.6  492.74  5006.8  491.88  5021.3  490.65  5025.6  489.80
  5025.8  489.30  5029.3  489.30  5029.6  489.80  5035.9  490.28  5042.2  492.03
  5049.5  493.19  5063.0  494.01  5113.0  495.99  5149.5  496.95  5163.0  497.71
  5171.3  497.69  5199.5  498.58  5206.8  498.92  5213.0  499.55  5249.5  500.68
#Mann=3,-1,0
  4793.3    0.12       0  5025.6    0.05       0  5029.6    0.12       0
Bank Sta=5025.6,5029.6
Exp/Cntr=0.3,0.1

Type RM Length L Ch R = 1,1485,468,468,468
BEGIN DESCRIPTION:
SANDIES TRIBUTARY 6 2.0
END DESCRIPTION:
XS GIS Cut Line= 3
      2335224.97     13703774.98      2335125.00     13703725.00
      2334925.02     13703774.99
#Sta/Elev= 30
  4882.8  496.71  4927.5  495.15  4935.9  494.56  4941.5  494.57  4949.8  493.86
  4972.2  492.74  4980.6  491.84  4986.2  491.78  4991.8  490.38  4997.1  490.38
  5012.6  486.65  5017.8  487.93  5023.5  485.96  5023.7  485.46  5027.2  485.46
  5027.5  485.96  5035.8  488.52  5046.1  490.54  5053.8  491.46  5059.0  491.13
  5066.7  492.11  5077.0  492.80  5087.3  493.07  5095.1  493.62  5118.3  494.19
  5128.6  494.79  5136.3  495.02  5141.5  494.85  5190.4  496.77  5200.7  497.03
#Mann=3,-1,0
  4882.8    0.12       0  5023.5    0.05       0  5027.5    0.12       0
Bank Sta=5023.5,5027.5
Exp/Cntr=0.3,0.1

Type RM Length L Ch R = 1,1017,0,0,0
BEGIN DESCRIPTION:
SANDIES TRIBUTARY 6 1.0
END DESCRIPTION:
XS GIS Cut Line= 3
      2335325.02     13703325.01      2335175.00     13703275.00
      2335025.01     13703374.99
#Sta/Elev= 30
  4841.4  495.46  4844.1  495.46  4852.0  494.75  4862.5  494.10  4883.6  493.20
  4894.1  492.27  4915.2  490.96  4925.8  490.10  4957.4  488.62  4978.5  487.30
  4989.0  485.76  4996.9  484.31  5002.5  484.31  5005.0  482.82  5005.3  482.32
  5008.8  482.32  5009.0  482.82  5013.1  483.03  5022.1  485.87  5028.1  486.04
  5035.6  487.45  5043.1  488.41  5052.0  488.65  5064.1  489.09  5079.2  490.46
  5085.2  490.46  5094.2  491.20  5107.7  491.61  5151.3  493.73  5179.8  494.59
#Mann=4,-1,0
  4841.4    0.12       0  5005.0    0.05       0  5009.0    0.12       0
  5052.0    0.07       0
Bank Sta=5005,5009
Exp/Cntr=0.3,0.1

Chan Stop Cuts=-1