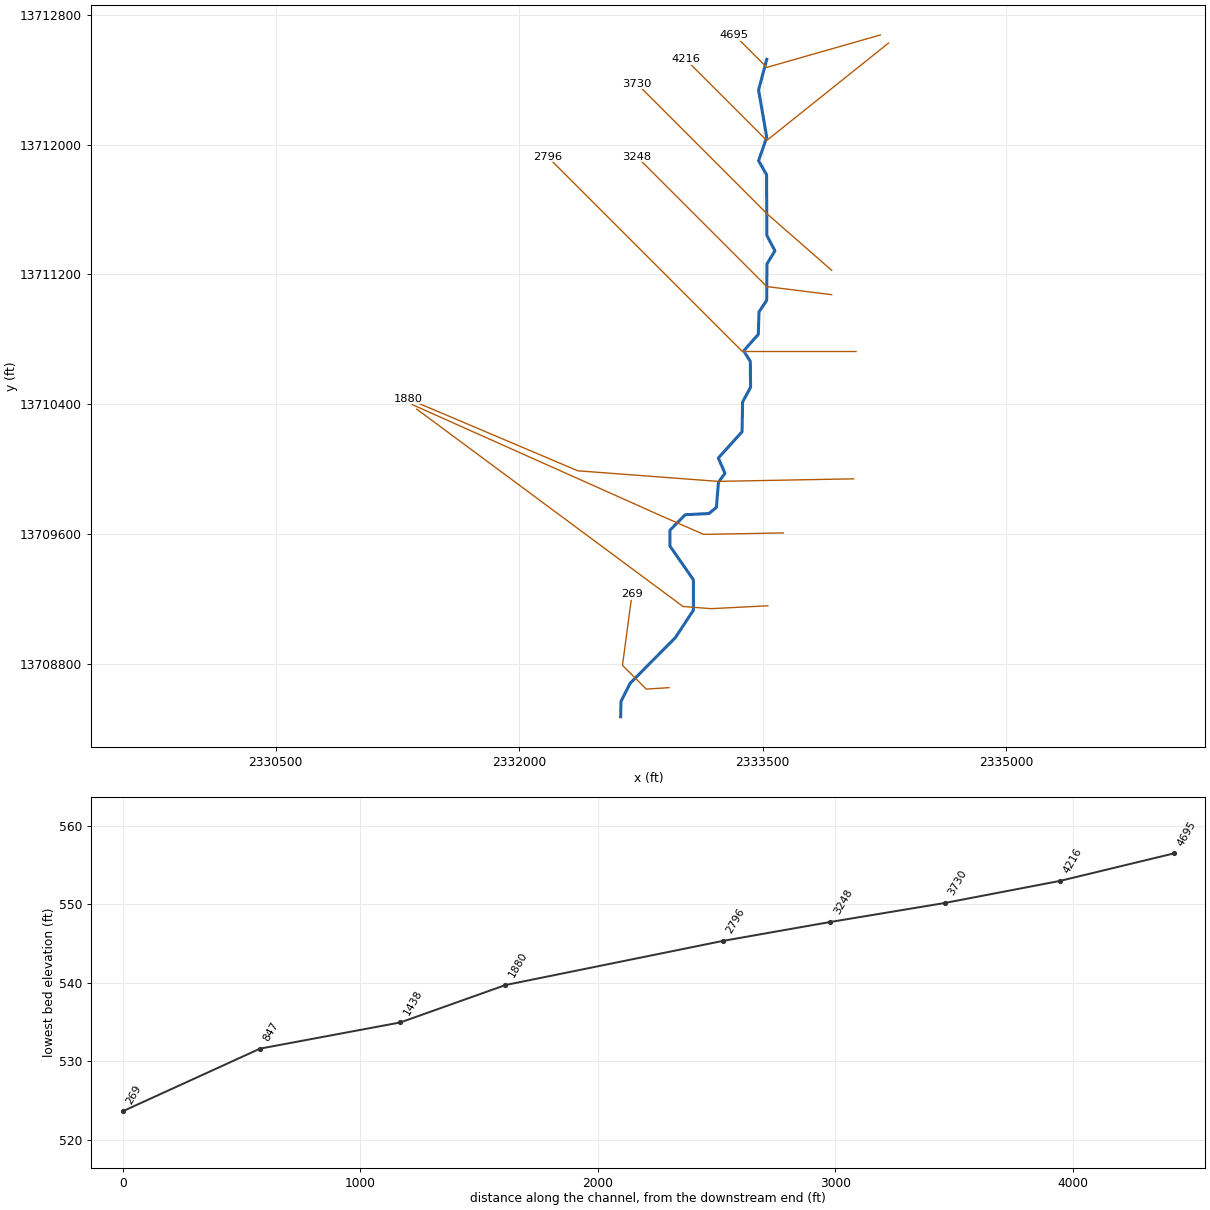
--- SANDIES TRIBUTARY 7.prj (project) ---

Proj Title=SANDIES TRIBUTARY 7 Base Level Engineering
Current Plan=p01
Default Exp/Contr=0.3,0.1
English Units
Geom File=g01
Flow File=f01
Plan File=p01
Y Axis Title=Elevation
X Axis Title(PF)=Main Channel Distance
X Axis Title(XS)=Station
BEGIN DESCRIPTION:
SANDIES TRIBUTARY 7
END DESCRIPTION:
DSS Export Rating Curves= 0
DSS Export Rating Curve Sorted= 0
DSS Export Volume Flow Curves= 0
DXF OffsetX= 0
DXF OffsetY= 0
DXF ScaleX= 1
DXF ScaleY= 10

--- SANDIES TRIBUTARY 7.p01 (plan) ---

Plan Title=Multiple Run
Short Identifier=Multiple
Geom File=g01
Flow File=f01
Subcritical Flow
K Sum by GR= 0
Std Step Tol= 0.01
Critical Tol= 0.01
Num of Std Step Trials= 20
Max Error Tol= 0.3
Flow Tol Ratio= 0.001
Split Flow NTrial= 30
Split Flow Tol= 0.02
Split Flow Ratio= 0.02
Log Output Level= 0
Friction Slope Method= 1
Unsteady Friction Slope Method= 2
Unsteady Bridges Friction Slope Method= 1
Parabolic Critical Depth
Global Vel Dist=  1 , 1 , 1
Global Log Level= 0
CheckData=True
Encroach Param= -1, 0, 0, 0
BEGIN DESCRIPTION:
Multiple Run
END DESCRIPTION:

--- SANDIES TRIBUTARY 7.f01 (steady flow) ---

Flow Title=Multiple
Number of Profiles=7
Profile Names=10-year,25-year,50-year,1pct_min,100-year,1pct_plu,500-year
River Rch & RM= SANDIES TRIBUTAR,Reach-1,4695
     778    1279    1739    1146    2286    4561    3911
River Rch & RM= SANDIES TRIBUTAR,Reach-1,1880
     881    1456    1988    1314    2622    5232    4519
Boundary for River Rch & Prof#=SANDIES TRIBUTAR,Reach-1,1
Up Type=0
Dn Type=3
Dn Slope=0.01
Boundary for River Rch & Prof#=SANDIES TRIBUTAR,Reach-1,2
Up Type=0
Dn Type=3
Dn Slope=0.01
Boundary for River Rch & Prof#=SANDIES TRIBUTAR,Reach-1,3
Up Type=0
Dn Type=3
Dn Slope=0.01
Boundary for River Rch & Prof#=SANDIES TRIBUTAR,Reach-1,4
Up Type=0
Dn Type=3
Dn Slope=0.01
Boundary for River Rch & Prof#=SANDIES TRIBUTAR,Reach-1,5
Up Type=0
Dn Type=3
Dn Slope=0.01
Boundary for River Rch & Prof#=SANDIES TRIBUTAR,Reach-1,6
Up Type=0
Dn Type=3
Dn Slope=0.01
Boundary for River Rch & Prof#=SANDIES TRIBUTAR,Reach-1,7
Up Type=0
Dn Type=3
Dn Slope=0.01

--- SANDIES TRIBUTARY 7.g01 (geometry) ---

Geom Title=Existing Conditions

River Reach=SANDIES TRIBUTAR,Reach-1
Reach XY= 30
      2333525.00     13712525.00      2333474.50     13712335.17
      2333524.95     13712045.04      2333474.60     13711900.00
      2333523.78     13711814.50      2333525.54     13711440.21
      2333575.28     13711345.18      2333526.24     13711264.50
      2333524.48     13711040.22      2333477.27     13710969.06
      2333472.92     13710830.86      2333382.81     13710728.41
      2333423.61     13710664.57      2333425.36     13710504.85
      2333376.22     13710414.49      2333372.94     13710230.85
      2333226.66     13710068.95      2333267.41     13709975.01
      2333227.47     13709919.14      2333214.68     13709764.82
      2333169.35     13709726.98      2333022.54     13709719.54
      2332928.45     13709623.52      2332928.67     13709526.59
      2333072.94     13709319.14      2333072.94     13709130.86
      2332961.37     13708961.79      2332683.14     13708681.06
      2332627.07     13708569.14      2332625.00     13708475.00

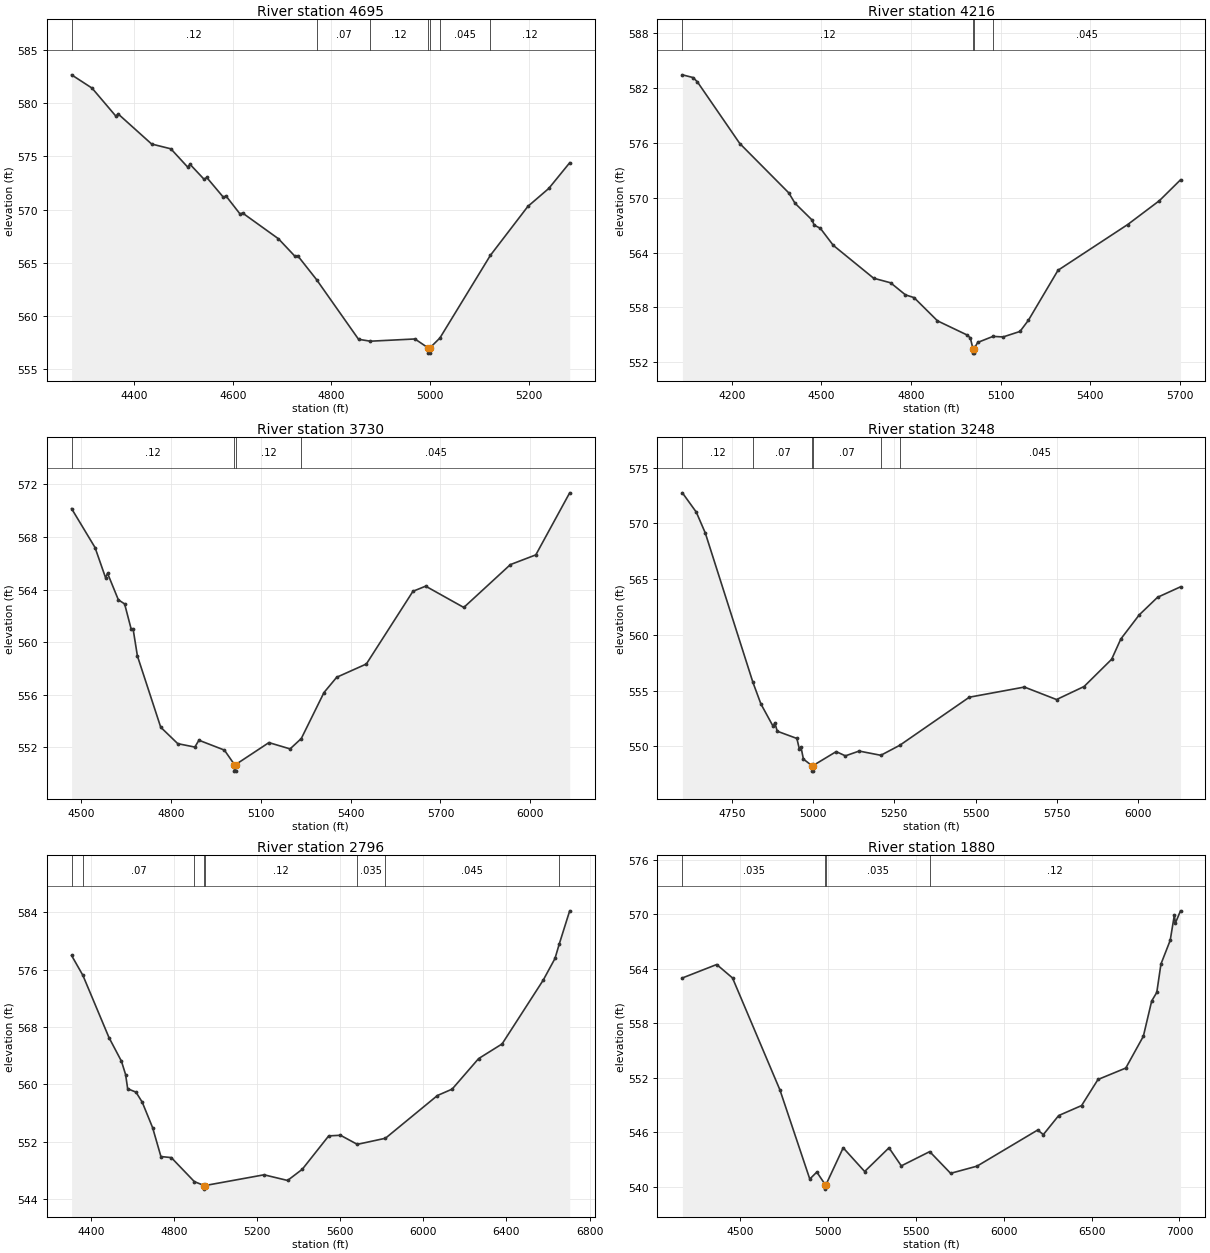
Type RM Length L Ch R = 1,4695,479,479,479
BEGIN DESCRIPTION:
SANDIES TRIBUTARY 7 6.0
END DESCRIPTION:
XS GIS Cut Line= 3
      2334225.04     13712675.01      2333525.00     13712475.00
      2333324.99     13712675.01
#Sta/Elev= 30
  4272.6  582.65  4314.2  581.40  4362.3  578.78  4367.5  578.96  4435.1  576.15
  4474.1  575.70  4507.9  574.00  4513.1  574.24  4541.7  572.83  4546.9  573.01
  4580.7  571.15  4585.9  571.28  4614.5  569.58  4619.7  569.67  4692.5  567.25
  4726.3  565.59  4731.5  565.66  4769.7  563.42  4855.0  557.81  4879.0  557.63
  4969.4  557.84  4996.0  557.01  4996.3  556.51  4999.8  556.51  5000.0  557.01
  5020.1  557.93  5122.5  565.69  5198.6  570.29  5241.1  571.98  5283.5  574.39
#Mann=7,-1,0
  4272.6    0.12       0  4769.7    0.07       0  4879.0    0.12       0
  4996.0    0.05       0  5000.0    0.12       0  5020.1   0.045       0
  5122.5    0.12       0
Bank Sta=4996,5000
Exp/Cntr=0.3,0.1

Type RM Length L Ch R = 1,4216,486,486,486
BEGIN DESCRIPTION:
SANDIES TRIBUTARY 7 5.0
END DESCRIPTION:
XS GIS Cut Line= 3
      2334275.00     13712625.00      2333525.00     13712025.00
      2333024.98     13712525.02
#Sta/Elev= 30
  4035.0  583.44  4071.0  583.14  4085.4  582.66  4227.1  575.93  4391.2  570.53
  4412.0  569.40  4469.6  567.55  4476.0  567.01  4496.8  566.66  4540.0  564.80
  4675.3  561.20  4732.1  560.70  4781.8  559.38  4810.6  559.08  4889.0  556.54
  4988.3  554.99  4999.0  554.67  5007.6  553.51  5007.9  553.01  5011.4  553.01
  5011.6  553.51  5023.8  554.18  5074.9  554.84  5108.6  554.78  5165.2  555.38
  5193.5  556.61  5292.5  562.07  5525.8  567.07  5631.9  569.68  5702.6  571.96
#Mann=4,-1,0
  4035.0    0.12       0  5007.6    0.05       0  5011.6    0.12       0
  5074.9   0.045       0
Bank Sta=5007.6,5011.6
Exp/Cntr=0.3,0.1

Type RM Length L Ch R = 1,3730,482,482,482
BEGIN DESCRIPTION:
SANDIES TRIBUTARY 7 4.0
END DESCRIPTION:
XS GIS Cut Line= 3
      2333925.03     13711224.97      2333525.00     13711575.00
      2332725.01     13712374.99
#Sta/Elev= 30
  4468.4  570.16  4546.7  567.20  4581.9  564.90  4588.5  565.24  4624.6  563.22
  4645.5  562.91  4667.3  561.00  4673.9  560.99  4688.2  558.95  4766.0  553.53
  4822.9  552.28  4879.9  552.02  4893.6  552.54  4978.6  551.79  5012.0  550.69
  5012.3  550.19  5015.9  550.19  5016.2  550.69  5127.2  552.36  5197.9  551.88
  5235.3  552.67  5311.1  556.17  5353.5  557.33  5452.5  558.34  5608.1  563.87
  5650.5  564.26  5777.8  562.64  5933.3  565.90  6018.2  566.64  6131.3  571.36
#Mann=4,-1,0
  4468.4    0.12       0  5012.0    0.05       0  5016.2    0.12       0
  5235.3   0.045       0
Bank Sta=5012,5016.2
Exp/Cntr=0.3,0.1

Type RM Length L Ch R = 1,3248,452,452,452
BEGIN DESCRIPTION:
SANDIES TRIBUTARY 7 3.0
END DESCRIPTION:
XS GIS Cut Line= 3
      2333924.97     13711075.00      2333525.00     13711125.00
      2332724.97     13711925.03
#Sta/Elev= 30
  4597.0  572.73  4639.8  571.00  4667.5  569.13  4814.4  555.72  4838.8  553.80
  4876.6  551.78  4881.7  552.11  4889.2  551.35  4949.7  550.70  4957.2  549.76
  4962.3  549.93  4969.8  548.85  4995.5  548.27  4995.7  547.77  4999.4  547.77
  4999.7  548.27  5070.8  549.52  5099.1  549.14  5141.5  549.57  5208.3  549.19
  5266.8  550.09  5480.9  554.40  5650.6  555.31  5749.6  554.19  5834.5  555.36
  5919.3  557.80  5947.6  559.62  6004.2  561.78  6060.7  563.36  6131.5  564.30
#Mann=6,-1,0
  4597.0    0.12       0  4814.4    0.07       0  4995.5    0.05       0
  4999.7    0.07       0  5208.3    0.12       0  5266.8   0.045       0
Bank Sta=4995.5,4999.7
Exp/Cntr=0.3,0.1

Type RM Length L Ch R = 1,2796,916,916,916
BEGIN DESCRIPTION:
SANDIES TRIBUTARY 7 2.0
END DESCRIPTION:
XS GIS Cut Line= 3
      2334075.04     13710725.00      2333375.00     13710725.00
      2332175.00     13711925.00
#Sta/Elev= 30
  4307.3  577.98  4361.8  575.20  4487.3  566.52  4547.3  563.22  4567.3  561.35
  4577.3  559.37  4617.3  558.90  4647.3  557.50  4697.3  553.94  4737.3  549.91
  4787.3  549.76  4898.1  546.41  4945.2  545.86  4945.5  545.36  4949.4  545.86
  5233.6  547.36  5346.8  546.57  5417.5  548.13  5544.7  552.79  5601.3  552.88
  5682.3  551.61  5817.6  552.46  6068.0  558.43  6138.7  559.32  6266.0  563.58
  6379.1  565.63  6577.1  574.54  6633.7  577.56  6654.0  579.56  6704.4  584.21
#Mann=8,-1,0
  4307.3    0.12       0  4361.8    0.07       0  4898.1    0.12       0
  4945.2    0.05       0  4949.4    0.12       0  5682.3   0.035       0
  5817.6   0.045       0  6654.0    0.12       0
Bank Sta=4945.2,4949.4
Exp/Cntr=0.3,0.1

Type RM Length L Ch R = 1,1880,442,442,442
BEGIN DESCRIPTION:
SANDIES TRIBUTARY 7 1.0
END DESCRIPTION:
XS GIS Cut Line= 4
      2334060.37     13709940.71      2333225.00     13709925.00
      2332361.20     13709990.14      2331316.24     13710433.00
#Sta/Elev= 30
  4169.3  562.98  4364.7  564.46  4454.7  562.98  4724.8  550.65  4894.8  540.84
  4934.8  541.61  4982.5  540.23  4982.8  539.73  4987.2  540.23  5085.0  544.28
  5207.3  541.67  5345.8  544.28  5416.0  542.29  5577.7  543.86  5696.8  541.47
  5847.2  542.26  6192.8  546.24  6224.7  545.73  6312.2  547.83  6442.6  548.93
  6536.0  551.80  6694.3  553.06  6794.4  556.56  6841.8  560.44  6870.9  561.39
  6894.6  564.51  6947.3  567.12  6971.0  569.91  6976.4  569.01  7006.0  570.37
#Mann=4,-1,0
  4169.3   0.035       0  4982.5   0.035       0  4987.2   0.035       0
  5577.7    0.12       0
Bank Sta=4982.5,4987.2
Exp/Cntr=0.3,0.1

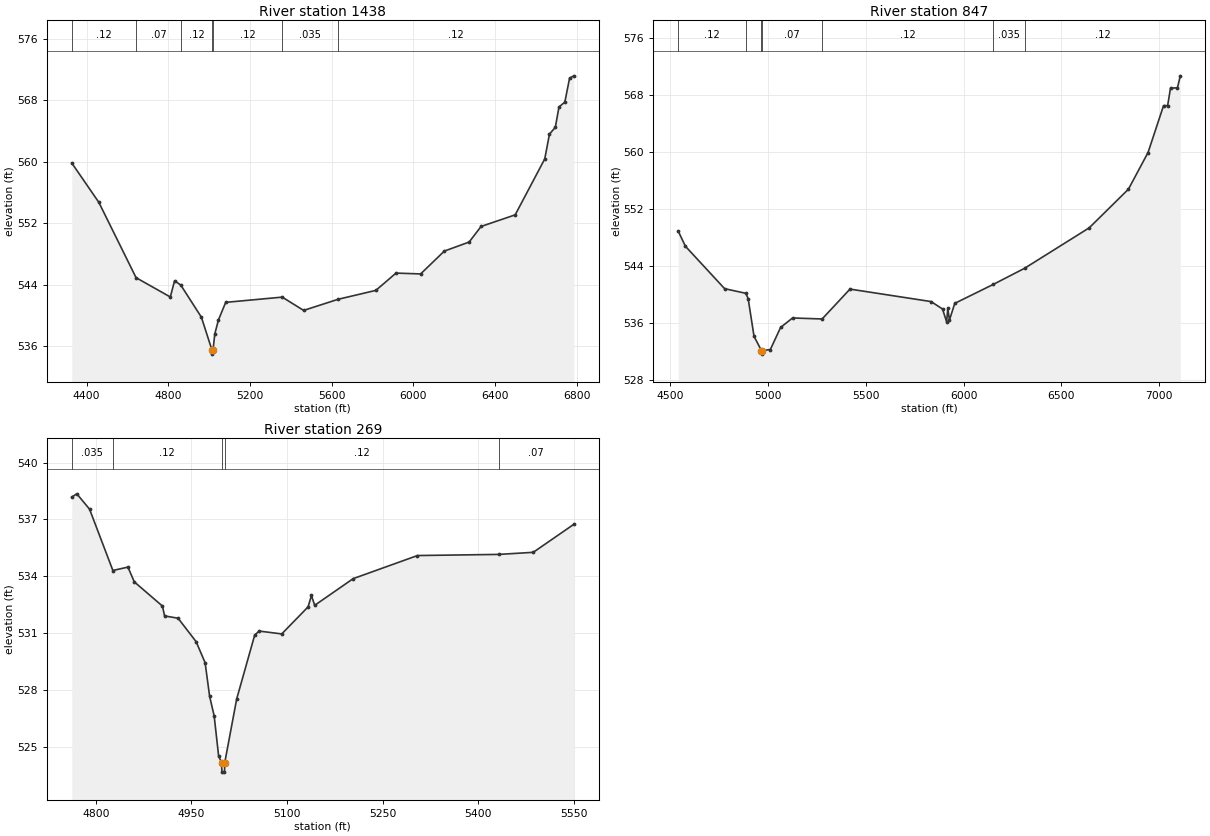
Type RM Length L Ch R = 1,1438,591,591,591
BEGIN DESCRIPTION:
SANDIES TRIBUTARY 7 0.6
END DESCRIPTION:
XS GIS Cut Line= 4
      2333627.14     13709607.44      2333136.13     13709598.55
      2332891.73     13709705.20      2331340.47     13710398.31
#Sta/Elev= 30
  4327.9  559.85  4460.1  554.74  4642.6  544.92  4810.1  542.41  4831.1  544.53
  4861.8  543.94  4962.1  539.78  5014.3  535.47  5014.6  534.97  5019.0  535.47
  5027.8  537.61  5045.8  539.43  5081.1  541.71  5357.9  542.39  5462.5  540.66
  5631.3  542.11  5815.9  543.27  5914.5  545.52  6035.0  545.41  6150.7  548.38
  6272.3  549.56  6330.7  551.59  6497.6  553.10  6642.3  560.38  6665.5  563.62
  6694.2  564.50  6711.9  567.14  6740.6  567.78  6763.8  570.89  6784.7  571.20
#Mann=7,-1,0
  4327.9    0.12       0  4642.6    0.07       0  4861.8    0.12       0
  5014.3    0.05       0  5019.0    0.12       0  5357.9   0.035       0
  5631.3    0.12       0
Bank Sta=5014.3,5019
Exp/Cntr=0.3,0.1

Type RM Length L Ch R = 1,847,578,578,578
BEGIN DESCRIPTION:
SANDIES TRIBUTARY 7 0.4
END DESCRIPTION:
XS GIS Cut Line= 4
      2333531.59     13709158.64      2333182.79     13709140.86
      2333009.48     13709154.19      2331369.45     13710369.65
#Sta/Elev= 30
  4542.9  548.88  4579.5  546.76  4779.8  540.81  4888.1  540.16  4900.0  539.42
  4930.0  534.13  4967.8  532.13  4968.2  531.63  4972.5  532.13  5013.3  532.27
  5065.7  535.37  5126.8  536.70  5277.9  536.56  5420.1  540.75  5834.3  539.00
  5892.7  537.96  5913.6  536.17  5919.8  538.05  5928.2  536.41  5955.3  538.75
  6152.9  541.42  6312.0  543.67  6641.9  549.34  6842.2  554.76  6942.4  559.90
  7021.7  566.48  7042.5  566.48  7057.2  568.93  7092.6  568.98  7107.3  570.66
#Mann=7,-1,0
  4542.9    0.12       0  4888.1    0.07       0  4967.8    0.05       0
  4972.5    0.07       0  5277.9    0.12       0  6152.9   0.035       0
  6312.0    0.12       0
Bank Sta=4967.8,4972.5
Exp/Cntr=0.3,0.1

Type RM Length L Ch R = 1,269,0,0,0
BEGIN DESCRIPTION:
SANDIES TRIBUTARY 7 0.2
END DESCRIPTION:
XS GIS Cut Line= 4
      2332922.88     13708654.29      2332782.86     13708645.40
      2332636.22     13708792.04      2332694.68     13709228.16
#Sta/Elev= 30
  4762.2  538.18  4770.1  538.35  4790.1  537.54  4826.7  534.30  4850.3  534.48
  4860.3  533.70  4904.5  532.42  4907.8  531.90  4929.0  531.78  4957.3  530.54
  4971.4  529.43  4978.5  527.65  4985.6  526.62  4992.6  524.50  4997.3  524.15
  4997.7  523.65  5001.8  523.65  5002.2  524.15  5020.9  527.51  5049.2  530.89
  5056.3  531.10  5091.6  530.95  5133.0  532.38  5138.2  532.98  5143.3  532.46
  5203.7  533.87  5304.6  535.09  5432.0  535.15  5486.2  535.26  5549.9  536.74
#Mann=5,-1,0
  4762.2   0.035       0  4826.7    0.12       0  4997.3    0.05       0
  5002.2    0.12       0  5432.0    0.07       0
Bank Sta=4997.3,5002.2
Exp/Cntr=0.3,0.1

Chan Stop Cuts=-1