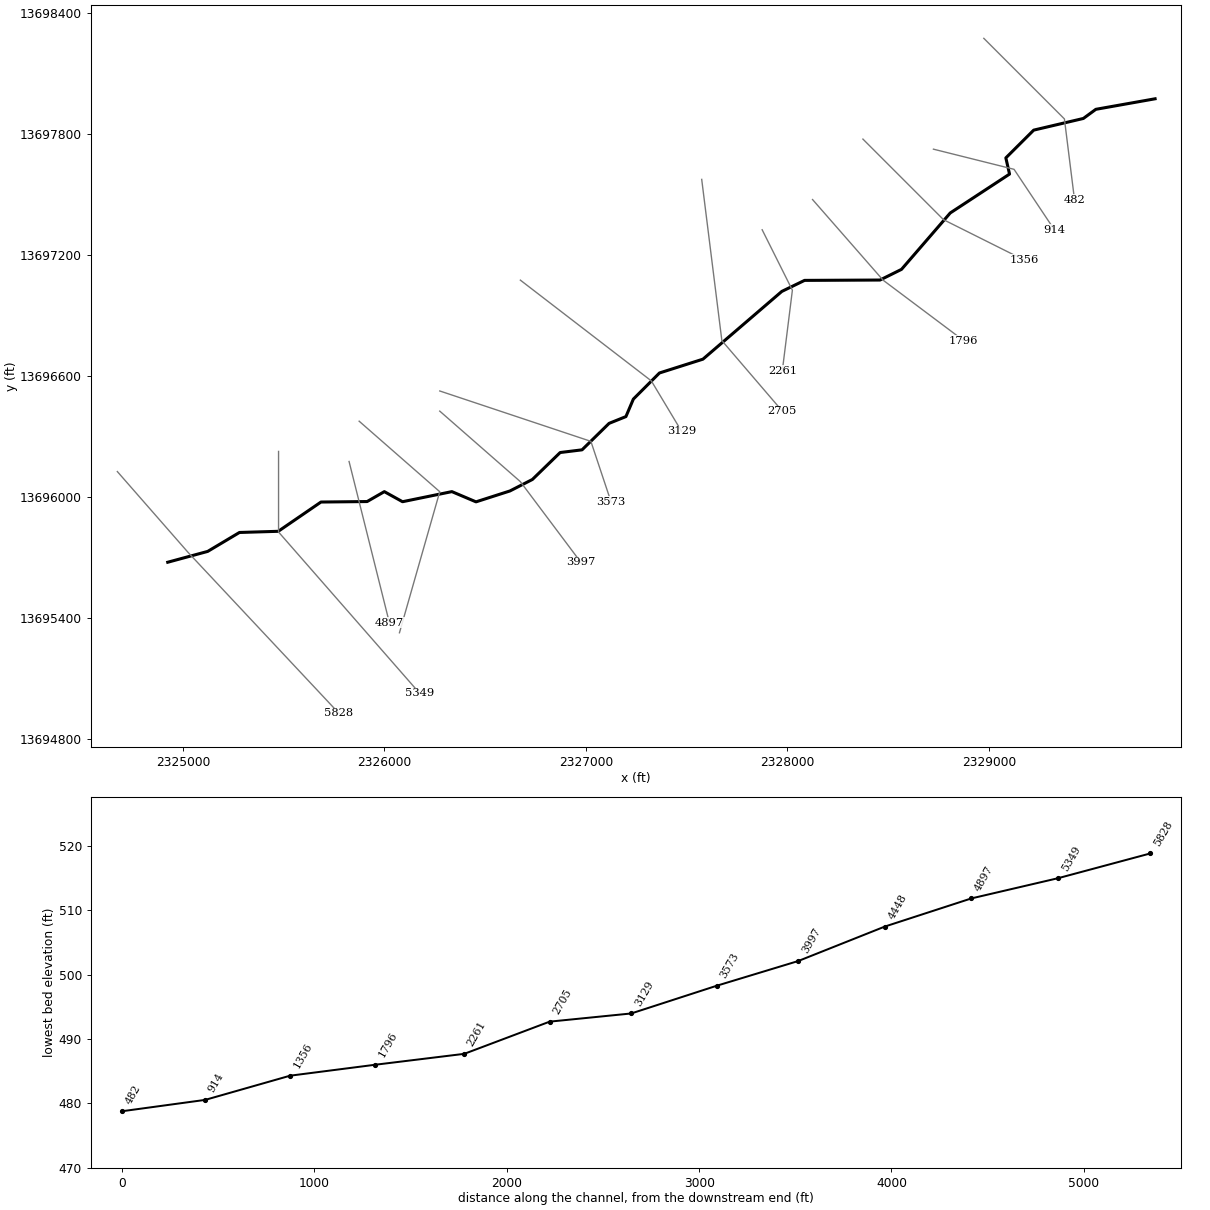
--- SANDIES TRIBUTARY 9.prj (project) ---

Proj Title=SANDIES TRIBUTARY 9 Base Level Engineering
Current Plan=p01
Default Exp/Contr=0.3,0.1
English Units
Geom File=g01
Flow File=f01
Plan File=p01
BEGIN DESCRIPTION:
SANDIES TRIBUTARY 9
END DESCRIPTION:

--- SANDIES TRIBUTARY 9.p01 (plan) ---

Plan Title=Multiple Run
Short Identifier=Multiple
Geom File=g01
Flow File=f01
Subcritical Flow
K Sum by GR= 0
Std Step Tol= 0.01
Critical Tol= 0.01
Num of Std Step Trials= 20
Max Error Tol= 0.3
Flow Tol Ratio= 0.001
Split Flow NTrial= 30
Split Flow Tol= 0.02
Split Flow Ratio= 0.02
Log Output Level= 0
Friction Slope Method= 1
Unsteady Friction Slope Method= 2
Unsteady Bridges Friction Slope Method= 1
Parabolic Critical Depth
Global Vel Dist=  1 , 1 , 1
Global Log Level= 0
CheckData=True
Encroach Param= -1, 0, 0, 0
BEGIN DESCRIPTION:
Multiple Run
END DESCRIPTION:

--- SANDIES TRIBUTARY 9.f01 (steady flow) ---

Flow Title=Multiple
Number of Profiles=7
Profile Names=10-year,25-year,50-year,1pct_min,100-year,1pct_plu,500-year
River Rch & RM= SANDIES TRIBUTAR,Reach-1,5828
     715    1177    1602    1057    2108    4207    3619
River Rch & RM= SANDIES TRIBUTAR,Reach-1,5349
    1152    1945    2694    1804    3600    7184    6379
River Rch & RM= SANDIES TRIBUTAR,Reach-1,914
    1144    1928    2667    1784    3560    7103    6290
Boundary for River Rch & Prof#=SANDIES TRIBUTAR,Reach-1,1
Up Type=0
Dn Type=3
Dn Slope=0.005
Boundary for River Rch & Prof#=SANDIES TRIBUTAR,Reach-1,2
Up Type=0
Dn Type=3
Dn Slope=0.005
Boundary for River Rch & Prof#=SANDIES TRIBUTAR,Reach-1,3
Up Type=0
Dn Type=3
Dn Slope=0.005
Boundary for River Rch & Prof#=SANDIES TRIBUTAR,Reach-1,4
Up Type=0
Dn Type=3
Dn Slope=0.005
Boundary for River Rch & Prof#=SANDIES TRIBUTAR,Reach-1,5
Up Type=0
Dn Type=3
Dn Slope=0.005
Boundary for River Rch & Prof#=SANDIES TRIBUTAR,Reach-1,6
Up Type=0
Dn Type=3
Dn Slope=0.005
Boundary for River Rch & Prof#=SANDIES TRIBUTAR,Reach-1,7
Up Type=0
Dn Type=3
Dn Slope=0.005

--- SANDIES TRIBUTARY 9.g01 (geometry) ---

Geom Title=Existing Conditions

River Reach=SANDIES TRIBUTAR,Reach-1
Reach XY= 30
      2324925.00     13695675.00      2325123.42     13695728.82
      2325280.93     13695822.76      2325473.53     13695828.55
      2325685.50     13695973.80      2325914.50     13695976.24
      2326000.00     13696025.40      2326090.27     13695975.40
      2326335.17     13696025.50      2326454.82     13695974.72
      2326623.42     13696028.82      2326734.68     13696085.76
      2326872.57     13696219.48      2326981.17     13696232.86
      2327115.34     13696364.21      2327198.84     13696397.86
      2327235.79     13696484.66      2327365.32     13696614.24
      2327581.17     13696682.86      2327972.70     13697019.17
      2328085.50     13697073.80      2328459.80     13697075.50
      2328566.52     13697128.51      2328808.33     13697408.35
      2329102.64     13697601.30      2329084.31     13697681.66
      2329222.57     13697819.48      2329469.02     13697877.36
      2329530.94     13697922.73      2329825.00     13697975.00

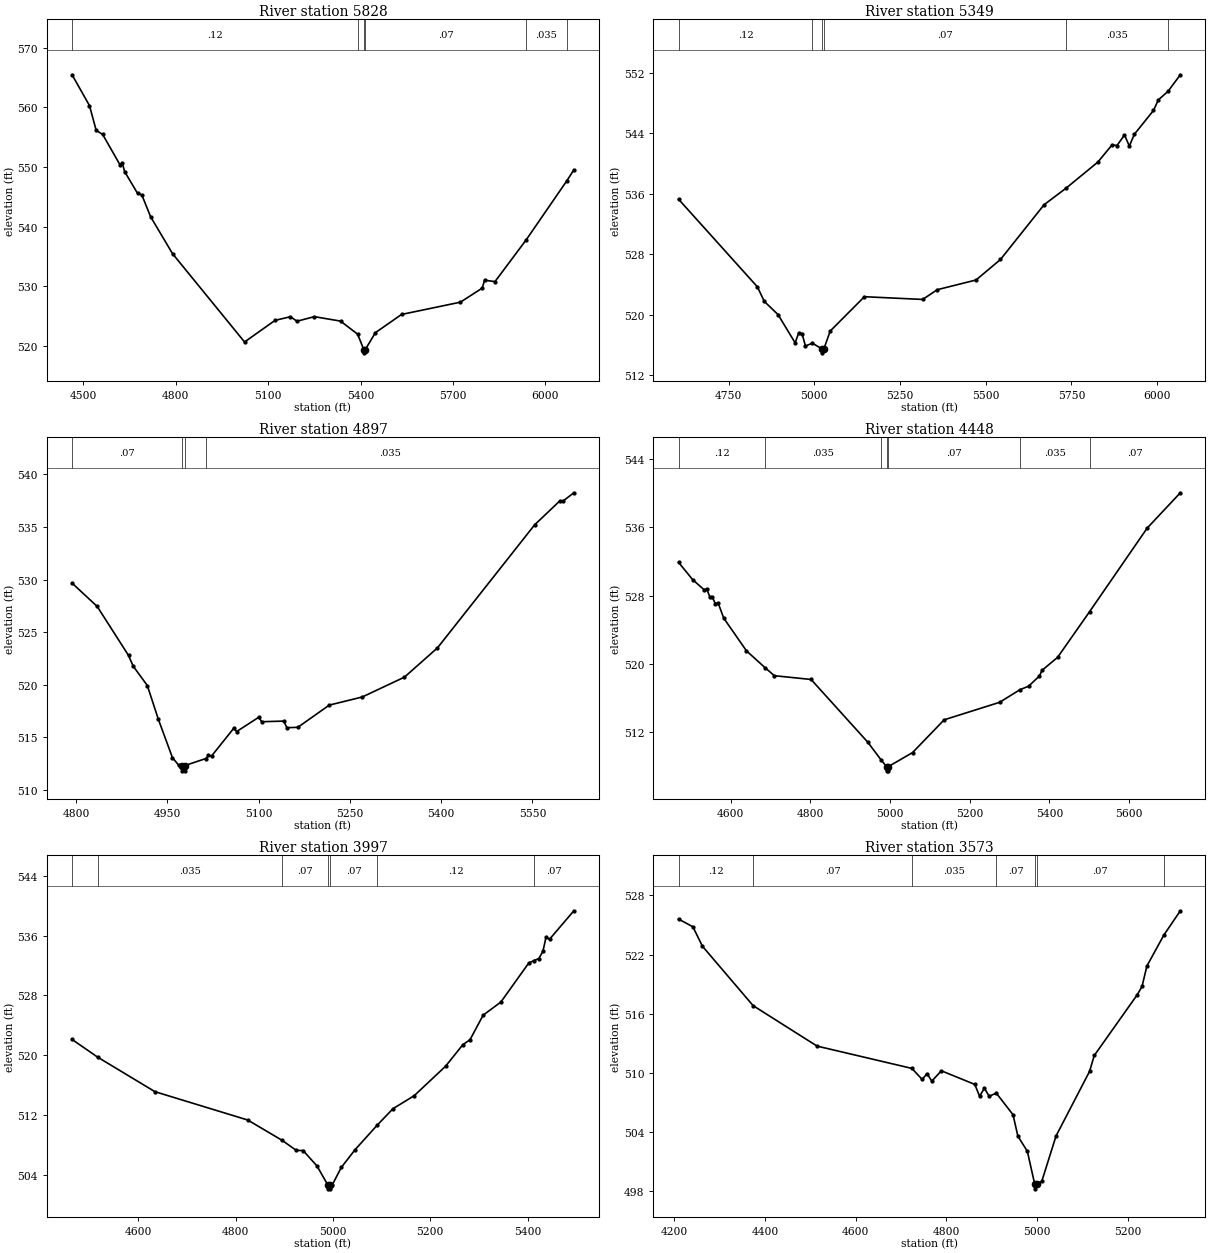
Type RM Length L Ch R = 1,5828,479,479,479
BEGIN DESCRIPTION:
SANDIES TRIBUTARY 9 13.0
END DESCRIPTION:
XS GIS Cut Line= 3
      2324674.99     13696125.01      2325025.00     13695725.00
      2325775.00     13694925.00
#Sta/Elev= 30
  4464.1  565.45  4520.6  560.28  4542.4  556.11  4563.3  555.45  4620.2  550.29
  4626.9  550.69  4634.5  549.22  4676.7  545.55  4690.5  545.29  4718.9  541.64
  4790.1  535.44  5023.7  520.63  5122.9  524.26  5172.7  524.87  5193.7  524.11
  5250.3  524.88  5335.3  524.13  5390.6  521.94  5411.0  519.31  5411.3  518.81
  5415.0  519.31  5448.2  522.19  5533.2  525.25  5724.2  527.31  5795.0  529.67
  5802.3  530.99  5836.3  530.76  5937.5  537.76  6068.9  547.63  6092.2  549.50
#Mann=6,-1,0
  4464.1    0.12       0  5390.6    0.07       0  5411.0    0.05       0
  5415.0    0.07       0  5937.5   0.035       0  6068.9    0.12       0
Bank Sta=5411,5415
Exp/Cntr=0.3,0.1

Type RM Length L Ch R = 1,5349,452,452,452
BEGIN DESCRIPTION:
SANDIES TRIBUTARY 9 12.0
END DESCRIPTION:
XS GIS Cut Line= 3
      2325475.00     13696224.97      2325475.00     13695825.00
      2326175.01     13695024.99
#Sta/Elev= 30
  4604.3  535.28  4834.3  523.69  4854.3  521.77  4894.3  520.03  4944.3  516.29
  4954.3  517.56  4964.3  517.52  4974.3  515.88  4994.6  516.24  5023.4  515.47
  5023.7  514.97  5027.9  515.47  5046.5  517.85  5146.2  522.39  5316.1  522.03
  5358.8  523.32  5471.7  524.60  5542.9  527.31  5670.1  534.55  5734.2  536.74
  5826.7  540.18  5868.4  542.47  5882.7  542.38  5904.5  543.77  5918.7  542.30
  5933.0  543.85  5989.0  547.01  6003.2  548.41  6031.4  549.54  6067.3  551.73
#Mann=6,-1,0
  4604.3    0.12       0  4994.6    0.07       0  5023.4    0.05       0
  5027.9    0.07       0  5734.2   0.035       0  6031.4    0.12       0
Bank Sta=5023.4,5027.9
Exp/Cntr=0.3,0.1

Type RM Length L Ch R = 1,4897,449,449,449
BEGIN DESCRIPTION:
SANDIES TRIBUTARY 9 11.0
END DESCRIPTION:
XS GIS Cut Line= 3
      2325824.99     13696175.03      2325875.00     13695975.00
      2326025.01     13695374.96
#Sta/Elev= 30
  4793.4  529.67  4834.7  527.45  4886.2  522.79  4893.9  521.77  4917.1  519.93
  4935.2  516.72  4958.4  513.07  4968.7  512.35  4974.1  512.32  4974.4  511.82
  4978.3  511.82  4978.6  512.32  5013.3  512.99  5017.6  513.29  5022.8  513.24
  5058.9  515.85  5064.0  515.56  5100.1  516.91  5105.2  516.49  5141.3  516.55
  5146.5  515.92  5164.5  515.96  5216.1  518.07  5270.2  518.84  5339.7  520.73
  5393.9  523.51  5553.6  535.21  5594.9  537.48  5600.0  537.46  5618.1  538.26
#Mann=4,-1,0
  4793.4    0.07       0  4974.1    0.05       0  4978.6    0.07       0
  5013.3   0.035       0
Bank Sta=4974.1,4978.6
Exp/Cntr=0.3,0.1

Type RM Length L Ch R = 1,4448,451,451,451
BEGIN DESCRIPTION:
SANDIES TRIBUTARY 9 10.0
END DESCRIPTION:
XS GIS Cut Line= 3
      2325874.99     13696375.01      2326275.00     13696025.00
      2326075.01     13695325.03
#Sta/Elev= 30
  4469.2  531.90  4504.8  529.86  4533.3  528.69  4539.9  528.78  4547.5  527.88
  4554.2  527.79  4561.7  527.05  4568.4  527.16  4582.6  525.36  4639.6  521.53
  4686.1  519.56  4709.8  518.61  4801.9  518.17  4944.2  510.82  4978.1  508.71
  4991.3  507.96  4991.6  507.46  4995.5  507.46  4995.9  507.96  5056.6  509.60
  5135.9  513.44  5275.0  515.49  5326.1  516.97  5347.8  517.38  5375.1  518.58
  5381.6  519.24  5420.6  520.76  5501.0  526.12  5645.5  535.91  5728.7  540.05
#Mann=7,-1,0
  4469.2    0.12       0  4686.1   0.035       0  4978.1    0.07       0
  4991.3    0.05       0  4995.9    0.07       0  5326.1   0.035       0
  5501.0    0.07       0
Bank Sta=4991.3,4995.9
Exp/Cntr=0.3,0.1

Type RM Length L Ch R = 1,3997,424,424,424
BEGIN DESCRIPTION:
SANDIES TRIBUTARY 9 9.0
END DESCRIPTION:
XS GIS Cut Line= 3
      2326275.00     13696425.00      2326675.00     13696075.00
      2326975.00     13695675.00
#Sta/Elev= 30
  4463.7  522.09  4516.1  519.73  4634.1  515.10  4824.8  511.31  4895.5  508.59
  4924.5  507.25  4938.7  507.22  4967.2  505.16  4989.5  502.60  4989.9  502.10
  4993.9  502.10  4994.2  502.60  4998.3  502.60  5017.1  504.96  5045.2  507.32
  5091.5  510.66  5123.3  512.82  5167.1  514.57  5231.7  518.52  5267.1  521.40
  5281.7  522.05  5308.7  525.34  5345.2  527.10  5402.5  532.32  5413.4  532.65
  5423.3  532.92  5431.7  533.91  5437.9  535.76  5445.2  535.50  5495.2  539.31
#Mann=7,-1,0
  4463.7    0.12       0  4516.1   0.035       0  4895.5    0.07       0
  4989.5    0.05       0  4994.2    0.07       0  5091.5    0.12       0
  5413.4    0.07       0
Bank Sta=4989.5,4994.2
Exp/Cntr=0.3,0.1

Type RM Length L Ch R = 1,3573,444,444,444
BEGIN DESCRIPTION:
SANDIES TRIBUTARY 9 8.0
END DESCRIPTION:
XS GIS Cut Line= 3
      2326275.04     13696524.99      2327025.00     13696275.00
      2327125.02     13695974.95
#Sta/Elev= 30
  4209.2  525.59  4240.8  524.81  4261.9  522.84  4373.7  516.82  4514.8  512.72
  4723.9  510.46  4746.7  509.34  4757.3  509.94  4767.8  509.17  4788.9  510.22
  4862.7  508.84  4873.2  507.64  4883.8  508.45  4894.3  507.65  4910.2  507.95
  4947.0  505.77  4957.6  503.61  4978.6  502.06  4994.7  498.76  4995.1  498.26
  4999.4  498.76  5010.3  499.01  5041.9  503.62  5115.7  510.15  5126.2  511.77
  5221.1  517.93  5231.6  518.77  5242.2  520.83  5279.7  523.97  5316.0  526.43
#Mann=7,-1,0
  4209.2    0.12       0  4373.7    0.07       0  4723.9   0.035       0
  4910.2    0.07       0  4994.7    0.05       0  4999.4    0.07       0
  5279.7    0.07       0
Bank Sta=4994.7,4999.4
Exp/Cntr=0.3,0.1

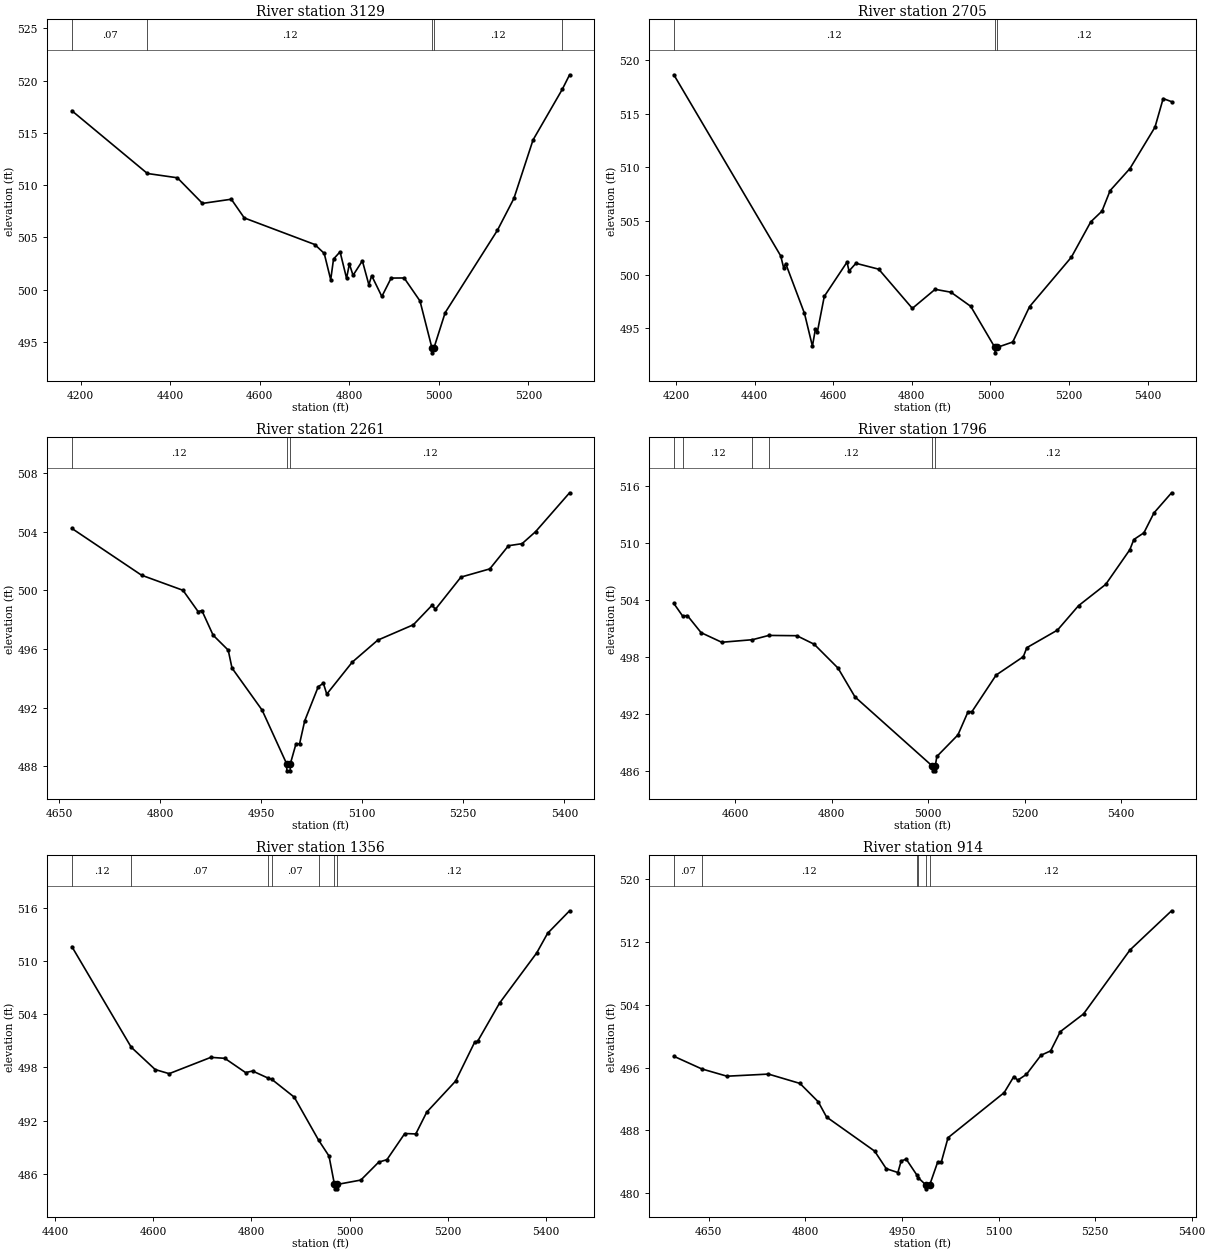
Type RM Length L Ch R = 1,3129,424,424,424
BEGIN DESCRIPTION:
SANDIES TRIBUTARY 9 7.0
END DESCRIPTION:
XS GIS Cut Line= 3
      2326675.00     13697075.00      2327325.00     13696575.00
      2327475.00     13696325.00
#Sta/Elev= 30
  4180.2  517.11  4348.9  511.11  4415.8  510.70  4471.9  508.25  4536.3  508.65
  4565.3  506.86  4722.7  504.32  4743.8  503.47  4758.3  500.95  4764.6  502.93
  4779.2  503.62  4793.7  501.09  4800.0  502.46  4808.2  501.37  4829.0  502.76
  4843.5  500.47  4849.8  501.34  4872.5  499.35  4893.3  501.11  4922.3  501.12
  4957.7  498.92  4984.2  494.46  4984.6  493.96  4989.1  494.46  5013.9  497.80
  5130.5  505.67  5167.4  508.72  5210.2  514.32  5275.5  519.16  5291.8  520.55
#Mann=5,-1,0
  4180.2    0.07       0  4348.9    0.12       0  4984.2    0.05       0
  4989.1    0.12       0  5275.5   0.035       0
Bank Sta=4984.2,4989.1
Exp/Cntr=0.3,0.1

Type RM Length L Ch R = 1,2705,444,444,444
BEGIN DESCRIPTION:
SANDIES TRIBUTARY 9 6.0
END DESCRIPTION:
XS GIS Cut Line= 3
      2327574.99     13697575.04      2327675.00     13696775.00
      2327974.97     13696425.04
#Sta/Elev= 30
  4194.0  518.65  4466.1  501.74  4473.7  500.60  4478.7  501.03  4526.6  496.37
  4546.8  493.31  4554.3  494.89  4559.4  494.64  4577.0  497.96  4634.9  501.16
  4640.0  500.33  4657.6  501.05  4715.6  500.50  4801.2  496.84  4859.2  498.62
  4899.5  498.35  4949.9  497.03  5011.4  493.19  5011.8  492.69  5016.5  493.19
  5056.8  493.70  5099.6  497.00  5206.1  501.62  5255.5  504.92  5284.0  505.92
  5304.8  507.84  5355.3  509.90  5419.0  513.76  5439.8  516.43  5461.2  516.14
#Mann=3,-1,0
  4194.0    0.12       0  5011.4    0.05       0  5016.5    0.12       0
Bank Sta=5011.4,5016.5
Exp/Cntr=0.3,0.1

Type RM Length L Ch R = 1,2261,465,465,465
BEGIN DESCRIPTION:
SANDIES TRIBUTARY 9 5.0
END DESCRIPTION:
XS GIS Cut Line= 3
      2327875.00     13697324.99      2328025.00     13697025.00
      2327975.00     13696625.01
#Sta/Elev= 30
  4669.2  504.22  4772.6  501.03  4834.1  500.00  4856.5  498.55  4862.1  498.62
  4878.8  496.94  4901.2  495.92  4906.8  494.70  4951.5  491.83  4987.7  488.19
  4988.2  487.69  4993.0  487.69  4993.5  488.19  5001.8  489.54  5007.1  489.54
  5014.7  491.10  5034.8  493.43  5042.4  493.66  5047.4  492.92  5085.2  495.10
  5123.0  496.60  5175.9  497.65  5203.6  498.98  5208.7  498.71  5246.5  500.90
  5289.3  501.46  5317.0  503.04  5337.2  503.18  5357.3  504.00  5407.7  506.65
#Mann=3,-1,0
  4669.2    0.12       0  4987.7    0.05       0  4993.5    0.12       0
Bank Sta=4987.7,4993.5
Exp/Cntr=0.3,0.1

Type RM Length L Ch R = 1,1796,440,440,440
BEGIN DESCRIPTION:
SANDIES TRIBUTARY 9 4.0
END DESCRIPTION:
XS GIS Cut Line= 3
      2328124.97     13697475.03      2328475.00     13697075.00
      2328875.04     13696774.97
#Sta/Elev= 30
  4472.8  503.60  4491.0  502.28  4500.8  502.33  4529.3  500.53  4572.0  499.52
  4635.8  499.79  4669.6  500.24  4727.7  500.21  4763.7  499.31  4813.1  496.80
  4848.2  493.77  5008.6  486.49  5009.1  485.99  5014.1  485.99  5014.6  486.49
  5017.9  487.50  5061.6  489.77  5082.5  492.20  5090.8  492.23  5140.8  496.07
  5197.1  498.00  5204.4  498.95  5267.9  500.80  5311.6  503.37  5367.9  505.61
  5417.9  509.26  5426.2  510.33  5447.1  511.04  5467.9  513.13  5504.4  515.25
#Mann=6,-1,0
  4472.8    0.07       0  4491.0    0.12       0  4635.8    0.07       0
  4669.6    0.12       0  5008.6    0.05       0  5014.6    0.12       0
Bank Sta=5008.6,5014.6
Exp/Cntr=0.3,0.1

Type RM Length L Ch R = 1,1356,442,442,442
BEGIN DESCRIPTION:
SANDIES TRIBUTARY 9 3.0
END DESCRIPTION:
XS GIS Cut Line= 3
      2328374.97     13697775.03      2328775.00     13697375.00
      2329174.97     13697175.02
#Sta/Elev= 30
  4434.5  511.62  4555.2  500.28  4604.2  497.75  4632.5  497.29  4717.4  499.13
  4745.7  499.02  4788.1  497.41  4802.2  497.59  4834.2  496.78  4841.6  496.64
  4887.1  494.64  4936.5  489.80  4957.8  488.00  4968.9  484.80  4969.4  484.30
  4974.4  484.30  4974.9  484.80  5022.6  485.29  5058.9  487.31  5075.7  487.59
  5112.0  490.54  5134.4  490.49  5156.7  492.95  5215.4  496.45  5254.6  500.88
  5260.2  500.93  5304.9  505.25  5380.4  510.90  5402.7  513.12  5447.4  515.66
#Mann=7,-1,0
  4434.5    0.12       0  4555.2    0.07       0  4834.2    0.12       0
  4841.6    0.07       0  4936.5    0.12       0  4968.9    0.05       0
  4974.9    0.12       0
Bank Sta=4968.9,4974.9
Exp/Cntr=0.3,0.1

Type RM Length L Ch R = 1,914,432,432,432
BEGIN DESCRIPTION:
SANDIES TRIBUTARY 9 2.0
END DESCRIPTION:
XS GIS Cut Line= 3
      2328725.00     13697725.00      2329125.00     13697625.00
      2329325.02     13697324.97
#Sta/Elev= 30
  4595.8  497.44  4639.1  495.83  4678.3  494.90  4742.7  495.17  4791.6  493.98
  4820.0  491.64  4832.9  489.70  4907.6  485.35  4925.6  483.11  4943.7  482.62
  4948.8  484.09  4956.6  484.33  4973.4  482.27  4975.3  481.96  4987.1  481.04
  4987.6  480.54  4993.1  481.04  5005.5  483.95  5011.1  483.95  5021.6  487.06
  5108.8  492.81  5123.8  494.86  5129.8  494.39  5143.3  495.13  5165.9  497.57
  5180.9  498.13  5195.9  500.58  5232.0  502.84  5304.1  510.99  5368.7  515.99
#Mann=6,-1,0
  4595.8    0.07       0  4639.1    0.12       0  4973.4    0.07       0
  4975.3    0.12       0  4987.1    0.05       0  4993.1    0.12       0
Bank Sta=4987.1,4993.1
Exp/Cntr=0.3,0.1

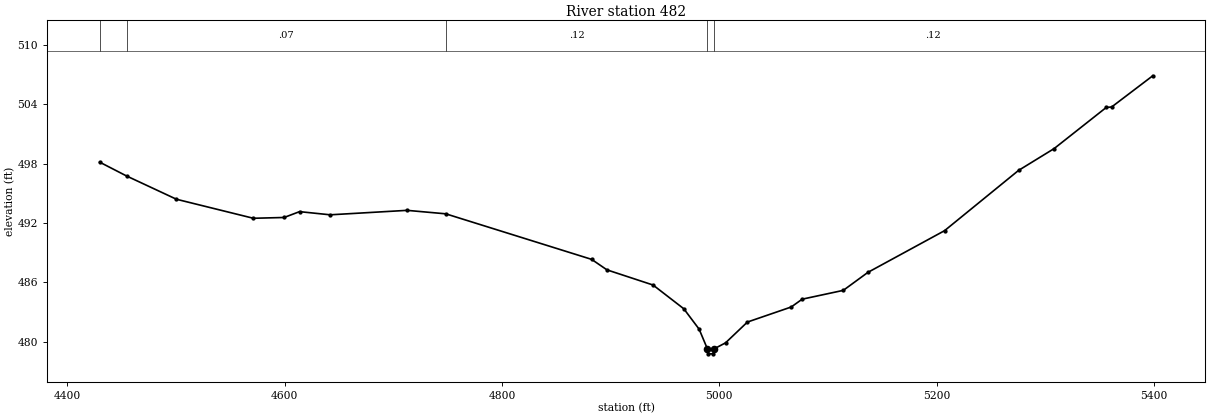
Type RM Length L Ch R = 1,482,0,0,0
BEGIN DESCRIPTION:
SANDIES TRIBUTARY 9 1.0
END DESCRIPTION:
XS GIS Cut Line= 3
      2328975.00     13698275.00      2329375.00     13697875.00
      2329425.00     13697475.00
#Sta/Elev= 30
  4429.9  498.14  4454.7  496.74  4500.6  494.39  4571.3  492.47  4599.6  492.55
  4613.8  493.14  4642.0  492.82  4712.7  493.27  4748.3  492.92  4882.5  488.32
  4896.6  487.26  4939.0  485.73  4967.3  483.33  4981.4  481.27  4989.0  479.28
  4989.5  478.78  4994.6  478.78  4995.1  479.28  5005.7  479.89  5025.8  481.99
  5066.1  483.51  5076.2  484.30  5114.0  485.19  5136.7  487.01  5207.2  491.22
  5275.2  497.30  5308.0  499.51  5355.9  503.66  5360.9  503.71  5398.7  506.86
#Mann=5,-1,0
  4429.9    0.12       0  4454.7    0.07       0  4748.3    0.12       0
  4989.0    0.05       0  4995.1    0.12       0
Bank Sta=4989,4995.1
Exp/Cntr=0.3,0.1

Chan Stop Cuts=-1