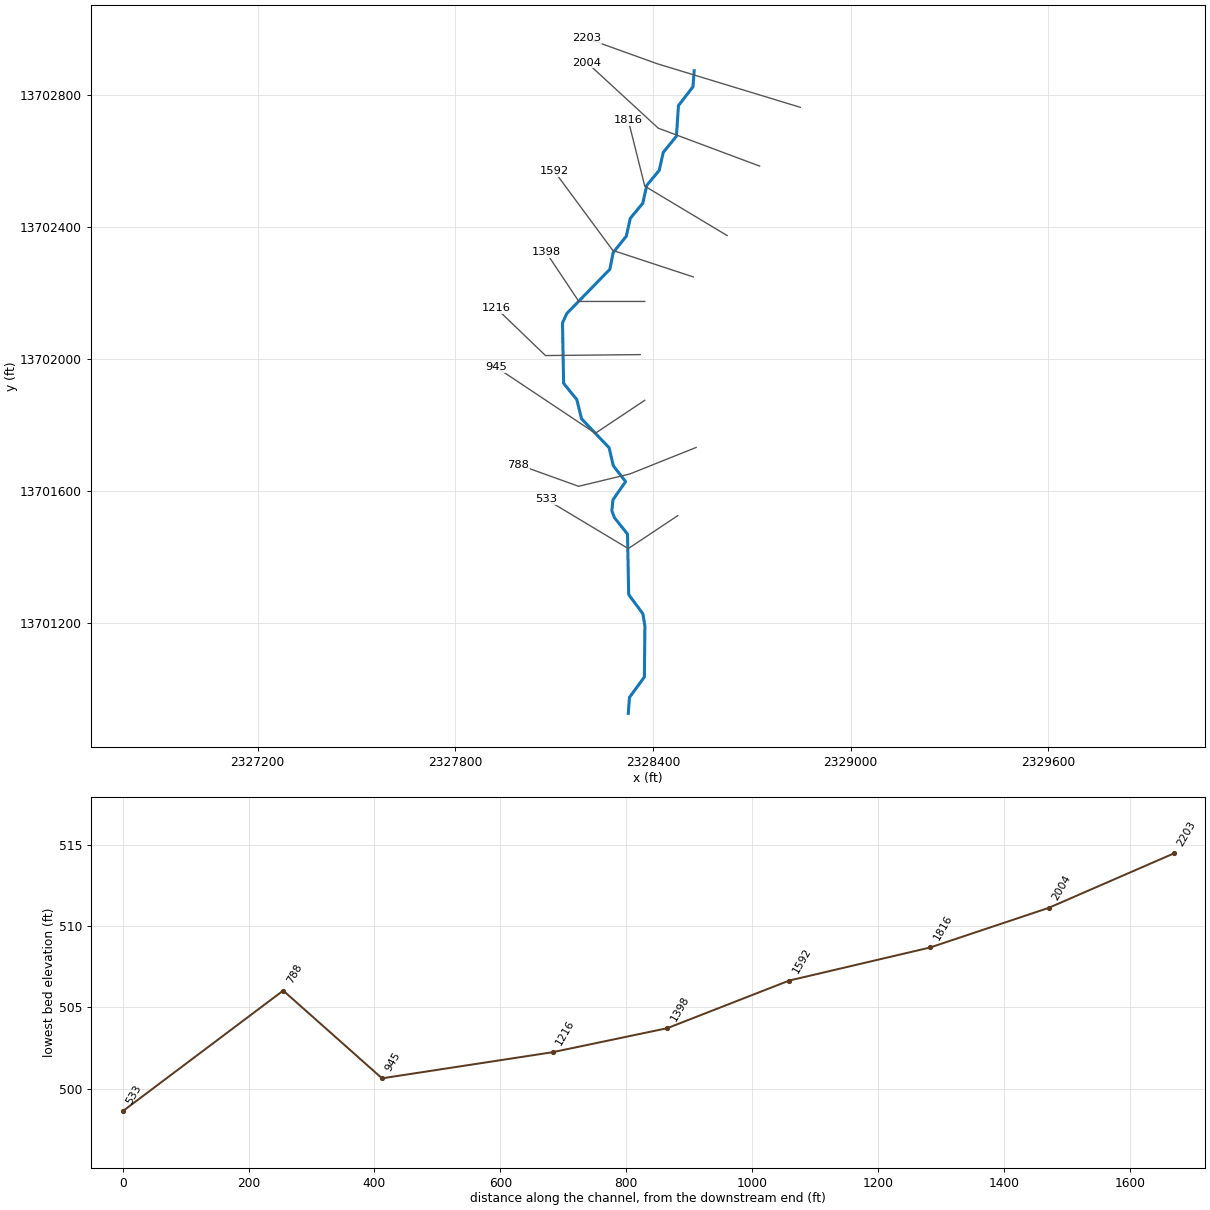
--- SANDIES TRIBUTARY 9B.prj (project) ---

Proj Title=SANDIES TRIBUTARY 9B Base Level Engineering
Current Plan=p01
Default Exp/Contr=0.3,0.1
English Units
Geom File=g01
Flow File=f01
Plan File=p01
BEGIN DESCRIPTION:
SANDIES TRIBUTARY 9B
END DESCRIPTION:

--- SANDIES TRIBUTARY 9B.p01 (plan) ---

Plan Title=Multiple Run
Short Identifier=Multiple
Geom File=g01
Flow File=f01
Subcritical Flow
K Sum by GR= 0
Std Step Tol= 0.01
Critical Tol= 0.01
Num of Std Step Trials= 20
Max Error Tol= 0.3
Flow Tol Ratio= 0.001
Split Flow NTrial= 30
Split Flow Tol= 0.02
Split Flow Ratio= 0.02
Log Output Level= 0
Friction Slope Method= 1
Unsteady Friction Slope Method= 2
Unsteady Bridges Friction Slope Method= 1
Parabolic Critical Depth
Global Vel Dist=  1 , 1 , 1
Global Log Level= 0
CheckData=True
Encroach Param= -1, 0, 0, 0
BEGIN DESCRIPTION:
Multiple Run
END DESCRIPTION:

--- SANDIES TRIBUTARY 9B.f01 (steady flow) ---

Flow Title=Multiple
Number of Profiles=7
Profile Names=10-year,25-year,50-year,1pct_min,100-year,1pct_plu,500-year
River Rch & RM= SANDIES TRIBUTAR,Reach-1,2203
     220     335     433     273     545    1087     850
Boundary for River Rch & Prof#=SANDIES TRIBUTAR,Reach-1,1
Up Type=0
Dn Type=3
Dn Slope=0.005
Boundary for River Rch & Prof#=SANDIES TRIBUTAR,Reach-1,2
Up Type=0
Dn Type=3
Dn Slope=0.005
Boundary for River Rch & Prof#=SANDIES TRIBUTAR,Reach-1,3
Up Type=0
Dn Type=3
Dn Slope=0.005
Boundary for River Rch & Prof#=SANDIES TRIBUTAR,Reach-1,4
Up Type=0
Dn Type=3
Dn Slope=0.005
Boundary for River Rch & Prof#=SANDIES TRIBUTAR,Reach-1,5
Up Type=0
Dn Type=3
Dn Slope=0.005
Boundary for River Rch & Prof#=SANDIES TRIBUTAR,Reach-1,6
Up Type=0
Dn Type=3
Dn Slope=0.005
Boundary for River Rch & Prof#=SANDIES TRIBUTAR,Reach-1,7
Up Type=0
Dn Type=3
Dn Slope=0.005

--- SANDIES TRIBUTARY 9B.g01 (geometry) ---

Geom Title=Existing Conditions

River Reach=SANDIES TRIBUTAR,Reach-1
Reach XY= 30
      2328525.00     13702875.00      2328521.36     13702826.51
      2328477.23     13702769.08      2328471.18     13702676.58
      2328431.12     13702627.18      2328418.92     13702572.80
      2328381.08     13702527.20      2328368.92     13702472.80
      2328331.08     13702427.20      2328318.92     13702372.80
      2328279.19     13702323.26      2328269.17     13702272.70
      2328138.37     13702138.32      2328125.38     13702109.84
      2328128.75     13701926.55      2328168.86     13701877.17
      2328183.16     13701818.95      2328266.86     13701731.04
      2328279.45     13701676.65      2328316.93     13701628.31
      2328278.61     13701573.36      2328275.15     13701540.42
      2328282.83     13701519.09      2328322.71     13701469.07
      2328326.22     13701285.51      2328369.25     13701227.33
      2328375.43     13701190.18      2328373.88     13701035.46
      2328328.65     13700973.49      2328325.00     13700925.00

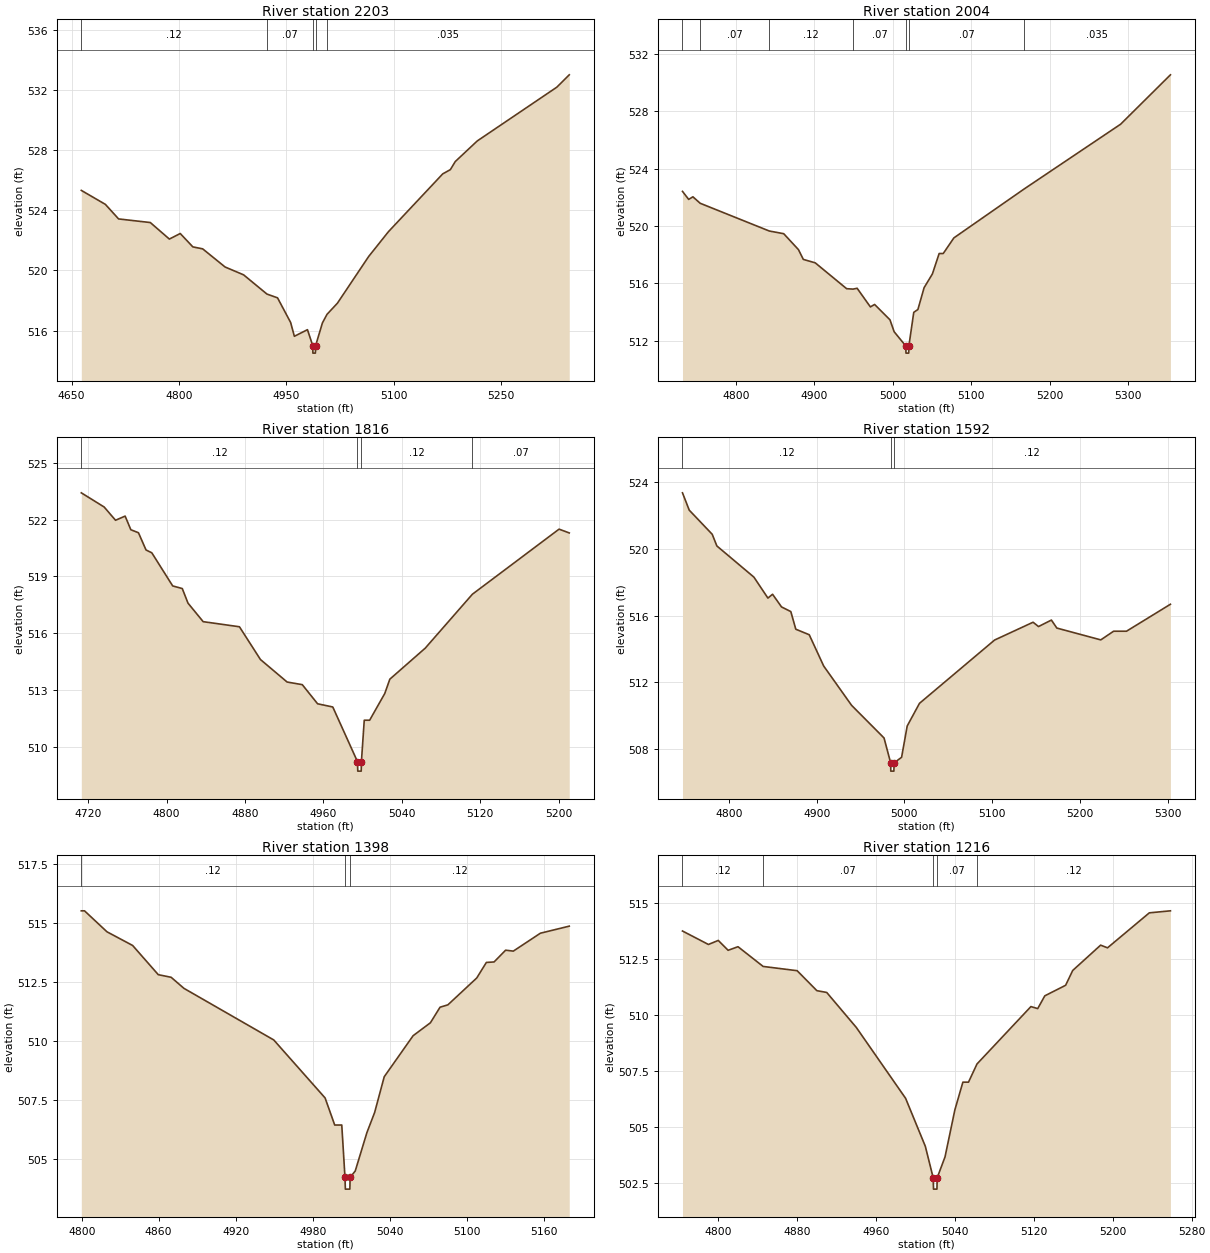
Type RM Length L Ch R = 1,2203,199,199,199
BEGIN DESCRIPTION:
21646
END DESCRIPTION:
XS GIS Cut Line= 3
      2328847.18     13702764.01      2328413.04     13702896.26
      2328198.74     13702973.41
#Sta/Elev= 30
  4663.6  525.33  4697.2  524.40  4715.7  523.43  4760.0  523.19  4786.6  522.09
  4801.8  522.46  4819.4  521.57  4833.1  521.44  4864.5  520.23  4890.3  519.71
  4922.9  518.43  4937.7  518.18  4956.0  516.54  4961.2  515.62  4979.5  516.06
  4986.9  515.00  4987.1  514.50  4990.6  514.50  4990.9  515.00  5000.4  516.51
  5006.8  517.08  5021.3  517.82  5065.0  520.93  5092.6  522.58  5168.5  526.43
  5179.1  526.71  5186.0  527.25  5216.7  528.62  5327.9  532.20  5345.2  533.02
#Mann=5,-1,0
  4663.6    0.12       0  4922.9    0.07       0  4986.9    0.05       0
  4990.9    0.07       0  5006.8   0.035       0
Bank Sta=4986.9,4990.9
Exp/Cntr=0.3,0.1

Type RM Length L Ch R = 1,2004,188,188,188
BEGIN DESCRIPTION:
21645
END DESCRIPTION:
XS GIS Cut Line= 3
      2328723.56     13702585.76      2328415.92     13702700.77
      2328199.84     13702899.79
#Sta/Elev= 30
  4731.7  522.41  4739.6  521.85  4745.0  522.03  4754.3  521.58  4842.3  519.65
  4860.8  519.46  4879.6  518.35  4885.8  517.67  4901.0  517.43  4941.0  515.63
  4949.2  515.60  4954.4  515.66  4971.3  514.36  4976.7  514.53  4996.3  513.46
  5001.6  512.63  5016.4  511.64  5016.7  511.14  5020.2  511.14  5020.4  511.64
  5026.6  513.98  5031.9  514.18  5039.8  515.70  5050.4  516.66  5059.0  518.08
  5064.2  518.08  5077.8  519.17  5167.2  522.57  5290.4  527.09  5353.9  530.53
#Mann=7,-1,0
  4731.7    0.12       0  4754.3    0.07       0  4842.3    0.12       0
  4949.2    0.07       0  5016.4    0.05       0  5020.4    0.07       0
  5167.2   0.035       0
Bank Sta=5016.4,5020.4
Exp/Cntr=0.3,0.1

Type RM Length L Ch R = 1,1816,224,224,224
BEGIN DESCRIPTION:
SANDIES TRIBUTARY 9B 4.0
END DESCRIPTION:
XS GIS Cut Line= 3
      2328624.96     13702375.02      2328375.00     13702525.00
      2328324.99     13702725.04
#Sta/Elev= 30
  4713.1  523.41  4736.4  522.66  4748.0  521.96  4757.8  522.18  4763.6  521.46
  4771.4  521.30  4779.1  520.39  4785.0  520.24  4806.3  518.49  4816.1  518.35
  4821.9  517.58  4837.4  516.60  4874.4  516.33  4895.8  514.60  4923.0  513.41
  4938.5  513.27  4954.1  512.26  4969.6  512.09  4994.8  509.20  4995.1  508.70
  4998.6  508.70  4998.8  509.20  5001.7  511.39  5007.2  511.39  5022.6  512.80
  5027.8  513.56  5063.9  515.20  5112.0  518.05  5200.4  521.49  5210.8  521.29
#Mann=4,-1,0
  4713.1    0.12       0  4994.8    0.05       0  4998.8    0.12       0
  5112.0    0.07       0
Bank Sta=4994.8,4998.8
Exp/Cntr=0.3,0.1

Type RM Length L Ch R = 1,1592,194,194,194
BEGIN DESCRIPTION:
21644
END DESCRIPTION:
XS GIS Cut Line= 3
      2328522.27     13702249.42      2328277.93     13702329.91
      2328100.34     13702570.51
#Sta/Elev= 30
  4747.0  523.37  4754.7  522.33  4780.9  520.88  4786.2  520.18  4828.4  518.31
  4844.4  517.05  4849.7  517.28  4859.9  516.52  4870.5  516.24  4876.2  515.18
  4891.5  514.85  4908.0  512.97  4939.8  510.61  4976.8  508.65  4984.3  507.16
  4984.5  506.66  4988.0  506.66  4988.3  507.16  4996.8  507.49  5003.2  509.37
  5017.2  510.73  5102.8  514.53  5146.7  515.60  5152.9  515.34  5167.6  515.73
  5173.8  515.25  5223.9  514.54  5238.5  515.06  5253.2  515.06  5303.3  516.68
#Mann=3,-1,0
  4747.0    0.12       0  4984.3    0.05       0  4988.3    0.12       0
Bank Sta=4984.3,4988.3
Exp/Cntr=0.3,0.1

Type RM Length L Ch R = 1,1398,182,182,182
BEGIN DESCRIPTION:
SANDIES TRIBUTARY 9B 3.0
END DESCRIPTION:
XS GIS Cut Line= 3
      2328375.02     13702175.00      2328175.00     13702175.00
      2328075.00     13702325.00
#Sta/Elev= 30
  4799.7  515.53  4802.2  515.53  4819.7  514.64  4839.7  514.06  4859.7  512.82
  4869.7  512.71  4879.7  512.24  4949.7  510.05  4989.7  507.59  4997.2  506.44
  5002.7  506.44  5005.2  504.22  5005.5  503.72  5009.0  503.72  5009.2  504.22
  5013.2  504.49  5022.3  506.12  5028.3  506.97  5035.8  508.49  5058.3  510.23
  5071.8  510.78  5079.3  511.44  5085.4  511.54  5107.9  512.68  5115.4  513.34
  5121.4  513.36  5130.4  513.86  5136.4  513.82  5157.5  514.58  5180.0  514.88
#Mann=3,-1,0
  4799.7    0.12       0  5005.2    0.05       0  5009.2    0.12       0
Bank Sta=5005.2,5009.2
Exp/Cntr=0.3,0.1

Type RM Length L Ch R = 1,1216,271,271,271
BEGIN DESCRIPTION:
21643
END DESCRIPTION:
XS GIS Cut Line= 3
      2328361.30     13702013.68      2328073.81     13702010.80
      2327924.31     13702154.56
#Sta/Elev= 30
  4763.5  513.75  4789.8  513.15  4799.8  513.33  4809.8  512.89  4819.8  513.05
  4845.3  512.17  4879.8  511.98  4899.8  511.09  4909.8  511.01  4939.8  509.45
  4989.8  506.29  5009.8  504.15  5017.8  502.74  5018.1  502.24  5021.6  502.24
  5021.8  502.74  5029.8  503.68  5039.8  505.78  5047.9  507.01  5053.6  507.01
  5062.2  507.82  5116.9  510.38  5123.8  510.29  5131.0  510.86  5152.1  511.33
  5159.3  511.99  5187.6  513.12  5194.6  513.00  5237.0  514.56  5258.4  514.65
#Mann=5,-1,0
  4763.5    0.12       0  4845.3    0.07       0  5017.8    0.05       0
  5021.8    0.07       0  5062.2    0.12       0
Bank Sta=5017.8,5021.8
Exp/Cntr=0.3,0.1

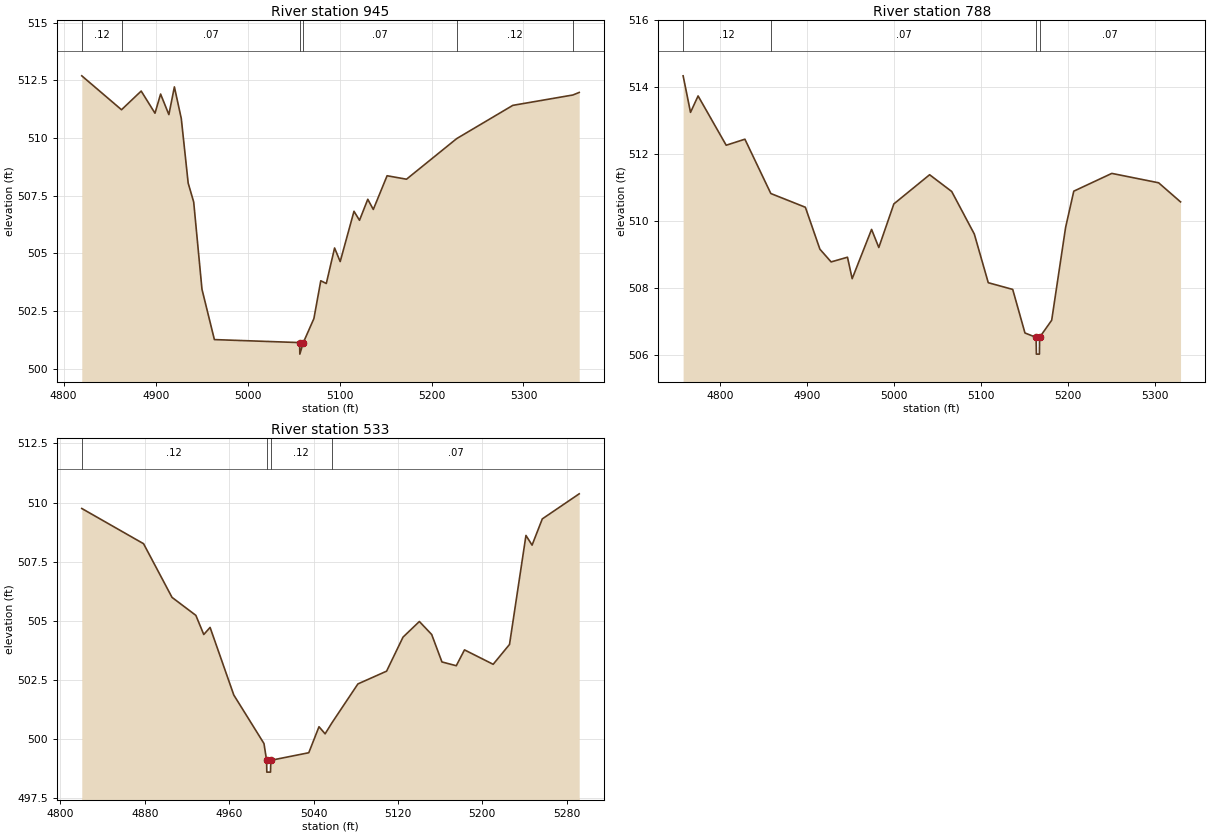
Type RM Length L Ch R = 1,945,157,157,157
BEGIN DESCRIPTION:
SANDIES TRIBUTARY 9B 2.0
END DESCRIPTION:
XS GIS Cut Line= 3
      2328375.02     13701875.01      2328225.00     13701775.00
      2327924.96     13701975.02
#Sta/Elev= 30
  4819.7  512.69  4862.9  511.22  4884.3  512.03  4899.3  511.07  4905.4  511.90
  4914.4  511.01  4920.4  512.21  4927.9  510.84  4935.4  508.04  4941.4  507.22
  4950.4  503.44  4963.9  501.26  5056.6  501.13  5056.8  500.63  5060.6  501.13
  5072.1  502.17  5079.6  503.81  5085.6  503.69  5094.6  505.23  5100.7  504.64
  5115.7  506.82  5121.7  506.43  5130.7  507.34  5136.7  506.90  5151.7  508.36
  5172.8  508.21  5227.4  509.97  5288.4  511.41  5353.8  511.86  5360.6  511.97
#Mann=6,-1,0
  4819.7    0.12       0  4862.9    0.07       0  5056.6    0.05       0
  5060.6    0.07       0  5227.4    0.12       0  5353.8    0.07       0
Bank Sta=5056.6,5060.6
Exp/Cntr=0.3,0.1

Type RM Length L Ch R = 1,788,255,255,255
BEGIN DESCRIPTION:
21642
END DESCRIPTION:
XS GIS Cut Line= 4
      2328530.95     13701731.96      2328329.67     13701651.45
      2328174.43     13701614.08      2327990.69     13701680.11
#Sta/Elev= 30
  4757.6  514.34  4766.1  513.25  4774.8  513.74  4807.1  512.27  4828.6  512.45
  4858.4  510.83  4898.1  510.42  4914.8  509.17  4927.7  508.79  4946.5  508.93
  4951.9  508.29  4974.2  509.76  4982.5  509.22  4999.8  510.52  5040.9  511.39
  5066.3  510.89  5092.3  509.62  5108.3  508.17  5136.4  507.97  5150.5  506.67
  5163.3  506.54  5163.6  506.04  5167.1  506.04  5167.3  506.54  5181.2  507.05
  5197.2  509.82  5206.6  510.90  5250.3  511.43  5304.1  511.15  5329.3  510.58
#Mann=4,-1,0
  4757.6    0.12       0  4858.4    0.07       0  5163.3    0.05       0
  5167.3    0.07       0
Bank Sta=5163.3,5167.3
Exp/Cntr=0.3,0.1

Type RM Length L Ch R = 1,533,0,0,0
BEGIN DESCRIPTION:
SANDIES TRIBUTARY 9B 1.0
END DESCRIPTION:
XS GIS Cut Line= 3
      2328474.99     13701525.00      2328325.00     13701425.00
      2328075.01     13701574.99
#Sta/Elev= 30
  4820.2  509.75  4878.8  508.26  4905.8  505.99  4928.4  505.23  4935.9  504.42
  4941.9  504.72  4964.4  501.86  4993.0  499.81  4995.5  499.10  4995.7  498.60
  4999.2  498.60  4999.5  499.10  5035.5  499.42  5045.2  500.52  5051.0  500.22
  5057.4  500.68  5082.1  502.33  5109.3  502.87  5124.9  504.31  5140.4  504.97
  5152.1  504.42  5161.8  503.26  5175.4  503.10  5183.2  503.77  5210.4  503.16
  5225.9  504.00  5241.5  508.61  5247.3  508.20  5257.0  509.31  5292.0  510.37
#Mann=4,-1,0
  4820.2    0.12       0  4995.5    0.05       0  4999.5    0.12       0
  5057.4    0.07       0
Bank Sta=4995.5,4999.5
Exp/Cntr=0.3,0.1

Chan Stop Cuts=-1