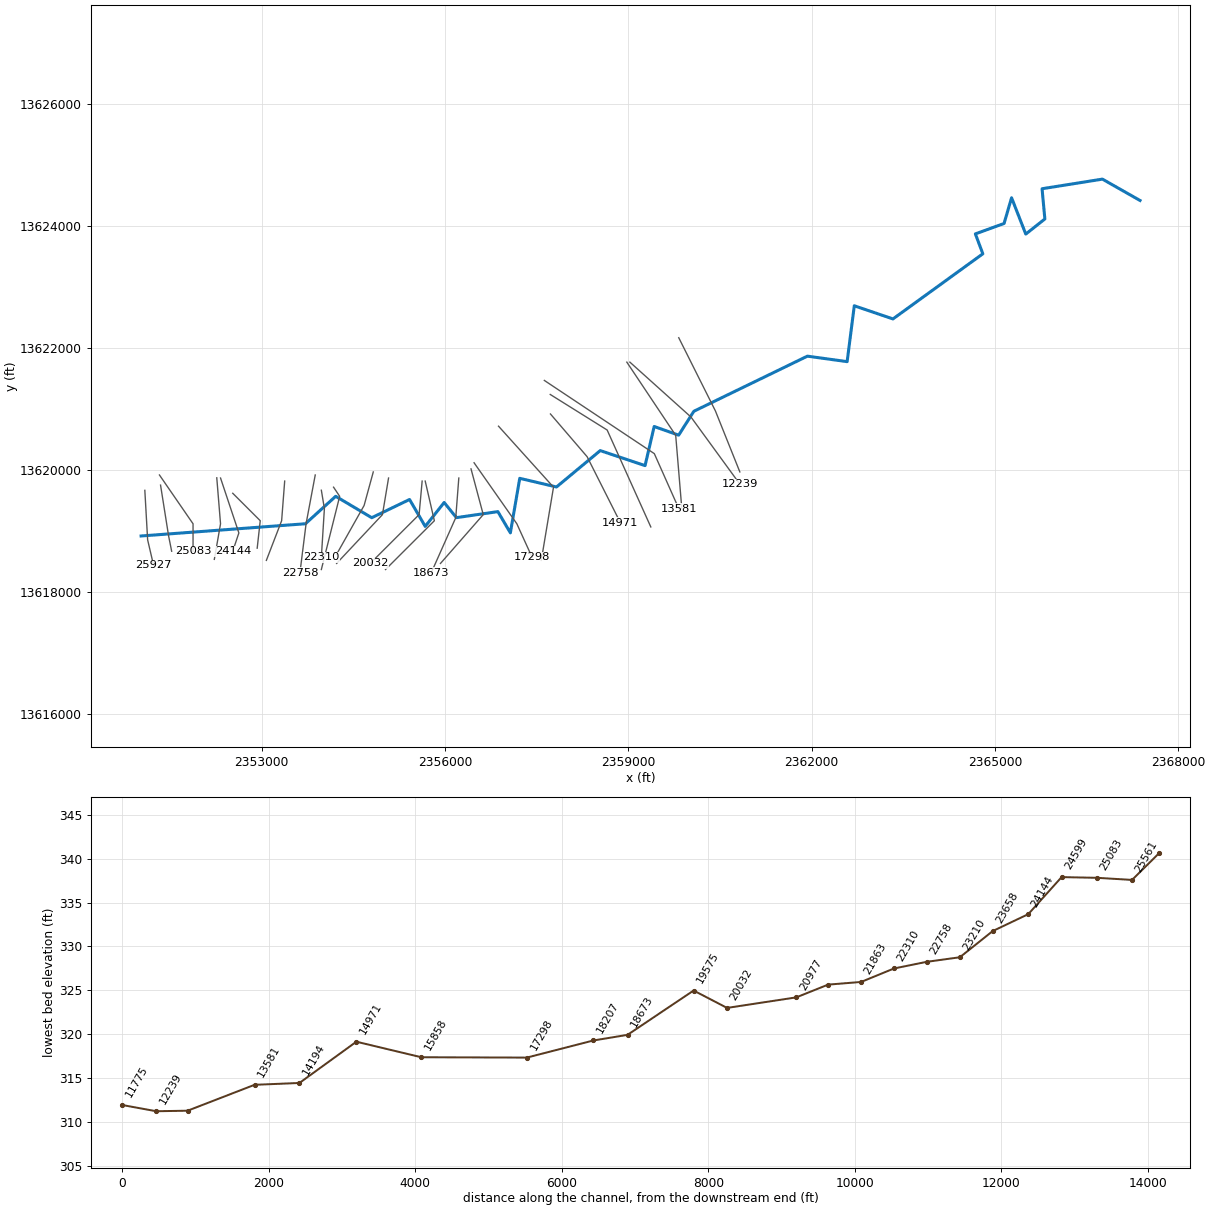
--- SHOCKLEY CREEK.prj (project) ---

Proj Title=SHOCKLEY CREEK Base Level Engineering
Current Plan=p01
Default Exp/Contr=0.3,0.1
English Units
Geom File=g01
Flow File=f01
Plan File=p01
Y Axis Title=Elevation
X Axis Title(PF)=Main Channel Distance
X Axis Title(XS)=Station
BEGIN DESCRIPTION:
SHOCKLEY CREEK
END DESCRIPTION:
DSS Export Rating Curves= 0
DSS Export Rating Curve Sorted= 0
DSS Export Volume Flow Curves= 0
DXF OffsetX= 0
DXF OffsetY= 0
DXF ScaleX= 1
DXF ScaleY= 10

--- SHOCKLEY CREEK.p01 (plan) ---

Plan Title=Multiple Run
Program Version=4.10
Short Identifier=Multiple
Geom File=g01
Flow File=f01
Subcritical Flow
K Sum by GR= 0
Std Step Tol= 0.01
Critical Tol= 0.01
Num of Std Step Trials= 20
Max Error Tol= 0.3
Flow Tol Ratio= 0.001
Split Flow NTrial= 30
Split Flow Tol= 0.02
Split Flow Ratio= 0.02
Log Output Level= 0
Friction Slope Method= 1
Unsteady Friction Slope Method= 2
Unsteady Bridges Friction Slope Method= 1
Parabolic Critical Depth
Global Vel Dist= 1 , 1 , 1
Global Log Level= 0
CheckData=True
Encroach Param=-1 ,0,0, 0
BEGIN DESCRIPTION:
Multiple Run
END DESCRIPTION:
Computation Interval=1HOUR
Output Interval=1HOUR
Run HTab= 0
Run UNet= 0
Run PostProcess= 0
Run WQNet= 0
UNET Theta= 1
UNET Theta Warmup= 1
UNET ZTol= 0.02
UNET ZSATol= 0.05
UNET MxIter= 20
UNET MaxInSteps= 0
UNET DtIC= 0
UNET DtMin= 0
UNET MaxCRTS= 20
UNET WFStab= 2
UNET SFStab= 1
UNET WFX= 1
UNET SFX= 1
UNET DSS MLevel= 4
UNET DZMax Abort= 100
UNET Convert EG Bridges= 0
UNET Use Existing IB Tables=-1
UNET Froude Reduction=False
UNET Froude Limit= 1
UNET Froude Power= 10
UNET Time Slicing=0,0, 5
UNET Junction Losses=0
Instantaneous Interval=1HOUR
Write IC File= 0
Write IC File at Sim End=0
Echo Input=False
Echo Parameters=False
Echo Output=False
Write Detailed= 0
WQ AD Non Conservative
WQ ULTIMATE=-1
WQ Max Comp Step=1HOUR
WQ Output Interval=15MIN
WQ Output Selected Increments= 0
WQ Output face flow=0
WQ Output face velocity=0
WQ Output face area=0
WQ Output face dispersion=0
WQ Output cell volume=0
WQ Output cell surface area=0
WQ Output cell continuity=0
WQ Output cumulative cell continuity=0
WQ Output face conc=0
WQ Output face dconc_dx=0
WQ Output face courant=0
WQ Output face peclet=0
WQ Output face adv mass=0
WQ Output face disp mass=0
WQ Output cell mass=0
WQ Output cell source sink temp=0
WQ Output cell source sink nsm=0
WQ Output MaxMinRange=-1
WQ Daily Max Min Mean=-1
WQ Daily Range=0
WQ Daily Time=0
WQ Create Restart=0
WQ Fixed Restart=0
WQ System Summary=0
WQ Use Fixed Temperature=0
Sorting and Armoring Iterations= 10
XS Update Threshold= 0.02
Hydraulics Update Threshold= 0.02
Energy Slope Method= 1
Volume Change Method= 0
XS Weighting Method= 0
Number of US Weighted Cross Sections= 1
Number of DS Weighted Cross Sections= 1
Upstream XS Weight=0.25
Main XS Weight=0.5
Downstream XS Weight=0.25
Number of DS XS's Weighted with US Boundary= 1
Upstream Boundary Weight= 1
Weight of XSs Associated with US Boundary= 0
Number of US XS's Weighted with DS Boundary= 1
Downstream Boundary Weight= 0.5
Weight of XSs Associated with DS Boundary= 0.5
Sediment Output Level= 4
Mass or Volume Output= 0
Output Increment Type= 1
Profile and TS Output Increment= 10
XS Output Flag= 0
XS Output Increment= 10
Disregard all LS=0
Disregard all Conn=0
Disregard all Breaches=0
Disregard all Pumps=0

--- SHOCKLEY CREEK.f01 (steady flow) ---

Flow Title=Multiple
Number of Profiles=7
Profile Names=10-year,25-year,50-year,1pct_min,100-year,1pct_plu,500-year
River Rch & RM= SHOCKLEY CREEK,Reach-1,25927
     766    1259    1711    1125    2244    4477    3829
River Rch & RM= SHOCKLEY CREEK,Reach-1,24144
    1105    1842    2527    1675    3341    6667    5798
River Rch & RM= SHOCKLEY CREEK,Reach-1,22758
    1264    2112    2902    1925    3840    7663    6674
River Rch & RM= SHOCKLEY CREEK,Reach-1,17298
    1937    3291    4571    3061    6107   12185   10820
River Rch & RM= SHOCKLEY CREEK,Reach-1,14971
    2201    3744    5203    3483    6950   13868   12310
River Rch & RM= SHOCKLEY CREEK,Reach-1,9076
    2308    3927    5462    3658    7298   14561   12933
River Rch & RM= SHOCKLEY CREEK,Reach-1,6874
    2351    3990    5538    3700    7383   14730   13023
Boundary for River Rch & Prof#=SHOCKLEY CREEK,Reach-1,1
Up Type=0
Dn Type=3
Dn Slope=0.005
Boundary for River Rch & Prof#=SHOCKLEY CREEK,Reach-1,2
Up Type=0
Dn Type=3
Dn Slope=0.005
Boundary for River Rch & Prof#=SHOCKLEY CREEK,Reach-1,3
Up Type=0
Dn Type=3
Dn Slope=0.005
Boundary for River Rch & Prof#=SHOCKLEY CREEK,Reach-1,4
Up Type=0
Dn Type=3
Dn Slope=0.005
Boundary for River Rch & Prof#=SHOCKLEY CREEK,Reach-1,5
Up Type=0
Dn Type=3
Dn Slope=0.005
Boundary for River Rch & Prof#=SHOCKLEY CREEK,Reach-1,6
Up Type=0
Dn Type=3
Dn Slope=0.005
Boundary for River Rch & Prof#=SHOCKLEY CREEK,Reach-1,7
Up Type=0
Dn Type=3
Dn Slope=0.005

--- SHOCKLEY CREEK.g01 (geometry) ---

Geom Title=Existing Conditions
Program Version=4.10

River Reach=SHOCKLEY CREEK  ,Reach-1
Reach XY= 30
        2351025.       13618925.      2353714.55     13619125.53
      2354209.75     13619575.55      2354799.88     13619224.68
      2355418.91     13619523.44      2355674.97     13619082.08
      2355985.25     13619474.03      2356185.43     13619225.53
      2356864.39     13619324.41      2357068.92     13618976.56
      2357222.42     13619870.05      2357823.78     13619728.43
      2358540.23     13620324.76      2359273.55     13620078.53
      2359422.56     13620719.61      2359823.58     13620578.04
       2360072.3     13620969.64      2361930.86     13621872.95
      2362581.08     13621783.13      2362698.13     13622698.85
      2363331.06     13622483.14      2364802.35     13623550.97
      2364680.05     13623877.28      2365149.48     13624047.84
      2365272.58     13624469.61      2365504.85     13623874.28
       2365817.4     13624121.66      2365771.65     13624617.41
      2366759.64     13624775.11        2367375.       13624425.

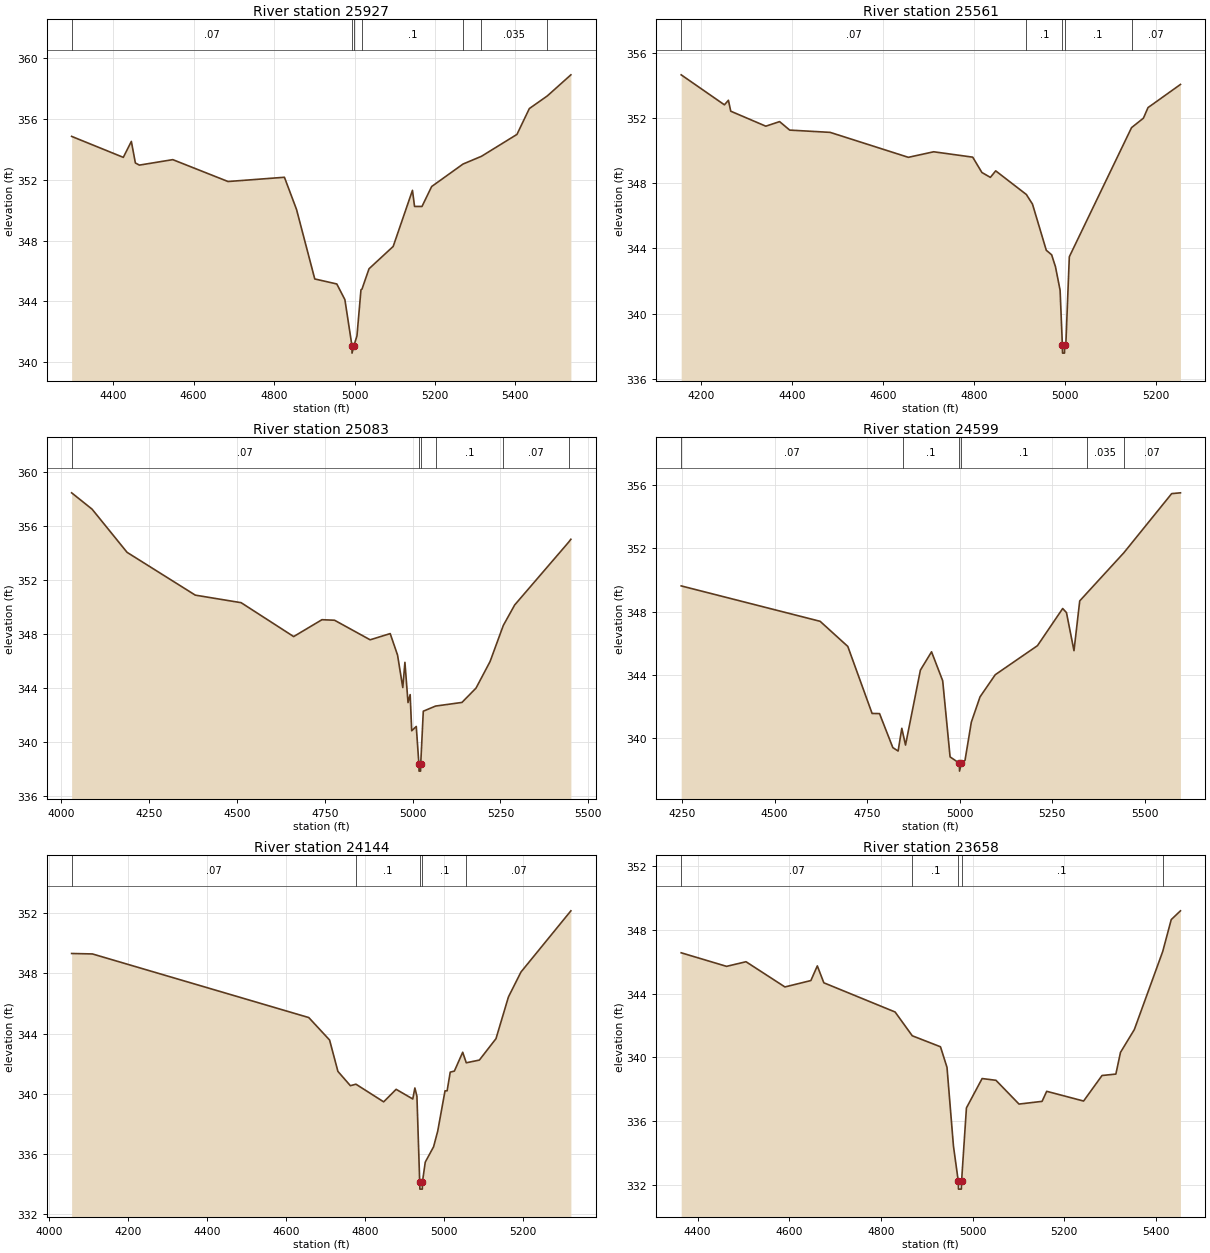
Type RM Length L Ch R = 1 ,25927   ,366,366,366
BEGIN DESCRIPTION:
E20828
END DESCRIPTION:
XS GIS Cut Line= 3
      2351085.98     13619673.28       2351131.7     13618861.69
      2351228.87     13618444.43
#Sta/Elev= 30
  4296.6  354.86  4425.1  353.48  4445.1  354.53  4455.1  353.11  4465.1  352.97
  4548.1  353.33  4685.5  351.89  4825.7  352.17  4855.8  350.05  4901.1  345.48
  4955.9  345.15    4976  344.12  4993.5   341.1  4993.8   340.6  4998.5   341.1
    5006  341.73    5016  344.77  5018.5  344.81    5036  346.15  5096.1  347.62
    5144  351.31  5149.2  350.25  5167.7  350.25  5191.7  351.56  5269.7  353.04
  5315.6  353.55  5403.8  354.99  5434.6  356.69  5479.2  357.52  5537.9  358.91
#Mann= 7 ,-1 , 0
  4296.6     .07       0  4993.5     .05       0  4998.5     .07       0
  5018.5      .1       0  5269.7     .07       0  5315.6    .035       0
  5479.2     .07       0
Bank Sta=4993.5,4998.5
XS Rating Curve= 0 ,0
Exp/Cntr=0.3,0.1

Type RM Length L Ch R = 1 ,25561   ,478,478,478
BEGIN DESCRIPTION:
SHOCKLEY CREEK 30.0
END DESCRIPTION:
XS GIS Cut Line= 3
      2351343.17     13619759.02        2351475.       13618925.
      2351524.99     13618675.03
#Sta/Elev= 30
  4155.6  354.65  4250.8  352.81  4259.6  353.09  4264.7  352.42  4341.9   351.5
  4372.3  351.78  4394.5  351.26  4483.6  351.12  4655.8  349.59  4711.6  349.93
  4797.5   349.6  4817.7  348.66  4836.4  348.36  4848.1  348.76  4915.6  347.31
  4929.1  346.72  4959.5  343.89  4971.3  343.61  4979.7  342.88  4989.9  341.44
  4994.9  338.08  4995.3  337.58  4999.6  337.58  4999.9  338.08  5002.5  338.08
  5010.2  343.49  5147.2  351.41  5173.3  351.99  5183.5  352.64  5254.9  354.06
#Mann= 5 ,-1 , 0
  4155.6     .07       0  4915.6      .1       0  4994.9     .05       0
  4999.9      .1       0  5147.2     .07       0
Bank Sta=4994.9,4999.9
XS Rating Curve= 0 ,0
Exp/Cntr=0.3,0.1

Type RM Length L Ch R = 1 ,25083   ,484,484,484
BEGIN DESCRIPTION:
SHOCKLEY CREEK 29.0
END DESCRIPTION:
XS GIS Cut Line= 3
        2351325.       13619925.        2351875.       13619125.
        2351875.     13618675.02
#Sta/Elev= 30
  4029.7  358.44  4087.9  357.23  4187.5  354.03  4381.6  350.86  4512.1   350.3
  4661.6  347.79  4742.1  349.04  4777.9     349  4879.2  347.55  4936.3  348.01
  4957.2  346.42  4972.1  344.01  4978.2  345.88    4987   342.9  4993.1  343.49
  4997.5  340.81  5010.5  341.13    5018  338.32  5018.4  337.82  5022.7  337.82
  5023.1  338.32  5030.5  342.26  5065.4  342.64  5140.5  342.91  5180.5  343.97
  5220.5  345.94  5258.1  348.61  5290.5  350.13  5444.3  354.79  5450.5     355
#Mann= 6 ,-1 , 0
  4029.7     .07       0    5018     .05       0  5023.1     .07       0
  5065.4      .1       0  5258.1     .07       0  5444.3    .035       0
Bank Sta=5018,5023.1
XS Rating Curve= 0 ,0
Exp/Cntr=0.3,0.1

Type RM Length L Ch R = 1 ,24599   ,455,455,455
BEGIN DESCRIPTION:
SHOCKLEY CREEK 28.0
END DESCRIPTION:
XS GIS Cut Line= 3
      2352263.35     13619879.02        2352325.       13619125.
      2352223.34     13618541.63
#Sta/Elev= 30
  4247.6  349.62  4622.9  347.38  4697.7  345.79  4763.3  341.55  4783.4  341.54
  4819.3  339.39  4833.6  339.17  4843.6  340.61  4846.6  340.29  4853.6  339.55
  4893.8  344.29  4923.9  345.45    4954  343.62    4974   338.8  4999.1   338.4
  4999.5   337.9  5004.2   338.4  5014.3  338.58  5031.4     341  5054.9   342.6
    5096     344  5210.1  345.84  5278.2  348.19  5288.4  347.93  5308.7  345.52
  5324.2  348.67  5342.9  349.15  5443.5  351.72  5572.6  355.46  5596.3  355.51
#Mann= 6 ,-1 , 0
  4247.6     .07       0  4846.6      .1       0  4999.1     .05       0
  5004.2      .1       0  5342.9    .035       0  5443.5     .07       0
Bank Sta=4999.1,5004.2
XS Rating Curve= 0 ,0
Exp/Cntr=0.3,0.1

Type RM Length L Ch R = 1 ,24144   ,486,486,486
BEGIN DESCRIPTION:
SHOCKLEY CREEK 27.0
END DESCRIPTION:
XS GIS Cut Line= 3
      2352324.99     13619875.04        2352625.       13618975.
      2352524.98     13618674.95
#Sta/Elev= 30
  4056.3  349.31    4109  349.28  4657.2  345.06  4709.9  343.57    4731  341.49
  4762.6  340.54  4776.7  340.64  4846.9  339.47  4878.5   340.3  4920.7  339.66
    4926  340.39  4931.2  339.84  4938.2  334.18  4938.7  333.68  4944.8  333.68
  4945.3  334.18  4952.3  335.47  4973.4  336.49  4983.9  337.53  5002.4   340.2
  5007.7   340.2  5015.6  341.44  5026.1  341.51  5047.2  342.76  5056.2  342.06
  5089.4  342.24  5131.5  343.66  5163.1  346.43  5194.8  348.08  5321.3  352.14
#Mann= 5 ,-1 , 0
  4056.3     .07       0  4776.7      .1       0  4938.2     .05       0
  4945.3      .1       0  5056.2     .07       0
Bank Sta=4938.2,4945.3
XS Rating Curve= 0 ,0
Exp/Cntr=0.3,0.1

Type RM Length L Ch R = 1 ,23658   ,448,448,448
BEGIN DESCRIPTION:
SHOCKLEY CREEK 26.0
END DESCRIPTION:
XS GIS Cut Line= 3
      2352524.98     13619625.02        2352975.       13619175.
        2352925.     13618724.99
#Sta/Elev= 30
  4364.2  346.56  4463.2  345.71  4505.6     346  4590.5  344.42  4647.1  344.82
  4661.2  345.74  4675.4  344.68  4830.9  342.85  4868.3  341.36  4929.9  340.67
  4944.1  339.38  4958.2  334.44  4968.7  332.25  4969.2  331.75  4975.4  331.75
  4975.9  332.25  4986.5  336.84  5020.7  338.68  5050.9  338.57  5101.2  337.08
  5151.5  337.25  5161.6  337.88  5242.1  337.27  5282.3  338.87  5312.5  338.96
  5322.6  340.32  5352.8  341.75  5414.7  346.64  5433.3  348.64  5453.4  349.19
#Mann= 5 ,-1 , 0
  4364.2     .07       0  4868.3      .1       0  4968.7     .05       0
  4975.9      .1       0  5414.7     .07       0
Bank Sta=4968.7,4975.9
XS Rating Curve= 0 ,0
Exp/Cntr=0.3,0.1

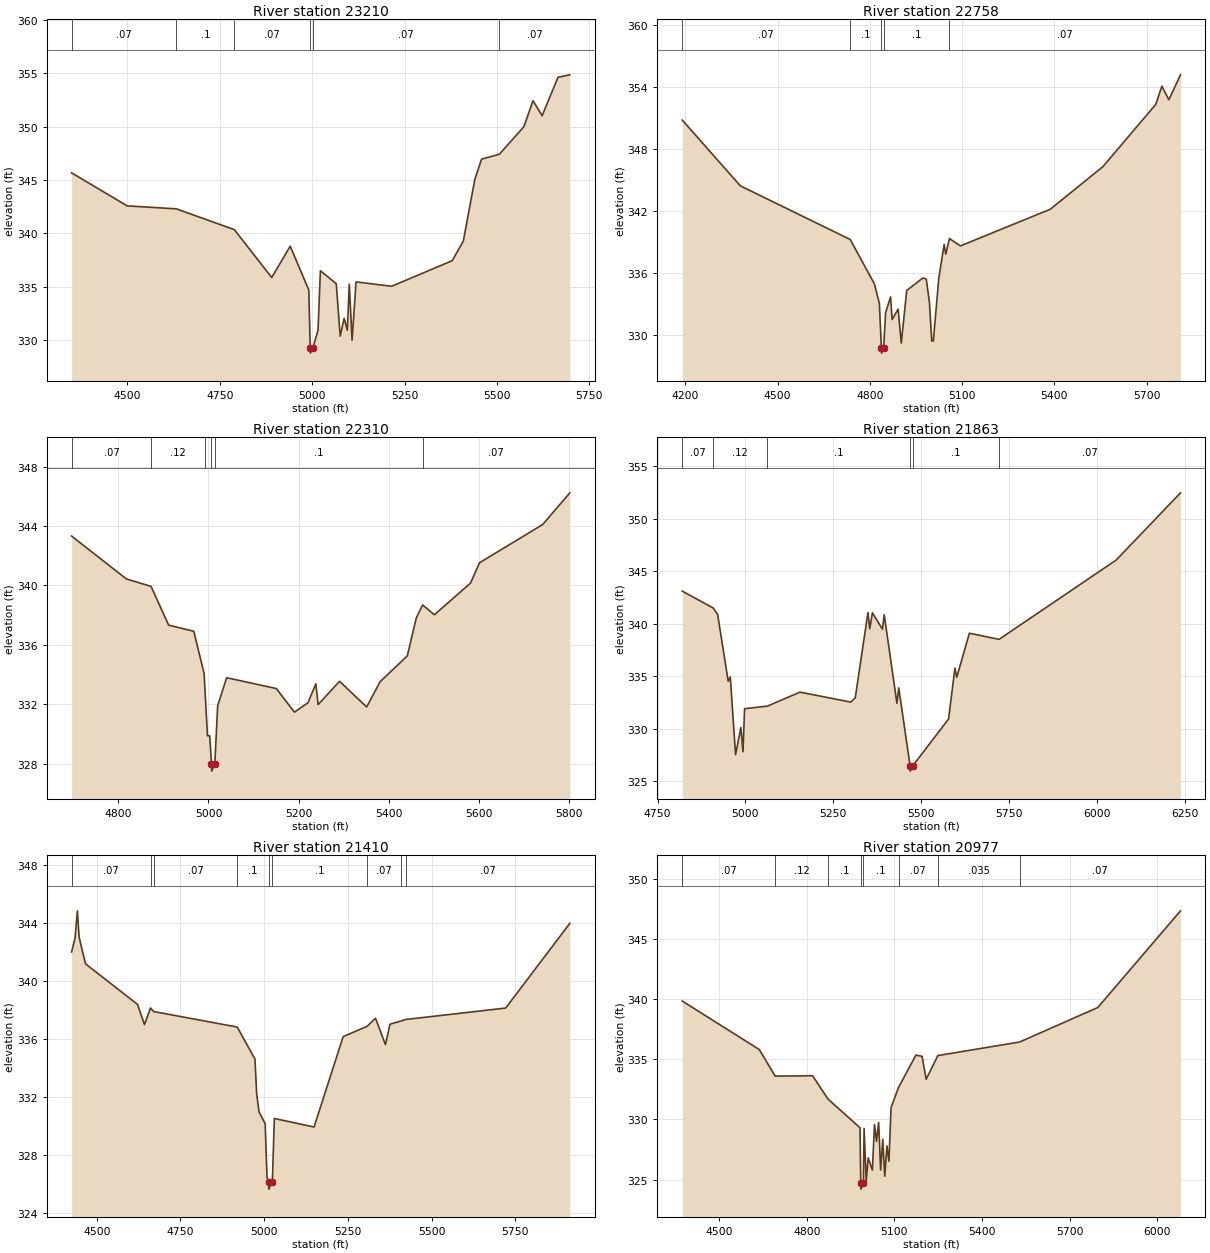
Type RM Length L Ch R = 1 ,23210   ,452,452,452
BEGIN DESCRIPTION:
SHOCKLEY CREEK 25.0
END DESCRIPTION:
XS GIS Cut Line= 3
        2353375.     13619824.99        2353325.       13619175.
      2353075.01     13618525.03
#Sta/Elev= 30
  4348.8  345.68  4499.2  342.58  4632.5   342.3  4789.2  340.35  4890.4  335.86
  4940.5   338.8  4990.7  334.69  4994.6  329.27  4995.1  328.77  5001.8  329.27
  5015.7  330.92  5022.1   336.5    5065  335.28  5075.7  330.37  5086.4  332.03
    5095  330.92  5100.3  335.24  5107.8  329.98  5118.6  335.45    5215  335.04
  5378.9  337.44  5408.9  339.28    5440  345.06  5458.2  346.96  5506.4  347.42
  5572.8  350.01  5597.5  352.44  5622.1  351.03    5665  354.64  5697.1  354.87
#Mann= 6 ,-1 , 0
  4348.8     .07       0  4632.5      .1       0  4789.2     .07       0
  4994.6     .05       0  5001.8     .07       0  5506.4     .07       0
Bank Sta=4994.6,5001.8
XS Rating Curve= 0 ,0
Exp/Cntr=0.3,0.1

Type RM Length L Ch R = 1 ,22758   ,448,448,448
BEGIN DESCRIPTION:
SHOCKLEY CREEK 24.0
END DESCRIPTION:
XS GIS Cut Line= 3
        2353875.     13619925.01        2353725.       13619125.
        2353625.     13618324.98
#Sta/Elev= 30
  4190.2  350.81  4379.3  344.44  4736.5  339.25  4815.1  334.95  4831.2  333.06
  4837.7  328.75  4838.2  328.25  4845.1  328.75  4851.5  332.16  4867.6  333.69
  4872.7   331.5  4892.2  332.51  4902.4  329.23  4920.2  334.32  4972.8  335.53
  4983.8  335.41    4994  333.15  5001.6  329.43  5006.7  329.43  5024.3  335.46
  5041.9  338.77    5047  337.83  5059.1  339.34  5094.9  338.63  5387.1  342.18
  5558.4  346.31  5729.8  352.32  5749.9  354.09  5772.6  352.78  5810.4  355.19
#Mann= 5 ,-1 , 0
  4190.2     .07       0  4736.5      .1       0  4837.7     .05       0
  4845.1      .1       0  5059.1     .07       0
Bank Sta=4837.7,4845.1
XS Rating Curve= 0 ,0
Exp/Cntr=0.3,0.1

Type RM Length L Ch R = 1 ,22310   ,447,447,447
BEGIN DESCRIPTION:
SHOCKLEY CREEK 23.0
END DESCRIPTION:
XS GIS Cut Line= 3
        2353975.     13619674.97        2354025.       13619375.
        2353975.     13618574.97
#Sta/Elev= 30
  4696.2  343.32  4817.8  340.43  4872.6  339.93  4911.6  337.32  4967.4  336.91
  4990.2  334.07  4992.7  332.69  4997.8  329.87  5002.8  329.87  5006.6  327.99
  5007.1  327.49  5014.1  327.99  5020.4   331.9  5040.4  333.78  5150.6  333.05
  5190.7  331.46  5220.7  332.09  5238.3  333.37  5243.3  331.97  5290.9  333.54
    5351  331.81  5381.1  333.52  5441.2  335.25  5461.2  337.81  5475.2  338.68
  5501.3  338.02  5581.4  340.15  5601.5  341.52  5741.8   344.1  5801.9  346.23
#Mann= 6 ,-1 , 0
  4696.2     .07       0  4872.6     .12       0  4992.7      .1       0
  5006.6     .05       0  5014.1      .1       0  5475.2     .07       0
Bank Sta=5006.6,5014.1
XS Rating Curve= 0 ,0
Exp/Cntr=0.3,0.1

Type RM Length L Ch R = 1 ,21863   ,453,453,453
BEGIN DESCRIPTION:
SHOCKLEY CREEK 22.0
END DESCRIPTION:
XS GIS Cut Line= 3
        2354175.       13619725.        2354275.       13619575.
        2353975.     13618375.01
#Sta/Elev= 30
  4820.3  343.12  4908.4  341.51    4921  340.89    4951  334.53    4957  334.94
    4972  327.53  4987.1  330.12  4993.1   327.8  4997.6  331.91  5062.7  332.16
  5155.2  333.49  5299.5  332.54  5312.4  332.95  5348.5  341.07  5353.6  339.54
  5361.3  341.05  5389.7  339.49  5394.8  340.87  5430.9  332.43  5436.1   333.9
  5468.4  326.46  5468.9  325.96  5475.9  326.46  5577.8  330.93  5595.9  335.78
    5601   334.9  5637.1  339.11  5721.4  338.52  6054.5  346.08  6237.5  352.49
#Mann= 6 ,-1 , 0
  4820.3     .07       0  4908.4     .12       0  5062.7      .1       0
  5468.4     .05       0  5475.9      .1       0  5721.4     .07       0
Bank Sta=5468.4,5475.9
XS Rating Curve= 0 ,0
Exp/Cntr=0.3,0.1

Type RM Length L Ch R = 1 ,21410   ,433,433,433
BEGIN DESCRIPTION:
SHOCKLEY CREEK 21.0
END DESCRIPTION:
XS GIS Cut Line= 3
      2354825.01     13619975.05        2354675.       13619425.
      2354225.01     13618625.01
#Sta/Elev= 30
  4424.8  341.99  4435.2  342.97  4442.1  344.83  4447.3  343.02  4466.3  341.18
  4621.8  338.38  4642.5  336.99  4660.5  338.13  4669.8  337.89  4919.5  336.82
  4972.5  334.61  4977.7  332.18  4984.6  330.97  5002.9  330.16  5008.6  326.43
  5013.5  326.15    5014  325.65  5022.3  326.15  5024.6  326.29  5030.3  330.52
  5148.9  329.93  5235.9  336.16  5307.4  336.87  5332.4  337.43  5362.1  335.61
  5375.8  337.02  5409.7  337.24  5422.3  337.34  5721.3  338.13  5912.8  343.97
#Mann= 9 ,-1 , 0
  4424.8     .07       0  4660.5     .12       0  4669.8     .07       0
  4919.5      .1       0  5013.5     .05       0  5022.3      .1       0
  5307.4     .07       0  5409.7    .035       0  5422.3     .07       0
Bank Sta=5013.5,5022.3
XS Rating Curve= 0 ,0
Exp/Cntr=0.3,0.1

Type RM Length L Ch R = 1 ,20977   ,945,945,945
BEGIN DESCRIPTION:
SHOCKLEY CREEK 20.0
END DESCRIPTION:
XS GIS Cut Line= 3
      2355074.99     13619874.97        2354975.       13619275.
      2354225.02     13618475.02
#Sta/Elev= 30
    4374  339.86  4637.6  335.82  4691.9  333.61    4820  333.64    4873  331.69
  4982.2  329.31  4984.9   324.7  4985.4   324.2  4993.8   324.7  4996.2  329.25
  5003.5  324.89  5010.3   326.8  5024.5  325.79  5031.8  329.57  5038.7  328.18
    5046  329.75  5052.8  325.78  5060.1  328.35    5067  325.27  5074.3   327.8
  5081.2  326.52  5088.5  330.99    5114  332.66  5173.5  335.36  5194.5  335.26
  5208.6  333.35  5248.7  335.32  5528.7  336.45  5795.8  339.32  6078.8  347.37
#Mann= 8 ,-1 , 0
    4374     .07       0  4691.9     .12       0    4873      .1       0
  4984.9     .05       0  4993.8      .1       0    5114     .07       0
  5248.7    .035       0  5528.7     .07       0
Bank Sta=4984.9,4993.8
XS Rating Curve= 0 ,0
Exp/Cntr=0.3,0.1

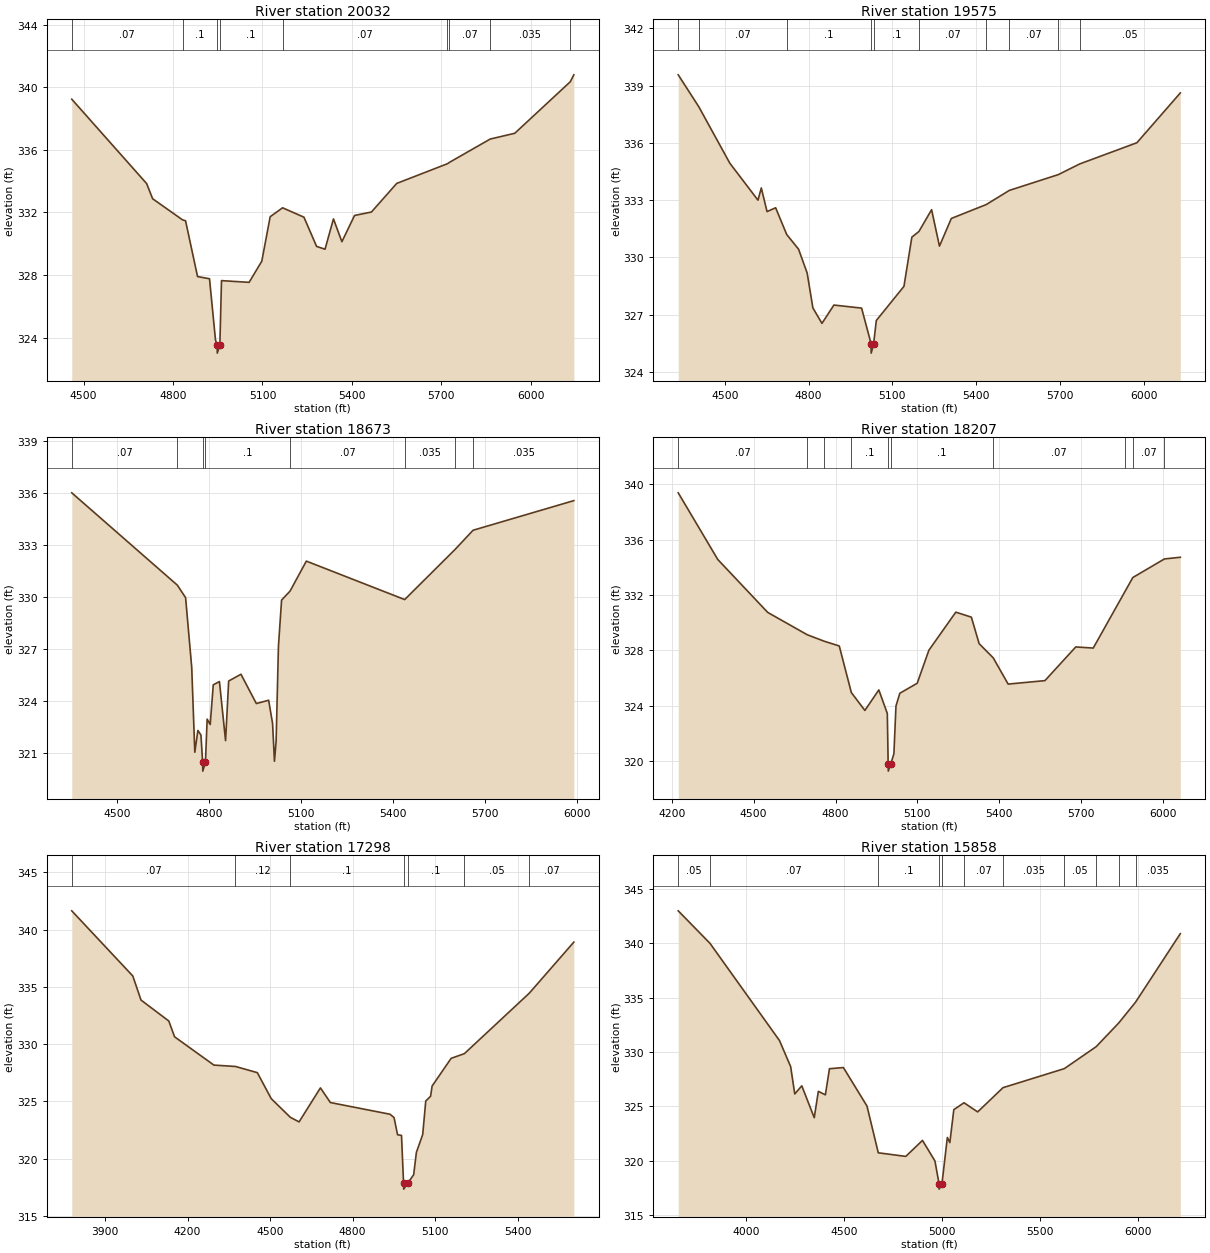
Type RM Length L Ch R = 1 ,20032   ,457,457,457
BEGIN DESCRIPTION:
SHOCKLEY CREEK 19.0
END DESCRIPTION:
XS GIS Cut Line= 3
        2355625.     13619825.04        2355575.       13619275.
      2354774.98     13618474.98
#Sta/Elev= 30
  4460.5  339.25  4711.6  333.85  4731.7  332.88  4831.9  331.53  4842.1  331.47
  4882.3   327.9  4922.4  327.76  4942.5  323.84    4948   323.5  4948.5     323
  4957.1   323.5  4962.6  327.64  5055.2  327.53  5097.7  328.88  5125.9  331.73
  5167.5   332.3  5239.1   331.7  5281.5  329.83  5309.8  329.65  5338.1  331.59
  5366.4  330.13  5408.8  331.81  5465.4  332.03  5550.2  333.86  5720.2  335.12
  5726.3   335.2  5863.8   336.7  5946.2  337.07  6131.9  340.36  6144.2  340.81
#Mann= 9 ,-1 , 0
  4460.5     .07       0  4831.9      .1       0    4948     .05       0
  4957.1      .1       0  5167.5     .07       0  5720.2    .035       0
  5726.3     .07       0  5863.8    .035       0  6131.9     .05       0
Bank Sta=4948,4957.1
XS Rating Curve= 0 ,0
Exp/Cntr=0.3,0.1

Type RM Length L Ch R = 1 ,19575   ,902,902,902
BEGIN DESCRIPTION:
SHOCKLEY CREEK 18.0
END DESCRIPTION:
XS GIS Cut Line= 3
      2355675.01     13619824.97        2355825.       13619175.
      2355025.01     13618375.01
#Sta/Elev= 30
  4333.3  339.57  4406.8   337.9    4518  334.94  4618.9     333  4630.9  333.64
  4651.4   332.4  4682.2   332.6  4721.8   331.2  4764.3  330.43  4795.1  329.18
  4815.6  327.35  4848.1  326.54  4890.9   327.5  4990.1  327.34    5024  325.48
  5024.5  324.98  5033.2  325.48  5042.8  326.69  5141.8  328.48  5170.1  331.06
  5195.6  331.36  5240.8   332.5    5269  330.59  5311.5  332.04  5436.7  332.77
  5519.1  333.51    5695  334.34  5771.6   334.9  5976.2  336.01  6131.7  338.62
#Mann= 10 ,-1 , 0
  4333.3     .05       0  4406.8     .07       0  4721.8      .1       0
    5024     .05       0  5033.2      .1       0  5195.6     .07       0
  5436.7    .035       0  5519.1     .07       0    5695    .035       0
  5771.6     .05       0
Bank Sta=5024,5033.2
XS Rating Curve= 0 ,0
Exp/Cntr=0.3,0.1

Type RM Length L Ch R = 1 ,18673   ,466,466,466
BEGIN DESCRIPTION:
SHOCKLEY CREEK 17.0
END DESCRIPTION:
XS GIS Cut Line= 3
        2356225.     13619874.96        2356175.       13619225.
      2355774.99     13618324.97
#Sta/Elev= 30
  4351.7  335.99    4696  330.66  4722.8  329.94  4742.8  325.91  4752.8  321.02
  4762.9  322.28  4772.9  322.01  4778.3  320.43  4778.8  319.93  4787.5  320.43
    4793  322.93    4803  322.62    4813  324.91  4833.1   325.1  4853.1  321.69
  4863.2  325.13  4903.3  325.52  4953.4  323.83  4993.5  324.02  5006.3  322.69
  5012.5   320.5  5017.9  321.66  5025.5  327.14  5035.7   329.8  5063.4  330.32
  5116.4  332.05    5437  329.83  5601.7  332.73  5659.9  333.83  5988.5  335.54
#Mann= 8 ,-1 , 0
  4351.7     .07       0    4696      .1       0  4778.3     .05       0
  4787.5      .1       0  5063.4     .07       0    5437    .035       0
  5601.7     .05       0  5659.9    .035       0
Bank Sta=4778.3,4787.5
XS Rating Curve= 0 ,0
Exp/Cntr=0.3,0.1

Type RM Length L Ch R = 1 ,18207   ,909,909,909
BEGIN DESCRIPTION:
SHOCKLEY CREEK 16.0
END DESCRIPTION:
XS GIS Cut Line= 3
        2356425.       13620025.        2356625.       13619275.
      2355925.01     13618475.01
#Sta/Elev= 30
  4223.8  339.37  4368.7  334.56  4551.7  330.74  4696.4  329.13    4759  328.66
  4813.7  328.32  4857.9  324.96  4907.5  323.67  4958.6  325.15  4989.7  323.45
  4992.8  319.79  4993.3  319.29    5002  319.79  5013.8  320.54  5021.4  323.99
  5035.6  324.91  5099.2  325.63  5141.9  328.01  5240.6  330.76  5297.6   330.4
    5326  328.49  5377.8  327.46  5432.3  325.57  5567.1  325.82    5680  328.25
  5744.1  328.17  5860.3  332.25  5889.1  333.26  6004.9   334.6    6063  334.72
#Mann= 10 ,-1 , 0
  4223.8     .07       0  4696.4      .1       0    4759     .07       0
  4857.9      .1       0  4992.8     .05       0    5002      .1       0
  5377.8     .07       0  5860.3     .05       0  5889.1     .07       0
  6004.9    .035       0
Bank Sta=4992.8,5002
XS Rating Curve= 0 ,0
Exp/Cntr=0.3,0.1

Type RM Length L Ch R = 1 ,17298   ,1440,1440,1440
BEGIN DESCRIPTION:
SHOCKLEY CREEK 15.0
END DESCRIPTION:
XS GIS Cut Line= 3
      2356474.97     13620125.04        2357175.       13619125.
      2357425.02     13618574.96
#Sta/Elev= 30
  3779.2  341.64  4001.1  335.95  4030.8  333.85  4131.9  332.02  4152.9  330.64
  4295.8  328.17  4374.2  328.05  4453.7  327.51  4504.2  325.24  4573.7  323.61
  4605.4  323.21    4683  326.18  4719.2   324.9  4935.8  323.88  4950.6  323.59
  4963.3  322.09  4977.7  322.03  4985.2  317.84  4985.7  317.34  4999.8  317.84
  5021.9   318.6  5031.8  320.55  5054.8  322.11  5065.8  325.03  5083.4  325.45
  5088.9  326.34  5158.1  328.76  5206.3  329.17  5442.2  334.45  5604.1  338.91
#Mann= 7 ,-1 , 0
  3779.2     .07       0  4374.2     .12       0  4573.7      .1       0
  4985.2     .05       0  4999.8      .1       0  5206.3     .05       0
  5442.2     .07       0
Bank Sta=4985.2,4999.8
XS Rating Curve= 0 ,0
Exp/Cntr=0.3,0.1

Type RM Length L Ch R = 1 ,15858   ,887,887,887
BEGIN DESCRIPTION:
SHOCKLEY CREEK 14.0
END DESCRIPTION:
XS GIS Cut Line= 3
        2356875.       13620725.        2357775.       13619725.
        2357575.     13618525.02
#Sta/Elev= 30
  3654.1  342.97  3816.2  339.98  4170.9  331.04  4227.8  328.64  4248.7  326.13
  4284.6  326.88  4348.1  323.95    4369  326.37  4404.9  326.05  4425.8  328.45
  4496.8  328.56  4617.2  325.02  4674.9  320.72  4815.2  320.39  4900.4  321.86
    4964  319.97  4984.9  317.88  4985.4  317.38  4999.8  317.88  5027.3  322.13
    5040  321.66  5060.3  324.69  5112.4  325.32    5182  324.48  5311.4  326.71
  5624.2  328.46  5786.8  330.48  5901.9  332.66  5987.6  334.57    6216  340.87
#Mann= 11 ,-1 , 0
  3654.1     .05       0  3816.2     .07       0  4674.9      .1       0
  4984.9     .05       0  4999.8      .1       0  5112.4     .07       0
  5311.4    .035       0  5624.2     .05       0  5786.8    .035       0
  5901.9     .07       0  5987.6    .035       0
Bank Sta=4984.9,4999.8
XS Rating Curve= 0 ,0
Exp/Cntr=0.3,0.1

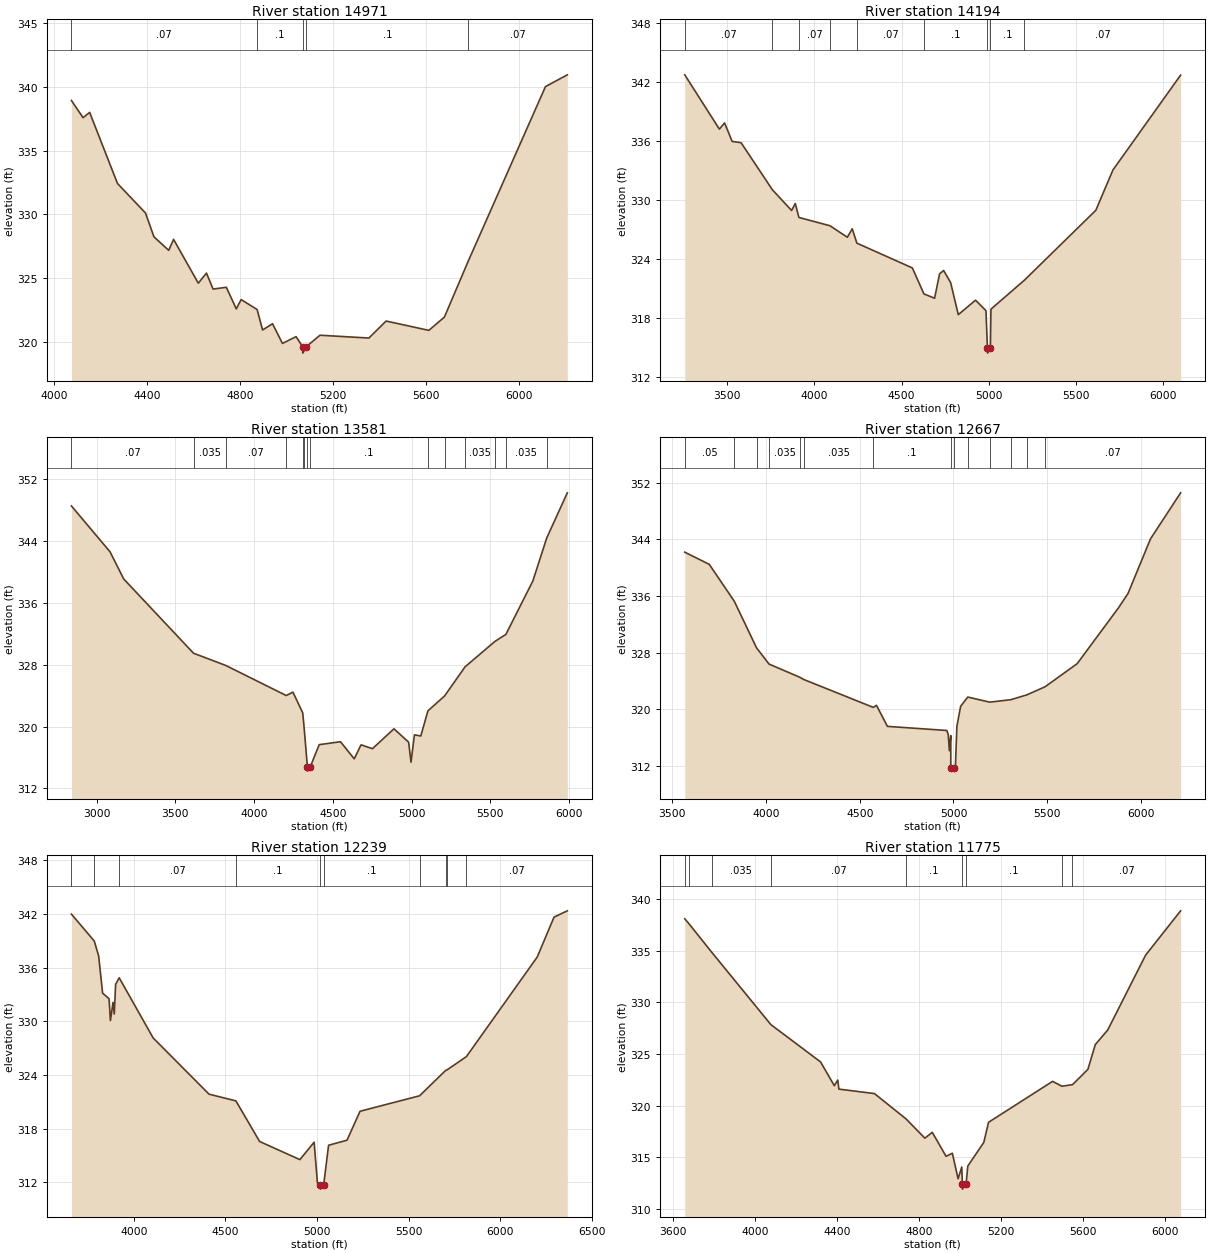
Type RM Length L Ch R = 1 ,14971   ,777,777,777
BEGIN DESCRIPTION:
SHOCKLEY CREEK 13.0
END DESCRIPTION:
XS GIS Cut Line= 3
      2357725.03     13620924.96        2358325.       13620225.
      2358870.16     13619142.09
#Sta/Elev= 30
  4073.7  338.91  4123.6  337.57  4152.1  337.98  4271.8  332.42  4392.5  330.11
  4428.7  328.25  4492.4  327.19  4513.2  328.05  4619.7  324.62  4654.8  325.41
  4683.3  324.16  4740.4   324.3  4783.2  322.61  4804.1  323.34  4872.9  322.56
  4896.3  320.96  4939.1  321.45  4981.9  319.91  5040.4  320.44    5069  319.65
  5069.5  319.15    5084  319.65  5143.5  320.55  5353.9  320.33    5428  321.66
  5612.1  320.93    5679  321.97  5782.4  326.38  6114.1     340    6208  340.92
#Mann= 5 ,-1 , 0
  4073.7     .07       0  4872.9      .1       0    5069     .05       0
    5084      .1       0  5782.4     .07       0
Bank Sta=5069,5084
XS Rating Curve= 0 ,0
Exp/Cntr=0.3,0.1

Type RM Length L Ch R = 1 ,14194   ,613,613,613
BEGIN DESCRIPTION:
E20827
END DESCRIPTION:
XS GIS Cut Line= 3
      2357721.57     13621244.99      2358653.15     13620662.04
      2359367.55      13619073.2
#Sta/Elev= 30
  3257.4  342.74  3455.7  337.22  3485.6  337.85  3528.8  335.97    3580  335.84
  3759.7  331.05  3869.5  328.95  3890.7  329.66  3911.4  328.24  4089.1   327.4
    4189  326.23    4217  327.09  4243.5  325.63  4561.4  323.11  4627.7  320.47
  4688.8  320.03  4717.4  322.51  4740.6  322.85  4780.7  321.62  4824.6  318.36
  4923.2  319.83  4983.1  318.77  4991.5  314.95    4992  314.45  5008.5  314.95
  5011.7  318.92    5203  321.86  5612.6  328.97  5710.7  333.07  6098.4  342.71
#Mann= 9 ,-1 , 0
  3257.4     .07       0  3759.7    .035       0  3911.4     .07       0
  4089.1    .035       0  4243.5     .07       0  4627.7      .1       0
  4991.5     .05       0  5008.5      .1       0    5203     .07       0
Bank Sta=4991.5,5008.5
XS Rating Curve= 0 ,0
Exp/Cntr=0.3,0.1

Type RM Length L Ch R = 1 ,13581   ,914,914,914
BEGIN DESCRIPTION:
SHOCKLEY CREEK 12.0
END DESCRIPTION:
XS GIS Cut Line= 3
      2357625.01     13621474.99        2359425.       13620275.
        2359825.       13619375.
#Sta/Elev= 30
  2840.8  348.51  3085.7  342.59  3172.8  339.07  3615.8  329.48  3820.2   327.9
  4204.4  324.01    4247  324.45    4309  321.78  4315.7  320.39  4339.1  314.74
  4339.6  314.24  4356.1  314.74  4413.7  317.66  4548.9  318.04  4636.1  315.83
  4679.6  317.64  4751.7  317.14  4888.4  319.71  4981.6  317.98  4996.6   315.4
  5018.5  318.93  5058.8  318.78    5104  322.03  5210.4  323.97  5339.8  327.72
  5529.7  331.01    5599  331.91  5770.1  338.81  5858.3  344.37    5989  350.21
#Mann= 14 ,-1 , 0
  2840.8     .07       0  3615.8    .035       0  3820.2     .07       0
  4204.4     .12       0    4309     .07       0  4315.7      .1       0
  4339.1     .05       0  4356.1      .1       0    5104     .07       0
  5210.4      .1       0  5339.8    .035       0  5529.7     .07       0
    5599    .035       0  5858.3     .07       0
Bank Sta=4339.1,4356.1
XS Rating Curve= 0 ,0
Exp/Cntr=0.3,0.1

Type RM Length L Ch R = 1 ,12667   ,428,428,428
BEGIN DESCRIPTION:
SHOCKLEY CREEK 11.0
END DESCRIPTION:
XS GIS Cut Line= 3
      2358974.98     13621775.04        2359775.       13620575.
        2359875.     13619375.02
#Sta/Elev= 30
    3566  342.21  3696.7  340.49  3830.2  335.29  3948.9  328.71  4015.7  326.41
  4181.2  324.53  4201.2  324.23  4572.1  320.29  4589.1  320.58  4647.7  317.61
  4964.7  317.03  4972.2  316.45  4978.2  314.18  4985.7  316.31  4985.8  311.79
  4986.3  311.29  5003.6  311.79  5010.8  312.16  5018.3   317.6  5038.4  320.45
  5076.5  321.75  5193.6  321.03  5306.5  321.38  5390.9  322.05  5489.5  323.21
  5660.5  326.47  5881.3  334.37  5931.5  336.37  6051.9   344.1  6212.4  350.59
#Mann= 14 ,-1 , 0
    3566     .05       0  3830.2    .035       0  3948.9     .07       0
  4015.7    .035       0  4181.2     .12       0  4201.2    .035       0
  4572.1      .1       0  4985.8     .05       0  5003.6      .1       0
  5076.5     .07       0  5193.6     .12       0  5306.5     .07       0
  5390.9     .12       0  5489.5     .07       0
Bank Sta=4985.8,5003.6
XS Rating Curve= 0 ,0
Exp/Cntr=0.3,0.1

Type RM Length L Ch R = 1 ,12239   ,464,464,464
BEGIN DESCRIPTION:
SHOCKLEY CREEK 10.0
END DESCRIPTION:
XS GIS Cut Line= 3
        2359025.       13621775.        2360025.       13620875.
        2360825.       13619775.
#Sta/Elev= 30
  3659.6  341.99  3784.1  338.98    3808  337.31  3829.6  333.15  3864.8  332.53
  3872.2  330.09  3886.4  332.12  3893.2  330.82  3900.6  334.13  3920.1  334.87
  4105.4  328.14  4410.4  321.85  4556.9   321.1  4686.2  316.56  4905.9  314.53
  4983.7  316.48  5001.6  311.93    5018  311.73  5018.5  311.23  5035.9  311.73
  5062.5  316.14    5163   316.7  5234.1  319.94    5559  321.67  5702.9  324.54
  5706.9  324.54  5814.4  326.05  6200.9  337.19  6292.8  341.66  6365.1  342.36
#Mann= 10 ,-1 , 0
  3659.6     .05       0  3784.1    .035       0  3920.1     .07       0
  4556.9      .1       0    5018     .05       0  5035.9      .1       0
    5559     .12       0  5702.9     .07       0  5706.9     .12       0
  5814.4     .07       0
Bank Sta=5018,5035.9
XS Rating Curve= 0 ,0
Exp/Cntr=0.3,0.1

Type RM Length L Ch R = 1 ,11775   ,478,478,478
BEGIN DESCRIPTION:
SHOCKLEY CREEK 9.0
END DESCRIPTION:
XS GIS Cut Line= 3
      2359825.02     13622174.96        2360425.       13620975.
      2360824.99     13619975.03
#Sta/Elev= 30
  3658.3  338.08  3677.6  337.63  3788.9  334.87  4078.2  327.85  4320.7  324.24
  4387.8  321.94  4404.5  322.49  4410.1  321.61  4583.4  321.18  4737.7  318.73
  4829.4  316.87  4865.7  317.43  4932.8  315.11  4963.6  315.41  4991.5  312.94
  5009.3  314.08  5012.4  312.44  5012.9  311.94  5030.4  312.44  5038.9  314.17
    5117  316.46  5139.9   318.4  5452.3  322.36  5497.8  321.89  5549.5  322.04
  5624.6  323.52  5660.9  325.92  5721.5  327.33    5906  334.56  6076.9  338.85
#Mann= 9 ,-1 , 0
  3658.3    .035       0  3677.6     .07       0  3788.9    .035       0
  4078.2     .07       0  4737.7      .1       0  5012.4     .05       0
  5030.4      .1       0  5497.8     .12       0  5549.5     .07       0
Bank Sta=5012.4,5030.4
XS Rating Curve= 0 ,0
Exp/Cntr=0.3,0.1