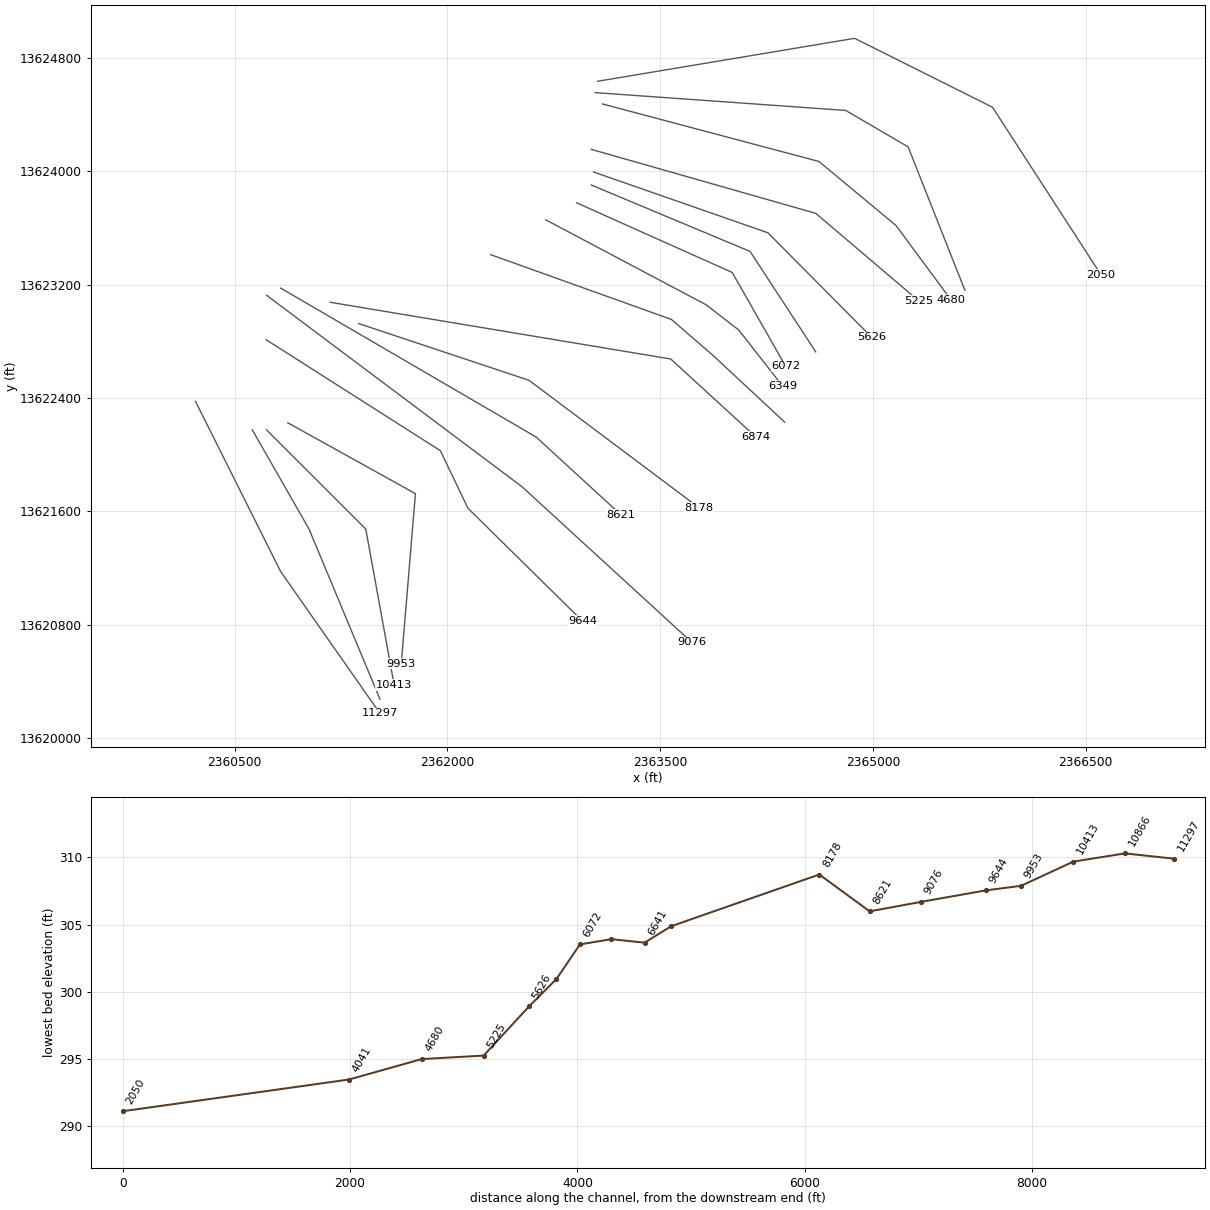
HEC-RAS study SHOCKLEY CREEK.prj: SHOCKLEY CREEK Base Level Engineering

--- SHOCKLEY CREEK.g01 (geometry) --- (continued)

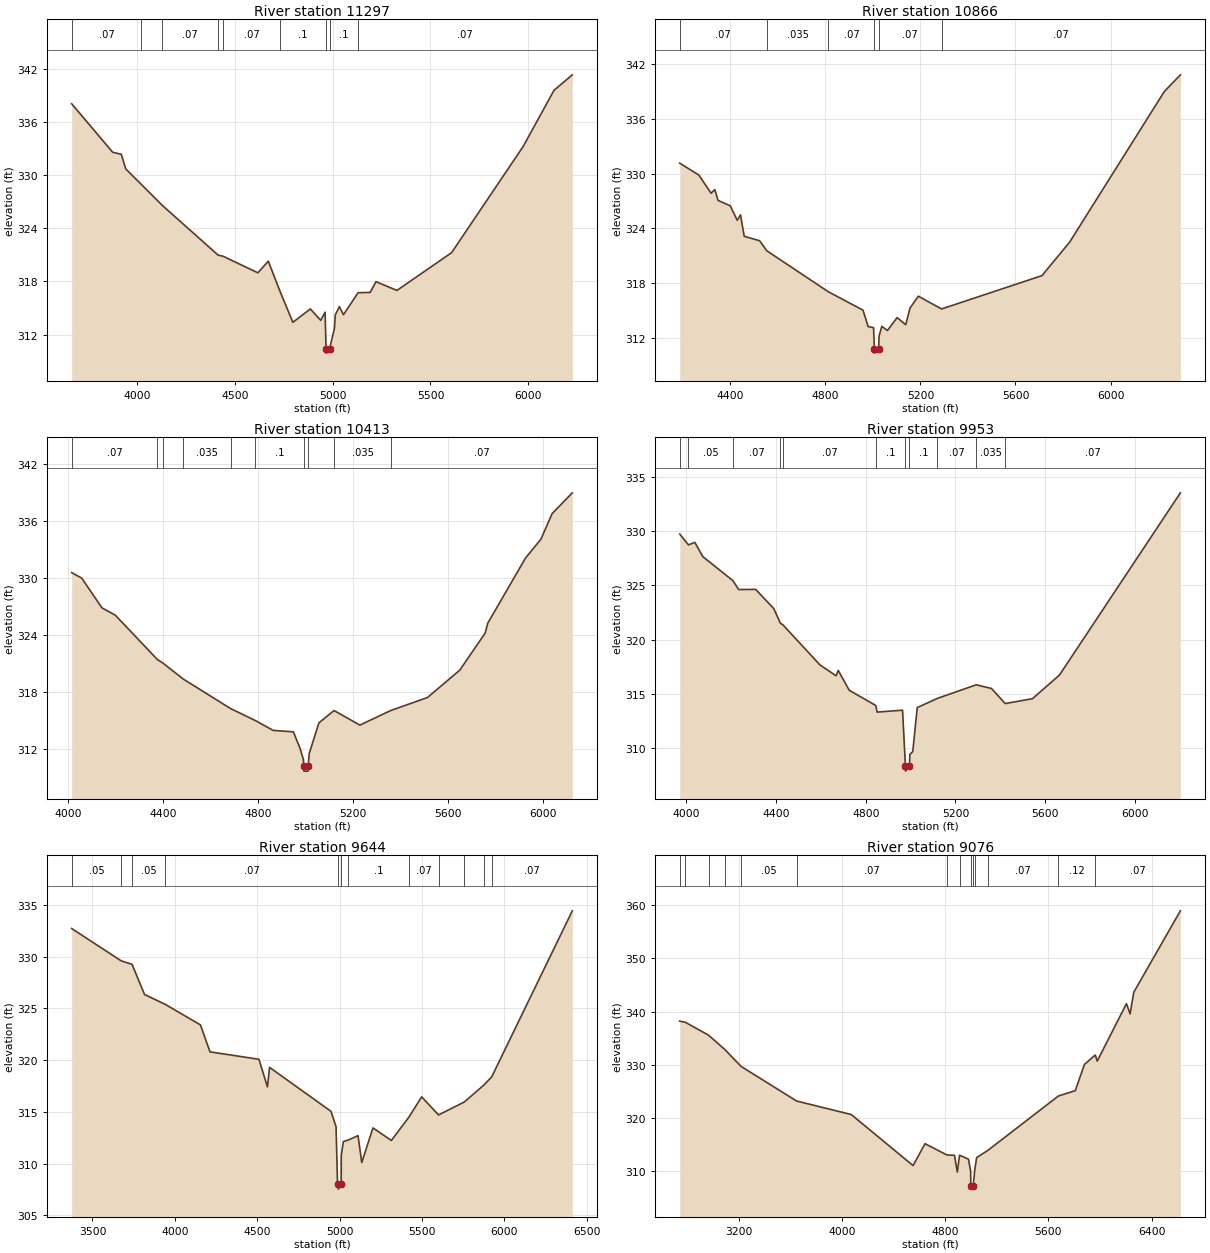
Type RM Length L Ch R = 1 ,11297   ,431,431,431
BEGIN DESCRIPTION:
SHOCKLEY CREEK 8.0
END DESCRIPTION:
XS GIS Cut Line= 3
      2360225.02     13622374.96        2360825.       13621175.
      2361525.03     13620174.96
#Sta/Elev= 30
  3663.8  338.06  3873.4  332.59  3918.1  332.35  3940.5   330.7  4018.5  328.99
  4127.4  326.59  4413.1  320.97  4437.6  320.85  4616.9  318.97    4670  320.29
    4730  316.88  4795.8  313.38  4885.2  314.89  4938.3   313.6  4960.7  314.52
  4965.6   310.4  4966.1   309.9  4983.7   310.4  5008.4  312.68  5012.8   314.2
  5033.7  315.15  5054.7  314.24  5129.5  316.72  5191.5  316.76  5221.2  317.97
  5328.4  316.98  5608.3  321.25  5974.5  333.24  6132.3  339.58  6226.1  341.33
#Mann= 9 ,-1 , 0
  3663.8     .07       0  4018.5    .035       0  4127.4     .07       0
  4413.1    .035       0  4437.6     .07       0    4730      .1       0
  4965.6     .05       0  4983.7      .1       0  5129.5     .07       0
Bank Sta=4965.6,4983.7
XS Rating Curve= 0 ,0
Exp/Cntr=0.3,0.1

Type RM Length L Ch R = 1 ,10866   ,453,453,453
BEGIN DESCRIPTION:
SHOCKLEY CREEK 7.0
END DESCRIPTION:
XS GIS Cut Line= 3
      2360625.02     13622174.97        2361025.       13621475.
        2361525.     13620274.99
#Sta/Elev= 30
  4187.6  331.15  4268.2  329.84  4319.3  327.85  4335.1  328.25  4348.8  327.06
  4399.9  326.47  4429.4  324.88  4443.1  325.47  4458.9  323.12  4523.7  322.63
  4553.8  321.53  4813.3  317.02  4958.5  315.01  4980.1  313.21    5003  313.08
  5006.4  310.79  5006.9  310.29  5024.5  310.79  5026.3  312.17  5037.7  313.23
  5061.5  312.77  5102.1  314.19  5138.4  313.41  5156.3  315.24  5191.5  316.54
    5289  315.14  5711.5   318.8    5828  322.48  6226.1  339.01  6293.8  340.85
#Mann= 6 ,-1 , 0
  4187.6     .07       0  4553.8    .035       0  4813.3     .07       0
  5006.4     .05       0  5024.5     .07       0    5289     .07       0
Bank Sta=5006.4,5024.5
XS Rating Curve= 0 ,0
Exp/Cntr=0.3,0.1

Type RM Length L Ch R = 1 ,10413   ,460,460,460
BEGIN DESCRIPTION:
SHOCKLEY CREEK 6.0
END DESCRIPTION:
XS GIS Cut Line= 3
      2360725.02     13622174.98        2361425.       13621475.
      2361624.99     13620375.05
#Sta/Elev= 30
  4015.1  330.55  4057.5  329.97  4142.3  326.85  4198.9  326.07  4376.1  321.41
  4399.3  321.04  4484.3  319.37  4683.9  316.26  4788.2     315  4863.6  313.96
  4948.4  313.81  4976.7  312.07  4990.9  310.88  4992.4  310.18  4992.9  309.68
    5010  309.68  5010.5  310.18  5015.2  311.52  5055.8  314.75  5119.7  316.05
  5228.6  314.52  5359.2  316.06  5513.2  317.42  5649.2   320.3  5755.9  324.19
  5767.3  325.25  5926.1  332.09  5990.9  334.07  6037.9  336.75    6123  338.94
#Mann= 10 ,-1 , 0
  4015.1     .07       0  4376.1    .035       0  4399.3     .07       0
  4484.3    .035       0  4683.9     .07       0  4788.2      .1       0
  4992.4     .05       0  5010.5      .1       0  5119.7    .035       0
  5359.2     .07       0
Bank Sta=4992.4,5010.5
XS Rating Curve= 0 ,0
Exp/Cntr=0.3,0.1

Type RM Length L Ch R = 1 ,9953    ,309,309,309
BEGIN DESCRIPTION:
SHOCKLEY CREEK 5.0
END DESCRIPTION:
XS GIS Cut Line= 3
      2360875.01     13622224.99        2361775.       13621725.
        2361675.     13620525.01
#Sta/Elev= 30
  3970.1  329.74  4008.9  328.74  4037.6  328.97    4073  327.66    4207  325.45
  4233.2  324.62  4308.7  324.64  4389.9  322.86    4419  321.52  4430.3  321.37
  4595.8  317.67  4667.9  316.67  4677.1  317.17  4726.2  315.34  4844.7  313.93
  4850.9  313.32  4964.2   313.5  4976.9  308.38  4977.4  307.88    4995  308.38
  4996.8  309.42  5009.7  309.68  5029.8  313.74  5120.1  314.59    5293  315.84
  5360.9   315.5  5422.3  314.11    5544  314.56  5664.4  316.74  6203.8  333.54
#Mann= 11 ,-1 , 0
  3970.1     .07       0  4008.9     .05       0    4207     .07       0
    4419    .035       0  4430.3     .07       0  4844.7      .1       0
  4976.9     .05       0    4995      .1       0  5120.1     .07       0
    5293    .035       0  5422.3     .07       0
Bank Sta=4976.9,4995
XS Rating Curve= 0 ,0
Exp/Cntr=0.3,0.1

Type RM Length L Ch R = 1 ,9644    ,568,568,568
BEGIN DESCRIPTION:
E20826
END DESCRIPTION:
XS GIS Cut Line= 4
      2360722.14     13622811.01      2361950.92     13622028.01
      2362145.25     13621622.22      2362951.13     13620827.77
#Sta/Elev= 30
  3373.8  332.73  3673.8  329.61  3740.5  329.26  3815.9  326.35  3940.6  325.41
  4155.6  323.41  4213.1  320.81  4510.2  320.09  4561.8  317.43  4574.8  319.31
  4947.5  315.06  4978.3  313.58  4987.3   308.1  4991.4  308.04  4991.9  307.54
  5009.6  308.04    5010  310.81  5022.7  312.14  5050.2  312.27  5111.7  312.71
  5134.4  310.11  5202.4  313.46    5314  312.24  5422.8  314.55  5497.8  316.46
  5600.4  314.71  5756.7  315.96  5873.4  317.57  5922.7  318.38  6412.4  334.44
#Mann= 12 ,-1 , 0
  3373.8     .05       0  3673.8     .07       0  3740.5     .05       0
  3940.6     .07       0  4991.4     .05       0  5009.6     .07       0
  5050.2      .1       0  5422.8     .07       0  5600.4     .12       0
  5756.7     .07       0  5873.4     .12       0  5922.7     .07       0
Bank Sta=4991.4,5009.6
XS Rating Curve= 0 ,0
Exp/Cntr=0.3,0.1

Type RM Length L Ch R = 1 ,9076    ,455,455,455
BEGIN DESCRIPTION:
SHOCKLEY CREEK 4.0
END DESCRIPTION:
XS GIS Cut Line= 3
      2360725.01       13623125.        2362525.       13621775.
      2363725.02     13620674.98
#Sta/Elev= 30
  2744.8  338.22  2786.1  338.04  2967.5   335.6  3094.2   332.9  3219.9  329.73
  3650.1  323.23  4072.9   320.7  4552.1  311.11  4644.8  315.22  4814.6   313.1
  4872.9  313.04  4894.8   309.9  4912.1  313.06  4981.3  312.31  4998.2  310.03
  4999.2  307.19  4999.7  306.69  5018.1  307.19  5029.5  310.22  5044.4  312.61
  5130.1  313.94  5678.2  324.18  5808.7  325.18  5879.3  330.09  5963.1  331.87
  5978.6  330.73  6204.9  341.51  6233.3   339.6  6261.6  343.65  6622.7  358.94
#Mann= 14 ,-1 , 0
  2744.8     .12       0  2786.1     .07       0  2967.5     .12       0
  3094.2     .07       0  3219.9     .05       0  3650.1     .07       0
  4814.6      .1       0  4912.1     .07       0  4999.2     .05       0
  5018.1     .07       0  5029.5      .1       0  5130.1     .07       0
  5678.2     .12       0  5963.1     .07       0
Bank Sta=4999.2,5018.1
XS Rating Curve= 0 ,0
Exp/Cntr=0.3,0.1

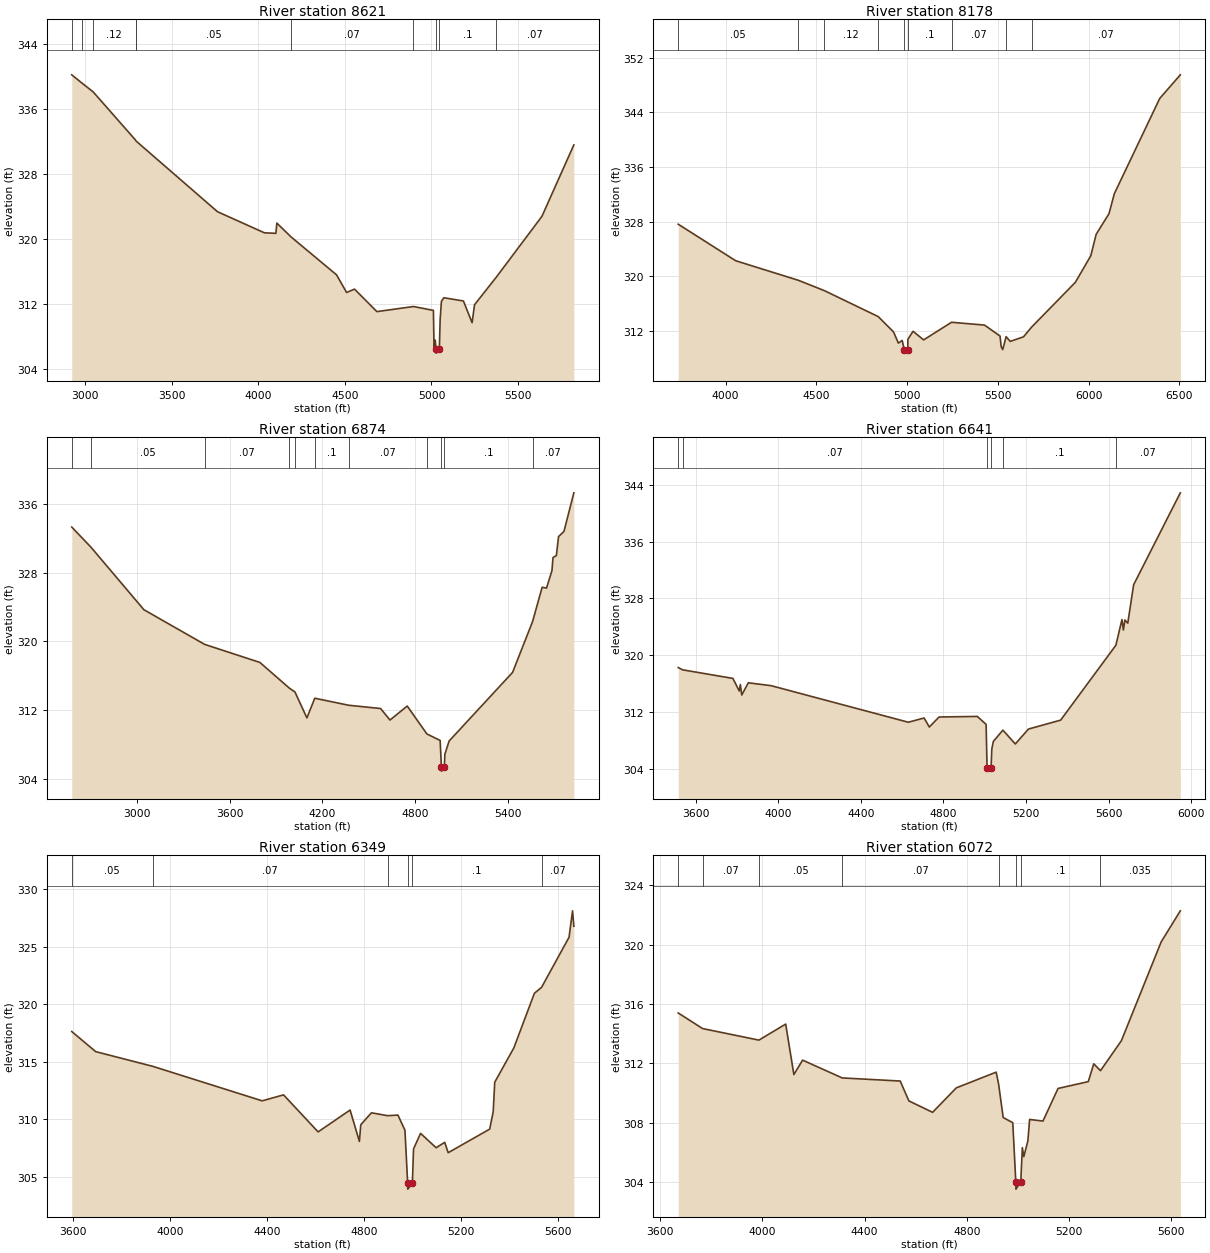
Type RM Length L Ch R = 1 ,8621    ,443,443,443
BEGIN DESCRIPTION:
SHOCKLEY CREEK 3.0
END DESCRIPTION:
XS GIS Cut Line= 3
      2360824.97     13623175.02        2362625.       13622125.
      2363224.97     13621575.03
#Sta/Elev= 30
    2924  340.25  2981.9  339.25  3047.4  338.15  3291.9  332.22  3294.5  332.11
  3765.4  323.39  4035.4   320.8    4102  320.73  4107.8  321.99  4189.7  320.29
  4452.2  315.62  4510.1  313.45    4556  313.86    4685  311.09  4896.2  311.72
  5011.3  311.24    5015  306.51  5021.8  307.58  5026.5  306.48    5027  305.98
  5045.5  306.48  5050.1  310.09  5057.5  312.36  5071.7   312.8  5184.6   312.4
  5234.5  309.73  5248.7  311.94  5374.5  315.34  5637.8  322.83  5821.8  331.62
#Mann= 10 ,-1 , 0
    2924     .12       0  2981.9     .07       0  3047.4     .12       0
  3291.9     .07       0  3294.5     .05       0  4189.7     .07       0
  4896.2      .1       0  5026.5     .05       0  5045.5      .1       0
  5374.5     .07       0
Bank Sta=5026.5,5045.5
XS Rating Curve= 0 ,0
Exp/Cntr=0.3,0.1

Type RM Length L Ch R = 1 ,8178    ,1304,1304,1304
BEGIN DESCRIPTION:
SHOCKLEY CREEK 2.0
END DESCRIPTION:
XS GIS Cut Line= 3
      2361375.01       13622925.        2362575.       13622525.
        2363775.       13621625.
#Sta/Elev= 30
  3739.7  327.61  4055.9  322.26  4400.4   319.4  4545.1  317.87  4841.2  314.07
  4925.5  311.82  4951.9  310.19    4973  310.58  4984.6  309.22  4985.1  308.72
  5003.6  309.22  5004.6  310.75  5032.7  311.92  5091.1  310.66  5244.8  313.24
  5426.5  312.83  5511.9  311.22  5518.1  309.68  5526.5  309.24  5545.4  311.13
  5568.1  310.44  5641.1  311.11  5685.6  312.53  5926.5  319.09  6011.9     323
  6041.1  326.13  6111.9  329.15  6141.1  332.07  6391.1  346.03  6504.6   349.5
#Mann= 9 ,-1 , 0
  3739.7     .05       0  4400.4     .07       0  4545.1     .12       0
  4841.2      .1       0  4984.6     .05       0  5003.6      .1       0
  5244.8     .07       0  5545.4      .1       0  5685.6     .07       0
Bank Sta=4984.6,5003.6
XS Rating Curve= 0 ,0
Exp/Cntr=0.3,0.1

Type RM Length L Ch R = 1 ,6874    ,233,233,233
BEGIN DESCRIPTION:
SHOCKLEY CREEK 1.0
END DESCRIPTION:
XS GIS Cut Line= 3
      2361175.01       13623075.        2363575.       13622675.
      2364174.97     13622125.02
#Sta/Elev= 30
  2579.4  333.29  2703.5  330.95  3045.7  323.67  3438.7  319.63  3795.9  317.53
  3986.2  314.54  4022.8  314.09  4100.1  311.07  4150.9  313.36  4370.6  312.54
  4576.6  312.16  4637.4  310.82  4748.9  312.45    4876   309.2  4961.8  308.44
  4969.8  305.37  4970.3  304.87  4989.2  305.37  4992.2  306.83  5019.6  308.37
  5430.3  316.37  5559.6  322.29  5621.4  326.28  5649.8  326.19  5684.9  328.22
  5691.7  329.75  5713.3  329.97  5727.5  332.18  5762.6  332.79  5826.4  337.28
#Mann= 11 ,-1 , 0
  2579.4     .07       0  2703.5     .05       0  3438.7     .07       0
  3986.2      .1       0  4022.8     .07       0  4150.9      .1       0
  4370.6     .07       0    4876      .1       0  4969.8     .05       0
  4989.2      .1       0  5559.6     .07       0
Bank Sta=4969.8,4989.2
XS Rating Curve= 0 ,0
Exp/Cntr=0.3,0.1

Type RM Length L Ch R = 1 ,6641    ,292,292,292
BEGIN DESCRIPTION:
E20825
END DESCRIPTION:
XS GIS Cut Line= 4
       2362305.3     13623411.13      2363579.81     13622953.91
      2363877.01     13622696.71      2364378.91     13622229.04
#Sta/Elev= 30
  3514.6  318.25  3535.6  317.93  3779.5  316.72  3810.3  314.95  3815.6  315.85
  3822.4  314.38  3854.3   316.1    3964   315.7  4629.8  310.54    4706  311.14
  4731.4  309.87  4778.5  311.28  4963.9  311.36  5006.6  310.24  5011.2  304.15
  5011.7  303.65  5030.6  304.15  5034.2  306.77  5041.8  307.84  5087.9  309.43
  5148.1  307.48  5211.8  309.58  5367.8  310.84  5635.4  321.39  5664.9  325.01
  5671.7  323.55    5679  324.95  5693.2  324.51  5721.5  329.92  5947.7  342.88
#Mann= 6 ,-1 , 0
  3514.6     .05       0  3535.6     .07       0  5011.2     .05       0
  5030.6     .07       0  5087.9      .1       0  5635.4     .07       0
Bank Sta=5011.2,5030.6
XS Rating Curve= 0 ,0
Exp/Cntr=0.3,0.1

Type RM Length L Ch R = 1 ,6349    ,277,277,277
BEGIN DESCRIPTION:
E20824
END DESCRIPTION:
XS GIS Cut Line= 4
      2362693.94     13623656.89      2363825.57     13623056.78
      2364054.19     13622879.61      2364362.81     13622485.26
#Sta/Elev= 30
  3595.9  317.62  3694.7  315.87  3930.3  314.59  4381.4  311.59  4469.4  312.11
    4612  308.89  4743.9  310.79  4782.3  308.06  4787.9  309.51  4831.9  310.55
  4898.4   310.3  4941.3  310.35  4970.2  309.03  4981.4  304.41  4981.9  303.91
  5000.8  304.41  5005.5   307.4  5034.5  308.76  5098.8  307.51  5134.1  307.98
  5148.6  307.08  5319.7  309.13  5334.2  310.65  5340.5  313.21  5419.2  316.19
  5504.2  320.95  5533.6  321.46    5647  325.82  5661.5  328.12  5666.8  326.78
#Mann= 6 ,-1 , 0
  3595.9     .05       0  3930.3     .07       0  4898.4      .1       0
  4981.4     .05       0  5000.8      .1       0  5533.6     .07       0
Bank Sta=4981.4,5000.8
XS Rating Curve= 0 ,0
Exp/Cntr=0.3,0.1

Type RM Length L Ch R = 1 ,6072    ,206,206,206
BEGIN DESCRIPTION:
E20823
END DESCRIPTION:
XS GIS Cut Line= 3
      2362911.12     13623776.92      2364008.46      13623285.4
      2364385.69      13622622.4
#Sta/Elev= 30
  3670.7   315.4    3766  314.35  3986.4  313.57  4091.3  314.65  4123.3  311.25
  4157.5  312.22  4312.5  311.02  4539.5  310.81  4573.6  309.47  4666.4   308.7
  4759.1  310.35  4915.2  311.41  4924.8  310.59  4942.6  308.35  4980.1     308
    4992  304.02  4992.5  303.52  5011.4  304.02  5017.6  306.32  5023.3  305.71
  5039.2  306.77  5046.1  308.22  5098.3  308.11  5157.4  310.31  5275.6  310.77
  5297.2  311.97  5323.5  311.51  5405.3  313.53  5560.9  320.19  5635.9  322.29
#Mann= 8 ,-1 , 0
  3670.7     .05       0    3766     .07       0  3986.4     .05       0
  4312.5     .07       0  4924.8      .1       0    4992     .05       0
  5011.4      .1       0  5323.5    .035       0
Bank Sta=4992,5011.4
XS Rating Curve= 0 ,0
Exp/Cntr=0.3,0.1

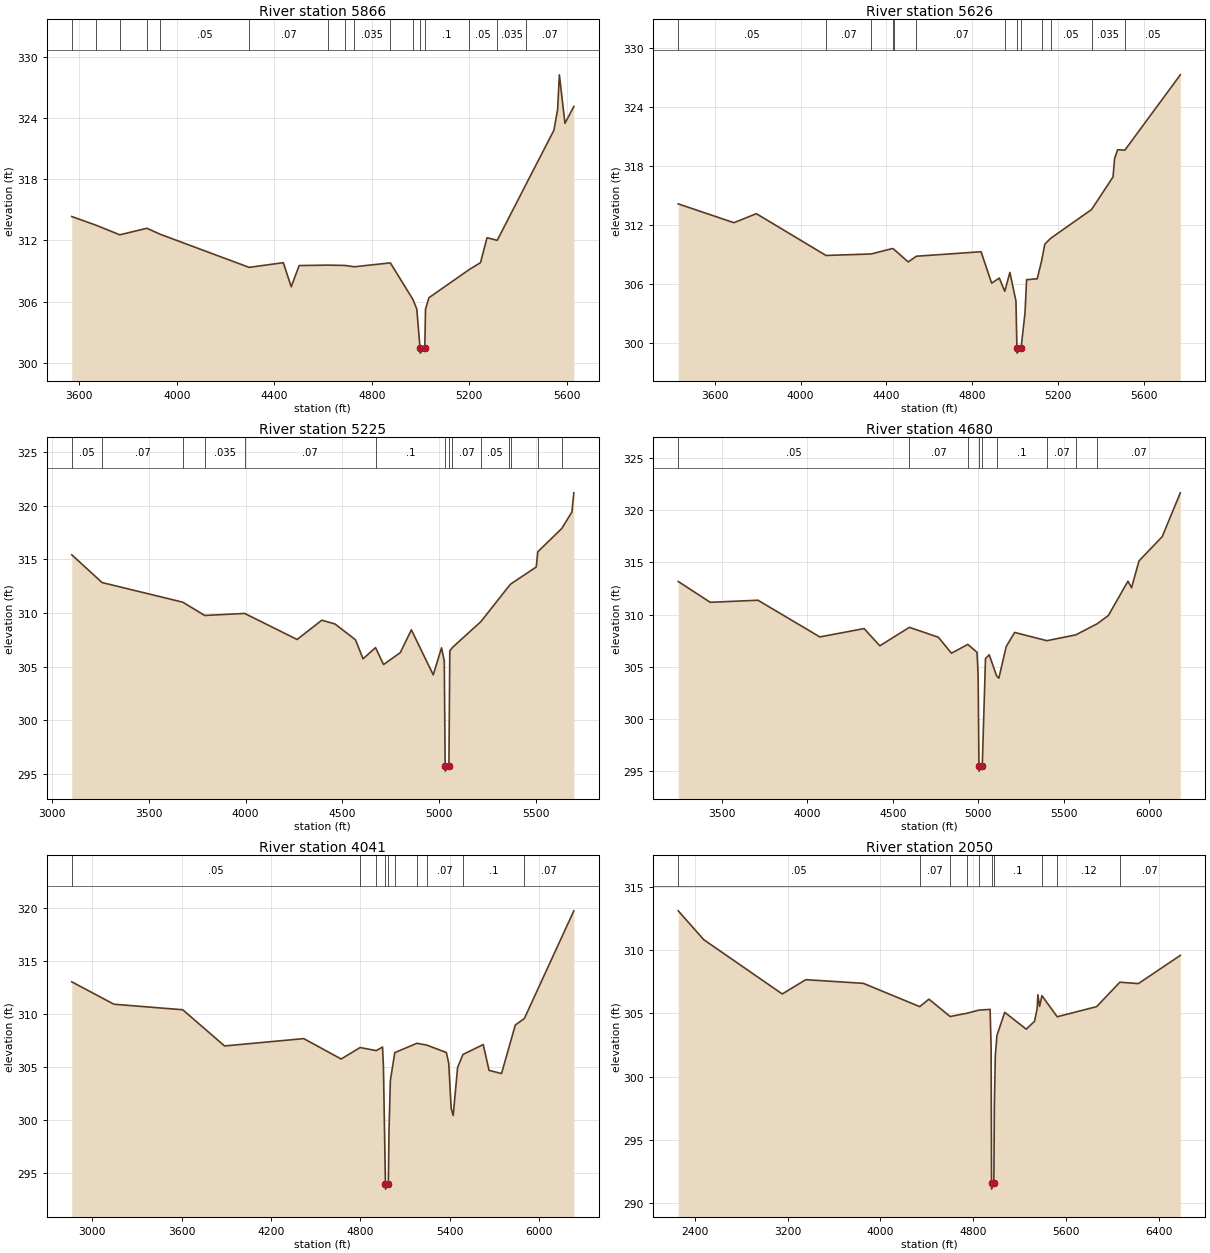
Type RM Length L Ch R = 1 ,5866    ,240,240,240
BEGIN DESCRIPTION:
E20822
END DESCRIPTION:
XS GIS Cut Line= 3
      2363014.01     13623902.65       2364134.2       13623434.
      2364597.15     13622725.29
#Sta/Elev= 30
  3568.8  314.33  3668.3  313.48  3765.9  312.54  3877.2  313.18  3932.1  312.59
  4296.8  309.35  4437.1  309.81  4469.6  307.45  4502.1  309.53  4620.7  309.57
  4689.6  309.54  4728.7  309.41  4876.5  309.79  4968.8  306.22  4984.9  305.28
  4998.3  301.45  4998.8  300.95  5017.7  301.45  5020.8  305.26    5035  306.38
  5199.8  309.13  5246.3  309.81  5273.3  312.25  5315.2     312  5433.2  317.48
  5547.8  322.78    5563  324.83  5570.2  328.21  5593.2  323.46  5629.6  325.11
#Mann= 16 ,-1 , 0
  3568.8     .05       0  3668.3     .07       0  3765.9     .05       0
  3877.2     .07       0  3932.1     .05       0  4296.8     .07       0
  4620.7    .035       0  4689.6     .07       0  4728.7    .035       0
  4876.5     .07       0  4968.8      .1       0  4998.3     .05       0
  5017.7      .1       0  5199.8     .05       0  5315.2    .035       0
  5433.2     .07       0
Bank Sta=4998.3,5017.7
XS Rating Curve= 0 ,0
Exp/Cntr=0.3,0.1

Type RM Length L Ch R = 1 ,5626    ,401,401,401
BEGIN DESCRIPTION:
E20821
END DESCRIPTION:
XS GIS Cut Line= 3
       2363031.1     13623994.12      2364259.94     13623565.45
       2364991.5     13622828.18
#Sta/Elev= 30
    3430  314.14  3689.5  312.22  3794.2  313.14  4118.7  308.88  4329.2  309.03
  4429.3  309.59  4434.5  309.52  4501.8  308.22  4539.8   308.8  4841.4  309.26
  4890.9  306.05  4926.3  306.58    4952  305.23  4975.8  307.15  5004.1  304.23
  5008.5  299.42    5009  298.92  5027.9  299.42  5046.5  303.08  5053.6  306.41
  5103.1   306.5  5123.4   308.3  5138.4  310.03    5166  310.63  5356.4  313.56
  5456.6  316.89  5463.7  318.75  5477.9  319.66  5511.7  319.62  5770.1   327.3
#Mann= 13 ,-1 , 0
    3430     .05       0  4118.7     .07       0  4329.2    .035       0
  4429.3     .07       0  4434.5    .035       0  4539.8     .07       0
    4952      .1       0  5008.5     .05       0  5027.9      .1       0
  5123.4     .07       0    5166     .05       0  5356.4    .035       0
  5511.7     .05       0
Bank Sta=5008.5,5027.9
XS Rating Curve= 0 ,0
Exp/Cntr=0.3,0.1

Type RM Length L Ch R = 1 ,5225    ,545,545,545
BEGIN DESCRIPTION:
E20820
END DESCRIPTION:
XS GIS Cut Line= 3
      2363014.02     13624154.13      2364597.15     13623702.62
      2365321.49     13623086.65
#Sta/Elev= 30
  3101.1  315.43  3257.9  312.84  3675.2  311.01    3789  309.77  3995.4  309.96
  4266.8  307.53  4394.5  309.33  4462.2  308.98  4568.3  307.51  4607.9  305.73
  4672.3  306.77  4713.9  305.19  4800.7  306.31  4857.8  308.43  4970.9  304.23
  5013.7  306.75    5028  305.53  5032.5  295.75    5033  295.25    5052  295.75
  5056.6  306.47  5070.5  306.79  5217.6   309.2  5364.6  312.56  5371.3   312.7
  5503.6  314.29  5511.7  315.71  5636.1  317.89  5688.1  319.42  5698.2  321.21
#Mann= 14 ,-1 , 0
  3101.1     .05       0  3257.9     .07       0  3675.2     .05       0
    3789    .035       0  3995.4     .07       0  4672.3      .1       0
  5032.5     .05       0    5052      .1       0  5070.5     .07       0
  5217.6     .05       0  5364.6     .07       0  5371.3    .035       0
  5511.7     .05       0  5636.1     .07       0
Bank Sta=5032.5,5052
XS Rating Curve= 0 ,0
Exp/Cntr=0.3,0.1

Type RM Length L Ch R = 1 ,4680    ,639,639,639
BEGIN DESCRIPTION:
E20819
END DESCRIPTION:
XS GIS Cut Line= 4
      2363094.04     13624474.19      2364620.01     13624068.41
      2365162.97     13623616.89      2365550.83     13623092.14
#Sta/Elev= 30
    3245  313.18  3432.2  311.18  3711.6  311.38  4073.5  307.86  4332.5  308.66
  4424.6  307.01  4597.6  308.78  4767.1  307.83  4843.6   306.3  4939.2  307.14
  4993.3  306.39  4999.8  304.18  5004.4  295.49  5004.9  294.99  5023.9  295.49
  5042.8  305.79  5064.6  306.15  5107.5  304.14  5120.9   303.9  5163.9  306.93
  5213.3  308.29  5402.2   307.5  5571.4  308.06    5696  309.12  5761.6  309.91
  5876.5  313.21  5897.3  312.58  5941.2  315.15  6076.9  317.48  6182.7  321.68
#Mann= 9 ,-1 , 0
    3245     .05       0  4597.6     .07       0  4939.2     .12       0
  5004.4     .05       0  5023.9     .12       0  5107.5      .1       0
  5402.2     .07       0  5571.4      .1       0    5696     .07       0
Bank Sta=5004.4,5023.9
XS Rating Curve= 0 ,0
Exp/Cntr=0.3,0.1

Type RM Length L Ch R = 1 ,4041    ,1991,1991,1991
BEGIN DESCRIPTION:
E20818
END DESCRIPTION:
XS GIS Cut Line= 4
      2363042.57     13624554.21      2364808.62     13624428.48
       2365248.7     13624171.28       2365648.7     13623159.85
#Sta/Elev= 30
  2863.3     313  3146.4  310.89  3607.6  310.37  3888.3  306.96  4419.7  307.65
  4670.3  305.73  4797.5  306.81  4905.9  306.52    4948  306.86  4953.9     305
  4967.4  293.97  4967.9  293.47  4986.9  293.97    4991  298.79  5000.3   303.7
    5030  306.33  5178.2  307.21  5244.6  307.04  5376.1  306.34    5392  305.32
  5408.4  301.08  5421.8  300.41  5451.5  304.94  5487.6  306.16  5623.5  307.09
  5662.4  304.66  5746.2  304.36  5838.5  308.93    5899  309.54  6231.2  319.69
#Mann= 10 ,-1 , 0
  2863.3     .05       0  4797.5     .07       0  4905.9      .1       0
  4967.4     .05       0  4986.9      .1       0    5030     .07       0
  5178.2      .1       0  5244.6     .07       0  5487.6      .1       0
    5899     .07       0
Bank Sta=4967.4,4986.9
XS Rating Curve= 0 ,0
Exp/Cntr=0.3,0.1

Type RM Length L Ch R = 1 ,2050    ,0,0,0
BEGIN DESCRIPTION:
E20817
END DESCRIPTION:
XS GIS Cut Line= 4
      2363059.69     13624634.23      2364871.49     13624937.15
       2365843.1     13624451.34      2366608.38     13623269.16
#Sta/Elev= 30
    2256   313.1  2476.2  310.82  3153.6  306.53  3356.4  307.66  3853.2  307.37
  4339.6  305.53  4418.7  306.12  4601.7  304.75    4743     305  4852.2  305.26
  4946.6  305.31  4955.4  302.25    4959  291.61  4959.5  291.11  4978.9  291.61
  4983.3  297.62  4991.3  301.63  5005.7  303.26  5072.8  305.08  5258.3  303.75
  5329.7  304.37  5352.6  305.37  5358.5  306.47  5373.7  305.55  5393.5   306.4
  5525.4  304.73  5865.8  305.53  6065.9  307.46  6225.8  307.35  6587.5  309.58
#Mann= 10 ,-1 , 0
    2256     .05       0  4339.6     .07       0  4601.7     .12       0
    4743     .07       0  4852.2      .1       0    4959     .05       0
  4978.9      .1       0  5393.5     .07       0  5525.4     .12       0
  6065.9     .07       0
Bank Sta=4959,4978.9
XS Rating Curve= 0 ,0
Exp/Cntr=0.3,0.1

Chan Stop Cuts=-1
Use User Specified Reach Order=0
Composite Channel Slope=5