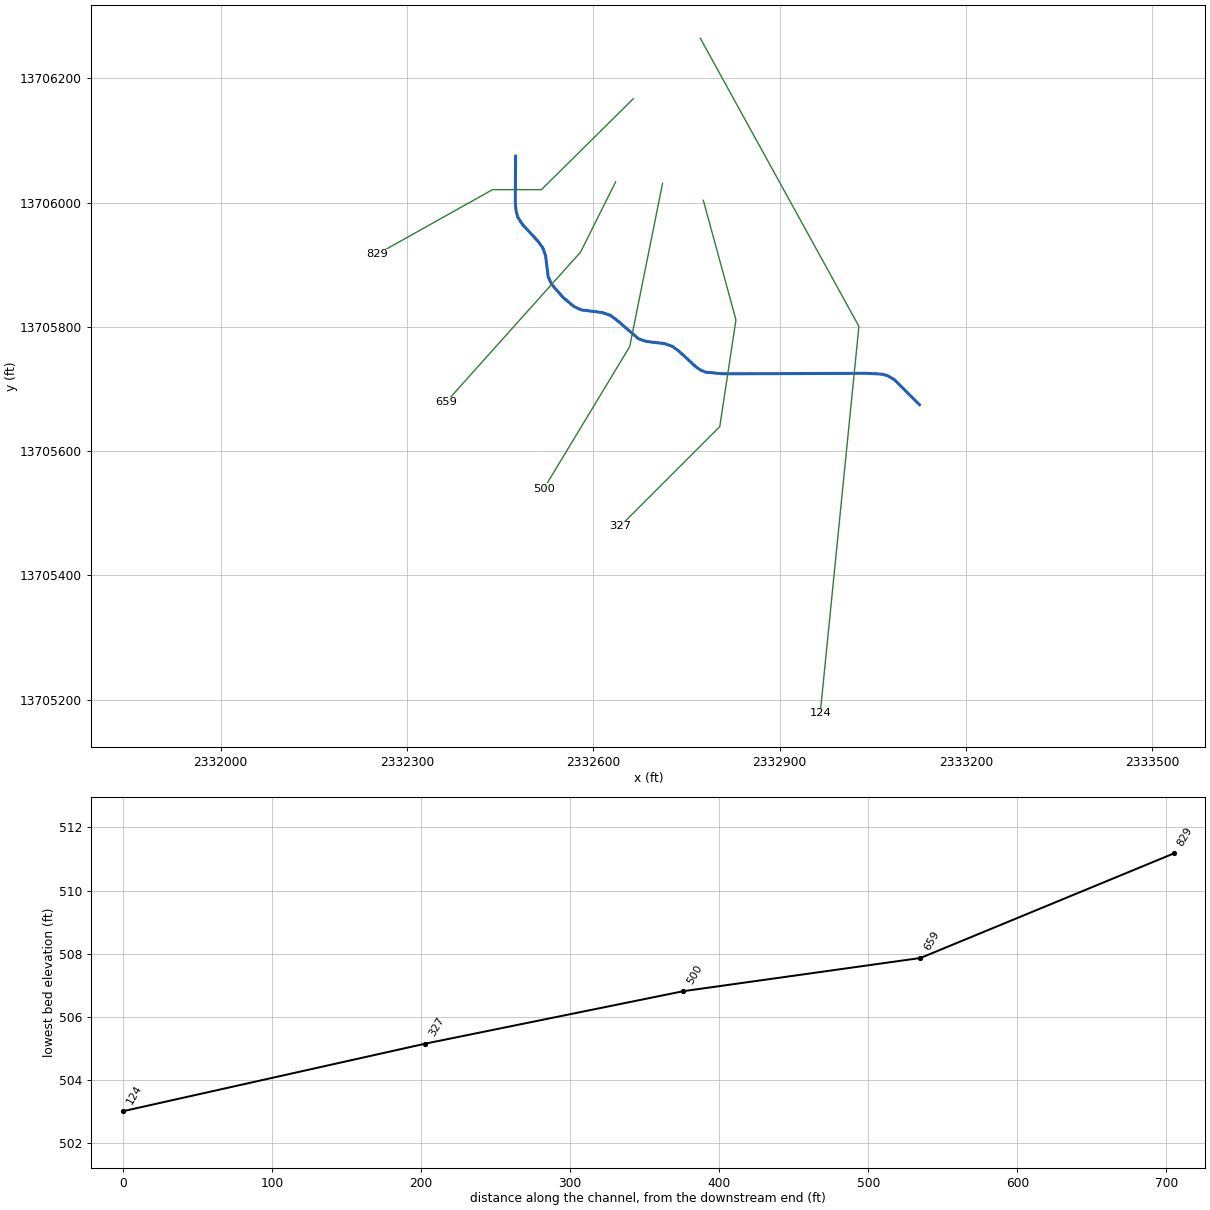
--- Stream0541.prj (project) ---

Proj Title=Stream0541 Base Level Engineering
Current Plan=p01
Default Exp/Contr=0.3,0.1
English Units
Geom File=g01
Flow File=f01
Plan File=p01
BEGIN DESCRIPTION:
Stream0541
END DESCRIPTION:

--- Stream0541.p01 (plan) ---

Plan Title=Multiple Run
Short Identifier=Multiple
Geom File=g01
Flow File=f01
Subcritical Flow
K Sum by GR= 0
Std Step Tol= 0.01
Critical Tol= 0.01
Num of Std Step Trials= 20
Max Error Tol= 0.3
Flow Tol Ratio= 0.001
Split Flow NTrial= 30
Split Flow Tol= 0.02
Split Flow Ratio= 0.02
Log Output Level= 0
Friction Slope Method= 1
Unsteady Friction Slope Method= 2
Unsteady Bridges Friction Slope Method= 1
Parabolic Critical Depth
Global Vel Dist=  1 , 1 , 1
Global Log Level= 0
CheckData=True
Encroach Param= -1, 0, 0, 0
BEGIN DESCRIPTION:
Multiple Run
END DESCRIPTION:

--- Stream0541.f01 (steady flow) ---

Flow Title=Multiple
Number of Profiles=7
Profile Names=10-year,25-year,50-year,1pct_min,100-year,1pct_plu,500-year
River Rch & RM= Stream0541,Reach-1,829
     510     828    1118     733    1462    2918    2477
Boundary for River Rch & Prof#=Stream0541,Reach-1,1
Up Type=0
Dn Type=3
Dn Slope=0.005
Boundary for River Rch & Prof#=Stream0541,Reach-1,2
Up Type=0
Dn Type=3
Dn Slope=0.005
Boundary for River Rch & Prof#=Stream0541,Reach-1,3
Up Type=0
Dn Type=3
Dn Slope=0.005
Boundary for River Rch & Prof#=Stream0541,Reach-1,4
Up Type=0
Dn Type=3
Dn Slope=0.005
Boundary for River Rch & Prof#=Stream0541,Reach-1,5
Up Type=0
Dn Type=3
Dn Slope=0.005
Boundary for River Rch & Prof#=Stream0541,Reach-1,6
Up Type=0
Dn Type=3
Dn Slope=0.005
Boundary for River Rch & Prof#=Stream0541,Reach-1,7
Up Type=0
Dn Type=3
Dn Slope=0.005

--- Stream0541.g01 (geometry) ---

Geom Title=Existing Conditions

River Reach=Stream0541,Reach-1
Reach XY= 30
      2332475.00     13706075.00      2332474.52     13705999.80
      2332476.00     13705985.41      2332478.63     13705976.50
      2332485.79     13705965.33      2332510.99     13705938.04
      2332518.88     13705927.16      2332523.27     13705914.25
      2332527.42     13705880.85      2332533.02     13705868.66
      2332551.16     13705847.85      2332568.66     13705833.02
      2332580.85     13705827.42      2332614.25     13705823.28
      2332627.16     13705818.89      2332638.05     13705811.01
      2332672.80     13705781.08      2332685.68     13705776.65
      2332714.31     13705773.33      2332727.18     13705768.88
      2332738.04     13705760.96      2332765.33     13705735.80
      2332772.65     13705730.71      2332780.93     13705727.24
      2332809.82     13705724.56      2333040.17     13705725.41
      2333064.60     13705724.04      2333073.64     13705721.71
      2333084.98     13705714.95      2333125.00     13705675.00

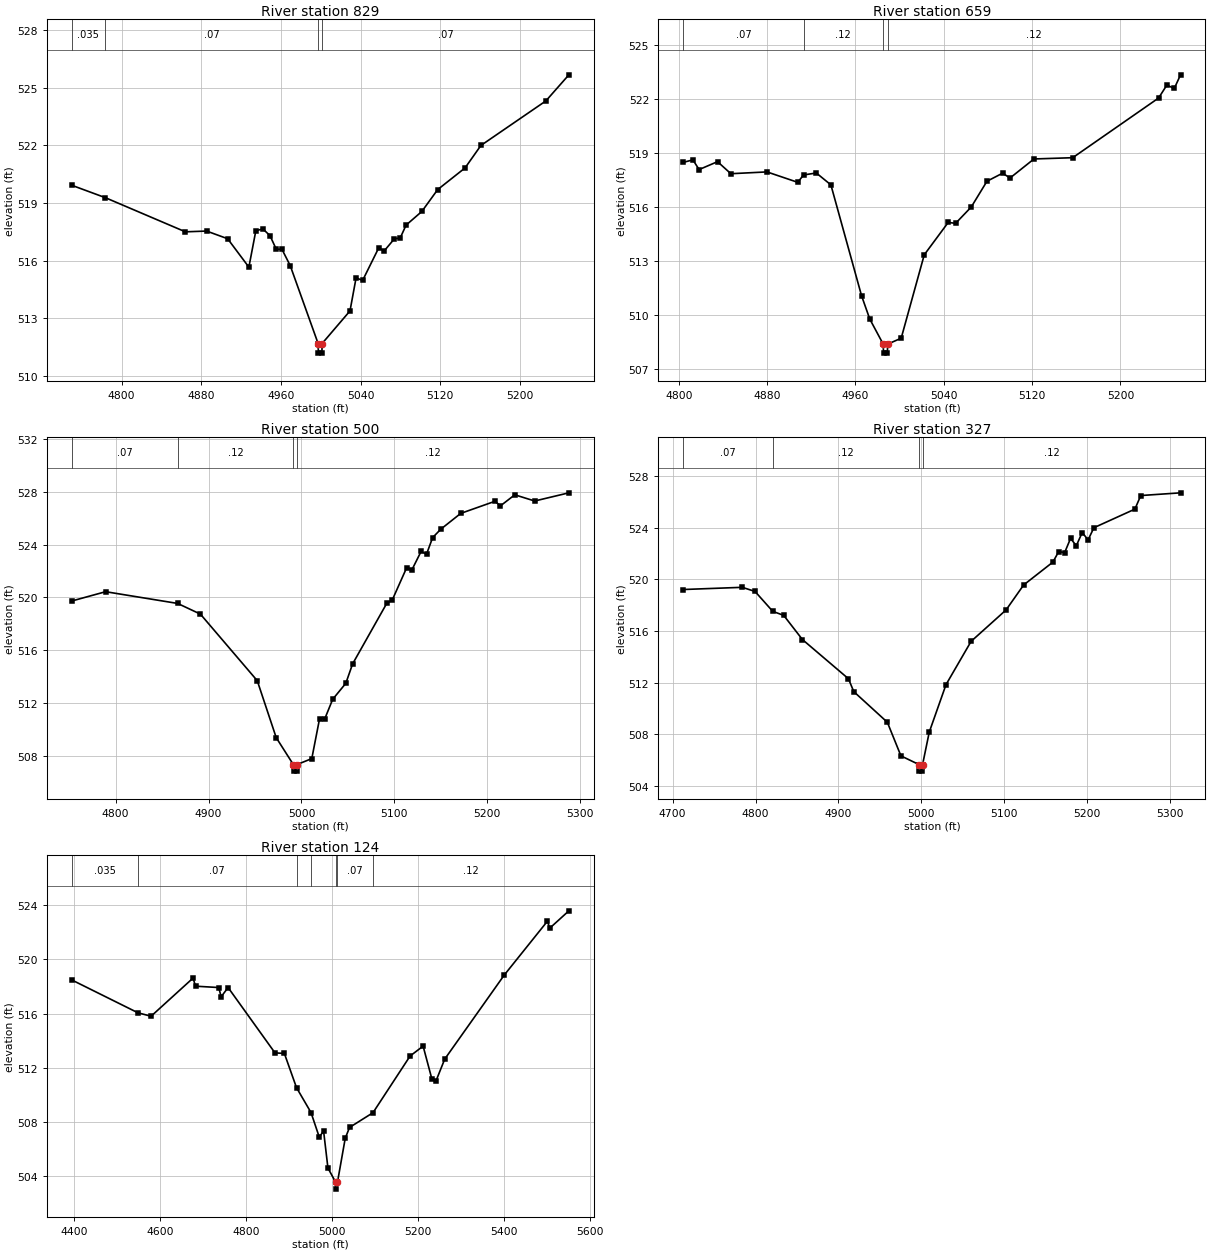
Type RM Length L Ch R = 1,829,170,170,170
BEGIN DESCRIPTION:
XS7054
END DESCRIPTION:
XS GIS Cut Line= 4
      2332664.39     13706167.31      2332516.55     13706021.05
      2332437.92     13706021.05      2332252.37     13705917.26
#Sta/Elev= 30
  4749.8  519.93  4783.7  519.28  4864.1  517.50  4885.4  517.54  4906.5  517.14
  4927.8  515.66  4934.8  517.56  4941.9  517.65  4949.0  517.30  4955.3  516.59
  4961.0  516.59  4969.3  515.74  4997.3  511.68  4997.6  511.18  5001.1  511.18
  5001.3  511.68  5029.3  513.38  5035.4  515.10  5042.0  514.97  5058.0  516.65
  5063.7  516.51  5073.9  517.14  5079.7  517.18  5085.6  517.85  5101.4  518.56
  5117.3  519.70  5144.8  520.83  5160.7  522.00  5225.9  524.32  5249.0  525.68
#Mann=4,-1,0
  4749.8   0.035       0  4783.7    0.07       0  4997.3    0.05       0
  5001.3    0.07       0
Bank Sta=4997.3,5001.3
Exp/Cntr=0.3,0.1

Type RM Length L Ch R = 1,659,159,159,159
BEGIN DESCRIPTION:
XS7053
END DESCRIPTION:
XS GIS Cut Line= 3
      2332636.06     13706033.60      2332579.46     13705920.39
      2332363.21     13705679.07
#Sta/Elev= 30
  4803.9  518.48  4812.7  518.62  4818.3  518.08  4835.0  518.52  4847.1  517.85
  4879.8  517.95  4907.7  517.37  4912.9  517.78  4924.5  517.89  4937.7  517.23
  4965.5  511.06  4972.9  509.77  4985.1  508.37  4985.4  507.87  4988.9  507.87
  4989.1  508.37  5001.4  508.70  5022.3  513.34  5044.0  515.14  5050.7  515.09
  5064.9  516.00  5079.1  517.43  5093.3  517.88  5100.0  517.61  5121.7  518.67
  5156.8  518.74  5234.6  522.06  5242.1  522.78  5248.8  522.59  5254.5  523.35
#Mann=4,-1,0
  4803.9    0.07       0  4912.9    0.12       0  4985.1    0.05       0
  4989.1    0.12       0
Bank Sta=4985.1,4989.1
Exp/Cntr=0.3,0.1

Type RM Length L Ch R = 1,500,173,173,173
BEGIN DESCRIPTION:
Stream0541 1.0
END DESCRIPTION:
XS GIS Cut Line= 3
      2332711.50     13706030.99      2332658.67     13705768.42
      2332520.36     13705539.49
#Sta/Elev= 30
  4752.5  519.72  4789.2  520.43  4866.7  519.54  4891.2  518.73  4952.4  513.68
  4972.8  509.36  4991.2  507.32  4991.5  506.82  4995.0  506.82  4995.2  507.32
  5011.1  507.77  5019.5  510.81  5025.2  510.81  5033.6  512.27  5047.7  513.48
  5055.0  514.95  5091.8  519.55  5097.7  519.80  5113.2  522.25  5119.0  522.11
  5128.7  523.48  5134.6  523.28  5141.2  524.54  5150.1  525.18  5171.4  526.37
  5208.3  527.29  5214.1  526.94  5229.6  527.78  5251.0  527.31  5287.8  527.93
#Mann=4,-1,0
  4752.5    0.07       0  4866.7    0.12       0  4991.2    0.05       0
  4995.2    0.12       0
Bank Sta=4991.2,4995.2
Exp/Cntr=0.3,0.1

Type RM Length L Ch R = 1,327,203,203,203
BEGIN DESCRIPTION:
XS7052
END DESCRIPTION:
XS GIS Cut Line= 4
      2332777.16     13706003.83      2332829.69     13705811.46
      2332803.65     13705639.58      2332643.09     13705479.03
#Sta/Elev= 30
  4712.7  519.21  4784.0  519.38  4799.4  519.06  4820.8  517.52  4834.0  517.21
  4856.6  515.34  4912.1  512.31  4918.6  511.31  4959.1  508.94  4975.5  506.34
  4997.6  505.66  4997.8  505.16  5001.3  505.16  5001.6  505.66  5009.7  508.18
  5029.9  511.85  5060.2  515.20  5102.4  517.63  5123.6  519.56  5158.9  521.33
  5166.0  522.15  5173.1  522.06  5180.2  523.16  5187.2  522.60  5194.3  523.62
  5201.4  523.05  5208.4  523.99  5257.9  525.43  5265.0  526.48  5313.0  526.69
#Mann=4,-1,0
  4712.7    0.07       0  4820.8    0.12       0  4997.6    0.05       0
  5001.6    0.12       0
Bank Sta=4997.6,5001.6
Exp/Cntr=0.3,0.1

Type RM Length L Ch R = 1,124,0,0,0
BEGIN DESCRIPTION:
XS7051
END DESCRIPTION:
XS GIS Cut Line= 3
      2332772.38     13706264.61      2333027.60     13705801.04
      2332965.30     13705178.03
#Sta/Elev= 30
  4394.7  518.49  4549.2  516.05  4579.5  515.80  4677.0  518.62  4682.7  518.02
  4736.6  517.92  4742.3  517.24  4758.4  517.92  4867.3  513.09  4889.1  513.05
  4917.3  510.52  4951.0  508.68  4970.2  506.86  4980.2  507.32  4990.3  504.58
  5008.4  503.52  5008.6  503.02  5012.4  503.52  5030.5  506.78  5040.5  507.58
  5095.0  508.67  5181.2  512.86  5211.4  513.59  5231.5  511.19  5241.5  511.03
  5261.6  512.63  5399.8  518.84  5500.3  522.83  5505.3  522.30  5550.0  523.59
#Mann=7,-1,0
  4394.7   0.035       0  4549.2    0.07       0  4917.3    0.12       0
  4951.0    0.07       0  5008.4    0.05       0  5012.4    0.07       0
  5095.0    0.12       0
Bank Sta=5008.4,5012.4
Exp/Cntr=0.3,0.1

Chan Stop Cuts=-1