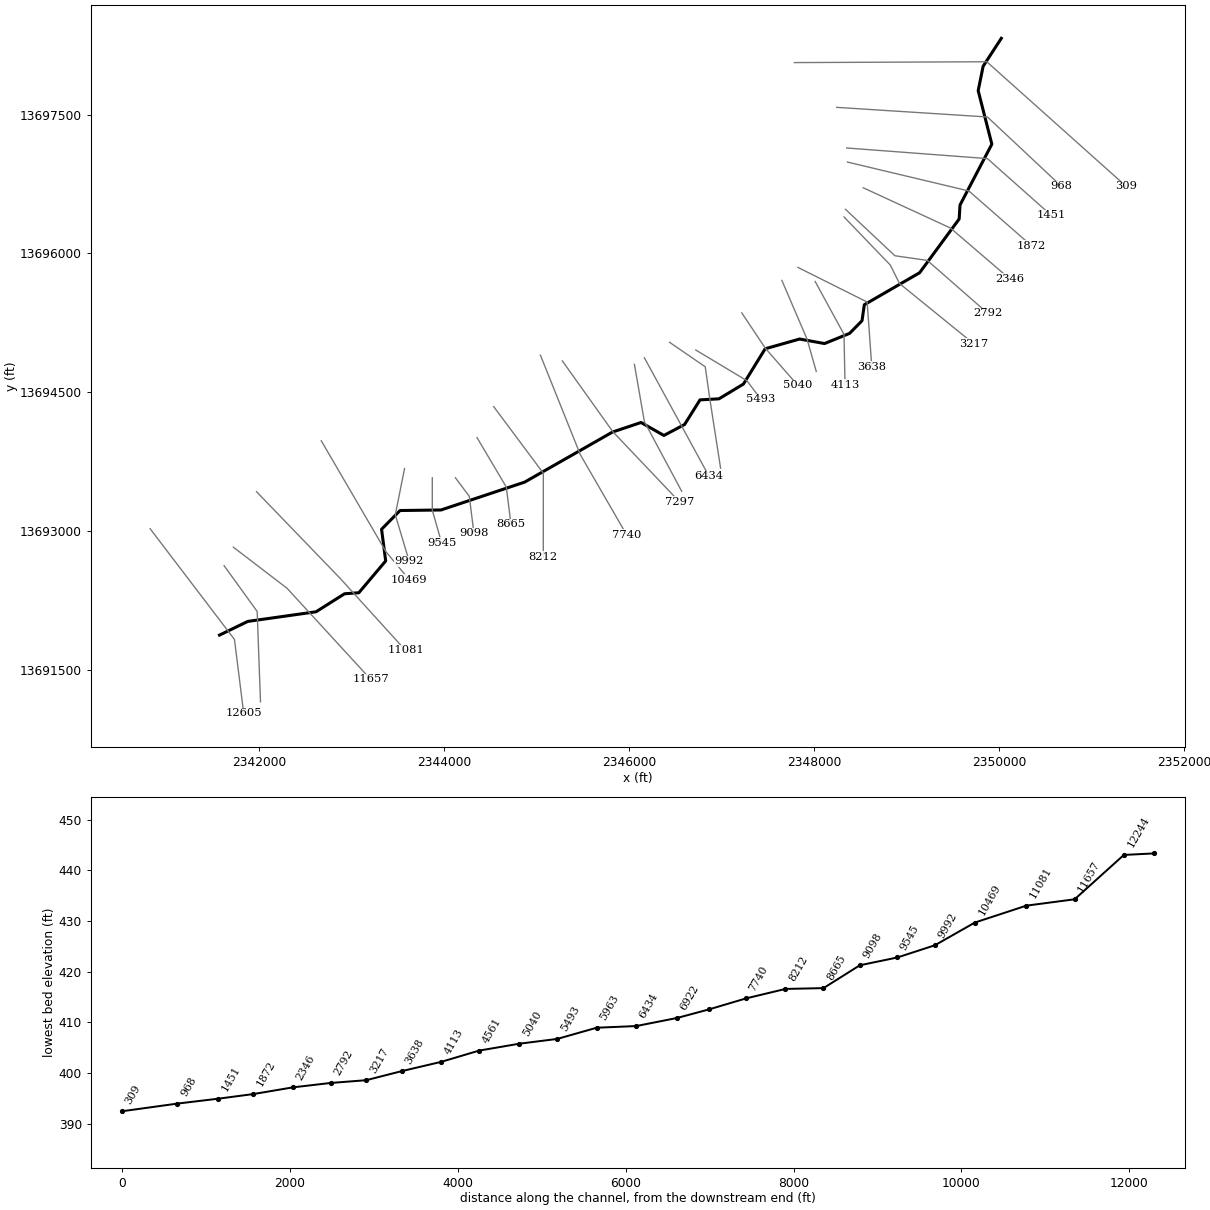
--- Stream0548.prj (project) ---

Proj Title=Stream0548 Base Level Engineering
Current Plan=p01
Default Exp/Contr=0.3,0.1
English Units
Geom File=g01
Flow File=f01
Plan File=p01
Y Axis Title=Elevation
X Axis Title(PF)=Main Channel Distance
X Axis Title(XS)=Station
BEGIN DESCRIPTION:
Stream0548
END DESCRIPTION:
DSS Export Rating Curves= 0
DSS Export Rating Curve Sorted= 0
DSS Export Volume Flow Curves= 0
DXF OffsetX= 0
DXF OffsetY= 0
DXF ScaleX= 1
DXF ScaleY= 10

--- Stream0548.p01 (plan) ---

Plan Title=Multiple Run
Short Identifier=Multiple
Geom File=g01
Flow File=f01
Subcritical Flow
K Sum by GR= 0
Std Step Tol= 0.01
Critical Tol= 0.01
Num of Std Step Trials= 20
Max Error Tol= 0.3
Flow Tol Ratio= 0.001
Split Flow NTrial= 30
Split Flow Tol= 0.02
Split Flow Ratio= 0.02
Log Output Level= 0
Friction Slope Method= 1
Unsteady Friction Slope Method= 2
Unsteady Bridges Friction Slope Method= 1
Parabolic Critical Depth
Global Vel Dist=  1 , 1 , 1
Global Log Level= 0
CheckData=True
Encroach Param= -1, 0, 0, 0
BEGIN DESCRIPTION:
Multiple Run
END DESCRIPTION:

--- Stream0548.f01 (steady flow) ---

Flow Title=Multiple
Number of Profiles=7
Profile Names=10-year,25-year,50-year,1pct_min,100-year,1pct_plu,500-year
River Rch & RM= Stream0548,Reach-1,12605
     714    1169    1584    1039    2074    4137    3524
River Rch & RM= Stream0548,Reach-1,9992
     956    1588    2175    1440    2874    5733    4976
River Rch & RM= Stream0548,Reach-1,7740
    1241    2083    2871    1912    3814    7610    6680
River Rch & RM= Stream0548,Reach-1,3217
    1325    2224    3066    2040    4071    8123    7123
Boundary for River Rch & Prof#=Stream0548,Reach-1,1
Up Type=0
Dn Type=3
Dn Slope=0.005
Boundary for River Rch & Prof#=Stream0548,Reach-1,2
Up Type=0
Dn Type=3
Dn Slope=0.005
Boundary for River Rch & Prof#=Stream0548,Reach-1,3
Up Type=0
Dn Type=3
Dn Slope=0.005
Boundary for River Rch & Prof#=Stream0548,Reach-1,4
Up Type=0
Dn Type=3
Dn Slope=0.005
Boundary for River Rch & Prof#=Stream0548,Reach-1,5
Up Type=0
Dn Type=3
Dn Slope=0.005
Boundary for River Rch & Prof#=Stream0548,Reach-1,6
Up Type=0
Dn Type=3
Dn Slope=0.005
Boundary for River Rch & Prof#=Stream0548,Reach-1,7
Up Type=0
Dn Type=3
Dn Slope=0.005

--- Stream0548.g01 (geometry) ---

Geom Title=Existing Conditions
Program Version=4.10

River Reach=Stream0548      ,Reach-1
Reach XY= 30
        2341575.       13691875.      2341880.86     13692022.93
      2342619.06     13692127.26      2342926.27     13692321.52
      2343081.19     13692332.82      2343371.25     13692676.55
      2343326.62     13693018.97      2343526.47     13693221.46
      2343969.07     13693227.24       2344873.5     13693528.62
      2345822.56     13694069.52      2346130.97     13694172.86
      2346378.23     13694032.84      2346601.88     13694151.27
      2346768.52     13694417.31      2346973.45     13694428.75
      2347238.24     13694588.62      2347472.57     13694969.48
      2347845.04     13695074.95      2348114.45      13695026.1
      2348384.68     13695135.76      2348519.53     13695272.55
      2348544.44     13695445.55      2349142.05     13695791.49
      2349569.52     13696372.56      2349578.76     13696523.44
      2349922.74     13697180.94      2349775.09     13697759.61
      2349828.75     13698023.45        2350025.       13698325.

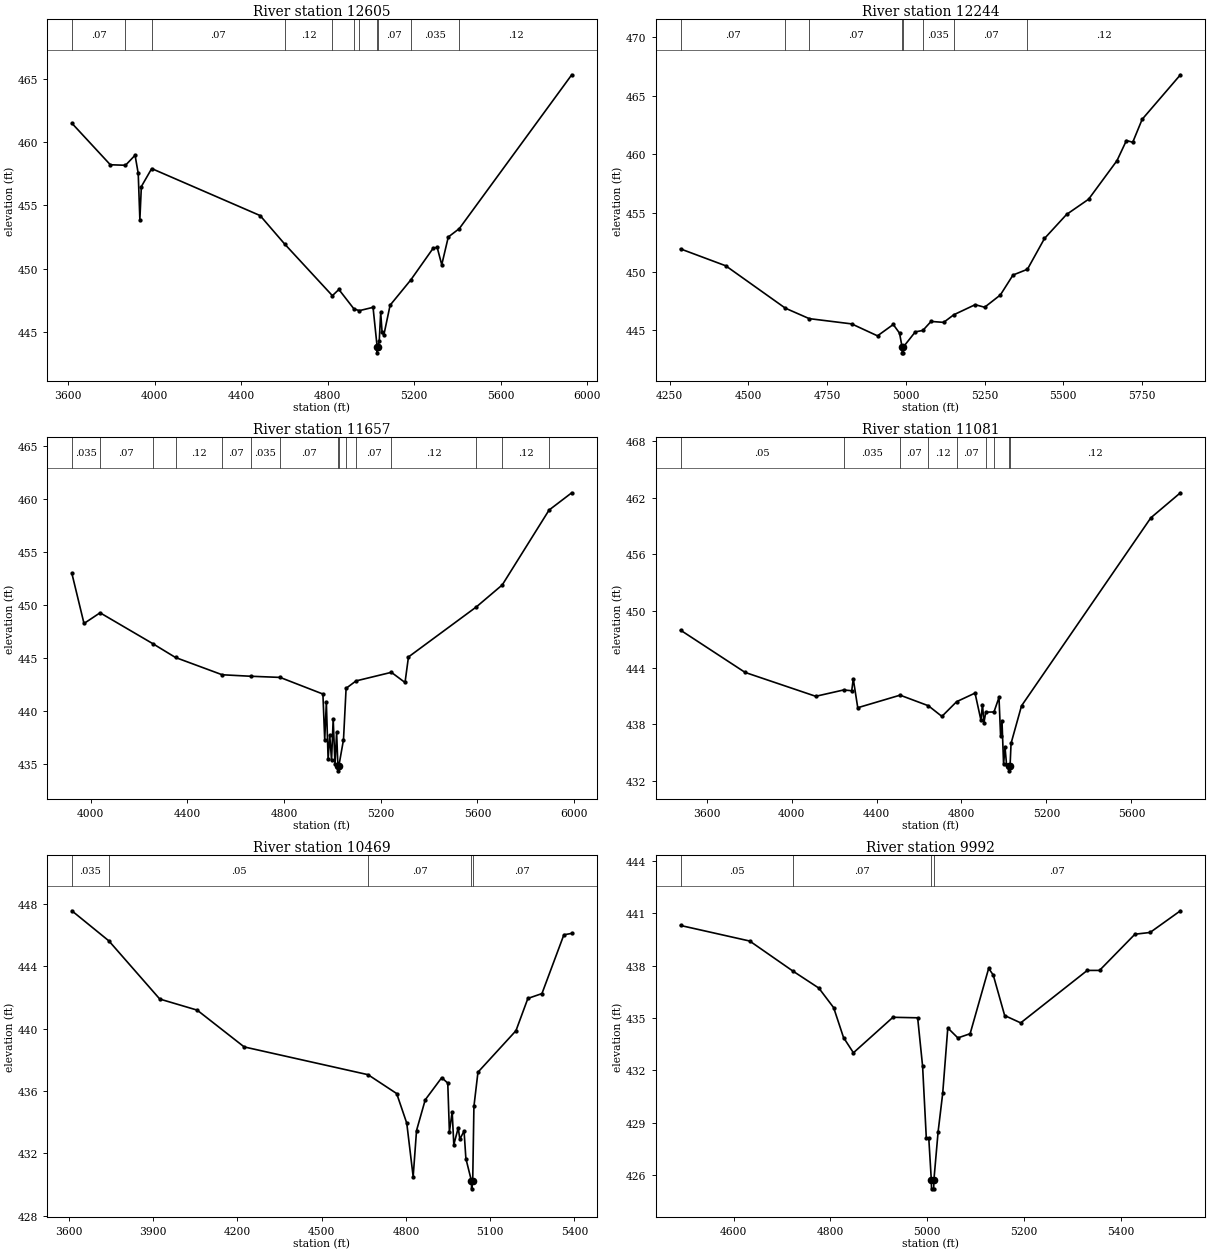
Type RM Length L Ch R = 1 ,12605   ,361,361,361
BEGIN DESCRIPTION:
Stream0548 27.0
END DESCRIPTION:
XS GIS Cut Line= 3
      2340824.99     13693025.01      2341736.81     13691827.85
      2341836.68     13691028.93
#Sta/Elev= 30
  3617.7  461.49  3795.5  458.21  3865.6  458.17  3909.8  458.96  3924.4  457.53
    3932  453.88  3938.9  456.49  3986.6  457.91  4487.8   454.2  4600.4  451.97
  4821.6  447.88  4851.6  448.37  4921.6  446.83  4946.4   446.7  5009.5  446.96
  5028.3  443.87  5028.6  443.37  5032.3  443.87  5038.2  444.31  5044.9  446.56
  5051.2     445  5059.4  444.78  5088.4  447.13  5183.8  449.12  5286.7  451.61
  5305.7   451.7    5327  450.32  5357.2  452.51    5408  453.17  5927.7  465.31
#Mann= 11 ,-1 , 0
  3617.7     .07       0  3865.6    .035       0  3986.6     .07       0
  4600.4     .12       0  4821.6     .07       0  4921.6    .035       0
  4946.4     .07       0  5028.3     .05       0  5032.3     .07       0
  5183.8    .035       0    5408     .12       0
Bank Sta=5028.3,5032.3
XS Rating Curve= 0 ,0
Exp/Cntr=0.3,0.1

Type RM Length L Ch R = 1 ,12244   ,587,587,587
BEGIN DESCRIPTION:
Stream0548 26.0
END DESCRIPTION:
XS GIS Cut Line= 3
      2341624.99     13692625.02      2341982.24     13692130.42
      2342018.09     13691153.61
#Sta/Elev= 30
  4284.3  451.94  4427.8   450.5  4617.3  446.88    4693  445.99  4827.8  445.54
  4909.9  444.52  4959.9  445.49  4979.9  444.75  4987.9  443.57  4988.2  443.07
  4991.7  443.07  4991.9  443.57  5029.9  444.86  5053.8  444.98    5080  445.75
    5120  445.67  5152.2  446.32  5220.1  447.18  5250.1  446.96  5300.1  448.01
  5340.2  449.71    5386   450.2  5440.2  452.83  5510.3  454.88  5580.3  456.18
  5670.4  459.47  5700.4  461.19  5720.4  461.04  5750.4     463  5871.9   466.8
#Mann= 8 ,-1 , 0
  4284.3     .07       0  4617.3    .035       0    4693     .07       0
  4987.9     .05       0  4991.9     .07       0  5053.8    .035       0
  5152.2     .07       0    5386     .12       0
Bank Sta=4987.9,4991.9
XS Rating Curve= 0 ,0
Exp/Cntr=0.3,0.1

Type RM Length L Ch R = 1 ,11657   ,576,576,576
BEGIN DESCRIPTION:
Stream0548 25.0
END DESCRIPTION:
XS GIS Cut Line= 3
      2341725.03     13692824.98      2342304.85     13692381.34
      2343209.94     13691395.61
#Sta/Elev= 30
  3921.7  452.96    3972  448.22  4038.5  449.23  4255.6  446.33  4350.6  445.01
  4543.7  443.38    4661  443.24  4783.3  443.13  4960.5  441.56  4967.9  437.23
  4974.7  440.77    4982   435.4  4988.8  437.65  4996.2   435.3    5003  439.21
  5010.4  434.91  5017.2  437.96  5022.4  434.81  5022.7  434.31  5026.7  434.81
  5045.6  437.24  5056.4   442.1  5097.6   442.8  5243.7  443.61  5300.2  442.65
  5314.4  445.06    5595  449.78  5702.5  451.86  5896.2  458.93    5990  460.56
#Mann= 15 ,-1 , 0
  3921.7    .035       0  4038.5     .07       0  4255.6    .035       0
  4350.6     .12       0  4543.7     .07       0    4661    .035       0
  4783.3     .07       0  5022.4     .05       0  5026.7     .07       0
  5056.4     .12       0  5097.6     .07       0  5243.7     .12       0
    5595     .07       0  5702.5     .12       0  5896.2     .07       0
Bank Sta=5022.4,5026.7
XS Rating Curve= 0 ,0
Exp/Cntr=0.3,0.1

Type RM Length L Ch R = 1 ,11081   ,612,612,612
BEGIN DESCRIPTION:
Stream0548 24.0
END DESCRIPTION:
XS GIS Cut Line= 3
      2341974.97     13693425.03      2342878.38     13692488.88
      2343586.01     13691709.59
#Sta/Elev= 30
  3477.2  447.96  3781.4  443.48  4113.8  440.95  4244.8  441.62  4283.3  441.54
  4290.5   442.8  4311.6  439.74    4511  441.07    4644  439.95  4707.8  438.82
  4777.1  440.38  4863.8  441.29  4891.5  438.43  4898.9  440.07  4905.7  438.14
  4914.3  439.27    4953  439.29  4976.6  440.83  4984.1  436.74  4990.8  438.29
  4998.2  433.75    5005  435.55  5012.4  433.67  5024.3  433.55  5024.6  433.05
  5028.7  433.55  5033.4  435.96  5082.7  439.94  5691.6  459.87  5830.8  462.52
#Mann= 9 ,-1 , 0
  3477.2     .05       0  4244.8    .035       0    4511     .07       0
    4644     .12       0  4777.1     .07       0  4914.3     .12       0
    4953     .07       0  5024.3     .05       0  5028.7     .12       0
Bank Sta=5024.3,5028.7
XS Rating Curve= 0 ,0
Exp/Cntr=0.3,0.1

Type RM Length L Ch R = 1 ,10469   ,477,477,477
BEGIN DESCRIPTION:
Stream0548 23.0
END DESCRIPTION:
XS GIS Cut Line= 3
        2342675.       13693975.        2343375.       13692775.
      2343625.03     13692474.97
#Sta/Elev= 30
  3610.6  447.55  3742.4  445.62  3923.6  441.89  4056.7  441.18  4224.2  438.82
    4665  437.04  4767.1  435.83    4803  433.93  4825.8   430.5  4837.8  433.46
  4868.8  435.43  4927.5  436.85    4949   436.5  4954.8  433.38  4964.7  434.66
  4970.5  432.55  4986.2  433.63    4992   432.9    5007  433.43  5013.5  431.66
  5033.4  430.22  5033.7  429.72  5037.8  430.22  5042.1     435  5056.5   437.2
  5191.8  439.86  5234.2  441.93  5284.3  442.24  5362.4  446.01  5390.4   446.1
#Mann= 5 ,-1 , 0
  3610.6    .035       0  3742.4     .05       0    4665     .07       0
  5033.4     .05       0  5037.8     .07       0
Bank Sta=5033.4,5037.8
XS Rating Curve= 0 ,0
Exp/Cntr=0.3,0.1

Type RM Length L Ch R = 1 ,9992    ,447,447,447
BEGIN DESCRIPTION:
Stream0548 22.0
END DESCRIPTION:
XS GIS Cut Line= 3
        2343575.       13693675.        2343475.       13693175.
      2343624.99     13692675.02
#Sta/Elev= 30
  4490.6  440.29  4633.4   439.4  4722.7  437.68  4776.1  436.71  4806.7  435.59
  4827.1  433.88  4847.5  433.01  4929.1  435.04  4980.1  435.01  4990.3  432.24
    4998  428.11  5003.1  428.11  5008.3  425.73  5008.7  425.23  5013.2  425.23
  5013.6  425.73  5022.3  428.49  5031.8  430.69  5042.3  434.43  5063.1  433.86
  5088.4   434.1  5126.7  437.84  5136.2  437.45  5159.7  435.14  5192.8  434.72
  5330.2  437.72  5355.5  437.72  5428.6  439.79  5459.9  439.89  5522.5  441.13
#Mann= 4 ,-1 , 0
  4490.6     .05       0  4722.7     .07       0  5008.3     .05       0
  5013.6     .07       0
Bank Sta=5008.3,5013.6
XS Rating Curve= 0 ,0
Exp/Cntr=0.3,0.1

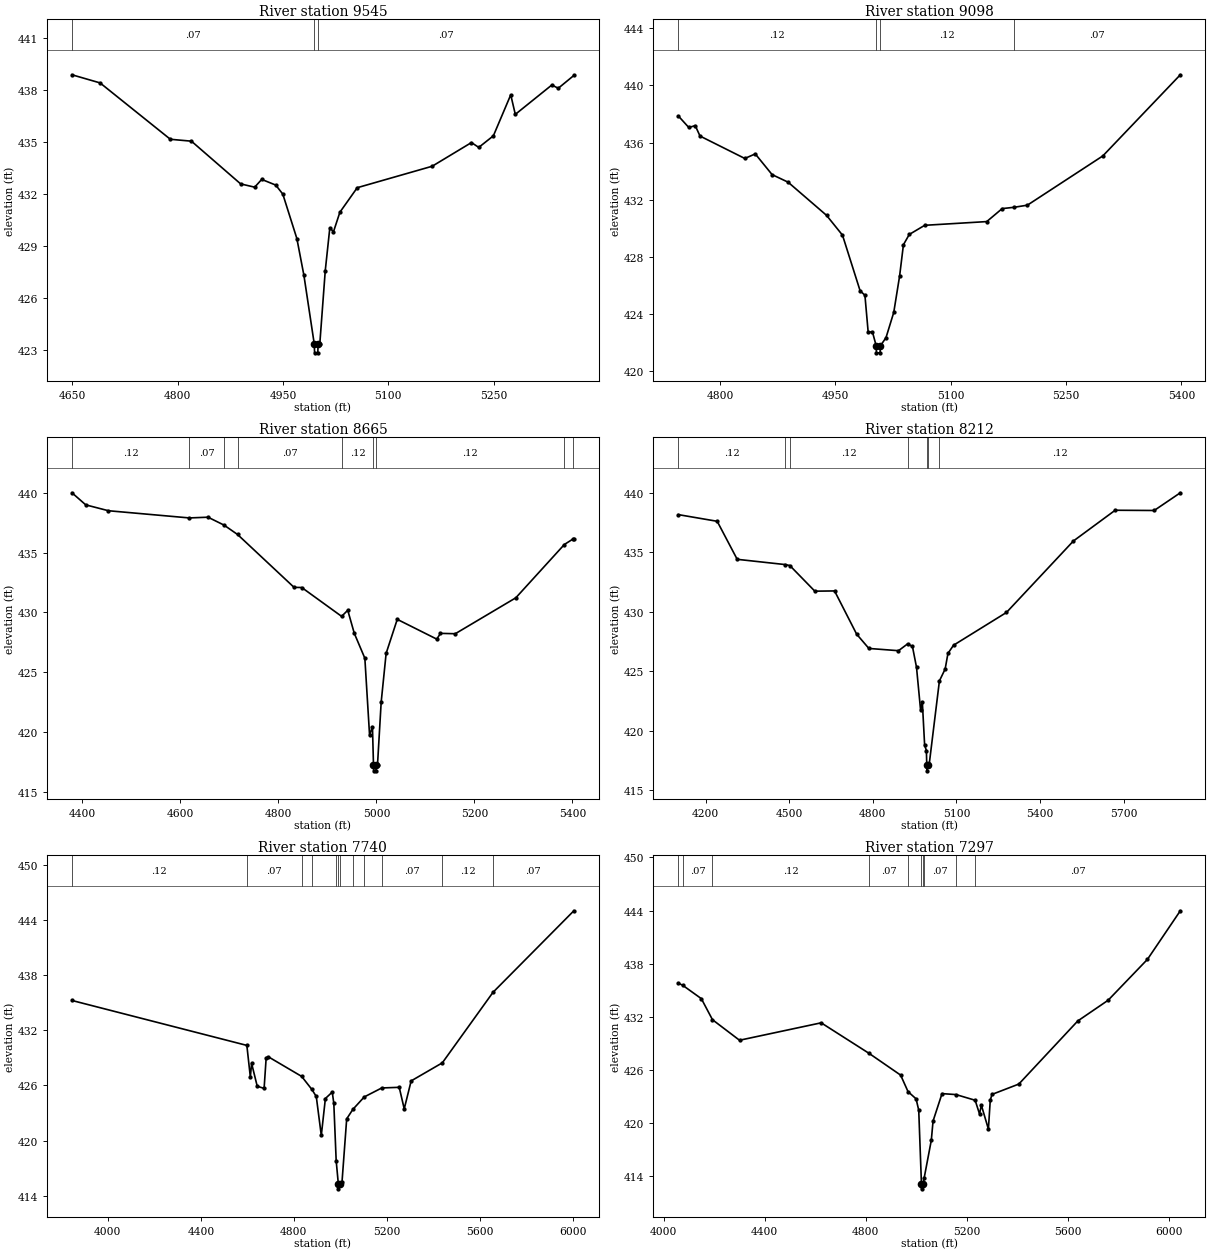
Type RM Length L Ch R = 1 ,9545    ,447,447,447
BEGIN DESCRIPTION:
Stream0548 21.0
END DESCRIPTION:
XS GIS Cut Line= 3
        2343875.     13693575.04        2343875.       13693225.
      2343975.01     13692874.95
#Sta/Elev= 30
  4649.8   438.9  4689.8  438.43  4789.8  435.17  4819.8  435.06  4889.8  432.59
  4909.8   432.4  4919.8  432.85  4939.8  432.52  4949.8     432  4969.8  429.43
  4979.8  427.31  4994.6  423.32    4995  422.82  4999.6  422.82    5000  423.32
  5002.4  423.32  5010.2  427.57  5016.7  430.05  5021.9  429.82    5031  430.95
  5055.7  432.37  5162.3  433.61  5218.2  434.98  5228.6   434.7  5249.4  435.37
  5274.1  437.74  5280.6  436.61  5332.6  438.31  5341.7  438.12  5363.9  438.86
#Mann= 3 ,-1 , 0
  4649.8     .07       0  4994.6     .05       0    5000     .07       0
Bank Sta=4994.6,5000
XS Rating Curve= 0 ,0
Exp/Cntr=0.3,0.1

Type RM Length L Ch R = 1 ,9098    ,433,433,433
BEGIN DESCRIPTION:
Stream0548 20.0
END DESCRIPTION:
XS GIS Cut Line= 3
      2344125.01     13693574.99        2344275.       13693375.
        2344325.       13692975.
#Sta/Elev= 30
  4745.6  437.86  4759.1  437.06  4767.5  437.19  4773.7  436.46    4832  434.89
  4845.6  435.21  4867.5  433.76  4888.3  433.23  4938.3  430.91  4959.1  429.52
    4982  425.63  4988.3  425.31  4992.5  422.74  4998.1  422.74  5002.9  421.78
  5003.3  421.28    5008  421.28  5008.5  421.78  5015.7  422.34  5025.8  424.11
  5033.4  426.65  5038.4  428.85    5046  429.57  5066.1  430.21  5146.8  430.47
  5166.9  431.38  5182.2  431.47  5199.7  431.62  5297.9  435.07  5398.7  440.75
#Mann= 4 ,-1 , 0
  4745.6     .12       0  5002.9     .05       0  5008.5     .12       0
  5182.2     .07       0
Bank Sta=5002.9,5008.5
XS Rating Curve= 0 ,0
Exp/Cntr=0.3,0.1

Type RM Length L Ch R = 1 ,8665    ,453,453,453
BEGIN DESCRIPTION:
Stream0548 19.0
END DESCRIPTION:
XS GIS Cut Line= 3
      2344358.47     13694009.12        2344675.       13693475.
        2344725.     13693074.98
#Sta/Elev= 30
  4378.8  439.99    4407  438.98  4453.3  438.49  4618.1  437.89  4656.4  437.95
  4689.1  437.29  4716.6  436.51    4832  432.09  4847.6  432.08    4929  429.67
  4941.5  430.18  4954.8  428.26  4976.4  426.17    4986  419.75  4991.9  420.46
    4994  417.27  4994.4  416.77  4999.1  416.77  4999.6  417.27  5002.2  417.27
  5009.7  422.51  5019.8  426.58  5042.5  429.42  5123.1  427.77  5130.7  428.25
  5160.9  428.22  5284.4  431.22  5383.4  435.67  5401.1  436.13  5402.8  436.13
#Mann= 9 ,-1 , 0
  4378.8     .12       0  4618.1     .07       0  4689.1     .12       0
  4716.6     .07       0    4929     .12       0    4994     .05       0
  4999.6     .12       0  5383.4     .07       0  5401.1     .12       0
Bank Sta=4994,4999.6
XS Rating Curve= 0 ,0
Exp/Cntr=0.3,0.1

Type RM Length L Ch R = 1 ,8212    ,472,472,472
BEGIN DESCRIPTION:
Stream0548 18.0
END DESCRIPTION:
XS GIS Cut Line= 3
      2344538.75     13694344.02        2345075.       13693625.
      2345074.54     13692721.27
#Sta/Elev= 30
  4102.7  438.17  4241.8  437.61  4313.6  434.41  4484.9  433.97  4502.3  433.89
  4592.1  431.73  4662.9  431.75  4742.2  428.11    4786  426.91  4892.3  426.72
  4924.7  427.29  4942.3  427.08  4956.9  425.33  4971.5  421.73  4977.8  422.42
  4986.1  418.76  4992.4  418.32  4993.7  417.11  4994.2  416.61  4999.4  417.11
  5002.2  417.11  5039.1  424.18  5059.7  425.18  5069.7  426.49  5089.7  427.18
  5279.7  429.94  5519.7  435.95  5669.7  438.54  5809.7  438.52  5903.4  440.01
#Mann= 7 ,-1 , 0
  4102.7     .12       0  4484.9     .07       0  4502.3     .12       0
  4924.7     .07       0  4993.7     .05       0  4999.4     .07       0
  5039.1     .12       0
Bank Sta=4993.7,4999.4
XS Rating Curve= 0 ,0
Exp/Cntr=0.3,0.1

Type RM Length L Ch R = 1 ,7740    ,443,443,443
BEGIN DESCRIPTION:
Stream0548 17.0
END DESCRIPTION:
XS GIS Cut Line= 3
      2345043.64     13694900.36        2345475.       13693825.
      2345975.55     13692959.11
#Sta/Elev= 30
  3845.5  435.27  4597.8  430.37  4612.8  426.92  4618.2  428.41  4642.4  425.92
    4672  425.68  4680.9  429.02  4690.8  429.12  4833.5  426.99  4877.1  425.58
  4896.4   424.8    4918  420.55  4935.6  424.58  4965.1  425.28  4971.8  424.06
    4982   417.8  4991.4  415.23  4991.9  414.73  4998.1  415.23    5007  415.44
  5027.2  422.36  5053.7  423.39  5102.7  424.75    5178  425.73  5253.2   425.8
  5274.7  423.45  5304.5   426.5  5438.6  428.47  5656.6  436.16  6004.3  445.05
#Mann= 12 ,-1 , 0
  3845.5     .12       0  4597.8     .07       0  4833.5     .12       0
  4877.1     .07       0    4982     .12       0  4991.4     .05       0
  4998.1     .12       0  5053.7     .07       0  5102.7     .12       0
    5178     .07       0  5438.6     .12       0  5656.6     .07       0
Bank Sta=4991.4,4998.1
XS Rating Curve= 0 ,0
Exp/Cntr=0.3,0.1

Type RM Length L Ch R = 1 ,7297    ,375,375,375
BEGIN DESCRIPTION:
Stream0548 16.0
END DESCRIPTION:
XS GIS Cut Line= 3
      2345280.59     13694838.56        2345825.       13694075.
      2346547.88     13693313.69
#Sta/Elev= 30
    4058  435.78  4074.5  435.56  4148.8  434.04  4192.9  431.66    4300  429.34
  4623.3  431.31  4812.9  427.86    4938   425.4  4967.4  423.53  4999.2  422.72
  5009.7  421.43  5020.5  413.05    5021  412.55  5027.2  413.05  5030.9  413.73
  5059.5  418.04  5066.4  420.21  5101.9  423.31  5157.4   423.2  5233.1  422.56
  5250.4  421.01  5257.7     422  5285.6   419.3  5292.9  422.56  5299.8  423.22
  5406.1  424.39  5639.5  431.52  5759.7  433.86  5915.4  438.48  6045.6  443.97
#Mann= 10 ,-1 , 0
    4058     .12       0  4074.5     .07       0  4192.9     .12       0
  4812.9     .07       0  4967.4     .12       0  5020.5     .05       0
  5027.2     .12       0  5030.9     .07       0  5157.4     .12       0
  5233.1     .07       0
Bank Sta=5020.5,5027.2
XS Rating Curve= 0 ,0
Exp/Cntr=0.3,0.1

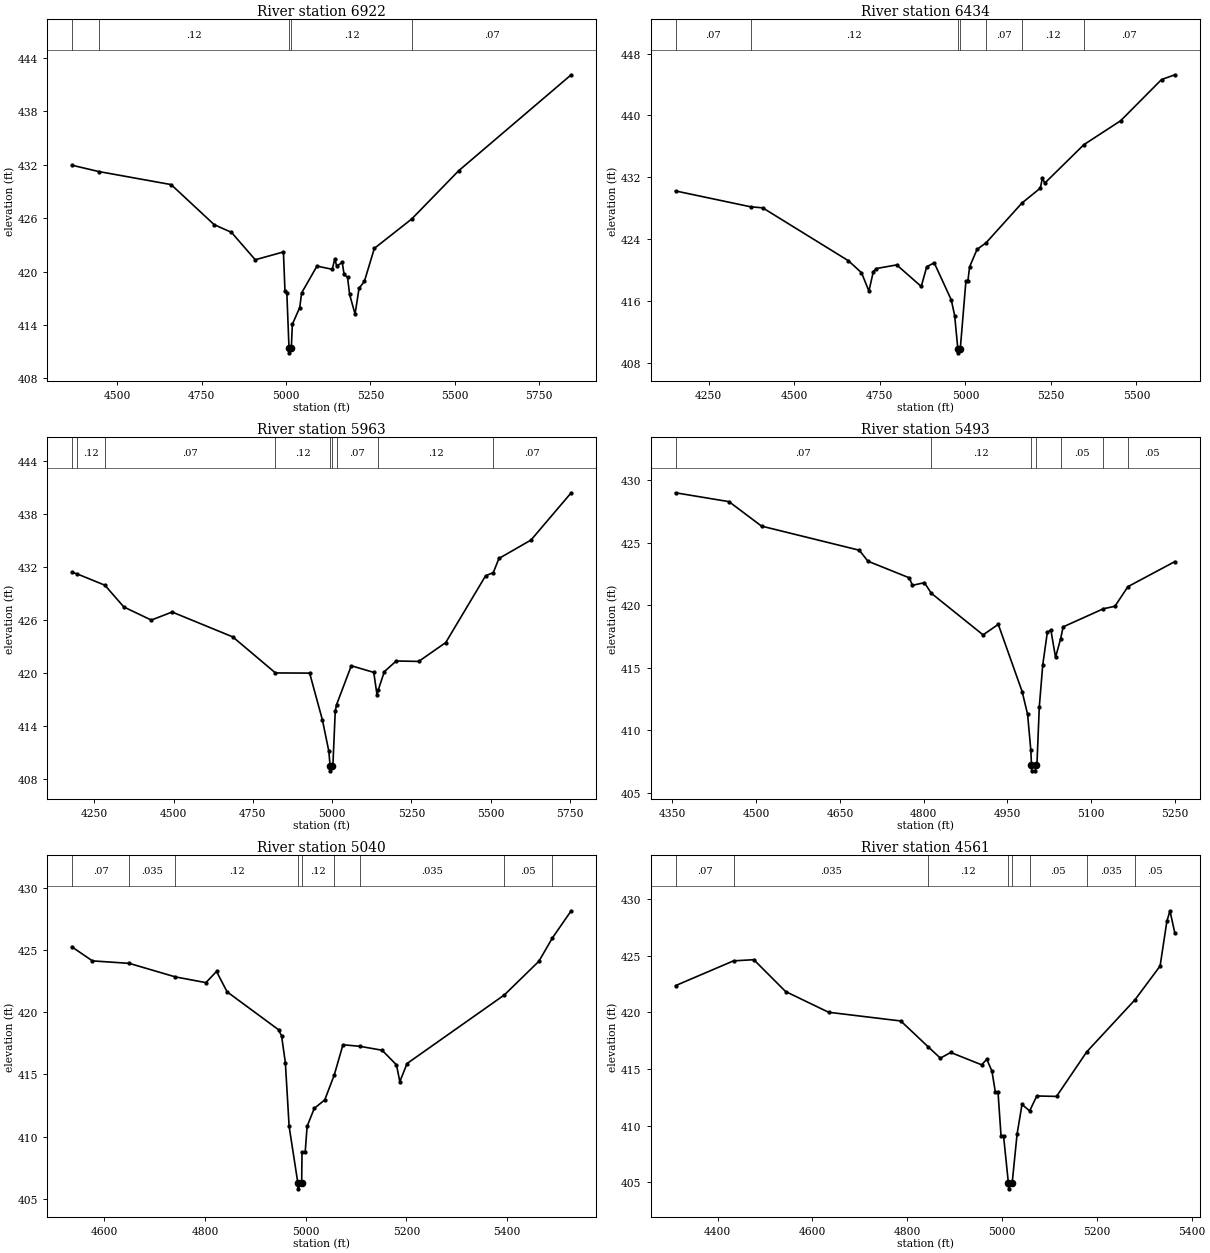
Type RM Length L Ch R = 1 ,6922    ,488,488,488
BEGIN DESCRIPTION:
Stream0548 15.0
END DESCRIPTION:
XS GIS Cut Line= 3
      2346059.67     13694800.95      2346167.21     13694182.58
      2346570.18     13693430.37
#Sta/Elev= 30
  4364.7  431.95    4444  431.24  4659.2  429.77  4786.9  425.27  4838.1  424.41
  4908.7  421.33  4992.3  422.21  4996.8  417.82  5002.4   417.6  5008.8  411.38
  5009.3  410.88  5015.7  411.38  5018.7  414.08  5040.6  415.97  5046.3  417.61
  5091.7  420.62  5137.1  420.26  5144.6  421.43  5150.3  420.61  5166.6  421.04
  5172.2  419.68  5182.5  419.34  5188.5  417.44  5204.7  415.23  5216.5  418.12
  5232.4  418.91  5261.9  422.61  5372.8  425.91  5511.8  431.32  5845.7   442.1
#Mann= 5 ,-1 , 0
  4364.7     .07       0    4444     .12       0  5008.8     .05       0
  5015.7     .12       0  5372.8     .07       0
Bank Sta=5008.8,5015.7
XS Rating Curve= 0 ,0
Exp/Cntr=0.3,0.1

Type RM Length L Ch R = 1 ,6434    ,471,471,471
BEGIN DESCRIPTION:
Stream0548 14.0
END DESCRIPTION:
XS GIS Cut Line= 3
       2346167.2     13694872.64        2346575.       13694125.
      2346866.18     13693591.17
#Sta/Elev= 30
  4152.7  430.23    4372  428.18  4407.7  428.04  4658.3  421.19  4696.3  419.65
  4718.1  417.27  4730.9  419.79    4740  420.19  4799.3  420.66    4871  417.87
  4887.1  420.42  4908.9  420.93  4958.8  416.13  4968.7  414.09    4978  409.78
  4978.5  409.28  4985.1  409.78  5001.5  418.53  5007.2  418.53  5012.4  420.42
  5034.2  422.67  5060.5  423.52  5165.3  428.66  5219.3   430.6    5225  431.91
  5232.1  431.24  5346.2  436.21  5453.8  439.31  5573.4  444.64  5612.4  445.26
#Mann= 7 ,-1 , 0
  4152.7     .07       0    4372     .12       0    4978     .05       0
  4985.1     .12       0  5060.5     .07       0  5165.3     .12       0
  5346.2     .07       0
Bank Sta=4978,4985.1
XS Rating Curve= 0 ,0
Exp/Cntr=0.3,0.1

Type RM Length L Ch R = 1 ,5963    ,470,470,470
BEGIN DESCRIPTION:
Stream0548 13.0
END DESCRIPTION:
XS GIS Cut Line= 4
      2346439.76     13695039.43        2346825.       13694775.
        2346875.       13694425.      2346990.91     13693679.67
#Sta/Elev= 30
  4179.2  431.38  4195.7   431.2  4283.4  429.92  4343.3  427.46  4429.9  425.98
  4495.6  426.89  4686.9  424.08  4821.5  420.01  4929.3  419.99  4969.7  414.68
  4989.9  411.15  4993.9  409.45  4994.4  408.95    5001  409.45  5002.5  409.45
  5010.1  415.69  5014.3  416.43  5060.7  420.82  5131.6  420.07  5141.7  417.55
  5145.4  418.05  5164.8  420.15  5202.4  421.36  5273.3  421.31  5358.6  423.44
  5484.4  430.99  5508.6  431.34  5526.3  432.94  5627.5  435.02  5754.3  440.36
#Mann= 9 ,-1 , 0
  4179.2     .07       0  4195.7     .12       0  4283.4     .07       0
  4821.5     .12       0  4993.9     .05       0    5001     .12       0
  5014.3     .07       0  5145.4     .12       0  5508.6     .07       0
Bank Sta=4993.9,5001
XS Rating Curve= 0 ,0
Exp/Cntr=0.3,0.1

Type RM Length L Ch R = 1 ,5493    ,453,453,453
BEGIN DESCRIPTION:
Stream0548 12.0
END DESCRIPTION:
XS GIS Cut Line= 4
      2346722.98     13694956.21        2347025.       13694775.
        2347275.       13694625.      2347425.02     13694424.97
#Sta/Elev= 30
  4355.8  429.01  4451.5   428.3  4509.8  426.34  4684.7  424.41  4700.2  423.53
  4774.1   422.2  4779.9   421.6  4801.3  421.81  4813.7  420.96  4906.3  417.63
  4933.5  418.47  4976.2  413.09    4986  411.26  4991.8  408.37  4992.9  407.24
  4993.4  406.74  4999.8  406.74  5000.3  407.24  5002.7  407.24  5006.9  411.84
  5013.1  415.23  5021.4  417.86  5027.7     418    5036  415.83  5045.1  417.32
  5049.6  418.27  5121.6  419.72  5142.3  419.92  5165.5  421.49  5249.6   423.5
#Mann= 7 ,-1 , 0
  4355.8     .07       0  4813.7     .12       0  4992.9     .05       0
  5000.3     .12       0  5045.1     .05       0  5121.6    .035       0
  5165.5     .05       0
Bank Sta=4992.9,5000.3
XS Rating Curve= 0 ,0
Exp/Cntr=0.3,0.1

Type RM Length L Ch R = 1 ,5040    ,479,479,479
BEGIN DESCRIPTION:
Stream0548 11.0
END DESCRIPTION:
XS GIS Cut Line= 4
       2347219.8      13695357.8        2347375.       13695125.
        2347475.       13694975.      2347825.01     13694574.98
#Sta/Elev= 30
  4535.7  425.26  4576.6  424.13  4649.7  423.93  4741.3  422.84    4802  422.38
    4823  423.28    4844  421.64  4946.2  418.59  4952.2  418.09  4959.7  415.95
  4967.2  410.81  4984.4  406.29  4984.9  405.79  4992.1  406.29  4992.8  408.74
  4999.1  408.74  5002.9  410.82  5017.1  412.26    5038  412.95  5056.8  414.95
  5074.1  417.38  5107.1  417.26  5151.9  416.94  5180.4  415.76    5187  414.41
  5201.3  415.87  5394.6  421.39  5463.2   424.1  5489.9  425.97  5527.3  428.16
#Mann= 9 ,-1 , 0
  4535.7     .07       0  4649.7    .035       0  4741.3     .12       0
  4984.4     .05       0  4992.1     .12       0  5056.8     .05       0
  5107.1    .035       0  5394.6     .05       0  5489.9     .07       0
Bank Sta=4984.4,4992.1
XS Rating Curve= 0 ,0
Exp/Cntr=0.3,0.1

Type RM Length L Ch R = 1 ,4561    ,448,448,448
BEGIN DESCRIPTION:
Stream0548 10.0
END DESCRIPTION:
XS GIS Cut Line= 4
      2347653.52     13695708.46        2347775.       13695425.
        2347925.       13695075.        2348025.     13694724.99
#Sta/Elev= 30
  4311.3  422.37  4433.7  424.56  4476.4  424.66  4543.5  421.85  4634.2  420.02
  4786.5  419.25  4843.9  416.98  4869.9  415.97  4891.7  416.47    4957  415.38
  4967.8  415.87  4978.7  414.82    4986  412.94  4991.4  413.02  4997.8  409.13
  5003.1  409.13  5013.4  404.93  5013.9  404.43  5021.3  404.93  5031.7  409.27
  5042.1  411.88  5058.2  411.31  5073.3  412.63  5114.9  412.59  5178.7  416.53
  5280.3  421.12  5333.3   424.1  5347.6  428.05  5354.1  428.98  5364.5  426.99
#Mann= 8 ,-1 , 0
  4311.3     .07       0  4433.7    .035       0  4843.9     .12       0
  5013.4     .05       0  5021.3     .12       0  5058.2     .05       0
  5178.7    .035       0  5280.3     .05       0
Bank Sta=5013.4,5021.3
XS Rating Curve= 0 ,0
Exp/Cntr=0.3,0.1

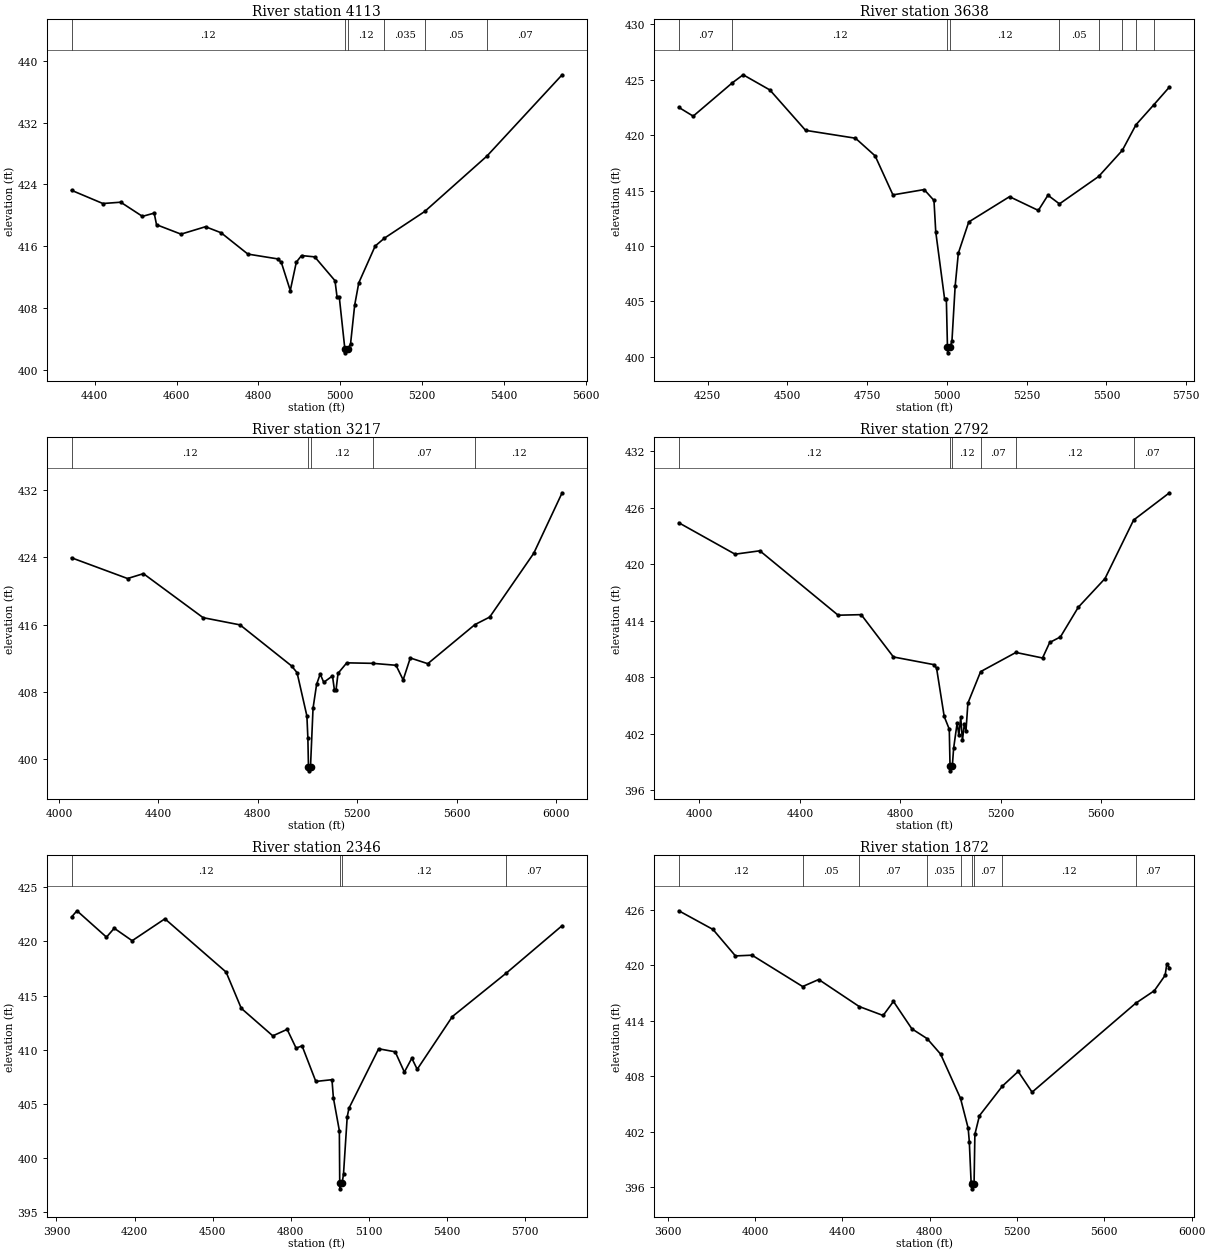
Type RM Length L Ch R = 1 ,4113    ,475,475,475
BEGIN DESCRIPTION:
Stream0548 9.0
END DESCRIPTION:
XS GIS Cut Line= 3
      2348013.26     13695697.05        2348325.       13695125.
      2348335.84     13694578.48
#Sta/Elev= 30
  4343.5  423.24  4420.1  421.53  4463.7   421.7  4516.7  419.87  4545.4  420.29
  4551.1  418.79  4610.9  417.57  4670.7  418.53  4708.7  417.75  4774.2  414.99
  4846.9  414.37  4855.9  413.91  4877.7  410.28  4892.5  413.95  4905.2   414.8
  4937.5  414.63  4986.9  411.55  4992.1  409.38  4997.5  409.38    5011  402.72
  5011.5  402.22  5018.9  402.72    5025  403.42    5035  408.39    5045  411.27
    5085  416.03  5107.6  417.05    5206   420.5    5358  427.67  5541.6  438.18
#Mann= 6 ,-1 , 0
  4343.5     .12       0    5011     .05       0  5018.9     .12       0
  5107.6    .035       0    5206     .05       0    5358     .07       0
Bank Sta=5011,5018.9
XS Rating Curve= 0 ,0
Exp/Cntr=0.3,0.1

Type RM Length L Ch R = 1 ,3638    ,421,421,421
BEGIN DESCRIPTION:
Stream0548 8.0
END DESCRIPTION:
XS GIS Cut Line= 4
      2347827.23     13695848.89        2348375.       13695575.
        2348575.       13695475.        2348625.     13694775.02
#Sta/Elev= 30
  4159.6   422.5  4204.6  421.71  4327.5  424.72  4361.2  425.44    4445  424.07
  4556.8  420.43  4713.3  419.72  4774.8  418.13  4830.7  414.61  4928.6  415.09
  4959.3  414.11  4964.9  411.27  4992.8  405.19  4998.1  405.19  5001.6  400.87
  5002.1  400.37  5009.7  400.87  5015.7  401.46  5025.7  406.39  5035.7  409.36
  5068.3  412.17  5196.1  414.45  5286.4  413.21  5316.5  414.58  5352.6   413.8
  5475.4  416.27  5549.7  418.63  5592.4  420.93  5648.2  422.73  5697.4  424.34
#Mann= 9 ,-1 , 0
  4159.6     .07       0  4327.5     .12       0  5001.6     .05       0
  5009.7     .12       0  5352.6     .05       0  5475.4    .035       0
  5549.7     .05       0  5592.4    .035       0  5648.2     .05       0
Bank Sta=5001.6,5009.7
XS Rating Curve= 0 ,0
Exp/Cntr=0.3,0.1

Type RM Length L Ch R = 1 ,3217    ,425,425,425
BEGIN DESCRIPTION:
Stream0548 7.0
END DESCRIPTION:
XS GIS Cut Line= 4
      2348325.24     13696394.32        2348825.       13695875.
        2348925.       13695675.      2349724.99     13695025.01
#Sta/Elev= 30
  4050.1  423.96  4275.7  421.49  4339.5  422.07  4579.8  416.83  4728.5  415.97
  4935.7  411.09  4958.1  410.28  4997.7  405.12  5001.6  402.49    5004  399.09
  5004.5  398.59  5012.2  399.09  5022.4  406.04  5036.8  408.89  5051.2  410.12
  5065.5  409.13  5100.7  409.89  5108.7  408.16  5115.1  408.25    5123   410.2
  5158.2  411.45  5262.7  411.39  5356.4  411.16  5385.2  409.42  5413.9  412.03
  5484.3  411.35  5673.9     416  5733.6   416.9    5911   424.5  6025.2   431.7
#Mann= 5 ,-1 , 0
  4050.1     .12       0    5004     .05       0  5012.2     .12       0
  5262.7     .07       0  5673.9     .12       0
Bank Sta=5004,5012.2
XS Rating Curve= 0 ,0
Exp/Cntr=0.3,0.1

Type RM Length L Ch R = 1 ,2792    ,446,446,446
BEGIN DESCRIPTION:
Stream0548 6.0
END DESCRIPTION:
XS GIS Cut Line= 5
      2348340.67     13696476.77        2348875.       13695975.
        2349225.       13695925.        2349625.       13695575.
      2349876.99     13695354.51
#Sta/Elev= 30
  3918.2  424.42    4142  421.08  4240.7  421.44  4552.3  414.59  4644.1  414.65
  4772.4  410.15    4934  409.33  4944.1  408.96  4974.5  403.82  4994.7  402.47
  4997.7  398.54  4998.2  398.04  5006.8  398.54  5011.9  400.42  5026.1  403.15
  5032.8  401.83  5040.3  403.73    5047  401.27  5054.6  403.01  5061.2  402.31
  5068.8  405.24  5119.5  408.59    5260  410.63  5365.9  410.04  5394.4  411.69
  5437.1  412.28  5508.3  415.44  5614.6  418.49  5728.4  424.71  5871.1  427.61
#Mann= 6 ,-1 , 0
  3918.2     .12       0  4997.7     .05       0  5006.8     .12       0
  5119.5     .07       0    5260     .12       0  5728.4     .07       0
Bank Sta=4997.7,5006.8
XS Rating Curve= 0 ,0
Exp/Cntr=0.3,0.1

Type RM Length L Ch R = 1 ,2346    ,474,474,474
BEGIN DESCRIPTION:
Stream0548 5.0
END DESCRIPTION:
XS GIS Cut Line= 4
      2348533.02     13696709.69        2349475.       13696275.
        2349825.       13695975.      2350117.98     13695723.87
#Sta/Elev= 30
  3957.9  422.23  3978.8  422.81  4092.2  420.38    4122   421.2  4190.8  420.05
  4316.6  422.07  4551.6  417.16  4609.9  413.82    4731  411.28  4786.1  411.88
  4820.5  410.15  4843.4  410.36  4896.2  407.08  4958.2  407.24  4963.7  405.56
  4986.6  402.54    4988  397.68  4988.5  397.18  4997.1  397.68  5002.5  398.54
  5016.7   403.8  5023.3   404.6  5137.5  410.09  5201.1  409.81  5236.3  407.94
  5264.8  409.22  5285.6   408.2  5420.6  413.06  5628.4  417.08  5842.2  421.44
#Mann= 4 ,-1 , 0
  3957.9     .12       0    4988     .05       0  4997.1     .12       0
  5628.4     .07       0
Bank Sta=4988,4997.1
XS Rating Curve= 0 ,0
Exp/Cntr=0.3,0.1

Type RM Length L Ch R = 1 ,1872    ,421,421,421
BEGIN DESCRIPTION:
Stream0548 4.0
END DESCRIPTION:
XS GIS Cut Line= 4
      2348362.78     13696987.49        2349675.       13696675.
        2350075.       13696325.      2350351.03     13696083.48
#Sta/Elev= 30
  3651.1  425.91  3807.6  423.89  3910.4  421.03  3986.5  421.11  4218.2  417.72
  4291.8  418.48  4477.2  415.56  4586.8  414.59  4634.1  416.11  4718.4  413.15
  4788.3  412.09  4849.9  410.42  4941.3  405.63  4976.4   402.4  4981.5  400.96
  4989.7  396.62  4992.8  396.35  4993.3  395.85    5002  396.35  5003.3  396.35
  5007.1  401.75    5028  403.76  5133.2  406.96  5205.5  408.54  5269.1   406.3
  5743.4  415.91  5829.1  417.27  5878.4  418.93    5886  420.14  5898.3  419.77
#Mann= 9 ,-1 , 0
  3651.1     .12       0  4218.2     .05       0  4477.2     .07       0
  4788.3    .035       0  4941.3     .07       0  4992.8     .05       0
    5002     .07       0  5133.2     .12       0  5743.4     .07       0
Bank Sta=4992.8,5002
XS Rating Curve= 0 ,0
Exp/Cntr=0.3,0.1

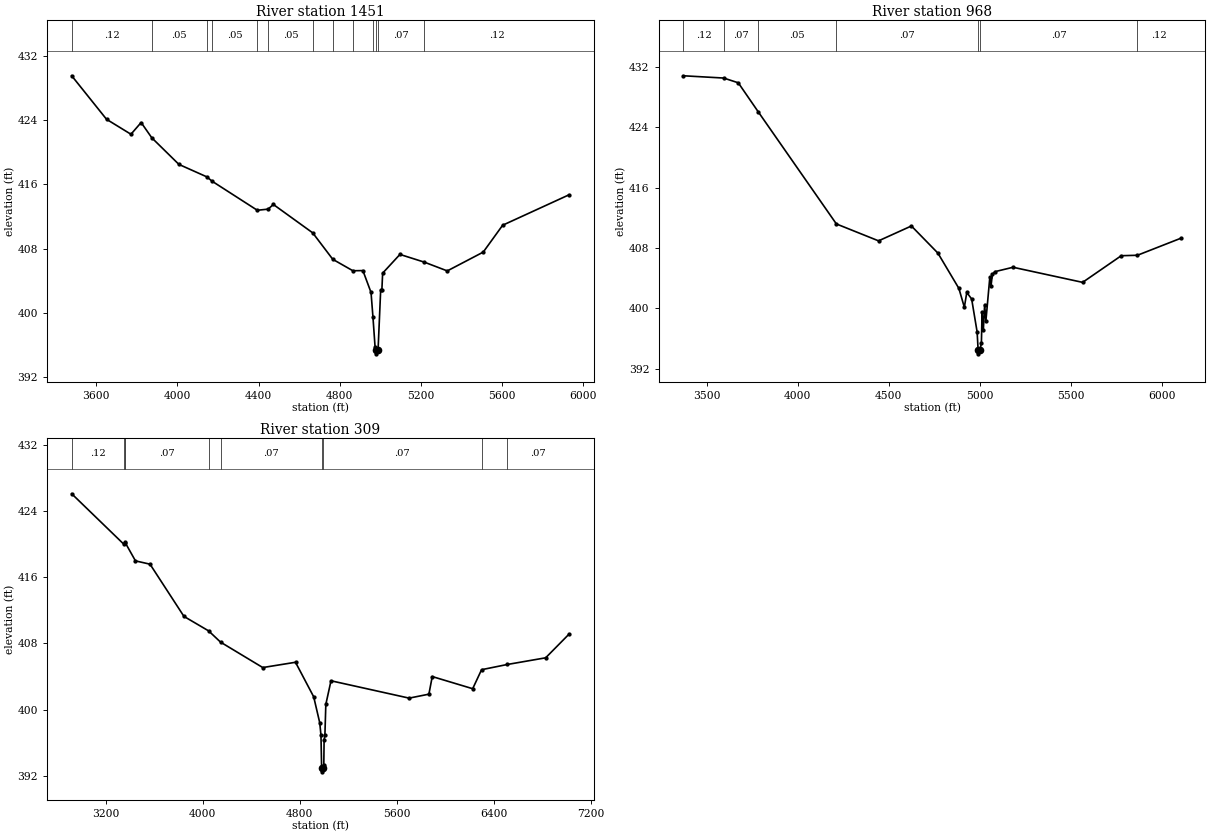
Type RM Length L Ch R = 1 ,1451    ,483,483,483
BEGIN DESCRIPTION:
Stream0548 3.0
END DESCRIPTION:
XS GIS Cut Line= 4
      2348353.82     13697139.84        2349875.       13697025.
        2350325.       13696625.      2350566.19     13696410.61
#Sta/Elev= 30
  3478.7   429.5  3650.4  424.09  3770.7  422.23  3820.9  423.69  3873.4  421.79
  4007.2  418.48  4144.1  416.94    4172  416.37  4393.5  412.78  4446.8  412.92
  4472.7   413.5  4666.7  409.97  4765.6  406.68  4864.6  405.26    4914  405.28
  4954.1  402.56  4963.5  399.52  4974.1  395.75  4979.6  395.43  4980.1  394.93
  4988.8  395.43  5001.7  402.91  5007.6  402.91  5011.3  404.96  5096.6  407.29
  5216.7  406.33  5329.9  405.24  5507.2  407.58  5602.9  410.92    5929  414.69
#Mann= 13 ,-1 , 0
  3478.7     .12       0  3873.4     .05       0  4144.1     .07       0
    4172     .05       0  4393.5     .07       0  4446.8     .05       0
  4666.7    .035       0  4765.6     .07       0  4864.6     .12       0
  4963.5     .07       0  4979.6     .05       0  4988.8     .07       0
  5216.7     .12       0
Bank Sta=4979.6,4988.8
XS Rating Curve= 0 ,0
Exp/Cntr=0.3,0.1

Type RM Length L Ch R = 1 ,968     ,659,659,659
BEGIN DESCRIPTION:
Stream0548 2.0
END DESCRIPTION:
XS GIS Cut Line= 3
       2348246.3     13697578.95        2349875.       13697475.
        2350675.       13696725.
#Sta/Elev= 30
  3373.2  430.81  3593.9  430.51  3674.1  429.88  3783.3  426.05  4212.6  411.18
  4444.1  408.94  4624.4  410.91  4769.7  407.32    4885  402.64    4915  400.14
  4928.4   402.1  4955.1  401.24  4985.2  396.87  4990.6  394.47  4991.1  393.97
  4999.8  394.47  5008.6  395.34  5012.3   399.5  5019.2  397.11  5026.5   400.5
  5033.3  398.34  5054.8   404.1  5061.6  403.01    5069  404.52  5083.1  404.86
  5182.3  405.44  5564.2  403.44  5776.3  406.97    5865  407.03  6101.8  409.27
#Mann= 7 ,-1 , 0
  3373.2     .12       0  3593.9     .07       0  3783.3     .05       0
  4212.6     .07       0  4990.6     .05       0  4999.8     .07       0
    5865     .12       0
Bank Sta=4990.6,4999.8
XS Rating Curve= 0 ,0
Exp/Cntr=0.3,0.1

Type RM Length L Ch R = 1 ,309     ,0,0,0
BEGIN DESCRIPTION:
Stream0548 1.0
END DESCRIPTION:
XS GIS Cut Line= 3
      2347789.17     13698062.86      2349868.26     13698071.83
      2351374.96     13696725.03
#Sta/Elev= 30
  2920.9  426.11  3351.2     420  3360.2  420.24    3364  420.15  3446.7  417.99
  3566.7  417.59  3846.7  411.27  4049.9  409.52  4148.3  408.16  4496.7  405.08
  4766.7  405.72  4916.7  401.54  4966.7  398.39  4976.7  396.89  4982.1  392.96
  4982.6  392.46  4991.4  392.96    5000  393.23  5002.5  396.28  5009.2  396.95
  5016.8  400.62  5059.4  403.48  5703.9  401.38  5866.9  401.86  5894.5  403.99
    6228  402.52  6301.3  404.82  6512.8  405.45  6829.9  406.26  7020.9   409.1
#Mann= 10 ,-1 , 0
  2920.9     .12       0  3351.2     .07       0  3360.2     .12       0
    3364     .07       0  4049.9     .05       0  4148.3     .07       0
  4982.1     .05       0  4991.4     .07       0  6301.3    .035       0
  6512.8     .07       0
Bank Sta=4982.1,4991.4
XS Rating Curve= 0 ,0
Exp/Cntr=0.3,0.1

Chan Stop Cuts=-1
Use User Specified Reach Order=0
Composite Channel Slope=5