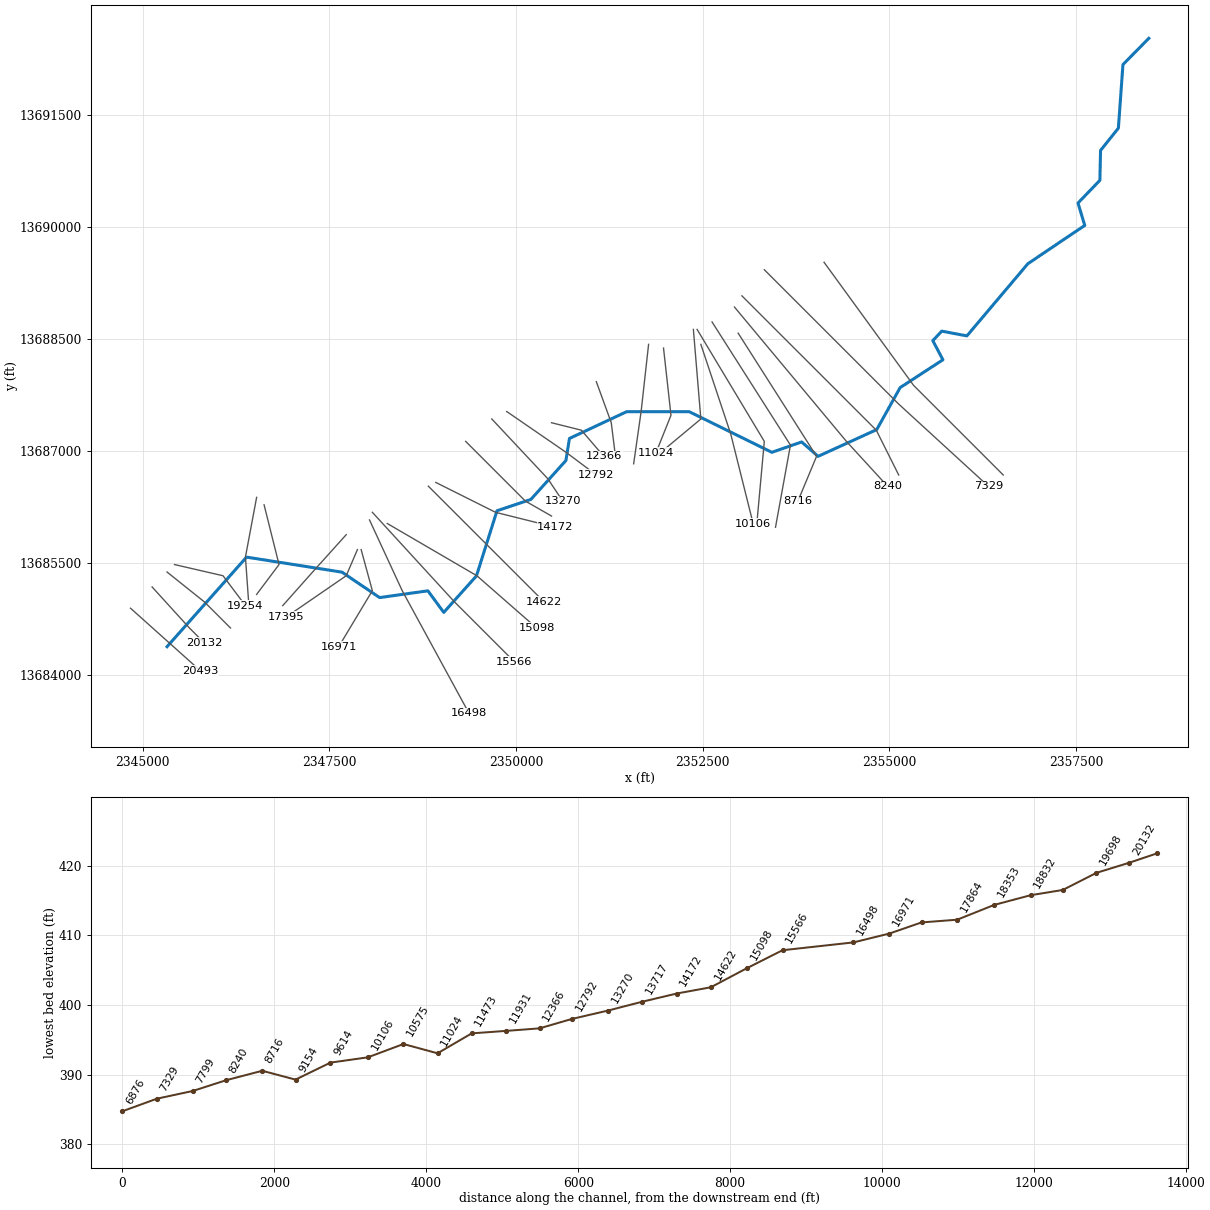
--- Stream0550.prj (project) ---

Proj Title=Stream0550 Base Level Engineering
Current Plan=p01
Default Exp/Contr=0.3,0.1
English Units
Geom File=g01
Flow File=f01
Plan File=p01
Y Axis Title=Elevation
X Axis Title(PF)=Main Channel Distance
X Axis Title(XS)=Station
BEGIN DESCRIPTION:
Stream0550
END DESCRIPTION:
DSS Export Rating Curves= 0
DSS Export Rating Curve Sorted= 0
DSS Export Volume Flow Curves= 0
DXF OffsetX= 0
DXF OffsetY= 0
DXF ScaleX= 1
DXF ScaleY= 10

--- Stream0550.p01 (plan) ---

Plan Title=Multiple Run
Short Identifier=Multiple
Geom File=g01
Flow File=f01
Subcritical Flow
K Sum by GR= 0
Std Step Tol= 0.01
Critical Tol= 0.01
Num of Std Step Trials= 20
Max Error Tol= 0.3
Flow Tol Ratio= 0.001
Split Flow NTrial= 30
Split Flow Tol= 0.02
Split Flow Ratio= 0.02
Log Output Level= 0
Friction Slope Method= 1
Unsteady Friction Slope Method= 2
Unsteady Bridges Friction Slope Method= 1
Parabolic Critical Depth
Global Vel Dist=  1 , 1 , 1
Global Log Level= 0
CheckData=True
Encroach Param= -1, 0, 0, 0
BEGIN DESCRIPTION:
Multiple Run
END DESCRIPTION:

--- Stream0550.f01 (steady flow) ---

Flow Title=Multiple
Number of Profiles=7
Profile Names=10-year,25-year,50-year,1pct_min,100-year,1pct_plu,500-year
River Rch & RM= Stream0550,Reach-1,20493
     936    1557    2134    1415    2823    5633    4901
River Rch & RM= Stream0550,Reach-1,20132
     989    1649    2265    1505    3003    5991    5232
River Rch & RM= Stream0550,Reach-1,18353
    1331    2255    3128    2096    4182    8345    7422
River Rch & RM= Stream0550,Reach-1,17864
    1393    2357    3267    2187    4363    8705    7721
River Rch & RM= Stream0550,Reach-1,15566
    1628    2768    3849    2583    5154   10284    9172
River Rch & RM= Stream0550,Reach-1,13717
    1815    3093    4307    2892    5771   11515   10285
River Rch & RM= Stream0550,Reach-1,10575
    1890    3209    4455    2982    5950   11872   10534
River Rch & RM= Stream0550,Reach-1,6447
    1987    3368    4672    3123    6230   12431   10998
River Rch & RM= Stream0550,Reach-1,1447
    2055    3488    4841    3237    6459   12887   11413
Boundary for River Rch & Prof#=Stream0550,Reach-1,1
Up Type=0
Dn Type=3
Dn Slope=0.005
Boundary for River Rch & Prof#=Stream0550,Reach-1,2
Up Type=0
Dn Type=3
Dn Slope=0.005
Boundary for River Rch & Prof#=Stream0550,Reach-1,3
Up Type=0
Dn Type=3
Dn Slope=0.005
Boundary for River Rch & Prof#=Stream0550,Reach-1,4
Up Type=0
Dn Type=3
Dn Slope=0.005
Boundary for River Rch & Prof#=Stream0550,Reach-1,5
Up Type=0
Dn Type=3
Dn Slope=0.005
Boundary for River Rch & Prof#=Stream0550,Reach-1,6
Up Type=0
Dn Type=3
Dn Slope=0.005
Boundary for River Rch & Prof#=Stream0550,Reach-1,7
Up Type=0
Dn Type=3
Dn Slope=0.005

--- Stream0550.g01 (geometry) ---

Geom Title=Existing Conditions
Program Version=4.10

River Reach=Stream0550      ,Reach-1
Reach XY= 30
        2345325.       13684375.      2346390.15     13685574.62
      2347669.15     13685372.94      2348171.67     13685032.61
      2348819.16     13685122.95      2349031.66     13684833.95
      2349469.17      13685322.7      2349744.58     13686195.58
       2350198.9     13686347.71      2350667.36     13686868.55
        2350715.     13687164.35      2351480.85     13687522.94
      2352319.11     13687523.03      2353426.46     13686978.52
       2353825.1     13687117.69      2354045.06     13686924.78
      2354831.06     13687283.14      2355144.22     13687845.58
      2355717.31     13688218.53      2355581.98     13688474.79
      2355701.47     13688602.16      2356038.38     13688538.53
      2356854.91     13689505.21      2357617.19     13690018.81
      2357526.76     13690318.88      2357819.55     13690622.53
      2357828.75     13691023.45       2358067.4     13691321.66
      2358128.62      13692173.5        2358475.       13692525.

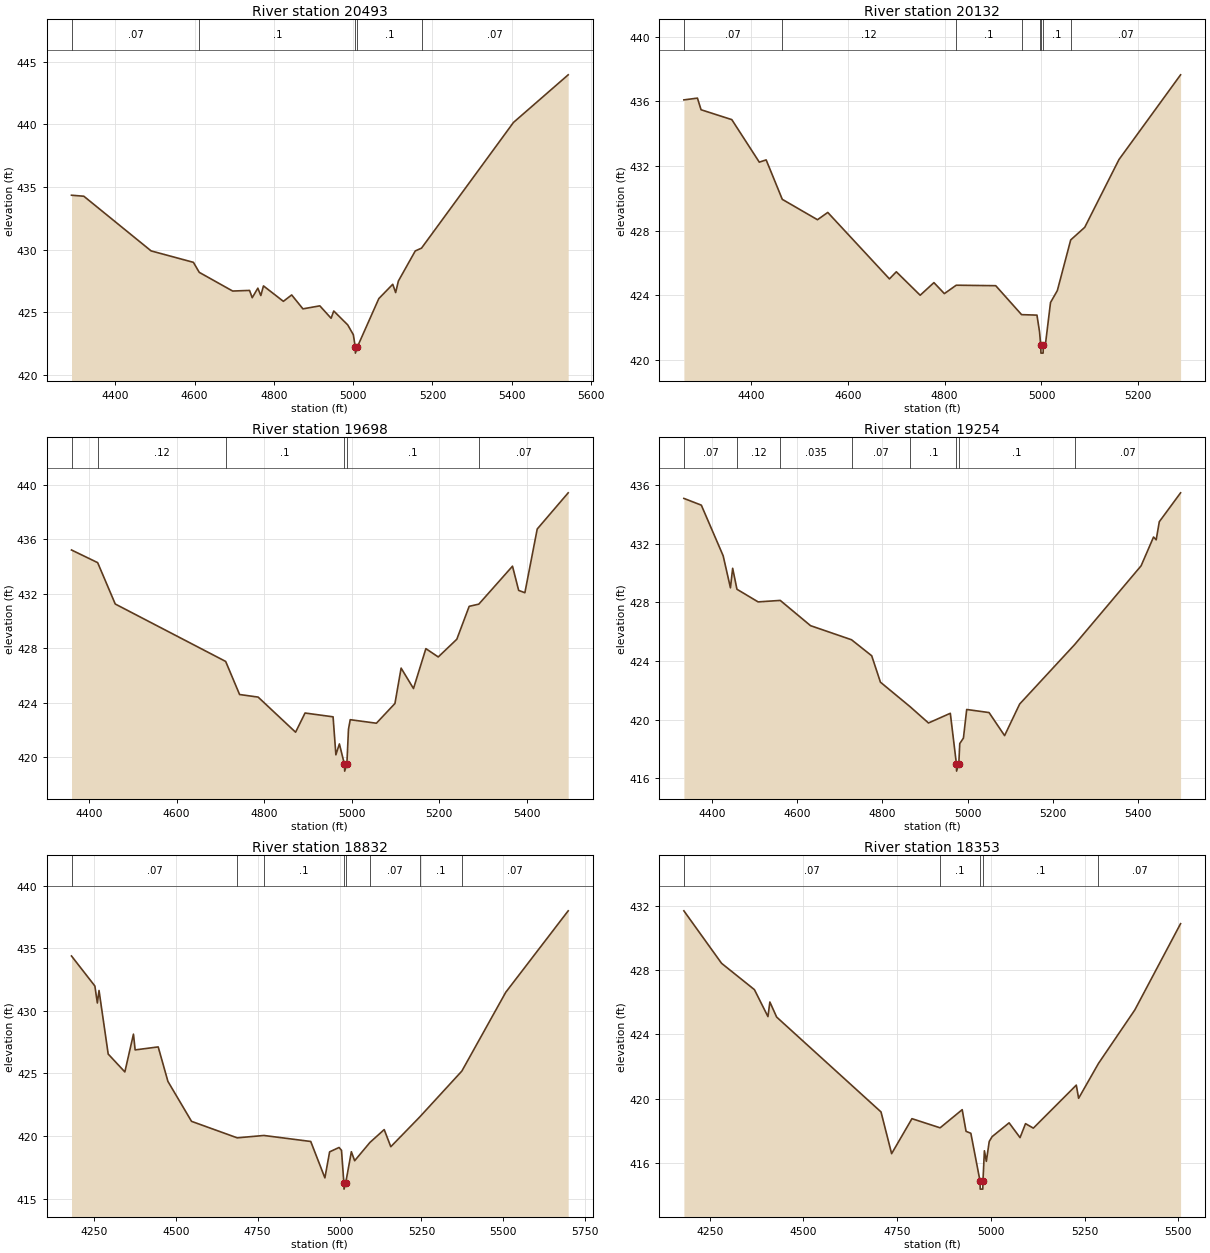
Type RM Length L Ch R = 1 ,20493   ,361,361,361
BEGIN DESCRIPTION:
XS7055
END DESCRIPTION:
XS GIS Cut Line= 2
      2344835.99     13684889.98      2345769.12      13684054.5
#Sta/Elev= 30
  4289.7  434.34  4320.8  434.26  4490.5   429.9  4597.1  428.99  4611.9  428.19
  4696.1   426.7  4738.7  426.75  4745.4  426.17  4759.6  426.93  4767.1  426.34
  4773.8  427.11    4824  425.88  4844.9  426.39  4873.3  425.28  4915.9  425.52
  4944.3  424.53    4951  425.11  4986.3     424  5000.4  423.22  5005.2  422.25
  5005.6  421.75  5010.6  422.25  5064.7   426.1  5099.8  427.24  5107.1  426.58
    5114   427.5  5156.6   429.9  5172.3  430.12  5404.1  440.14  5542.2  443.94
#Mann= 5 ,-1 , 0
  4289.7     .07       0  4611.9      .1       0  5005.2     .05       0
  5010.6      .1       0  5172.3     .07       0
Bank Sta=5005.2,5010.6
XS Rating Curve= 0 ,0
Exp/Cntr=0.3,0.1

Type RM Length L Ch R = 1 ,20132   ,434,434,434
BEGIN DESCRIPTION:
Stream0550 40.0
END DESCRIPTION:
XS GIS Cut Line= 3
        2345125.       13685175.        2345625.       13684625.
      2345825.03     13684424.97
#Sta/Elev= 30
  4261.2  436.08  4289.2  436.19  4296.7  435.47  4360.2  434.86    4417  432.23
  4431.2  432.37  4464.5  429.93  4537.2  428.67  4558.5  429.12  4685.9  425.01
  4700.1  425.45  4749.4     424  4777.8  424.78  4799.4   424.1  4823.9  424.62
  4905.5  424.59  4958.9   422.8  4990.7  422.77    4996  421.74  4998.4  420.92
  4998.9  420.42  5003.4  420.42  5003.8  420.92    5008  420.92  5018.7  423.55
  5032.8  424.29  5060.4  427.42  5089.4   428.2  5160.1  432.39  5287.4  437.63
#Mann= 8 ,-1 , 0
  4261.2     .07       0  4464.5     .12       0  4823.9      .1       0
  4958.9     .12       0    4996      .1       0  4998.4     .05       0
  5003.8      .1       0  5060.4     .07       0
Bank Sta=4998.4,5003.8
XS Rating Curve= 0 ,0
Exp/Cntr=0.3,0.1

Type RM Length L Ch R = 1 ,19698   ,444,444,444
BEGIN DESCRIPTION:
Stream0550 39.0
END DESCRIPTION:
XS GIS Cut Line= 3
      2345325.02     13685374.98        2345825.       13684975.
      2346175.03     13684624.97
#Sta/Elev= 30
  4359.7  435.21  4419.5  434.28  4459.7  431.24  4712.1  427.02  4743.9  424.59
  4786.3   424.4  4871.9  421.82  4893.5  423.23  4957.6  422.95    4964  420.16
    4972  420.96  4983.6  419.46  4984.1  418.96  4989.1  419.46  4992.8  422.04
  4996.8  422.74  5056.6  422.48    5099  423.93  5113.1  426.53  5141.4  425.03
  5169.7  427.96    5198  427.35  5240.4  428.65  5268.7  431.07  5290.7  431.23
  5367.7  434.02  5381.8  432.24    5396  432.07  5424.2  436.75    5495  439.41
#Mann= 6 ,-1 , 0
  4359.7     .07       0  4419.5     .12       0  4712.1      .1       0
  4983.6     .05       0  4989.1      .1       0  5290.7     .07       0
Bank Sta=4983.6,4989.1
XS Rating Curve= 0 ,0
Exp/Cntr=0.3,0.1

Type RM Length L Ch R = 1 ,19254   ,422,422,422
BEGIN DESCRIPTION:
Stream0550 38.0
END DESCRIPTION:
XS GIS Cut Line= 3
      2345425.04     13685474.99        2346075.       13685325.
      2346374.98     13684925.03
#Sta/Elev= 30
  4333.5  435.08  4374.5  434.62  4425.8  431.17  4442.9  428.99  4448.1  430.32
  4458.2  428.89  4507.9  428.03  4559.9  428.13  4631.1  426.41  4727.4  425.45
  4774.8  424.36  4795.3  422.56    4865  420.89  4908.2  419.78  4959.5  420.44
  4973.8     417  4974.2   416.5  4979.4     417  4981.7  418.38  4990.3  418.75
    4998   420.7  5050.5  420.49    5087  418.92  5122.4  421.07  5251.6  425.12
  5407.8  430.49    5437  432.45  5443.2  432.26  5450.5  433.49  5500.5  435.46
#Mann= 8 ,-1 , 0
  4333.5     .07       0  4458.2     .12       0  4559.9    .035       0
  4727.4     .07       0    4865      .1       0  4973.8     .05       0
  4979.4      .1       0  5251.6     .07       0
Bank Sta=4973.8,4979.4
XS Rating Curve= 0 ,0
Exp/Cntr=0.3,0.1

Type RM Length L Ch R = 1 ,18832   ,479,479,479
BEGIN DESCRIPTION:
Stream0550 37.0
END DESCRIPTION:
XS GIS Cut Line= 3
      2346525.01     13686375.05        2346375.       13685575.
        2346425.     13684874.97
#Sta/Elev= 30
  4181.9  434.39  4253.2  431.99  4260.8  430.63  4265.9  431.63  4293.9  426.55
  4344.7  425.12    4371  428.14  4376.1  426.88  4446.5  427.12  4476.2  424.36
  4548.2  421.17  4687.7  419.85  4768.9  420.04    4912  419.56  4955.2  416.65
  4969.6  418.73  4998.4  419.08  5005.9  418.85  5013.1  416.25  5013.6  415.75
  5018.7  416.25    5036  418.74    5046  418.02  5092.6  419.48  5136.2  420.51
  5156.3  419.14  5244.3  421.51  5373.2  425.19  5507.2  431.49  5697.7     438
#Mann= 8 ,-1 , 0
  4181.9     .07       0  4687.7     .12       0  4768.9      .1       0
  5013.1     .05       0  5018.7      .1       0  5092.6     .07       0
  5244.3      .1       0  5373.2     .07       0
Bank Sta=5013.1,5018.7
XS Rating Curve= 0 ,0
Exp/Cntr=0.3,0.1

Type RM Length L Ch R = 1 ,18353   ,489,489,489
BEGIN DESCRIPTION:
Stream0550 36.0
END DESCRIPTION:
XS GIS Cut Line= 3
        2346625.     13686274.99        2346825.       13685475.
      2346525.01     13685075.01
#Sta/Elev= 30
  4181.3   431.7  4281.8  428.43  4369.4  426.79  4405.5  425.11  4410.6  426.02
  4428.7  425.08    4707  419.17  4735.3  416.57  4789.5  418.75  4864.6  418.18
  4923.5  419.31  4933.8  417.96  4946.6  417.84  4971.1  414.86  4971.6  414.36
  4978.4  414.36  4978.9  414.86  4982.7  416.75  4987.9  416.09  4995.6  417.33
  5003.3  417.63  5048.6  418.49  5077.8  417.57  5092.4  418.44  5113.2  418.16
  5227.8  420.84    5234  420.02  5286.9  422.19    5384  425.53  5505.9   430.9
#Mann= 5 ,-1 , 0
  4181.3     .07       0  4864.6      .1       0  4971.1     .05       0
  4978.9      .1       0  5286.9     .07       0
Bank Sta=4971.1,4978.9
XS Rating Curve= 0 ,0
Exp/Cntr=0.3,0.1

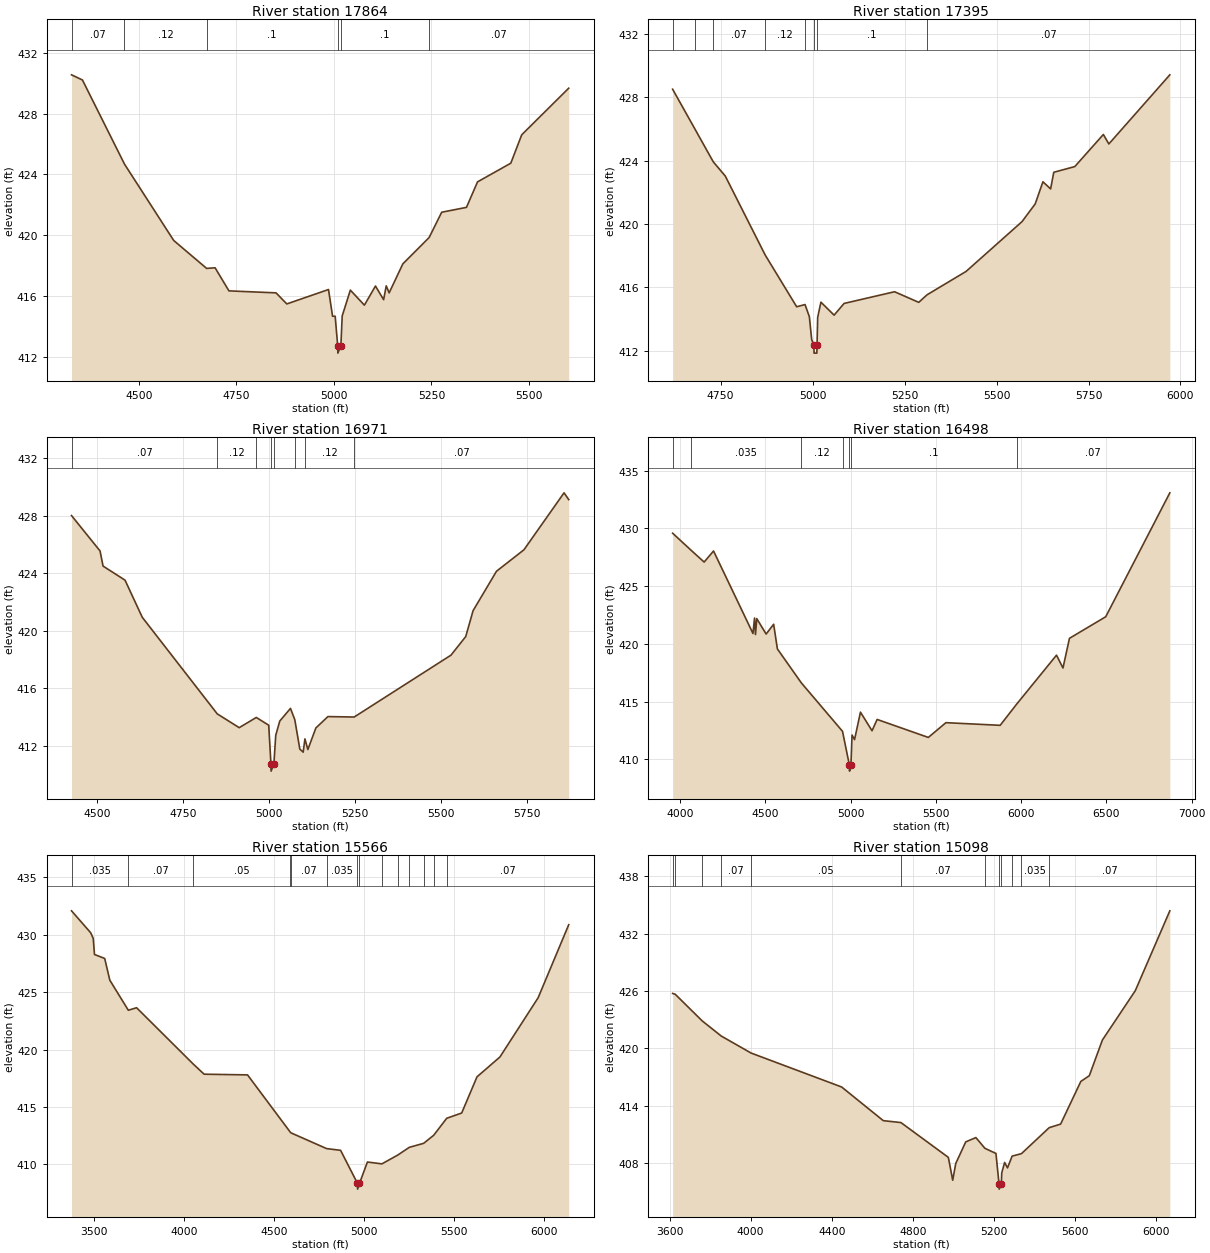
Type RM Length L Ch R = 1 ,17864   ,469,469,469
BEGIN DESCRIPTION:
Stream0550 35.0
END DESCRIPTION:
XS GIS Cut Line= 3
        2347725.       13685875.        2347275.       13685375.
      2346874.98     13684924.97
#Sta/Elev= 30
  4327.3  430.56  4355.3  430.22  4463.1  424.68  4589.3  419.65  4673.7  417.81
  4695.4  417.85  4730.9  416.33  4851.6   416.2  4879.3  415.47  4986.2  416.42
  4996.6  414.66  5003.3  414.66  5009.7  412.73  5010.2  412.23  5017.9  412.73
  5021.3  414.68  5042.2  416.38  5078.2  415.39  5106.6  416.65  5127.5  415.75
  5134.2  416.66  5141.7   416.2  5176.8  418.11  5244.1  419.84  5276.4  421.51
  5339.9  421.83  5368.3  423.51  5453.6  424.74  5481.6  426.61  5602.1  429.68
#Mann= 6 ,-1 , 0
  4327.3     .07       0  4463.1     .12       0  4673.7      .1       0
  5009.7     .05       0  5017.9      .1       0  5244.1     .07       0
Bank Sta=5009.7,5017.9
XS Rating Curve= 0 ,0
Exp/Cntr=0.3,0.1

Type RM Length L Ch R = 1 ,17395   ,424,424,424
BEGIN DESCRIPTION:
Stream0550 34.0
END DESCRIPTION:
XS GIS Cut Line= 3
      2347874.99     13685674.98        2347725.       13685325.
      2346924.99     13684774.99
#Sta/Elev= 30
  4619.5  428.52  4679.5  426.03    4730  423.93  4762.7  423.03  4870.9  418.05
  4956.7  414.77  4979.4  414.91  4991.2  414.14  4997.5   412.7  5003.4  412.34
  5003.9  411.84  5011.5  411.84    5012  412.34  5013.8   414.1  5022.6  415.06
  5058.5  414.24  5085.5  414.98  5222.8  415.72  5288.5  415.05  5311.3  415.53
    5417     417  5569.2  420.15  5605.1  421.27  5626.1  422.67    5647  422.22
  5655.6  423.27  5712.7  423.63  5790.4  425.66  5805.3  425.06  5971.1  429.43
#Mann= 8 ,-1 , 0
  4619.5     .07       0  4679.5     .12       0    4730     .07       0
  4870.9     .12       0  4979.4      .1       0  5003.4     .05       0
    5012      .1       0  5311.3     .07       0
Bank Sta=5003.4,5012
XS Rating Curve= 0 ,0
Exp/Cntr=0.3,0.1

Type RM Length L Ch R = 1 ,16971   ,473,473,473
BEGIN DESCRIPTION:
Stream0550 33.0
END DESCRIPTION:
XS GIS Cut Line= 3
        2347925.     13685674.99        2348075.       13685125.
      2347625.01     13684375.02
#Sta/Elev= 30
  4425.9     428  4508.8  425.54  4517.5  424.49  4581.4  423.51  4631.5  420.93
  4849.3  414.22  4913.1  413.26  4962.8  413.97  4998.9  413.43  5005.3  410.74
  5005.8  410.24  5013.9  410.74  5019.3  412.73    5031  413.72  5062.1   414.6
  5074.6  413.82  5089.3  411.77    5099  411.56  5104.1  412.48  5112.6  411.74
  5135.9  413.24  5170.9  414.03  5247.3     414  5528.5   418.3  5571.3  419.59
  5592.7  421.39  5660.7  424.13  5740.4  425.62    5857  429.58  5870.6  429.11
#Mann= 8 ,-1 , 0
  4425.9     .07       0  4849.3     .12       0  4962.8      .1       0
  5005.3     .05       0  5013.9      .1       0  5074.6     .07       0
  5104.1     .12       0  5247.3     .07       0
Bank Sta=5005.3,5013.9
XS Rating Curve= 0 ,0
Exp/Cntr=0.3,0.1

Type RM Length L Ch R = 1 ,16498   ,932,932,932
BEGIN DESCRIPTION:
Stream0550 32.0
END DESCRIPTION:
XS GIS Cut Line= 3
      2348036.91     13686072.76        2348475.       13685125.
      2349370.61     13683481.16
#Sta/Elev= 30
  3955.9  429.59  4065.8  428.09  4140.7  427.09  4195.8  428.05  4427.1   420.9
  4436.3  422.24  4441.8  420.81  4449.2  422.19  4504.3  420.85  4548.3   421.7
  4570.4  419.56  4710.7  416.62  4952.3  412.42  4992.9  409.47  4993.4  408.97
  5001.6  409.47  5008.1   412.1  5022.8   411.7  5057.5  414.08  5125.3  412.47
  5155.3  413.45  5455.5  411.89  5558.8  413.17  5876.9  412.94  5972.7  414.76
  6207.3  419.02  6245.3  417.91  6283.3  420.48    6496  422.35    6872  433.09
#Mann= 7 ,-1 , 0
  3955.9     .07       0  4065.8    .035       0  4710.7     .12       0
  4952.3      .1       0  4992.9     .05       0  5001.6      .1       0
  5972.7     .07       0
Bank Sta=4992.9,5001.6
XS Rating Curve= 0 ,0
Exp/Cntr=0.3,0.1

Type RM Length L Ch R = 1 ,15566   ,468,468,468
BEGIN DESCRIPTION:
Stream0550 31.0
END DESCRIPTION:
XS GIS Cut Line= 3
      2348074.97     13686175.03        2349175.       13684975.
        2349975.       13684175.
#Sta/Elev= 30
    3377  432.09  3483.4  430.18  3497.6  429.68  3504.4  428.29  3561.1  427.94
  3589.5  426.05  3692.3  423.43  3738.1  423.65  4053.4  418.73    4113  417.86
  4353.8   417.8  4591.6   412.8    4595  412.75  4792.7  411.38  4870.2  411.23
    4964  408.35  4964.5  407.85    4975  408.35  5019.1  410.21  5099.5  410.05
  5187.8  410.82  5251.6  411.49  5331.2  411.84  5386.9  412.54  5459.1  414.02
  5542.3  414.48  5627.2  417.63  5754.5  419.36  5966.6  424.52  6136.3  430.88
#Mann= 14 ,-1 , 0
    3377    .035       0  3692.3     .07       0  4053.4     .05       0
  4591.6    .035       0    4595     .07       0  4792.7    .035       0
    4964    .035       0    4975    .035       0  5099.5      .1       0
  5187.8    .035       0  5251.6      .1       0  5331.2    .035       0
  5386.9      .1       0  5459.1     .07       0
Bank Sta=4964,4975
XS Rating Curve= 0 ,0
Exp/Cntr=0.3,0.1

Type RM Length L Ch R = 1 ,15098   ,476,476,476
BEGIN DESCRIPTION:
Stream0550 30.0
END DESCRIPTION:
XS GIS Cut Line= 3
      2348274.99       13686025.        2349475.       13685325.
      2350275.02     13684624.98
#Sta/Elev= 30
  3615.1  425.74  3627.6  425.66    3761  422.87  3854.7  421.29    4002  419.51
  4448.7  415.96  4654.1  412.44    4741  412.24    4975   408.6  4996.5  406.21
  5011.5  407.96  5060.8  410.22  5110.7  410.67  5155.2  409.55  5209.8  409.01
  5225.2  405.78  5225.7  405.28  5236.2  405.78  5238.3  406.98  5252.5  408.07
  5266.8   407.5  5289.4  408.73  5335.5  408.99  5472.6  411.71  5528.7  412.08
  5628.4  416.54  5670.2  417.14  5734.7  420.87    5897  426.03  6067.4  434.38
#Mann= 12 ,-1 , 0
  3615.1    .035       0  3627.6     .07       0    3761     .05       0
  3854.7     .07       0    4002     .05       0    4741     .07       0
  5155.2    .035       0  5225.2     .05       0  5236.2    .035       0
  5289.4     .07       0  5335.5    .035       0  5472.6     .07       0
Bank Sta=5225.2,5236.2
XS Rating Curve= 0 ,0
Exp/Cntr=0.3,0.1

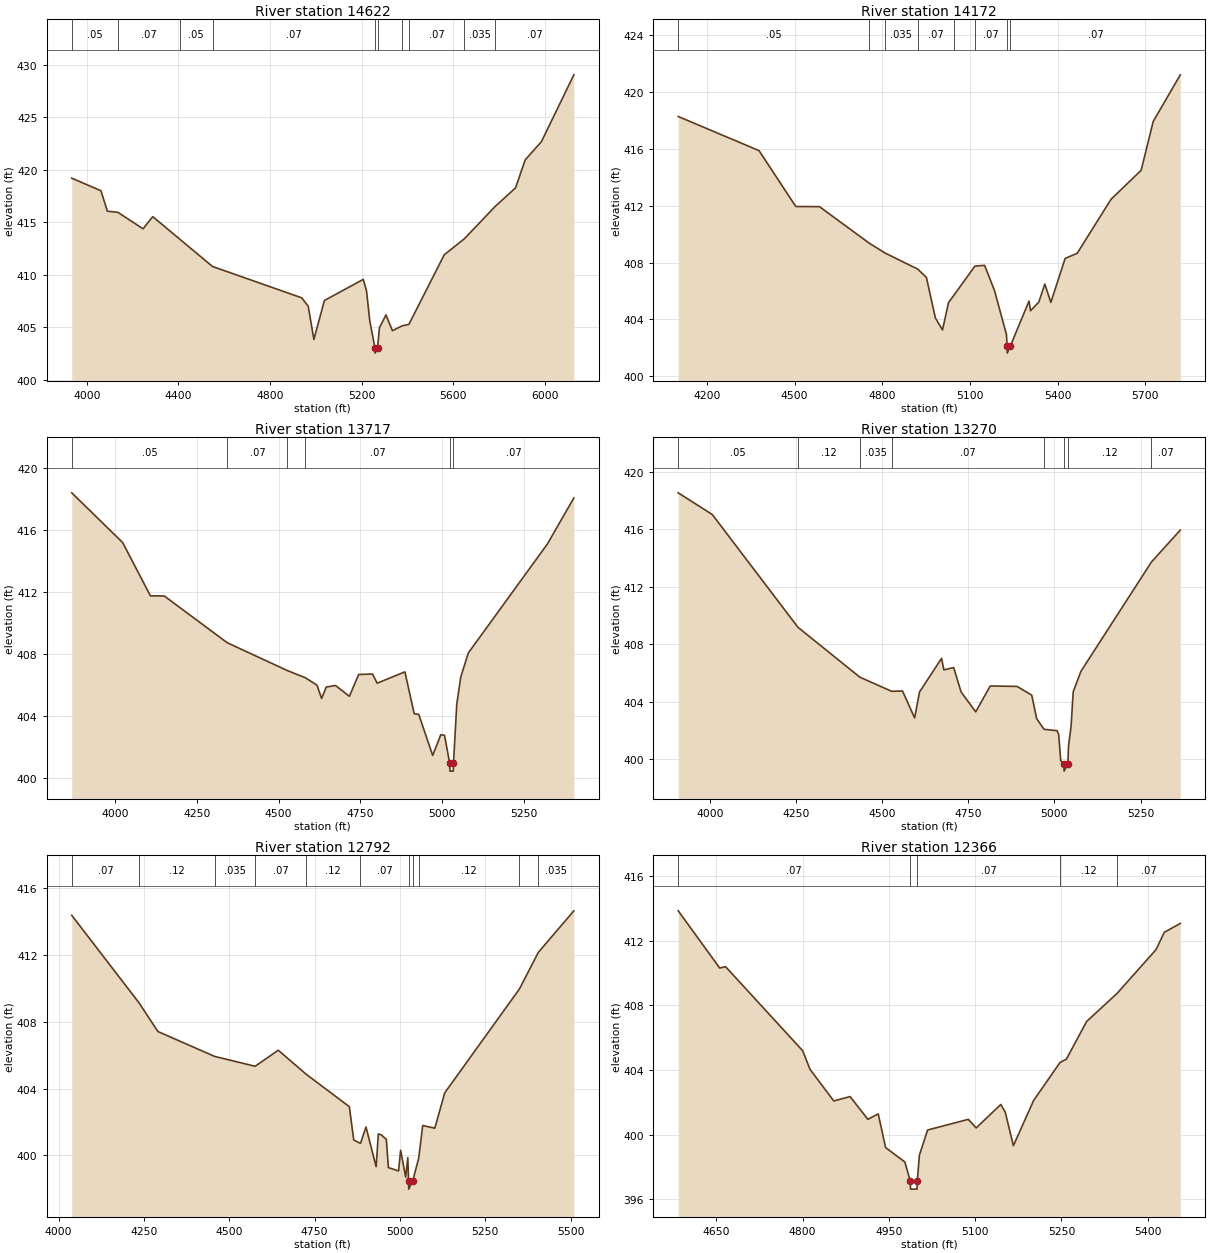
Type RM Length L Ch R = 1 ,14622   ,450,450,450
BEGIN DESCRIPTION:
Stream0550 29.0
END DESCRIPTION:
XS GIS Cut Line= 3
      2348824.98     13686525.02        2349575.       13685775.
      2350375.03     13684974.97
#Sta/Elev= 30
  3934.3  419.21  4061.6  418.01  4089.9  416.06  4135.9  415.95  4245.5  414.38
  4287.9  415.54  4405.4   413.4  4548.8  410.79  4938.4   407.8  4966.7     407
  4991.5  403.83  5037.4  407.55  5207.1  409.56  5221.3  408.46  5235.4   405.6
  5258.1  403.03  5258.6  402.53  5269.2  403.03  5277.8  404.96  5306.1  406.17
  5334.4  404.67  5377.6  405.14  5406.2  405.27  5560.7  411.91  5648.3  413.43
  5783.6  416.53  5871.8  418.28  5914.2  420.96  5984.9  422.69  6126.4  429.06
#Mann= 10 ,-1 , 0
  3934.3     .05       0  4135.9     .07       0  4405.4     .05       0
  4548.8     .07       0  5258.1     .05       0  5269.2     .07       0
  5377.6     .12       0  5406.2     .07       0  5648.3    .035       0
  5783.6     .07       0
Bank Sta=5258.1,5269.2
XS Rating Curve= 0 ,0
Exp/Cntr=0.3,0.1

Type RM Length L Ch R = 1 ,14172   ,455,455,455
BEGIN DESCRIPTION:
Stream0550 28.0
END DESCRIPTION:
XS GIS Cut Line= 3
      2348924.98     13686575.01        2349725.       13686175.
      2350525.02     13685974.99
#Sta/Elev= 30
  4101.4  418.27  4378.1  415.87  4503.9  411.94    4585  411.93  4755.5  409.36
  4809.5  408.67  4921.2  407.54  4951.1  406.96  4981.9   404.1  5006.2  403.26
  5026.8  405.18  5044.9  405.69  5117.3  407.75  5150.5   407.8    5184  406.05
  5225.2  402.94  5227.4  402.13  5227.9  401.63  5238.5  402.13  5302.5  405.29
  5307.7  404.61    5336  405.22  5356.6  406.49  5377.2   405.2  5426.2  408.29
  5467.4  408.65  5583.4  412.45  5686.5  414.49  5727.7  417.92  5820.5   421.2
#Mann= 8 ,-1 , 0
  4101.4     .05       0  4755.5     .07       0  4809.5    .035       0
  4921.2     .07       0  5044.9    .035       0  5117.3     .07       0
  5227.4     .05       0  5238.5     .07       0
Bank Sta=5227.4,5238.5
XS Rating Curve= 0 ,0
Exp/Cntr=0.3,0.1

Type RM Length L Ch R = 1 ,13717   ,447,447,447
BEGIN DESCRIPTION:
Stream0550 27.0
END DESCRIPTION:
XS GIS Cut Line= 3
      2349325.02     13687124.98        2350125.       13686325.
      2350475.04     13686124.98
#Sta/Elev= 30
  3867.9  418.42  4023.4  415.21  4108.3  411.77  4150.7  411.76  4343.1  408.74
  4527.1  406.94  4581.8  406.48  4617.4     406  4631.5  405.14  4645.7  405.88
    4674  405.98  4716.4  405.28  4744.7  406.69  4787.1  406.72  4801.3  406.13
  4886.1  406.86  4914.4  404.16  4928.5  404.11    4971  401.46  4995.7   402.8
  5007.2  402.76  5023.1  400.95  5023.6  400.45    5034  400.45  5034.5  400.95
  5044.6  404.77  5056.8  406.53  5079.9  408.08  5321.7  415.12  5402.4  418.09
#Mann= 6 ,-1 , 0
  3867.9     .05       0  4343.1     .07       0  4527.1    .035       0
  4581.8     .07       0  5023.1     .05       0  5034.5     .07       0
Bank Sta=5023.1,5034.5
XS Rating Curve= 0 ,0
Exp/Cntr=0.3,0.1

Type RM Length L Ch R = 1 ,13270   ,478,478,478
BEGIN DESCRIPTION:
Stream0550 26.0
END DESCRIPTION:
XS GIS Cut Line= 3
        2349675.     13687425.01        2350425.       13686625.
      2350624.97     13686325.04
#Sta/Elev= 30
  3908.3  418.54  4007.2  417.03  4255.8  409.19  4435.5  405.72  4527.8  404.74
  4559.2  404.76  4594.4  402.89  4608.5  404.69  4672.5  407.03  4679.3  406.23
  4707.7  406.39  4729.1   404.7  4771.6  403.31  4813.7  405.11  4891.8  405.08
  4934.3  404.47  4948.5  402.84  4969.8   402.1  5007.9     402  5012.4  401.74
  5018.4  399.92  5027.7  399.69  5028.2  399.19  5039.1  399.69  5040.9  400.92
  5048.5  402.33  5054.5   404.7    5077  406.13  5281.6  413.73  5365.4  415.95
#Mann= 8 ,-1 , 0
  3908.3     .05       0  4255.8     .12       0  4435.5    .035       0
  4527.8     .07       0  4969.8     .12       0  5027.7     .05       0
  5039.1     .12       0  5281.6     .07       0
Bank Sta=5027.7,5039.1
XS Rating Curve= 0 ,0
Exp/Cntr=0.3,0.1

Type RM Length L Ch R = 1 ,12792   ,426,426,426
BEGIN DESCRIPTION:
Stream0550 25.0
END DESCRIPTION:
XS GIS Cut Line= 3
      2349874.99     13687525.01        2350675.       13686975.
      2351074.97     13686675.02
#Sta/Elev= 30
  4038.8  414.38  4235.8  409.14  4291.2  407.42  4457.1  405.93    4576  405.34
  4643.7   406.3  4725.6  404.86  4851.9  402.92  4864.8  400.92  4884.6  400.72
  4900.7   401.7  4930.5  399.32  4936.8  401.29  4945.4  401.23  4960.3  400.96
  4966.3  399.27  4996.1  399.07  5002.2  400.31  5016.9   398.7  5023.2  399.87
  5025.4  398.48  5025.9  397.98  5037.7  398.48  5055.1  399.83  5066.9  401.79
  5102.3  401.63  5131.5  403.75  5350.2  409.97  5405.5  412.16  5509.6  414.65
#Mann= 11 ,-1 , 0
  4038.8     .07       0  4235.8     .12       0  4457.1    .035       0
    4576     .07       0  4725.6     .12       0  4884.6     .07       0
  5025.4     .05       0  5037.7     .07       0  5055.1     .12       0
  5350.2     .07       0  5405.5    .035       0
Bank Sta=5025.4,5037.7
XS Rating Curve= 0 ,0
Exp/Cntr=0.3,0.1

Type RM Length L Ch R = 1 ,12366   ,435,435,435
BEGIN DESCRIPTION:
Stream0550 24.0
END DESCRIPTION:
XS GIS Cut Line= 3
      2350475.04     13687374.99        2350875.       13687275.
      2351174.97     13686925.04
#Sta/Elev= 30
  4583.6  413.86  4655.7  410.32    4666   410.4    4800   405.2  4812.9  404.04
  4854.1  402.09  4882.5  402.36  4913.4  400.95  4931.4  401.29  4944.3   399.2
  4977.8  398.31  4987.1  397.13  4987.6  396.63  4998.9  396.63  4999.4  397.13
    5003  398.73  5017.3  400.29  5088.1  400.95  5101.8  400.42  5144.6  401.87
  5152.3   401.4  5166.5  399.32  5201.7  402.12  5247.6  404.47  5258.7  404.68
  5293.9  407.01  5346.9  408.75  5414.6  411.46  5428.9  412.53  5456.8  413.08
#Mann= 5 ,-1 , 0
  4583.6     .07       0  4987.1     .05       0  4999.4     .07       0
  5247.6     .12       0  5346.9     .07       0
Bank Sta=4987.1,4999.4
XS Rating Curve= 0 ,0
Exp/Cntr=0.3,0.1

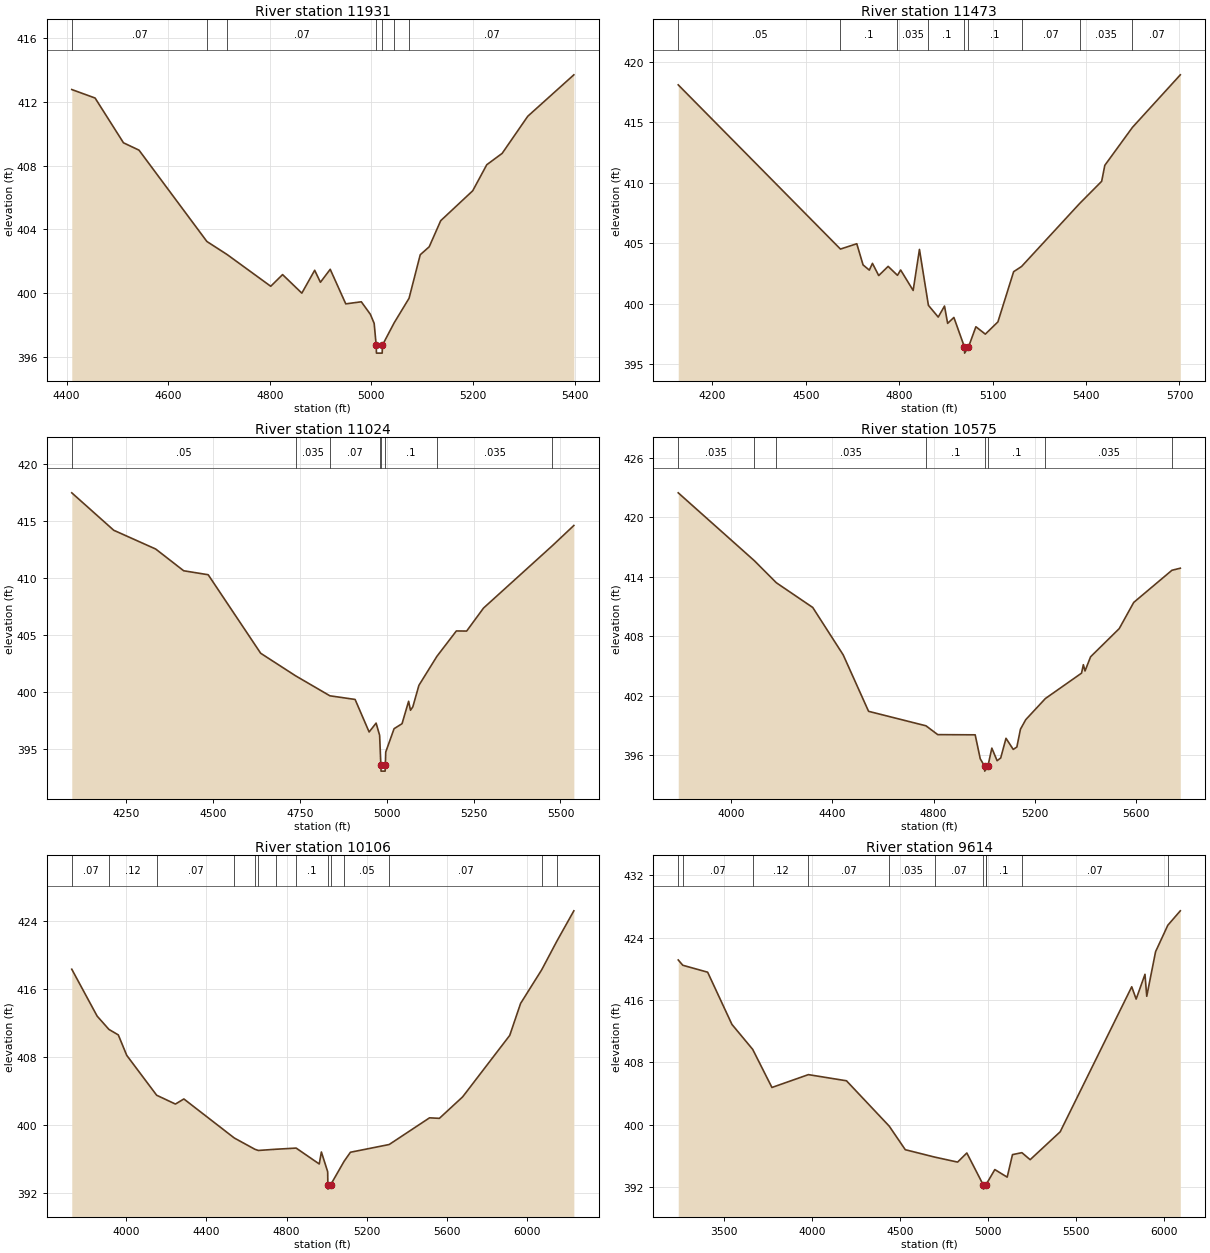
Type RM Length L Ch R = 1 ,11931   ,458,458,458
BEGIN DESCRIPTION:
Stream0550 23.0
END DESCRIPTION:
XS GIS Cut Line= 3
      2351074.99     13687925.02        2351275.       13687375.
        2351325.     13686974.97
#Sta/Elev= 30
  4410.2  412.75  4456.1  412.22    4512  409.42  4542.6  408.96  4676.2  403.25
  4716.2  402.43  4801.9  400.45  4825.2  401.18  4863.1  400.02  4888.4  401.45
  4899.7   400.7    4919  401.51  4949.6  399.35  4980.2  399.48    4998   398.7
  5005.5  398.13  5009.5  396.77    5010  396.27  5021.3  396.27  5021.8  396.77
  5044.8  398.16  5074.2   399.7  5096.2  402.42  5113.9  402.92  5136.5  404.55
  5199.5  406.42  5227.2  408.05  5257.5  408.76  5307.9  411.08  5398.6  413.67
#Mann= 7 ,-1 , 0
  4410.2     .07       0  4676.2    .035       0  4716.2     .07       0
  5009.5     .05       0  5021.8     .07       0  5044.8     .12       0
  5074.2     .07       0
Bank Sta=5009.5,5021.8
XS Rating Curve= 0 ,0
Exp/Cntr=0.3,0.1

Type RM Length L Ch R = 1 ,11473   ,449,449,449
BEGIN DESCRIPTION:
Stream0550 22.0
END DESCRIPTION:
XS GIS Cut Line= 3
        2351775.     13688425.03        2351675.       13687525.
        2351575.     13686824.98
#Sta/Elev= 30
  4090.1  418.08  4611.1  404.51  4663.6  404.95  4683.8   403.2  4703.9  402.77
  4713.9  403.33  4734.1  402.32  4764.3  403.08  4794.3  402.34  4804.5  402.78
  4844.7  401.09  4864.9  404.48  4893.7  399.86  4925.2  398.89  4945.4   399.8
  4955.4  398.37  4975.5  398.86  5009.5  396.41    5010  395.91  5022.3  396.41
  5046.2  398.09  5076.5  397.48  5116.9  398.49  5167.4  402.64  5192.9  403.07
  5379.2  408.27  5450.2  410.11  5460.3  411.43  5549.1  414.57  5702.8  418.91
#Mann= 9 ,-1 , 0
  4090.1     .05       0  4611.1      .1       0  4794.3    .035       0
  4893.7      .1       0  5009.5     .05       0  5022.3      .1       0
  5192.9     .07       0  5379.2    .035       0  5549.1     .07       0
Bank Sta=5009.5,5022.3
XS Rating Curve= 0 ,0
Exp/Cntr=0.3,0.1

Type RM Length L Ch R = 1 ,11024   ,449,449,449
BEGIN DESCRIPTION:
Stream0550 21.0
END DESCRIPTION:
XS GIS Cut Line= 3
      2351975.01     13688374.95        2352075.       13687475.
        2351875.     13686975.01
#Sta/Elev= 30
  4094.4  417.51  4215.1  414.22  4335.8  412.57  4416.3  410.66  4486.8  410.31
  4637.7  403.41    4738  401.43  4836.8  399.67  4909.3  399.35  4949.6  396.49
  4969.7  397.27  4979.8   396.2  4980.7  395.54  4983.4  393.55  4983.9  393.05
  4995.7  393.05  4996.2  393.55  4997.4  394.73  5021.4  396.78  5044.3  397.22
  5063.2  399.19  5068.6   398.4  5075.3   398.7  5092.8  400.59  5144.6  403.14
  5200.5  405.37  5230.1  405.36  5278.6  407.38  5476.5  412.86  5538.4  414.64
#Mann= 8 ,-1 , 0
  4094.4     .05       0    4738    .035       0  4836.8     .07       0
  4980.7      .1       0  4983.4     .05       0  4996.2      .1       0
  5144.6    .035       0  5476.5     .07       0
Bank Sta=4983.4,4996.2
XS Rating Curve= 0 ,0
Exp/Cntr=0.3,0.1

Type RM Length L Ch R = 1 ,10575   ,469,469,469
BEGIN DESCRIPTION:
Stream0550 20.0
END DESCRIPTION:
XS GIS Cut Line= 3
        2352375.     13688625.03        2352475.       13687425.
      2351875.01     13686925.01
#Sta/Elev= 30
  3790.5  422.44  4091.3   415.6  4178.6  413.37  4322.4  410.88  4442.8   406.1
  4543.1  400.41  4770.1  398.95  4816.6  398.06  4964.6  398.04  4984.7  395.62
  5001.8  394.88  5002.3  394.38  5014.9  394.88  5030.5   396.7  5051.3  395.43
  5065.6  395.71  5086.5  397.69  5115.1  396.57  5129.4  396.81  5143.7  398.61
  5164.6  399.57  5242.2   401.7  5385.2  404.26  5392.4  405.11  5398.9  404.48
    5421  405.91  5534.2  408.75  5591.5  411.39  5742.5  414.63  5775.7  414.84
#Mann= 8 ,-1 , 0
  3790.5    .035       0  4091.3     .07       0  4178.6    .035       0
  4770.1      .1       0  5001.8     .05       0  5014.9      .1       0
  5242.2    .035       0  5742.5     .07       0
Bank Sta=5001.8,5014.9
XS Rating Curve= 0 ,0
Exp/Cntr=0.3,0.1

Type RM Length L Ch R = 1 ,10106   ,492,492,492
BEGIN DESCRIPTION:
Stream0550 19.0
END DESCRIPTION:
XS GIS Cut Line= 3
      2352475.01     13688424.96        2352875.       13687225.
        2353175.       13686025.
#Sta/Elev= 30
  3729.2  418.35  3855.6  412.83  3914.6  411.26  3961.1  410.62  4003.2  408.21
  4152.2  403.52  4245.7  402.48  4287.8  403.08  4538.9  398.49  4641.7  397.16
  4658.6  397.02  4744.5  397.16  4847.3   397.3  4962.4  395.43    4973  396.84
  5004.4  394.52  5005.3  392.97  5005.8  392.47  5018.9  392.97  5086.3  395.75
  5117.8  396.81  5310.9  397.72    5512  400.86    5561   400.8    5677  403.33
  5911.5  410.56  5965.6  414.32  6070.8  418.28  6145.9  421.63    6231  425.22
#Mann= 14 ,-1 , 0
  3729.2     .07       0  3914.6     .12       0  4152.2     .07       0
  4538.9    .035       0  4641.7      .1       0  4658.6    .035       0
  4744.5     .07       0  4847.3      .1       0  5005.3     .05       0
  5018.9      .1       0  5086.3     .05       0  5310.9     .07       0
  6070.8    .035       0  6145.9     .07       0
Bank Sta=5005.3,5018.9
XS Rating Curve= 0 ,0
Exp/Cntr=0.3,0.1

Type RM Length L Ch R = 1 ,9614    ,460,460,460
BEGIN DESCRIPTION:
Stream0550 18.0
END DESCRIPTION:
XS GIS Cut Line= 3
        2352425.     13688625.01        2353325.       13687125.
        2353225.     13686025.03
#Sta/Elev= 30
  3237.9  421.13    3264  420.45  3405.1  419.56  3543.1  412.86  3661.2  409.65
  3770.5  404.76  3977.8  406.41  4194.2  405.62  4437.1   399.8  4528.5  396.77
  4696.4  395.82  4825.9  395.18  4878.3  396.35  4972.6  392.21  4973.1  391.71
  4986.3  392.21  4988.8  392.34  5037.4  394.22  5107.7  393.25  5137.8  396.14
  5191.3  396.39  5238.2  395.49  5408.9  399.07  5815.6  417.69  5840.7  416.11
  5890.9  419.29  5900.9  416.47  5951.2   422.2  6020.7  425.59  6091.7  427.44
#Mann= 11 ,-1 , 0
  3237.9    .035       0    3264     .07       0  3661.2     .12       0
  3977.8     .07       0  4437.1    .035       0  4696.4     .07       0
  4972.6     .05       0  4986.3     .07       0  4988.8      .1       0
  5191.3     .07       0  6020.7    .035       0
Bank Sta=4972.6,4986.3
XS Rating Curve= 0 ,0
Exp/Cntr=0.3,0.1

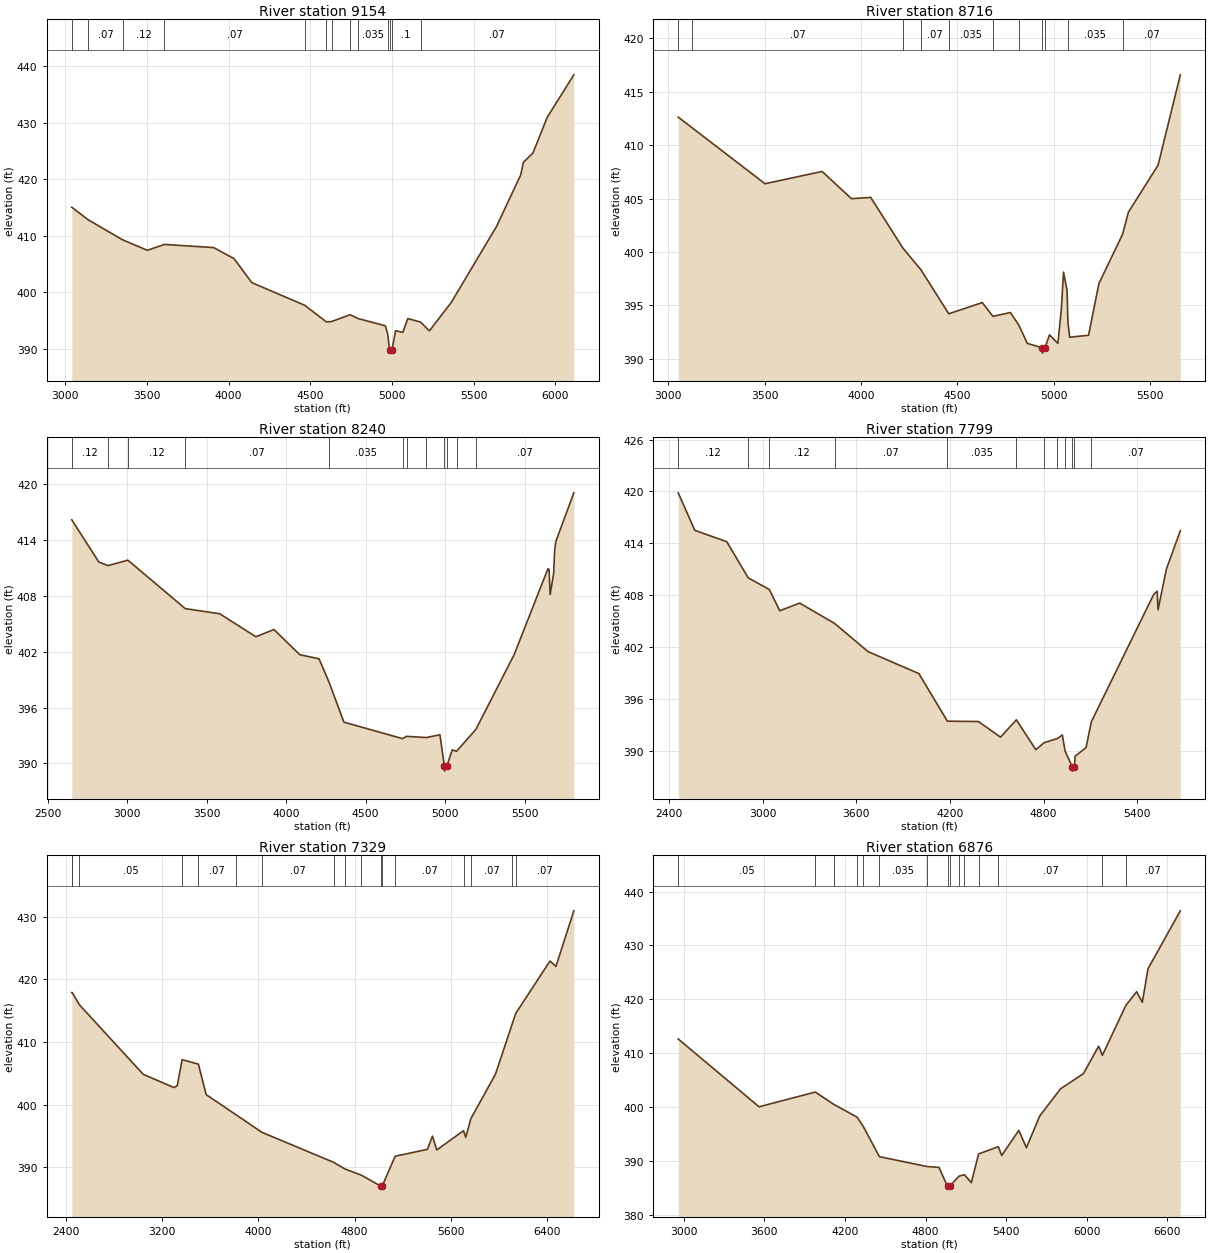
Type RM Length L Ch R = 1 ,9154    ,438,438,438
BEGIN DESCRIPTION:
Stream0550 17.0
END DESCRIPTION:
XS GIS Cut Line= 3
      2352625.01     13688724.99        2353675.       13687075.
        2353475.     13685974.98
#Sta/Elev= 30
  3039.4  415.05    3140  412.83  3350.3   409.3  3501.7  407.44  3606.8  408.48
    3908  407.92  4032.5  405.98  4141.7  401.73  4465.6  397.72    4598  394.79
  4629.8  394.85  4744.4  396.06  4790.2   395.4  4959.6  394.09  4973.6  392.63
  4985.3  389.77  4985.8  389.27    4999  389.77  5021.8  393.23  5066.3  392.94
  5096.8  395.38  5174.6  394.76  5228.9  393.21  5362.3  398.21  5639.3  411.62
  5787.9  420.76  5804.4  422.99  5862.9  424.64  5950.6  430.96  6113.2  438.45
#Mann= 13 ,-1 , 0
  3039.4    .035       0    3140     .07       0  3350.3     .12       0
  3606.8     .07       0  4465.6    .035       0    4598     .07       0
  4629.8    .035       0  4744.4     .07       0  4790.2    .035       0
  4973.6      .1       0  4985.3     .05       0    4999      .1       0
  5174.6     .07       0
Bank Sta=4985.3,4999
XS Rating Curve= 0 ,0
Exp/Cntr=0.3,0.1

Type RM Length L Ch R = 1 ,8716    ,476,476,476
BEGIN DESCRIPTION:
Stream0550 16.0
END DESCRIPTION:
XS GIS Cut Line= 3
        2352975.     13688574.99        2354025.       13686925.
      2353774.98     13686324.96
#Sta/Elev= 30
  3051.9  412.62  3122.1  411.65  3502.3  406.39  3798.6  407.54    3951  404.99
  4050.9  405.11    4218  400.37  4312.1  398.33  4455.9  394.22    4630  395.27
  4685.1  393.98  4775.7  394.34  4820.8  393.12  4863.7  391.45  4941.5  391.04
    4942  390.54  4955.3  391.04  4978.9  392.25  5022.3  391.45  5040.2  394.63
  5051.5  398.12  5069.9   396.4  5074.4  393.45  5083.5  392.03  5181.5  392.21
  5235.2  397.05  5358.1  401.66  5388.4  403.73  5542.3  408.13  5657.7  416.58
#Mann= 11 ,-1 , 0
  3051.9     .12       0  3122.1     .07       0    4218    .035       0
  4312.1     .07       0  4455.9    .035       0  4685.1     .07       0
  4820.8      .1       0  4941.5     .05       0  4955.3      .1       0
  5074.4    .035       0  5358.1     .07       0
Bank Sta=4941.5,4955.3
XS Rating Curve= 0 ,0
Exp/Cntr=0.3,0.1

Type RM Length L Ch R = 1 ,8240    ,441,441,441
BEGIN DESCRIPTION:
Stream0550 15.0
END DESCRIPTION:
XS GIS Cut Line= 3
      2352924.99     13688925.01        2354425.       13687125.
      2354974.98     13686525.02
#Sta/Elev= 30
    2652  416.12  2821.9   411.6  2879.8  411.21  3004.9  411.79  3365.4   406.6
  3582.1  406.05  3809.9  403.58  3923.1  404.36  4085.8  401.66  4206.9  401.22
  4269.2  398.74  4363.1  394.43  4732.3  392.66    4757  392.91  4882.1  392.78
  4967.1  393.08  4995.2  389.68  4995.7  389.18  5009.1  389.68  5044.7  391.46
  5071.2   391.3  5193.4  393.66  5433.8  401.67  5646.2  410.88  5653.3  410.79
  5660.1  408.11  5681.7  410.32  5688.5  412.86  5695.9  413.81    5809  419.01
#Mann= 12 ,-1 , 0
    2652     .12       0  2879.8    .035       0  3004.9     .12       0
  3365.4     .07       0  4269.2    .035       0  4732.3     .07       0
    4757    .035       0  4882.1     .07       0  4995.2     .05       0
  5009.1     .07       0  5071.2      .1       0  5193.4     .07       0
Bank Sta=4995.2,5009.1
XS Rating Curve= 0 ,0
Exp/Cntr=0.3,0.1

Type RM Length L Ch R = 1 ,7799    ,470,470,470
BEGIN DESCRIPTION:
Stream0550 14.0
END DESCRIPTION:
XS GIS Cut Line= 3
      2353025.01     13689074.99        2354825.       13687275.
      2355125.01     13686674.99
#Sta/Elev= 30
  2459.2  419.84  2565.2   415.5  2770.3  414.18  2907.6     410  3042.9  408.65
  3109.7  406.19    3237  407.08  3460.5  404.73  3675.4  401.46  4000.7  398.92
  4183.5  393.41  4382.5  393.37  4523.9  391.56  4625.2  393.57  4750.2  390.11
    4802  390.91  4888.7  391.41  4919.9  391.82  4937.4  389.96  4983.7  388.13
  4984.2  387.63  4997.6  388.13  5001.2  389.35  5071.9  390.36  5105.8  393.35
  5505.1  408.08  5527.4  408.46    5533   406.3  5586.1  410.99  5675.6  415.46
#Mann= 12 ,-1 , 0
  2459.2     .12       0  2907.6    .035       0  3042.9     .12       0
  3460.5     .07       0  4183.5    .035       0  4625.2     .07       0
    4802    .035       0  4888.7     .07       0  4937.4      .1       0
  4983.7     .05       0  4997.6      .1       0  5105.8     .07       0
Bank Sta=4983.7,4997.6
XS Rating Curve= 0 ,0
Exp/Cntr=0.3,0.1

Type RM Length L Ch R = 1 ,7329    ,453,453,453
BEGIN DESCRIPTION:
Stream0550 13.0
END DESCRIPTION:
XS GIS Cut Line= 3
        2353325.       13689425.        2355125.       13687625.
      2356325.02     13686524.98
#Sta/Elev= 30
  2449.4  417.91    2453  417.91  2513.5  415.95  3043.4  404.86  3297.9  402.75
  3326.2  403.04  3366.7   407.2    3502  406.48  3566.6  401.62  3815.4   398.4
  4029.7   395.6  4626.2  390.81  4719.9  389.75  4855.2  388.77    5016  387.03
  5016.5  386.53    5030  387.03  5137.5  391.78  5405.4  392.88  5447.9  394.99
  5483.4  392.78  5705.8  395.86  5724.1   394.8  5767.1  397.78  5971.7  404.89
    6111  412.92  6139.8  414.58  6424.6  422.95    6474  422.08  6622.9  430.96
#Mann= 17 ,-1 , 0
  2449.4     .05       0    2453     .07       0  2513.5     .05       0
  3366.7    .035       0    3502     .07       0  3815.4     .12       0
  4029.7     .07       0  4626.2      .1       0  4719.9    .035       0
  4855.2      .1       0    5016     .05       0    5030      .1       0
  5137.5     .07       0  5705.8     .12       0  5767.1     .07       0
    6111    .035       0  6139.8     .07       0
Bank Sta=5016,5030
XS Rating Curve= 0 ,0
Exp/Cntr=0.3,0.1

Type RM Length L Ch R = 1 ,6876    ,429,429,429
BEGIN DESCRIPTION:
Stream0550 12.0
END DESCRIPTION:
XS GIS Cut Line= 3
      2354124.99     13689525.02        2355325.       13687875.
        2356525.       13686675.
#Sta/Elev= 30
  2959.2  412.62  3560.9  400.02  3979.5  402.76    4116  400.49  4290.3   398.1
  4337.2  396.34  4456.5  390.76  4813.3  388.92  4900.1  388.77  4963.7  385.23
  4964.2  384.73  4978.7  385.23  5049.9  387.15  5089.4  387.41  5140.9  385.93
  5195.2  391.27  5341.8  392.61  5367.1  390.98  5494.4  395.64    5551  392.42
    5650  398.32  5805.5  403.37  5975.2  406.17  6088.4  411.28  6116.6  409.59
  6290.7  418.83  6371.2  421.39  6413.7  419.43  6456.1  425.67  6696.5  436.42
#Mann= 15 ,-1 , 0
  2959.2     .05       0  3979.5    .035       0    4116     .07       0
  4290.3    .035       0  4337.2     .07       0  4456.5    .035       0
  4813.3      .1       0  4963.7     .05       0  4978.7      .1       0
  5049.9     .12       0  5089.4      .1       0  5195.2     .12       0
  5341.8     .07       0  6116.6    .035       0  6290.7     .07       0
Bank Sta=4963.7,4978.7
XS Rating Curve= 0 ,0
Exp/Cntr=0.3,0.1