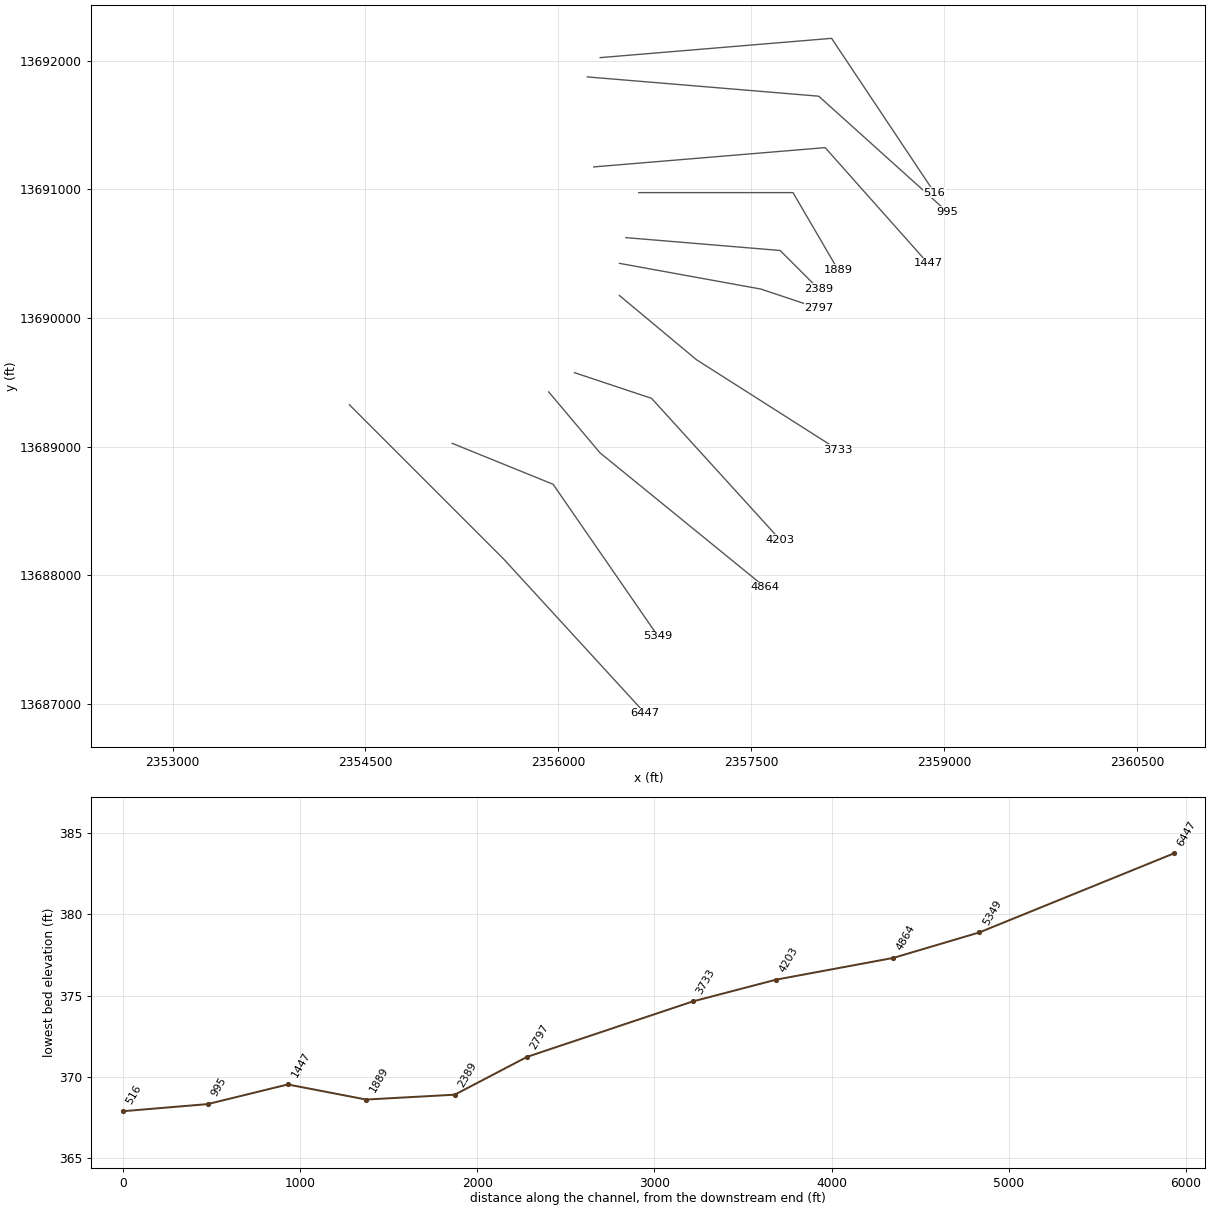
HEC-RAS study Stream0550.prj: Stream0550 Base Level Engineering

--- Stream0550.g01 (geometry) --- (continued)

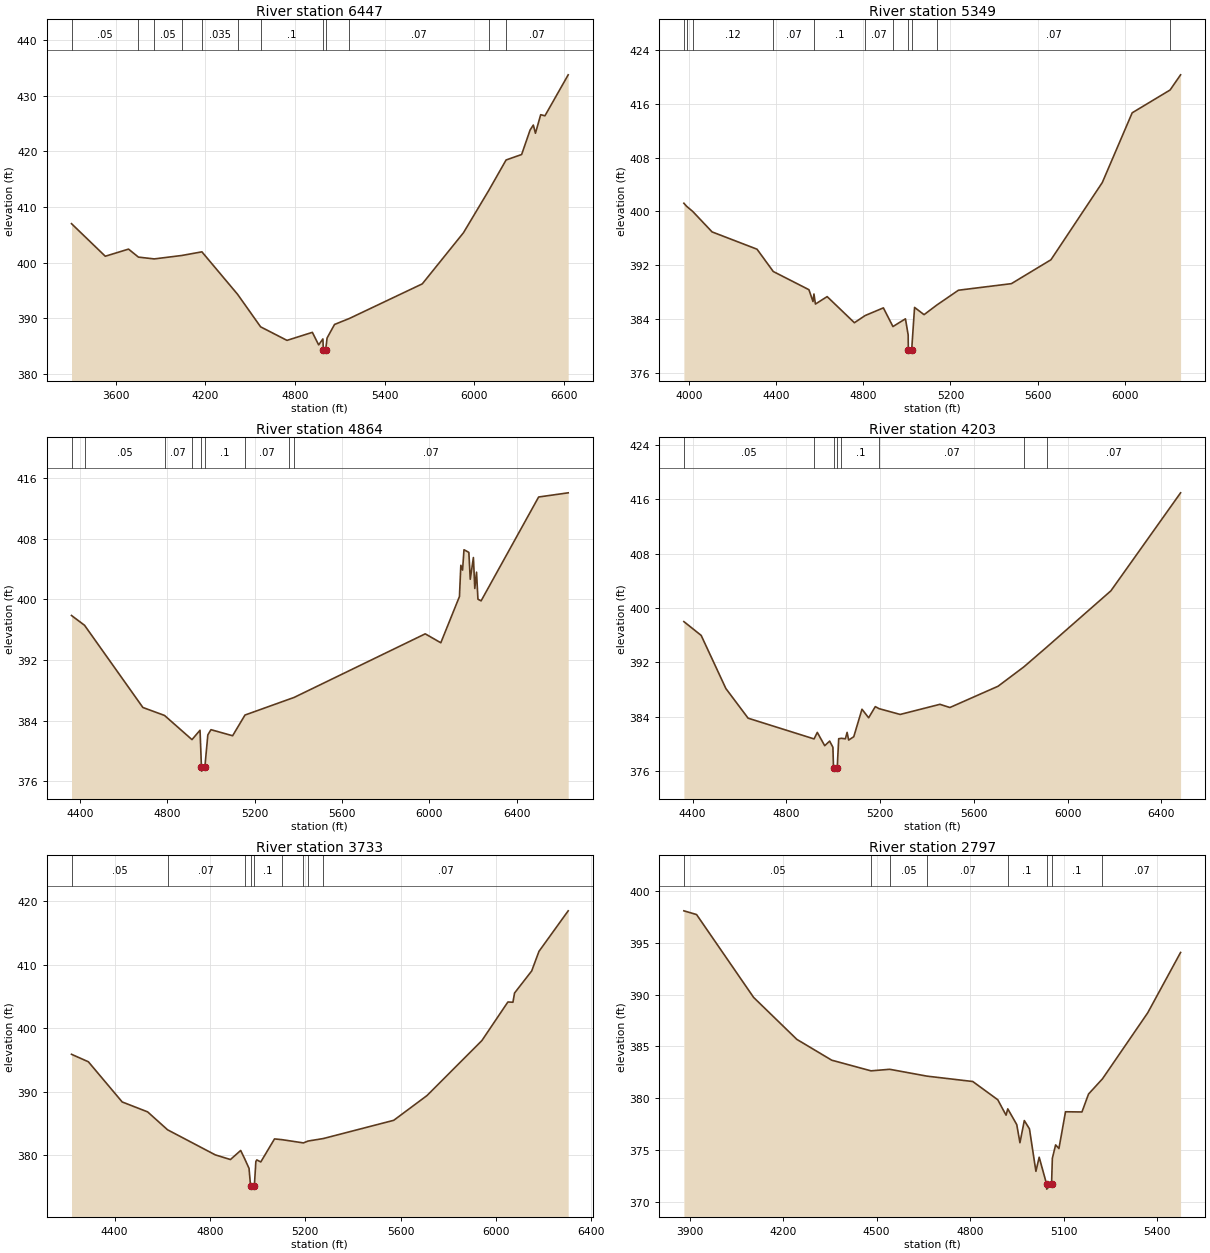
Type RM Length L Ch R = 1 ,6447    ,1098,1098,1098
BEGIN DESCRIPTION:
Stream0550 11.0
END DESCRIPTION:
XS GIS Cut Line= 3
      2354375.02     13689324.98        2355575.       13688125.
        2356675.       13686925.
#Sta/Elev= 30
  3303.2  407.01  3529.4  401.16    3685  402.44  3751.4     401  3857.1  400.68
  4042.2   401.3  4176.2  401.95  4415.1  394.32  4569.2  388.48  4745.7  386.05
  4915.4  387.49  4957.8  385.24  4986.1  386.31  4989.2  384.26  4989.7  383.76
  5004.2  384.26  5014.1  386.48    5064  388.91  5163.1  389.98  5651.4   396.2
  5927.3  405.39  6096.2  412.97  6212.4  418.45  6316.4  419.43  6373.1  423.83
  6394.7  424.72  6408.9  423.25    6444  426.58  6472.4  426.38  6628.1  433.74
#Mann= 12 ,-1 , 0
  3303.2     .05       0  3751.4     .07       0  3857.1     .05       0
  4042.2     .07       0  4176.2    .035       0  4415.1     .07       0
  4569.2      .1       0  4989.2     .05       0  5004.2      .1       0
  5163.1     .07       0  6096.2    .035       0  6212.4     .07       0
Bank Sta=4989.2,5004.2
XS Rating Curve= 0 ,0
Exp/Cntr=0.3,0.1

Type RM Length L Ch R = 1 ,5349    ,485,485,485
BEGIN DESCRIPTION:
Stream0550 10.0
END DESCRIPTION:
XS GIS Cut Line= 3
      2355174.98     13689025.01      2355959.02     13688706.83
        2356775.       13687525.
#Sta/Elev= 30
  3975.1  401.22  3987.5  400.77  4016.3  399.98  4104.6  396.95  4311.3  394.37
  4385.8  391.05  4549.7  388.34  4568.4  386.58  4572.8   387.7  4579.5   386.2
  4633.4  387.31  4758.6  383.42  4808.1  384.49  4891.8  385.63  4935.7  382.85
  4993.2     384  5005.7   381.6  5006.5  379.39    5007  378.89  5021.8  379.39
  5035.1   385.7  5078.7  384.62    5138  386.07  5236.6  388.26    5480  389.24
  5661.8   392.8  5897.8  404.31    6035  414.69  6209.2  418.09  6257.4  420.35
#Mann= 11 ,-1 , 0
  3975.1     .12       0  3987.5     .07       0  4016.3     .12       0
  4385.8     .07       0  4572.8      .1       0  4808.1     .07       0
  4935.7      .1       0  5006.5     .05       0  5021.8      .1       0
    5138     .07       0  6209.2     .05       0
Bank Sta=5006.5,5021.8
XS Rating Curve= 0 ,0
Exp/Cntr=0.3,0.1

Type RM Length L Ch R = 1 ,4864    ,661,661,661
BEGIN DESCRIPTION:
Stream0550 9.0
END DESCRIPTION:
XS GIS Cut Line= 3
      2355925.03     13689424.97       2356323.6     13688951.62
      2357607.23     13687906.49
#Sta/Elev= 30
  4361.8  397.86  4421.5  396.57  4688.6  385.72  4787.7  384.67  4913.4  381.48
  4950.3  382.72  4956.8  377.82  4957.3  377.32  4972.3  377.82    4986  382.11
  5000.4  382.79  5099.5  381.99    5156  384.72  5356.1  386.79  5380.6  387.04
  5981.4  395.44  6052.7  394.26    6138  400.36  6144.4  404.49  6152.3  403.85
  6158.8  406.54  6181.1  406.19  6187.5  402.64  6201.9  405.51  6208.3  401.43
  6216.2  403.58  6222.7  400.01  6237.1  399.79  6500.6   413.5  6635.9  414.05
#Mann= 9 ,-1 , 0
  4361.8     .07       0  4421.5     .05       0  4787.7     .07       0
  4913.4      .1       0  4956.8     .05       0  4972.3      .1       0
    5156     .07       0  5356.1    .035       0  5380.6     .07       0
Bank Sta=4956.8,4972.3
XS Rating Curve= 0 ,0
Exp/Cntr=0.3,0.1

Type RM Length L Ch R = 1 ,4203    ,470,470,470
BEGIN DESCRIPTION:
Stream0550 8.0
END DESCRIPTION:
XS GIS Cut Line= 3
      2356125.03     13689574.99        2356725.       13689375.
      2357724.98     13688275.03
#Sta/Elev= 30
  4363.1  397.98  4436.9  395.95  4542.3  388.13  4637.1  383.77  4918.5  380.72
  4932.3  381.68  4963.9  379.72    4985   380.4  4998.9  379.49  5001.4  376.48
  5001.9  375.98  5017.3  376.48  5023.6  380.75  5035.5  380.81    5052  380.73
  5059.4  381.68  5066.1  380.55  5087.8  381.04  5122.9  385.09  5151.3  383.83
  5179.7  385.47  5196.1  385.17  5285.8  384.32  5455.4  385.81  5497.9  385.34
  5703.4  388.47  5813.5  391.32  5911.6  394.24  6184.8  402.51  6482.1  416.93
#Mann= 8 ,-1 , 0
  4363.1     .05       0  4918.5     .07       0  5001.4     .05       0
  5017.3     .07       0  5035.5      .1       0  5196.1     .07       0
  5813.5    .035       0  5911.6     .07       0
Bank Sta=5001.4,5017.3
XS Rating Curve= 0 ,0
Exp/Cntr=0.3,0.1

Type RM Length L Ch R = 1 ,3733    ,936,936,936
BEGIN DESCRIPTION:
Stream0550 7.0
END DESCRIPTION:
XS GIS Cut Line= 3
      2356475.02     13690174.98        2357075.       13689675.
      2358174.97     13688975.02
#Sta/Elev= 30
    4219  395.88  4289.9   394.7  4431.8  388.37  4538.5  386.81  4622.1  383.99
  4822.3  380.04  4886.1   379.3  4929.1  380.73  4945.7  379.44  4964.2  377.91
  4970.6  375.14  4971.1  374.64  4986.5  375.14  4992.8  378.98  4996.7  379.24
  5013.5  378.92  5071.1  382.55  5102.9  382.43  5192.5  381.92  5211.5  382.21
  5276.2  382.61  5571.5  385.48  5711.2  389.38  5941.5  398.04  6050.7  404.12
  6071.9  404.08  6078.6  405.53  6150.6  409.01  6181.1  412.09  6303.8  418.48
#Mann= 9 ,-1 , 0
    4219     .05       0  4622.1     .07       0  4945.7      .1       0
  4970.6     .05       0  4986.5      .1       0  5102.9     .12       0
  5192.5     .07       0  5211.5     .12       0  5276.2     .07       0
Bank Sta=4970.6,4986.5
XS Rating Curve= 0 ,0
Exp/Cntr=0.3,0.1

Type RM Length L Ch R = 1 ,2797    ,408,408,408
BEGIN DESCRIPTION:
Stream0550 6.0
END DESCRIPTION:
XS GIS Cut Line= 3
      2356474.98       13690425.        2357575.       13690225.
        2358025.       13690075.
#Sta/Elev= 30
    3882  398.09  3922.7  397.73  4105.6  389.73  4244.1  385.68  4355.9  383.67
  4481.9  382.64    4542  382.79  4661.2  382.13  4808.2  381.61  4888.3  379.85
  4914.9  378.36  4920.4  378.97  4949.2  377.45  4959.4   375.7  4973.4  377.84
  4989.9  377.04  5010.6  372.94  5021.1   374.3  5044.7  371.72  5045.2  371.22
  5060.8  371.72  5063.3   374.2  5073.8  375.49  5084.4  375.14  5105.5  378.69
  5158.2  378.67  5179.3   380.4    5224  381.87    5369  388.24  5474.4  394.07
#Mann= 8 ,-1 , 0
    3882     .05       0  4481.9     .07       0    4542     .05       0
  4661.2     .07       0  4920.4      .1       0  5044.7     .05       0
  5060.8      .1       0    5224     .07       0
Bank Sta=5044.7,5060.8
XS Rating Curve= 0 ,0
Exp/Cntr=0.3,0.1

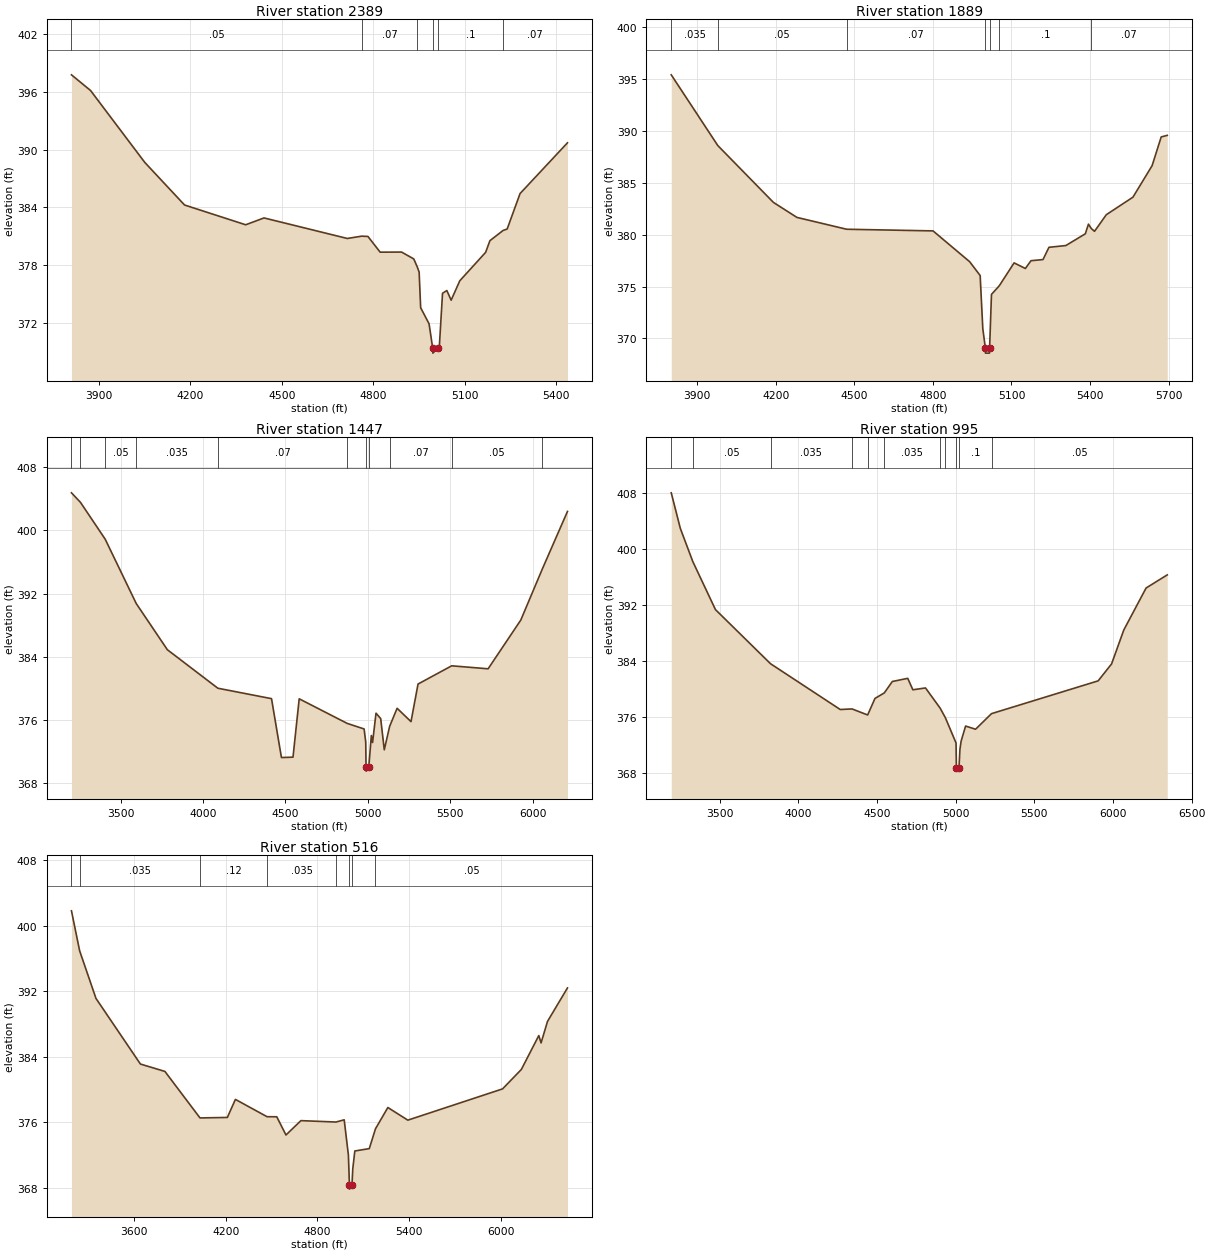
Type RM Length L Ch R = 1 ,2389    ,500,500,500
BEGIN DESCRIPTION:
Stream0550 5.0
END DESCRIPTION:
XS GIS Cut Line= 3
      2356524.96       13690625.        2357725.       13690525.
      2358025.03     13690224.97
#Sta/Elev= 30
  3809.4  397.75  3872.2  396.12  4050.3  388.66  4180.7  384.25  4381.4   382.2
  4441.6  382.91  4715.1  380.78  4762.4  381.02  4782.8  380.99  4822.9  379.36
  4893.2  379.37  4933.3  378.66    4945  377.81  4950.9  377.29  4955.9   373.6
  4983.5  371.93  4995.5  369.39    4996  368.89  5011.6  369.39  5017.1  369.52
  5027.7   375.1  5041.9  375.38    5056  374.38  5084.3  376.39  5169.2  379.34
  5183.3  380.55  5226.5  381.61  5239.9  381.76  5282.3  385.44  5437.9   390.7
#Mann= 6 ,-1 , 0
  3809.4     .05       0  4762.4     .07       0    4945      .1       0
  4995.5     .05       0  5011.6      .1       0  5226.5     .07       0
Bank Sta=4995.5,5011.6
XS Rating Curve= 0 ,0
Exp/Cntr=0.3,0.1

Type RM Length L Ch R = 1 ,1889    ,442,442,442
BEGIN DESCRIPTION:
Stream0550 4.0
END DESCRIPTION:
XS GIS Cut Line= 3
        2356625.       13690975.        2357825.       13690975.
      2358174.99     13690375.02
#Sta/Elev= 30
  3800.4  395.39  3978.2  388.58  4190.4  383.11  4280.4  381.66  4470.3  380.52
  4800.4  380.36  4940.4  377.39  4980.4  376.06  4990.4  370.96  5000.2  369.09
  5000.7  368.59  5015.9  368.59  5016.4  369.09  5023.6  374.25  5053.2  375.07
    5110  377.28    5153  376.74  5174.5  377.49  5220.4   377.6  5243.1  378.78
  5307.6  378.95    5382  380.08    5394  381.01  5404.9  380.59  5417.2  380.32
  5462.2  381.92    5564  383.61  5637.1  386.64  5671.9  389.41    5695  389.56
#Mann= 7 ,-1 , 0
  3800.4    .035       0  3978.2     .05       0  4470.3     .07       0
  5000.2     .05       0  5016.4     .07       0  5053.2      .1       0
  5404.9     .07       0
Bank Sta=5000.2,5016.4
XS Rating Curve= 0 ,0
Exp/Cntr=0.3,0.1

Type RM Length L Ch R = 1 ,1447    ,452,452,452
BEGIN DESCRIPTION:
Stream0550 3.0
END DESCRIPTION:
XS GIS Cut Line= 3
      2356275.04       13691175.        2358075.       13691325.
      2358875.03     13690424.97
#Sta/Elev= 30
    3201  404.77  3255.8  403.56  3405.7   398.9  3594.1  390.75    3783   384.9
  4089.5  380.02  4415.2   378.7  4475.4  371.24  4545.6  371.29  4583.2  378.68
  4874.1  375.57  4977.1  374.86  4987.1  373.19  4988.9  370.02  4989.4  369.52
  5005.5  370.02    5021  374.03  5028.5  373.14  5049.4  376.86  5077.9  376.17
  5099.6  372.22  5132.1  375.19  5177.4  377.48  5261.8  375.79  5304.5  380.55
  5508.8  382.86  5729.7  382.48  5928.3  388.66  6057.9  395.08  6211.4  402.41
#Mann= 11 ,-1 , 0
    3201     .05       0  3255.8    .035       0  3405.7     .05       0
  3594.1    .035       0  4089.5     .07       0  4874.1      .1       0
  4988.9     .05       0  5005.5      .1       0  5132.1     .07       0
  5508.8     .05       0  6057.9     .07       0
Bank Sta=4988.9,5005.5
XS Rating Curve= 0 ,0
Exp/Cntr=0.3,0.1

Type RM Length L Ch R = 1 ,995     ,479,479,479
BEGIN DESCRIPTION:
Stream0550 2.0
END DESCRIPTION:
XS GIS Cut Line= 3
      2356224.96       13691875.        2358025.       13691725.
      2359024.97     13690825.03
#Sta/Elev= 30
  3193.3  407.96    3251  402.89  3330.4  398.16  3474.3  391.32  3824.3  383.61
    4267  377.09  4342.2  377.17  4441.2  376.31  4487.8  378.67  4546.8  379.45
  4598.2  381.08    4696  381.53  4728.6   379.9  4808.9  380.16  4901.6  377.29
  4934.9  375.93  5002.9  372.32  5005.1  368.81  5005.6  368.31  5021.7  368.81
  5027.6  371.42  5035.1  372.58  5063.5  374.73    5127  374.28  5228.2   376.5
  5905.8  381.17    5991  383.58  6068.8  388.42  6210.4   394.4  6344.9  396.27
#Mann= 11 ,-1 , 0
  3193.3     .07       0  3330.4     .05       0  3824.3    .035       0
  4342.2     .07       0  4441.2     .12       0  4546.8    .035       0
  4901.6     .07       0  4934.9      .1       0  5005.1     .05       0
  5021.7      .1       0  5228.2     .05       0
Bank Sta=5005.1,5021.7
XS Rating Curve= 0 ,0
Exp/Cntr=0.3,0.1

Type RM Length L Ch R = 1 ,516     ,0,0,0
BEGIN DESCRIPTION:
Stream0550 1.0
END DESCRIPTION:
XS GIS Cut Line= 3
      2356324.99       13692025.        2358125.       13692175.
      2358925.02     13690974.97
#Sta/Elev= 30
  3188.8   401.8  3242.3  396.93  3349.4  391.12  3640.4  383.12  3800.9  382.22
  4030.6  376.55  4209.8  376.61  4262.5  378.81  4469.8   376.7  4533.5  376.69
  4593.7  374.47  4691.5  376.22  4921.4  376.05    4975  376.32  5002.6  372.02
  5009.3  368.37  5009.8  367.87  5025.9  368.37  5031.1  370.33  5044.6  372.52
  5139.3  372.81  5179.8  375.22    5261  377.82  5391.7  376.28  6012.1  380.09
  6135.3  382.46  6249.5  386.59  6264.5   385.7  6306.6  388.32  6437.3   392.4
#Mann= 8 ,-1 , 0
  3188.8     .07       0  3242.3    .035       0  4030.6     .12       0
  4469.8    .035       0  4921.4      .1       0  5009.3     .05       0
  5025.9      .1       0  5179.8     .05       0
Bank Sta=5009.3,5025.9
XS Rating Curve= 0 ,0
Exp/Cntr=0.3,0.1

Chan Stop Cuts=-1
Use User Specified Reach Order=0
Composite Channel Slope=5