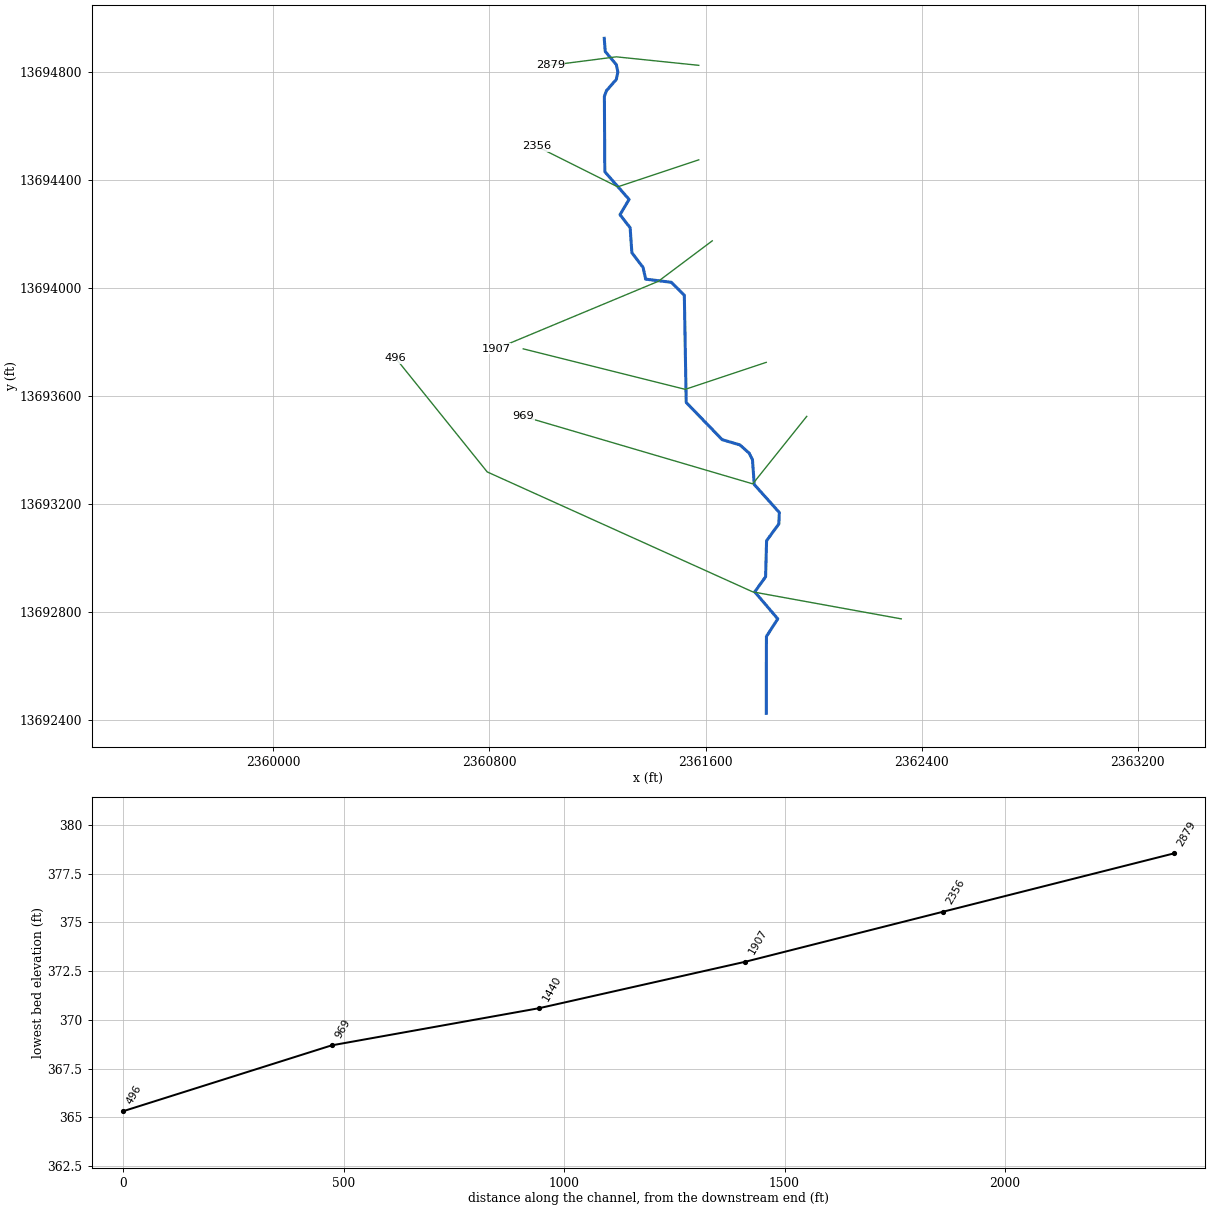
--- Stream0551.prj (project) ---

Proj Title=Stream0551 Base Level Engineering
Current Plan=p01
Default Exp/Contr=0.3,0.1
English Units
Geom File=g01
Flow File=f01
Plan File=p01
BEGIN DESCRIPTION:
Stream0551
END DESCRIPTION:

--- Stream0551.p01 (plan) ---

Plan Title=Multiple Run
Short Identifier=Multiple
Geom File=g01
Flow File=f01
Subcritical Flow
K Sum by GR= 0
Std Step Tol= 0.01
Critical Tol= 0.01
Num of Std Step Trials= 20
Max Error Tol= 0.3
Flow Tol Ratio= 0.001
Split Flow NTrial= 30
Split Flow Tol= 0.02
Split Flow Ratio= 0.02
Log Output Level= 0
Friction Slope Method= 1
Unsteady Friction Slope Method= 2
Unsteady Bridges Friction Slope Method= 1
Parabolic Critical Depth
Global Vel Dist=  1 , 1 , 1
Global Log Level= 0
CheckData=True
Encroach Param= -1, 0, 0, 0
BEGIN DESCRIPTION:
Multiple Run
END DESCRIPTION:

--- Stream0551.f01 (steady flow) ---

Flow Title=Multiple
Number of Profiles=7
Profile Names=10-year,25-year,50-year,1pct_min,100-year,1pct_plu,500-year
River Rch & RM= Stream0551,Reach-1,2879
     506     804    1069     689    1375    2744    2252
Boundary for River Rch & Prof#=Stream0551,Reach-1,1
Up Type=0
Dn Type=3
Dn Slope=0.005
Boundary for River Rch & Prof#=Stream0551,Reach-1,2
Up Type=0
Dn Type=3
Dn Slope=0.005
Boundary for River Rch & Prof#=Stream0551,Reach-1,3
Up Type=0
Dn Type=3
Dn Slope=0.005
Boundary for River Rch & Prof#=Stream0551,Reach-1,4
Up Type=0
Dn Type=3
Dn Slope=0.005
Boundary for River Rch & Prof#=Stream0551,Reach-1,5
Up Type=0
Dn Type=3
Dn Slope=0.005
Boundary for River Rch & Prof#=Stream0551,Reach-1,6
Up Type=0
Dn Type=3
Dn Slope=0.005
Boundary for River Rch & Prof#=Stream0551,Reach-1,7
Up Type=0
Dn Type=3
Dn Slope=0.005

--- Stream0551.g01 (geometry) ---

Geom Title=Existing Conditions

River Reach=Stream0551,Reach-1
Reach XY= 30
      2361225.00     13694925.00      2361228.69     13694876.49
      2361269.88     13694827.25      2361275.47     13694800.00
      2361269.63     13694772.82      2361233.19     13694731.08
      2361225.54     13694709.79      2361227.07     13694430.85
      2361316.99     13694328.33      2361283.29     13694271.78
      2361320.92     13694223.50      2361327.32     13694130.94
      2361368.70     13694076.78      2361378.38     13694033.15
      2361473.68     13694021.46      2361521.56     13693973.78
      2361528.54     13693576.46      2361661.80     13693438.64
      2361727.57     13693419.26      2361761.74     13693388.65
      2361773.90     13693364.67      2361780.54     13693272.58
      2361873.37     13693168.96      2361871.66     13693126.75
      2361826.25     13693064.50      2361822.52     13692930.86
      2361782.34     13692874.90      2361867.66     13692775.10
      2361825.66     13692709.84      2361825.00     13692425.00

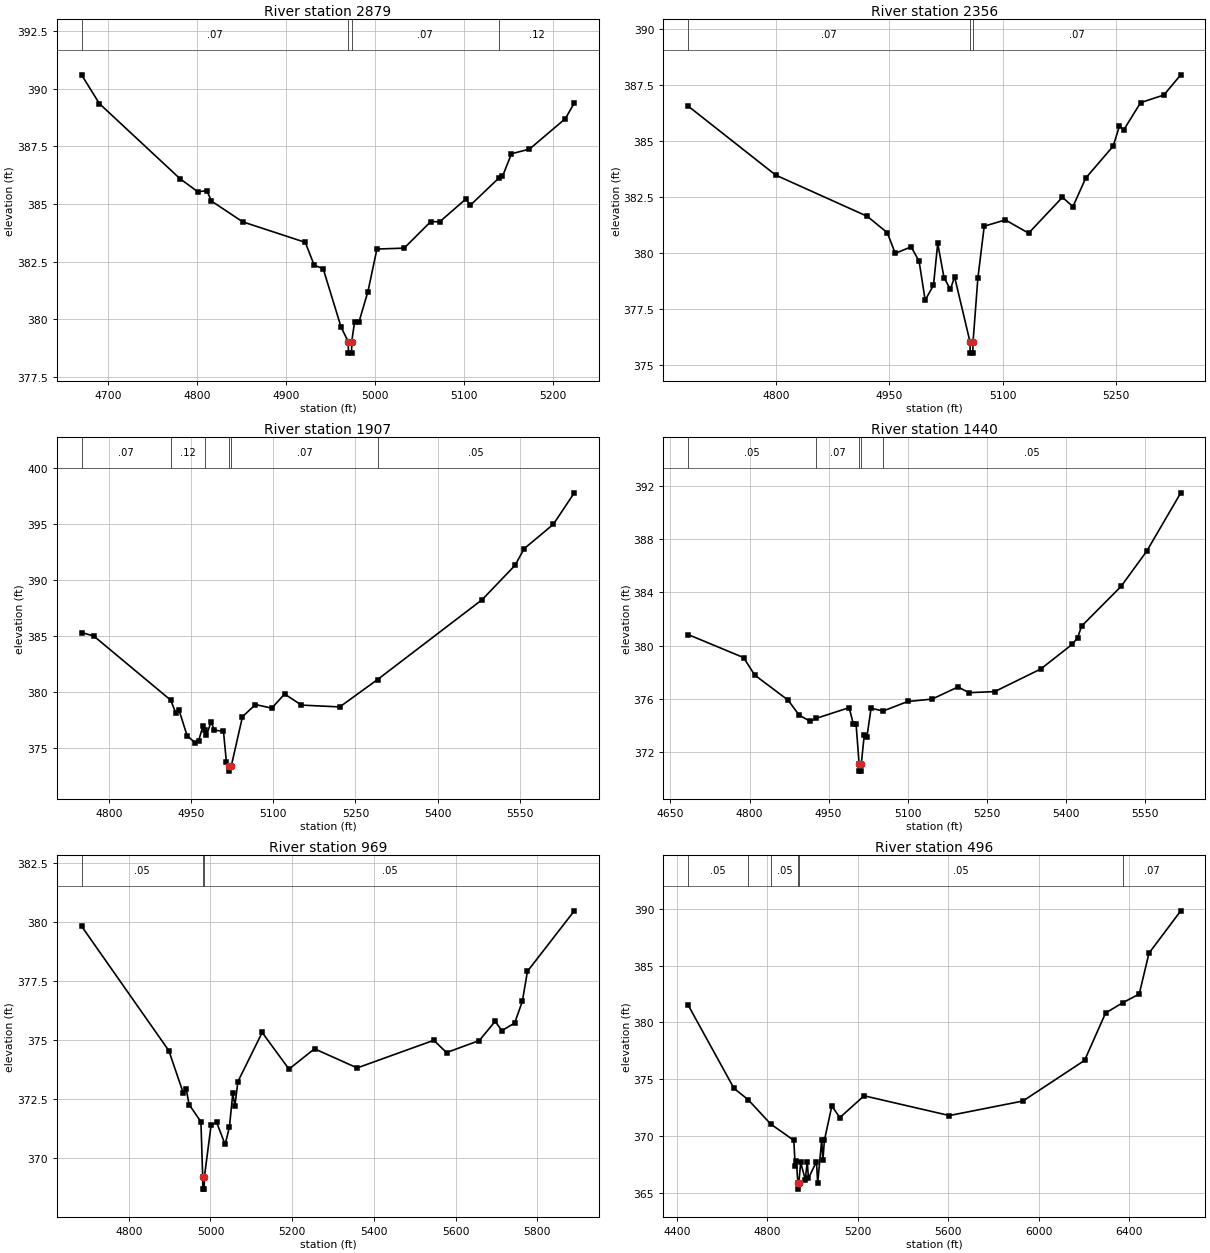
Type RM Length L Ch R = 1,2879,523,523,523
BEGIN DESCRIPTION:
Stream0551 6.0
END DESCRIPTION:
XS GIS Cut Line= 3
      2361575.03     13694825.00      2361269.78     13694856.50
      2361024.97     13694825.00
#Sta/Elev= 30
  4670.3  390.60  4690.4  389.35  4780.9  386.10  4801.0  385.53  4811.1  385.58
  4816.3  385.13  4851.3  384.23  4921.7  383.34  4931.7  382.35  4941.8  382.20
  4961.9  379.67  4969.9  379.04  4970.2  378.54  4973.7  378.54  4973.9  379.04
  4977.1  379.90  4982.1  379.90  4992.1  381.21  5002.2  383.05  5032.8  383.09
  5062.7  384.24  5072.7  384.23  5102.2  385.22  5107.2  384.95  5139.0  386.12
  5143.3  386.20  5153.4  387.18  5173.6  387.38  5213.9  388.70  5224.0  389.38
#Mann=4,-1,0
  4670.3    0.07       0  4969.9    0.05       0  4973.9    0.07       0
  5139.0    0.12       0
Bank Sta=4969.9,4973.9
Exp/Cntr=0.3,0.1

Type RM Length L Ch R = 1,2356,449,449,449
BEGIN DESCRIPTION:
Stream0551 5.0
END DESCRIPTION:
XS GIS Cut Line= 3
      2361574.96     13694474.99      2361275.00     13694375.00
      2360975.00     13694525.00
#Sta/Elev= 30
  4683.9  386.57  4799.8  383.49  4921.0  381.65  4947.4  380.92  4957.9  380.00
  4979.0  380.29  4989.5  379.64  4997.5  377.91  5008.5  378.58  5014.1  380.44
  5022.4  378.92  5030.8  378.39  5036.4  378.95  5056.8  376.05  5057.0  375.55
  5060.5  375.55  5060.8  376.05  5067.2  378.90  5075.6  381.21  5103.5  381.49
  5134.3  380.90  5179.0  382.50  5192.9  382.08  5209.7  383.35  5246.1  384.78
  5254.4  385.68  5260.0  385.50  5282.4  386.72  5313.1  387.06  5335.5  387.96
#Mann=3,-1,0
  4683.9    0.07       0  5056.8    0.05       0  5060.8    0.07       0
Bank Sta=5056.8,5060.8
Exp/Cntr=0.3,0.1

Type RM Length L Ch R = 1,1907,467,467,467
BEGIN DESCRIPTION:
Stream0551 4.0
END DESCRIPTION:
XS GIS Cut Line= 3
      2361625.01     13694175.01      2361425.00     13694025.00
      2360825.01     13693775.01
#Sta/Elev= 30
  4749.7  385.32  4771.6  385.03  4912.6  379.30  4921.6  378.18  4927.8  378.40
  4942.4  376.15  4957.0  375.50  4963.3  375.65  4971.6  377.02  4974.4  376.63
  4977.8  376.16  4986.2  377.37  4992.4  376.63  5008.9  376.53  5014.3  373.77
  5019.4  373.48  5019.6  372.98  5023.4  373.48  5043.6  377.83  5067.4  378.91
  5097.2  378.59  5120.5  379.85  5151.4  378.86  5221.3  378.70  5290.4  381.14
  5481.3  388.25  5541.4  391.31  5558.2  392.80  5611.3  394.96  5649.7  397.77
#Mann=6,-1,0
  4749.7    0.07       0  4912.6    0.12       0  4974.4    0.07       0
  5019.4    0.05       0  5023.4    0.07       0  5290.4    0.05       0
Bank Sta=5019.4,5023.4
Exp/Cntr=0.3,0.1

Type RM Length L Ch R = 1,1440,471,471,471
BEGIN DESCRIPTION:
Stream0551 3.0
END DESCRIPTION:
XS GIS Cut Line= 3
      2361825.02     13693725.01      2361525.00     13693625.00
      2360925.02     13693775.00
#Sta/Elev= 30
  4683.3  380.84  4788.7  379.11  4809.8  377.80  4873.1  375.92  4894.1  374.80
  4915.2  374.33  4926.9  374.56  4989.0  375.36  4996.9  374.12  5002.1  374.12
  5007.9  371.10  5008.1  370.60  5011.6  370.60  5011.9  371.10  5017.6  373.33
  5022.7  373.18  5030.5  375.31  5053.6  375.11  5100.1  375.82  5146.4  376.00
  5195.4  376.91  5216.0  376.48  5265.0  376.56  5352.6  378.26  5411.9  380.10
  5422.2  380.59  5429.9  381.47  5504.6  384.44  5553.6  387.10  5618.0  391.46
#Mann=5,-1,0
  4683.3    0.05       0  4926.9    0.07       0  5007.9    0.05       0
  5011.9    0.07       0  5053.6    0.05       0
Bank Sta=5007.9,5011.9
Exp/Cntr=0.3,0.1

Type RM Length L Ch R = 1,969,473,473,473
BEGIN DESCRIPTION:
Stream0551 2.0
END DESCRIPTION:
XS GIS Cut Line= 3
      2361975.01     13693525.01      2361775.00     13693275.00
      2360924.97     13693525.01
#Sta/Elev= 30
  4684.5  379.82  4898.2  374.55  4933.4  372.76  4940.6  372.93  4947.8  372.27
  4976.7  371.54  4981.1  369.19  4981.3  368.69  4984.8  368.69  4985.1  369.19
  5001.5  371.39  5015.1  371.52  5035.9  370.58  5046.4  371.31  5054.7  372.74
  5059.9  372.22  5067.2  373.24  5126.6  375.32  5192.3  373.77  5254.8  374.63
  5359.1  373.82  5546.7  374.99  5578.0  374.47  5658.2  374.98  5696.8  375.79
  5713.5  375.40  5744.7  375.72  5763.5  376.64  5776.0  377.91  5890.7  380.47
#Mann=3,-1,0
  4684.5    0.05       0  4981.1    0.05       0  4985.1    0.05       0
Bank Sta=4981.1,4985.1
Exp/Cntr=0.3,0.1

Type RM Length L Ch R = 1,496,0,0,0
BEGIN DESCRIPTION:
Stream0551 1.0
END DESCRIPTION:
XS GIS Cut Line= 4
      2362325.03     13692774.99      2361775.00     13692875.00
      2360791.62     13693319.20      2360452.60     13693740.42
#Sta/Elev= 30
  4448.6  381.54  4651.9  374.18  4713.8  373.20  4814.3  371.04  4916.2  369.61
  4922.5  367.39  4927.6  367.79  4934.5  365.81  4934.8  365.31  4938.5  365.81
  4946.7  367.66  4967.0  366.15  4975.9  367.74  4981.0  366.26  5016.5  367.73
  5022.0  365.87  5039.6  369.61  5045.1  367.88  5051.5  369.60  5084.5  372.63
  5119.9  371.61  5227.1  373.53  5604.2  371.79  5929.4  373.07  6202.1  376.65
  6294.9  380.82  6370.9  381.73  6443.7  382.49  6486.8  386.09  6627.4  389.82
#Mann=6,-1,0
  4448.6    0.05       0  4713.8   0.035       0  4814.3    0.05       0
  4934.5    0.05       0  4938.5    0.05       0  6370.9    0.07       0
Bank Sta=4934.5,4938.5
Exp/Cntr=0.3,0.1

Chan Stop Cuts=-1