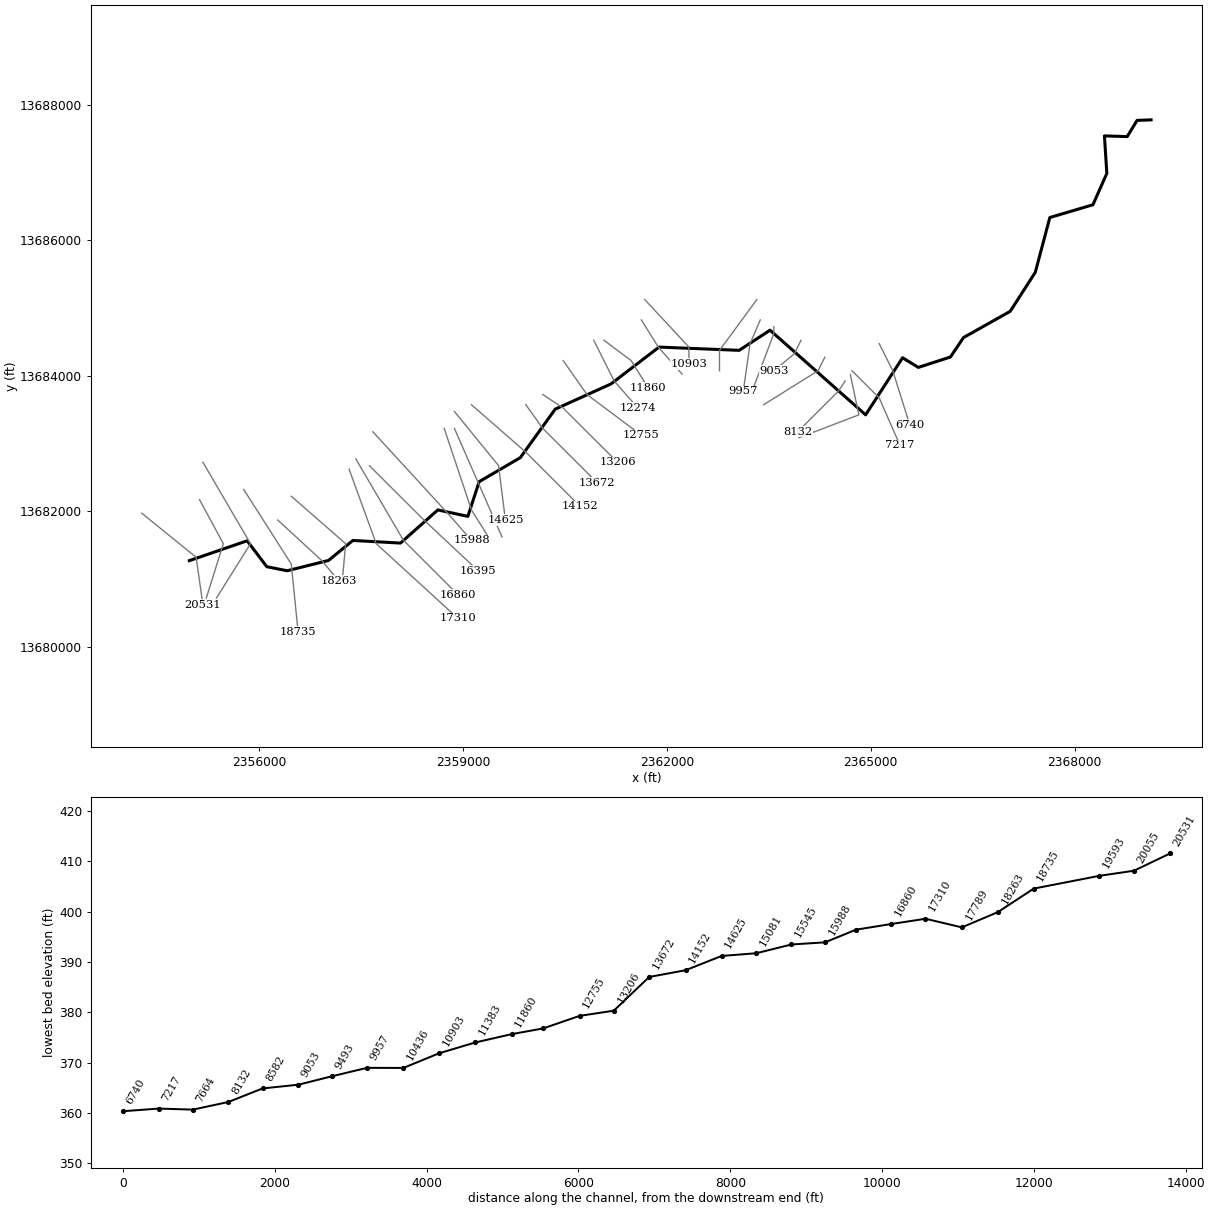
--- Stream0552.prj (project) ---

Proj Title=Stream0552 Base Level Engineering
Current Plan=p01
Default Exp/Contr=0.3,0.1
English Units
Geom File=g01
Flow File=f01
Plan File=p01
Y Axis Title=Elevation
X Axis Title(PF)=Main Channel Distance
X Axis Title(XS)=Station
BEGIN DESCRIPTION:
Stream0552
END DESCRIPTION:
DSS Export Rating Curves= 0
DSS Export Rating Curve Sorted= 0
DSS Export Volume Flow Curves= 0
DXF OffsetX= 0
DXF OffsetY= 0
DXF ScaleX= 1
DXF ScaleY= 10

--- Stream0552.p01 (plan) ---

Plan Title=Multiple Run
Short Identifier=Multiple
Geom File=g01
Flow File=f01
Subcritical Flow
K Sum by GR= 0
Std Step Tol= 0.01
Critical Tol= 0.01
Num of Std Step Trials= 20
Max Error Tol= 0.3
Flow Tol Ratio= 0.001
Split Flow NTrial= 30
Split Flow Tol= 0.02
Split Flow Ratio= 0.02
Log Output Level= 0
Friction Slope Method= 1
Unsteady Friction Slope Method= 2
Unsteady Bridges Friction Slope Method= 1
Parabolic Critical Depth
Global Vel Dist=  1 , 1 , 1
Global Log Level= 0
CheckData=True
Encroach Param= -1, 0, 0, 0
BEGIN DESCRIPTION:
Multiple Run
END DESCRIPTION:

--- Stream0552.f01 (steady flow) ---

Flow Title=Multiple
Number of Profiles=7
Profile Names=10-year,25-year,50-year,1pct_min,100-year,1pct_plu,500-year
River Rch & RM= Stream0552,Reach-1,20531
     659    1074    1452     950    1896    3784    3208
River Rch & RM= Stream0552,Reach-1,20055
     818    1346    1832    1206    2407    4802    4119
River Rch & RM= Stream0552,Reach-1,15988
    1134    1895    2604    1729    3451    6885    6010
River Rch & RM= Stream0552,Reach-1,14152
    1329    2235    3084    2055    4100    8181    7194
River Rch & RM= Stream0552,Reach-1,9957
    1422    2397    3312    2209    4408    8794    7748
River Rch & RM= Stream0552,Reach-1,7217
    1906    3227    4475    2991    5967   11906   10530
River Rch & RM= Stream0552,Reach-1,507
    1940    3287    4560    3049    6083   12138   10743
Boundary for River Rch & Prof#=Stream0552,Reach-1,1
Up Type=0
Dn Type=3
Dn Slope=0.005
Boundary for River Rch & Prof#=Stream0552,Reach-1,2
Up Type=0
Dn Type=3
Dn Slope=0.005
Boundary for River Rch & Prof#=Stream0552,Reach-1,3
Up Type=0
Dn Type=3
Dn Slope=0.005
Boundary for River Rch & Prof#=Stream0552,Reach-1,4
Up Type=0
Dn Type=3
Dn Slope=0.005
Boundary for River Rch & Prof#=Stream0552,Reach-1,5
Up Type=0
Dn Type=3
Dn Slope=0.005
Boundary for River Rch & Prof#=Stream0552,Reach-1,6
Up Type=0
Dn Type=3
Dn Slope=0.005
Boundary for River Rch & Prof#=Stream0552,Reach-1,7
Up Type=0
Dn Type=3
Dn Slope=0.005

--- Stream0552.g01 (geometry) ---

Geom Title=Existing Conditions
Program Version=4.10

River Reach=Stream0552      ,Reach-1
Reach XY= 30
        2354975.       13681275.      2355825.32     13681567.77
        2356115.     13681185.63      2356414.71       13681126.
      2357023.55     13681278.53      2357380.94     13681572.74
      2358081.72     13681534.17      2358630.97     13682022.86
      2359073.58     13681928.04      2359238.61       13682439.
      2359845.16     13682794.61      2360357.87      13683508.7
       2361177.7     13683880.36      2361885.63     13684424.39
       2363064.5      13684376.2      2363518.96     13684673.43
        2364925.       13683425.      2365468.81     13684267.25
      2365699.91     13684124.38      2366173.37     13684278.13
      2366364.84     13684564.64      2367052.48     13684951.66
      2367421.25     13685526.55      2367635.35     13686335.12
      2368269.18     13686522.68       2368473.8      13686985.5
      2368438.52     13687538.41       2368773.6       13687528.
      2368918.79      13687767.2        2369125.       13687775.

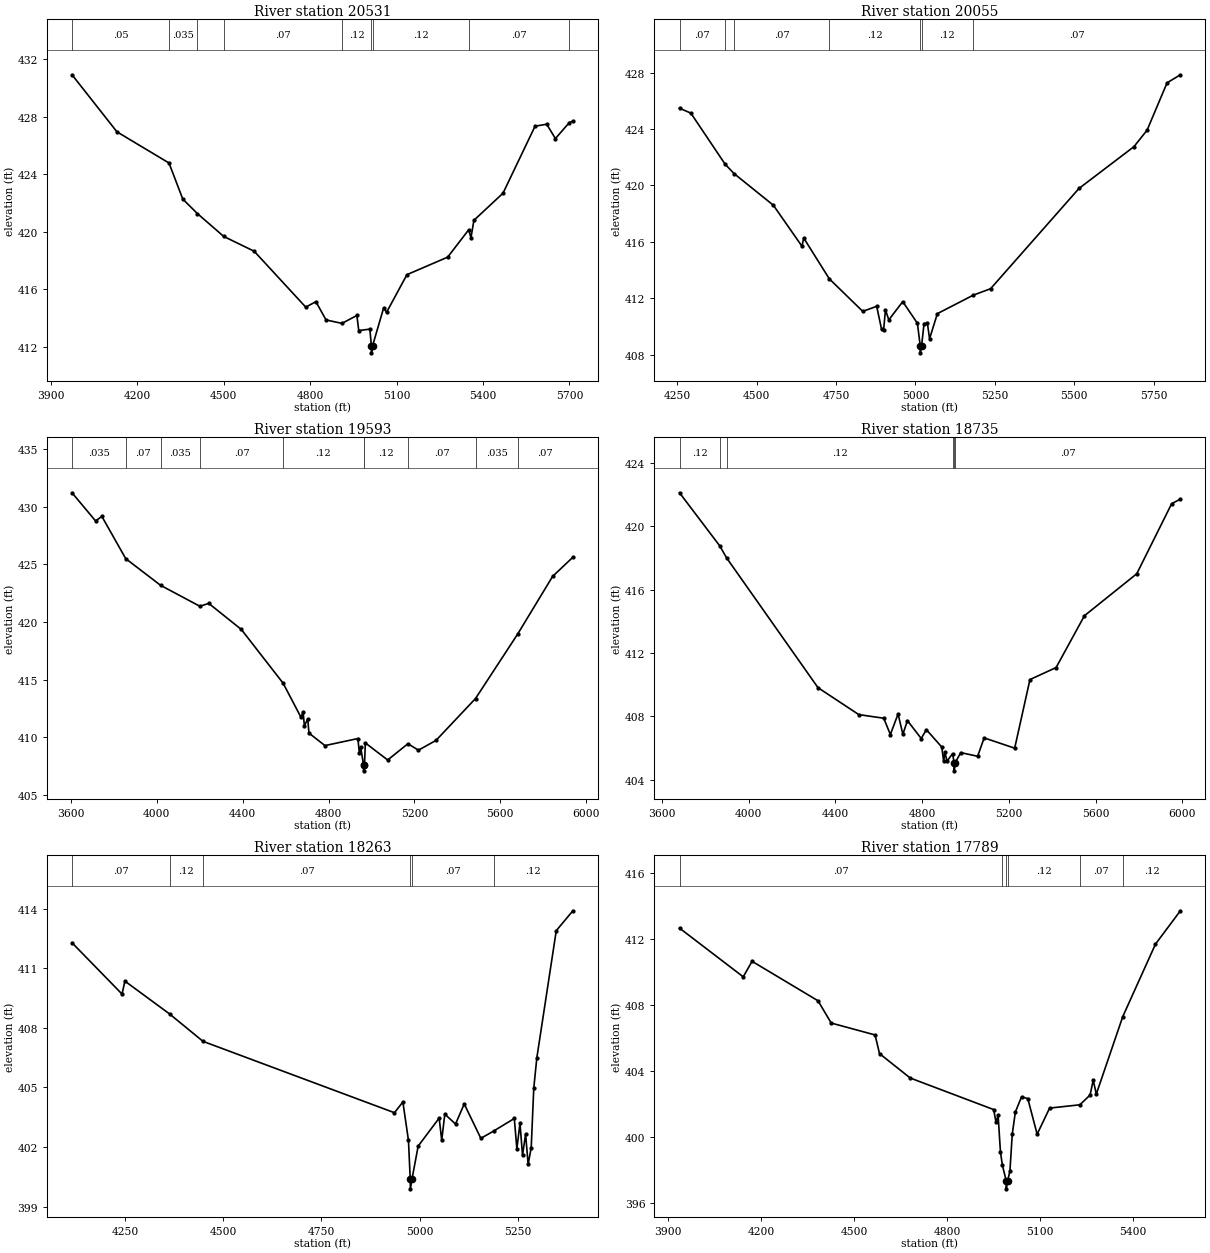
Type RM Length L Ch R = 1 ,20531   ,476,476,476
BEGIN DESCRIPTION:
Stream0552 42.0
END DESCRIPTION:
XS GIS Cut Line= 3
      2354274.99     13681975.01        2355075.       13681325.
        2355175.     13680624.99
#Sta/Elev= 30
  3974.1  430.91    4130  426.94  4310.6  424.77  4358.4  422.26  4409.2  421.25
  4500.5  419.66  4606.2  418.63  4785.1  414.74  4820.3  415.12  4855.5  413.85
  4910.7  413.61  4962.5  414.16    4969  413.11  5007.4  413.21  5012.9  412.06
  5013.2  411.56  5017.1  412.06  5055.4  414.69  5065.5  414.38  5136.2     417
  5277.6  418.22  5350.3  420.12  5358.4  419.57  5368.5  420.78  5469.6  422.67
  5580.7  427.33  5621.1  427.47  5651.4  426.47  5699.4  427.58    5712  427.69
#Mann= 9 ,-1 , 0
  3974.1     .05       0  4310.6    .035       0  4409.2     .05       0
  4500.5     .07       0  4910.7     .12       0  5012.9     .05       0
  5017.1     .12       0  5350.3     .07       0  5699.4    .035       0
Bank Sta=5012.9,5017.1
XS Rating Curve= 0 ,0
Exp/Cntr=0.3,0.1

Type RM Length L Ch R = 1 ,20055   ,462,462,462
BEGIN DESCRIPTION:
Stream0552 41.0
END DESCRIPTION:
XS GIS Cut Line= 3
        2355125.     13682175.01        2355475.       13681525.
        2355225.       13680725.
#Sta/Elev= 30
  4257.5  425.47  4293.2  425.12    4401   421.5  4429.3  420.83  4552.8  418.59
  4642.9  415.68  4648.5  416.26  4728.9  413.37  4834.3  411.06  4878.1  411.42
  4893.5  409.78    4900  409.77  4905.7  411.17  4916.2  410.46  4960.1  411.75
  5006.2  410.22  5015.1  408.62  5015.4  408.12  5019.4  408.62  5027.2   410.2
  5037.7  410.22  5044.5  409.12  5069.1   410.9    5182  412.21  5236.7  412.67
  5514.9  419.78  5687.7  422.74  5729.1  423.91    5792  427.27  5833.9  427.84
#Mann= 7 ,-1 , 0
  4257.5     .07       0    4401    .035       0  4429.3     .07       0
  4728.9     .12       0  5015.1     .05       0  5019.4     .12       0
    5182     .07       0
Bank Sta=5015.1,5019.4
XS Rating Curve= 0 ,0
Exp/Cntr=0.3,0.1

Type RM Length L Ch R = 1 ,19593   ,858,858,858
BEGIN DESCRIPTION:
Stream0552 40.0
END DESCRIPTION:
XS GIS Cut Line= 3
      2355174.98     13682725.03        2355875.       13681525.
      2355374.99     13680724.99
#Sta/Elev= 30
  3605.3   431.2  3714.9  428.76  3744.3  429.15  3855.4  425.49  4017.4  423.18
  4200.7  421.36  4242.1  421.61  4393.8  419.35  4588.4  414.69  4671.7  411.73
  4681.6  412.22  4687.4  410.99  4703.1  411.58  4708.9  410.36  4783.3  409.28
  4936.7  409.89  4943.7   408.6  4949.5  409.18    4963  407.59  4963.3  407.09
  4967.4  407.59  4971.4  409.51  5075.4  408.03  5169.7  409.44  5218.6  408.88
  5300.6  409.73  5484.5  413.36  5681.2  418.96  5843.6  423.95    5938  425.61
#Mann= 10 ,-1 , 0
  3605.3    .035       0  3855.4     .07       0  4017.4    .035       0
  4200.7     .07       0  4588.4     .12       0    4963     .05       0
  4967.4     .12       0  5169.7     .07       0  5484.5    .035       0
  5681.2     .07       0
Bank Sta=4963,4967.4
XS Rating Curve= 0 ,0
Exp/Cntr=0.3,0.1

Type RM Length L Ch R = 1 ,18735   ,472,472,472
BEGIN DESCRIPTION:
Stream0552 39.0
END DESCRIPTION:
XS GIS Cut Line= 3
      2355775.01     13682324.98        2356475.       13681225.
        2356575.       13680225.
#Sta/Elev= 30
  3681.8  422.12  3867.2  418.77  3898.9  418.01  4320.1  409.82  4508.1  408.12
  4623.3  407.89  4653.7  406.86  4689.3  408.16  4711.3  406.88  4732.5  407.74
    4796  406.61  4819.7  407.17  4890.8  406.07  4899.3  405.18  4905.2  405.76
  4914.5  405.18  4940.6  405.65  4947.8  405.07  4948.1  404.57  4952.3  405.07
    4978  405.72    5056  405.49  5086.1  406.65  5226.8     406  5297.2  410.33
  5417.8  411.09  5548.4  414.36  5789.6  417.01  5950.4  421.43  5990.6  421.72
#Mann= 6 ,-1 , 0
  3681.8     .12       0  3867.2     .07       0  3898.9     .12       0
  4940.6     .07       0  4947.8     .05       0  4952.3     .07       0
Bank Sta=4947.8,4952.3
XS Rating Curve= 0 ,0
Exp/Cntr=0.3,0.1

Type RM Length L Ch R = 1 ,18263   ,474,474,474
BEGIN DESCRIPTION:
Stream0552 38.0
END DESCRIPTION:
XS GIS Cut Line= 3
      2356275.01     13681874.99        2356925.       13681275.
      2357175.01     13680974.99
#Sta/Elev= 30
  4115.3  412.28  4242.6   409.7    4250  410.35  4363.6   408.7  4448.8  407.32
  4936.1  403.73  4957.6  404.27  4971.8  402.34  4976.3   400.4  4976.7   399.9
  4980.9   400.4  4996.5  402.05    5050  403.46  5056.5  402.34  5064.3  403.66
  5091.6  403.16  5113.8  404.17  5156.1  402.44  5188.9  402.81  5241.3  403.44
  5247.8  401.91  5255.7   403.2  5262.2  401.59    5270  402.65  5276.5  401.14
  5284.3  401.97  5290.8  404.96  5298.6  406.49  5348.1  412.89  5390.4  413.89
#Mann= 6 ,-1 , 0
  4115.3     .07       0  4363.6     .12       0  4448.8     .07       0
  4976.3     .05       0  4980.9     .07       0  5188.9     .12       0
Bank Sta=4976.3,4980.9
XS Rating Curve= 0 ,0
Exp/Cntr=0.3,0.1

Type RM Length L Ch R = 1 ,17789   ,479,479,479
BEGIN DESCRIPTION:
Stream0552 37.0
END DESCRIPTION:
XS GIS Cut Line= 3
      2356474.97     13682225.03        2357275.       13681525.
        2357225.     13680975.03
#Sta/Elev= 30
    3937  412.66  4142.5  409.71    4171  410.65  4383.6  408.26  4426.3  406.91
  4567.7  406.19    4582  405.06  4681.2  403.58  4950.2  401.67  4957.8   400.9
  4964.5  401.32  4972.1  399.09  4978.3   398.3  4990.4  397.37  4990.8  396.87
  4995.4  397.37  5002.6  397.95  5010.1  400.18  5020.1  401.52  5040.2  402.45
  5060.3  402.33  5090.4  400.18  5130.6  401.76  5228.2  401.96  5261.1  402.55
  5271.2  403.45  5281.2  402.61  5366.5   407.3    5472  411.69  5552.3  413.71
#Mann= 6 ,-1 , 0
    3937     .07       0  4978.3     .12       0  4990.4     .05       0
  4995.4     .12       0  5228.2     .07       0  5366.5     .12       0
Bank Sta=4990.4,4995.4
XS Rating Curve= 0 ,0
Exp/Cntr=0.3,0.1

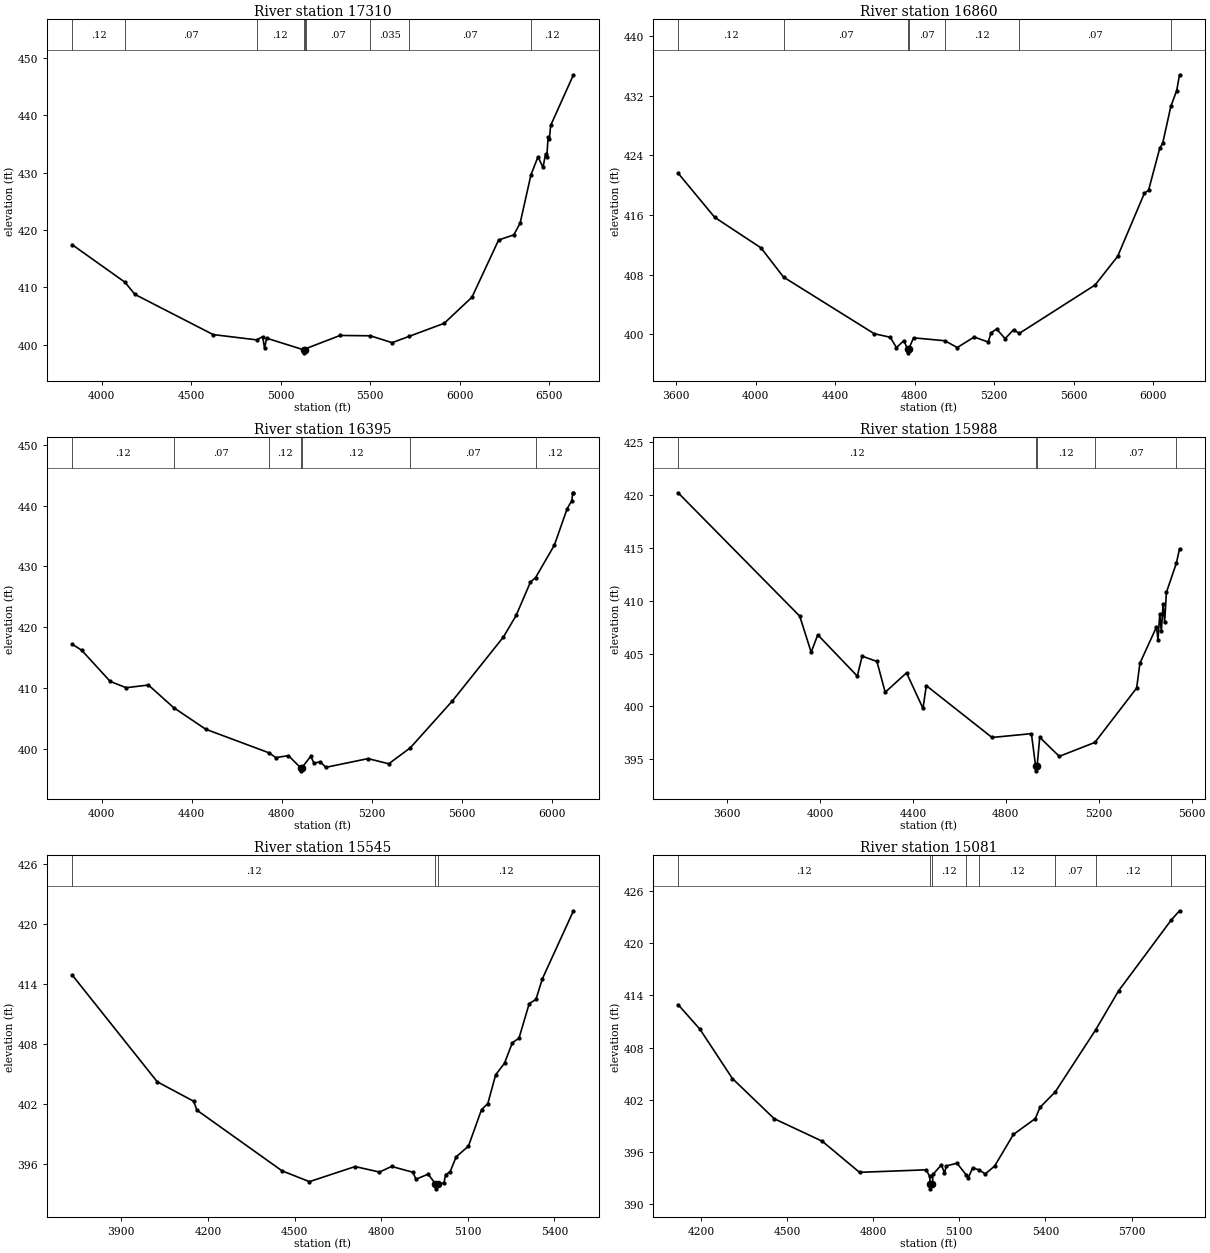
Type RM Length L Ch R = 1 ,17310   ,450,450,450
BEGIN DESCRIPTION:
Stream0552 36.0
END DESCRIPTION:
XS GIS Cut Line= 3
      2357325.01     13682624.98        2357725.       13681525.
      2358924.97     13680425.02
#Sta/Elev= 30
  3835.5  417.44  4130.1   410.9  4186.6  408.76  4622.9  401.76  4865.6  400.84
  4898.9  401.39  4910.2  399.36  4920.8  401.14  5130.8  399.08  5131.1  398.58
  5135.8  399.08  5140.6  399.32  5331.5  401.61  5500.4  401.55  5621.7  400.35
  5718.1  401.47  5912.1  403.72  6067.5  408.28  6216.1  418.24  6301.2  419.14
  6336.3   421.2  6396.6   429.6  6435.6  432.72    6464   430.9  6478.1  433.22
  6484.9  432.62  6492.3  436.21  6499.1  435.79  6506.5   438.2  6633.8  447.03
#Mann= 9 ,-1 , 0
  3835.5     .12       0  4130.1     .07       0  4865.6     .12       0
  5130.8     .05       0  5135.8     .12       0  5140.6     .07       0
  5500.4    .035       0  5718.1     .07       0  6396.6     .12       0
Bank Sta=5130.8,5135.8
XS Rating Curve= 0 ,0
Exp/Cntr=0.3,0.1

Type RM Length L Ch R = 1 ,16860   ,465,465,465
BEGIN DESCRIPTION:
Stream0552 35.0
END DESCRIPTION:
XS GIS Cut Line= 3
      2357424.99     13682775.02        2358125.       13681575.
      2358924.97     13680775.03
#Sta/Elev= 30
  3610.6  421.61  3794.6  415.69  4027.4   411.6  4140.6  407.69  4596.7   400.1
    4677  399.63  4708.4  398.24  4745.2  399.17  4764.6  398.04  4764.9  397.54
  4769.6  398.04  4794.4  399.55  4951.6  399.16    5014  398.25  5098.9  399.66
  5169.6  398.99  5183.7  400.23    5212  400.73  5254.4  399.44  5296.9  400.62
    5326  400.15    5707  406.63  5820.1  410.46  5954.5  418.91  5975.7  419.33
  6032.2  424.99  6046.4  425.59  6087.7  430.57  6117.1  432.67  6131.2  434.79
#Mann= 7 ,-1 , 0
  3610.6     .12       0  4140.6     .07       0  4764.6     .05       0
  4769.6     .07       0  4951.6     .12       0    5326     .07       0
  6087.7     .12       0
Bank Sta=4764.6,4769.6
XS Rating Curve= 0 ,0
Exp/Cntr=0.3,0.1

Type RM Length L Ch R = 1 ,16395   ,407,407,407
BEGIN DESCRIPTION:
Stream0552 34.0
END DESCRIPTION:
XS GIS Cut Line= 3
      2357625.03     13682674.97        2358425.       13681875.
      2359224.99     13681125.01
#Sta/Elev= 30
  3868.5  417.23  3910.9  416.24  4038.2   411.1  4108.9  410.07  4207.9  410.51
  4319.5  406.81  4462.4  403.25    4745  399.35  4773.6  398.58  4830.1  398.91
  4884.2  396.91  4884.5  396.41  4889.2  396.91  4929.1  398.79  4943.3  397.68
  4971.5  397.89  4996.3  396.99  5183.7  398.42  5275.6  397.57  5371.4  400.19
  5558.9  407.92    5785  418.39  5841.7  421.95  5905.2  427.42  5928.3  428.17
  6011.7  433.51  6068.3  439.48  6089.3  440.83    6093   442.1  6096.4   442.1
#Mann= 7 ,-1 , 0
  3868.5     .12       0  4319.5     .07       0    4745     .12       0
  4884.2     .05       0  4889.2     .12       0  5371.4     .07       0
  5928.3     .12       0
Bank Sta=4884.2,4889.2
XS Rating Curve= 0 ,0
Exp/Cntr=0.3,0.1

Type RM Length L Ch R = 1 ,15988   ,443,443,443
BEGIN DESCRIPTION:
Stream0552 33.0
END DESCRIPTION:
XS GIS Cut Line= 3
      2357675.02     13683174.98        2358775.       13681975.
      2359125.02     13681574.97
#Sta/Elev= 30
  3388.4  420.23  3912.2  408.55  3961.5  405.13  3989.9  406.78  4160.1  402.87
    4181  404.76  4244.6  404.26  4280.3  401.34  4372.2  403.18  4443.1  399.81
  4457.3  401.97  4740.3  397.06  4909.9  397.42  4927.9   394.4  4928.4   393.9
    4935   394.4  4945.7  397.08    5030  395.27  5183.3  396.59  5363.2  401.74
  5377.4   404.1  5448.6  407.52  5455.2  406.29  5462.8  408.76  5469.5  407.11
  5477.1  409.67  5483.7  407.95  5491.3  410.79  5534.3  413.57  5547.8  414.91
#Mann= 5 ,-1 , 0
  3388.4     .12       0  4927.9     .05       0    4935     .12       0
  5183.3     .07       0  5534.3     .12       0
Bank Sta=4927.9,4935
XS Rating Curve= 0 ,0
Exp/Cntr=0.3,0.1

Type RM Length L Ch R = 1 ,15545   ,464,464,464
BEGIN DESCRIPTION:
Stream0552 32.0
END DESCRIPTION:
XS GIS Cut Line= 3
      2358724.98     13683225.05        2359125.       13682025.
      2359375.02     13681624.97
#Sta/Elev= 30
  3729.4  414.89  4024.6  404.18  4151.1  402.23  4161.6  401.35  4456.8  395.27
  4551.6  394.19  4709.8   395.7  4794.1  395.15  4836.2  395.71    4910  395.13
  4920.6  394.43  4962.7  394.94  4988.1  393.97  4988.6  393.47  4995.3  393.97
  5017.4  394.04  5023.3   394.9  5038.6  395.16  5059.8  396.67  5102.3  397.74
  5147.7   401.4  5169.5  402.01  5196.6  404.88  5227.3  406.05  5254.4  408.09
  5277.4  408.55  5312.8     412  5336.3  412.44  5358.2  414.48  5466.1   421.3
#Mann= 3 ,-1 , 0
  3729.4     .12       0  4988.1     .05       0  4995.3     .12       0
Bank Sta=4988.1,4995.3
XS Rating Curve= 0 ,0
Exp/Cntr=0.3,0.1

Type RM Length L Ch R = 1 ,15081   ,456,456,456
BEGIN DESCRIPTION:
Stream0552 31.0
END DESCRIPTION:
XS GIS Cut Line= 3
      2358874.98     13683225.04        2359225.       13682425.
      2359575.01     13681624.97
#Sta/Elev= 30
  4120.6  412.94    4197  410.09  4309.7  404.43  4455.5   399.8  4622.7  397.21
  4752.5  393.63  4984.9  393.92  4996.6  393.17  4999.2  392.23  4999.7  391.73
  5006.4  392.23  5008.3  393.39  5037.5  394.48  5048.4  393.57  5055.1  394.37
  5092.1  394.68  5123.7  393.35  5130.7  392.95  5146.7  394.14  5169.8   393.9
  5190.3  393.44  5223.1  394.35  5288.6  397.99    5365  399.82  5380.9   401.1
  5434.3  402.89  5574.6  410.01  5654.6  414.51  5837.9  422.66  5867.1  423.74
#Mann= 8 ,-1 , 0
  4120.6     .12       0  4999.2     .05       0  5006.4     .12       0
  5123.7     .07       0  5169.8     .12       0  5434.3     .07       0
  5574.6     .12       0  5837.9     .07       0
Bank Sta=4999.2,5006.4
XS Rating Curve= 0 ,0
Exp/Cntr=0.3,0.1

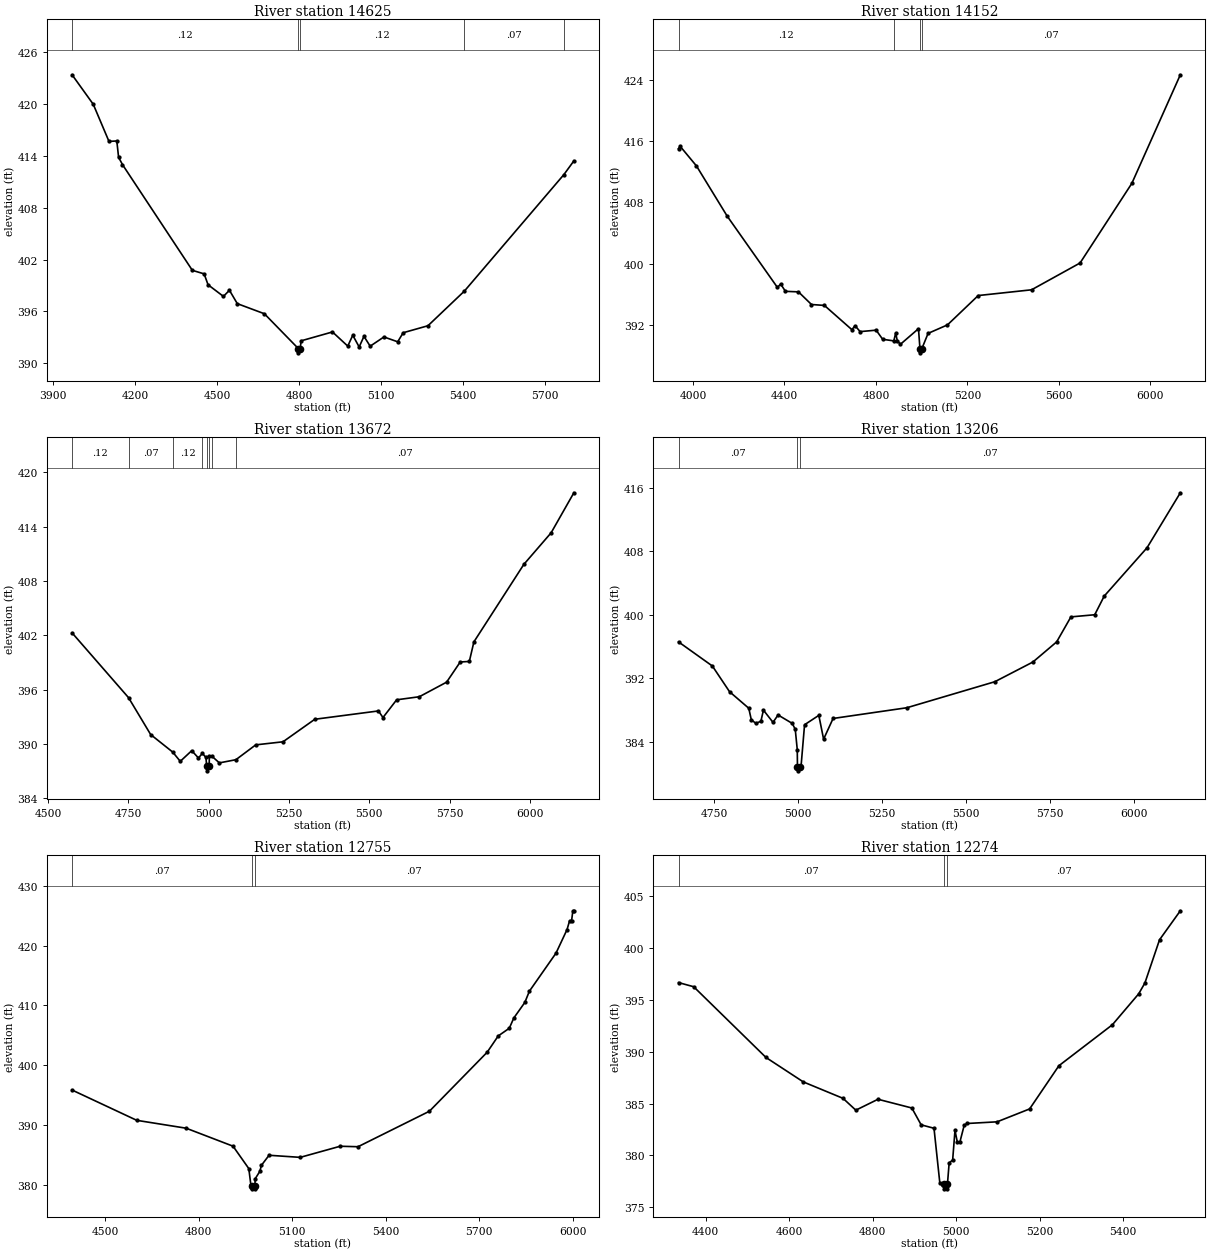
Type RM Length L Ch R = 1 ,14625   ,473,473,473
BEGIN DESCRIPTION:
Stream0552 30.0
END DESCRIPTION:
XS GIS Cut Line= 3
      2358874.98     13683475.03        2359525.       13682675.
        2359625.     13681875.04
#Sta/Elev= 30
  3969.4  423.41    4047  419.99  4104.5  415.69  4133.2  415.74  4139.7  413.85
    4154     413  4409.7  400.75  4452.9  400.34  4467.2  399.08  4523.5  397.73
  4545.5  398.44  4574.3  396.89  4673.4  395.72  4797.6  391.69  4798.1  391.19
  4804.8  391.69  4807.7  392.58  4922.7  393.61  4978.7  391.97    4997  393.23
  5020.4  391.87    5038   393.1  5060.7  391.96  5111.1  393.03  5161.5  392.47
  5181.6  393.52  5272.3  394.33  5405.8  398.35  5769.8  411.84  5806.4  413.43
#Mann= 5 ,-1 , 0
  3969.4     .12       0  4797.6     .05       0  4804.8     .12       0
  5405.8     .07       0  5769.8     .12       0
Bank Sta=4797.6,4804.8
XS Rating Curve= 0 ,0
Exp/Cntr=0.3,0.1

Type RM Length L Ch R = 1 ,14152   ,480,480,480
BEGIN DESCRIPTION:
Stream0552 29.0
END DESCRIPTION:
XS GIS Cut Line= 3
      2359124.96     13683575.03        2359925.       13682875.
      2360724.98     13682075.02
#Sta/Elev= 30
  3936.9  415.02  3944.1  415.32  4015.3  412.76  4149.6  406.21  4369.3   396.9
  4383.5  397.34  4404.4  396.39  4461.3  396.32  4518.3  394.67  4574.8  394.55
  4694.8  391.39  4709.1   391.9  4730.9  391.13  4801.1  391.32  4829.6  390.13
  4878.3  389.92  4886.5  390.94  4893.7  389.92  4907.4  389.48  4986.2  391.51
  4992.8  388.86  4993.3  388.36  5000.4  388.86  5028.2   390.9  5113.1  392.01
  5247.5  395.84  5480.8  396.59  5692.9  400.09  5919.2  410.48  6131.3  424.66
#Mann= 4 ,-1 , 0
  3936.9     .12       0  4878.3     .07       0  4992.8     .05       0
  5000.4     .07       0
Bank Sta=4992.8,5000.4
XS Rating Curve= 0 ,0
Exp/Cntr=0.3,0.1

Type RM Length L Ch R = 1 ,13672   ,466,466,466
BEGIN DESCRIPTION:
Stream0552 28.0
END DESCRIPTION:
XS GIS Cut Line= 3
      2359924.99     13683575.01        2360175.       13683225.
        2360975.       13682425.
#Sta/Elev= 30
  4575.2  402.27  4750.9  395.11  4819.8  391.03  4888.5  389.09  4911.9  388.07
  4947.6  389.25  4968.5  388.44  4980.7  388.95  4991.8   388.5  4994.1  387.52
  4994.6  387.02  5001.9  387.52  5002.3  388.64  5010.2  388.64  5033.6   387.9
    5085  388.25  5146.7  389.89  5231.6  390.23  5330.6  392.72  5528.6  393.64
  5542.7  392.91  5585.2  394.87  5655.9  395.21  5740.7  396.82  5783.1  399.05
  5811.4  399.11  5825.6  401.27  5981.1  409.84    6066  413.33  6136.7  417.75
#Mann= 8 ,-1 , 0
  4575.2     .12       0  4750.9     .07       0  4888.5     .12       0
  4980.7     .07       0  4994.1     .05       0  5001.9     .07       0
  5010.2     .12       0    5085     .07       0
Bank Sta=4994.1,5001.9
XS Rating Curve= 0 ,0
Exp/Cntr=0.3,0.1

Type RM Length L Ch R = 1 ,13206   ,451,451,451
BEGIN DESCRIPTION:
Stream0552 27.0
END DESCRIPTION:
XS GIS Cut Line= 3
      2360175.01       13683725.        2360475.       13683525.
      2361274.99     13682725.01
#Sta/Elev= 30
  4644.7  396.57  4745.3  393.53  4796.4  390.29  4853.5  388.21    4861  386.77
  4874.5   386.3  4889.6  386.57  4897.1  387.97  4925.6  386.43  4940.6  387.36
  4982.7   386.3  4991.7  385.56  4997.7  382.99  4998.3  380.82  4998.8  380.32
  5006.2  380.82  5008.8  380.82  5019.4  386.13  5061.8  387.31    5076  384.31
  5104.2  386.92  5323.4  388.27  5585.1  391.55  5698.2  394.03  5768.9  396.57
  5811.3  399.72  5882.1  399.99  5910.3  402.34  6037.6  408.43  6136.6  415.36
#Mann= 3 ,-1 , 0
  4644.7     .07       0  4998.3     .05       0  5006.2     .07       0
Bank Sta=4998.3,5006.2
XS Rating Curve= 0 ,0
Exp/Cntr=0.3,0.1

Type RM Length L Ch R = 1 ,12755   ,481,481,481
BEGIN DESCRIPTION:
Stream0552 26.0
END DESCRIPTION:
XS GIS Cut Line= 3
      2360474.97     13684225.04        2360825.       13683725.
      2361625.02     13683124.98
#Sta/Elev= 30
  4393.7  395.83  4601.3  390.76  4759.9  389.44  4910.3  386.43  4960.9  382.68
  4967.5  379.95  4971.5  379.79    4972  379.29  4979.5  379.29    4980  379.79
  4981.8  381.01  4996.7  382.25    5001   383.2  5025.9  384.91  5125.9  384.56
  5254.1  386.42  5311.4  386.34  5540.5  392.28  5725.9  402.16  5761.4  404.89
  5796.8  406.17  5811.4  407.89  5846.8   410.5  5861.4  412.38  5946.8  418.75
  5982.2  422.69  5990.5  424.19  5996.8  424.17  6000.9  425.84  6004.1  425.84
#Mann= 3 ,-1 , 0
  4393.7     .07       0  4971.5     .05       0    4980     .07       0
Bank Sta=4971.5,4980
XS Rating Curve= 0 ,0
Exp/Cntr=0.3,0.1

Type RM Length L Ch R = 1 ,12274   ,414,414,414
BEGIN DESCRIPTION:
Stream0552 25.0
END DESCRIPTION:
XS GIS Cut Line= 3
      2360925.01     13684524.97        2361225.       13683925.
        2361575.       13683525.
#Sta/Elev= 30
  4335.1  396.64  4371.4  396.24  4544.7  389.43  4634.1  387.08  4729.2   385.5
  4759.9  384.36    4813  385.41  4894.1  384.57  4916.4  382.95  4947.2  382.62
  4961.2  377.34  4970.8  377.29  4971.3  376.79    4979  376.79  4979.5  377.29
  4983.5  379.28  4991.9  379.57  4997.5  382.41  5003.1  381.29  5009.2  381.29
  5019.7  382.93  5027.2  383.08  5098.4  383.24  5176.3  384.48  5246.5  388.64
  5374.6  392.58  5437.7  395.56  5452.5   396.6  5487.6  400.76  5537.4  403.55
#Mann= 3 ,-1 , 0
  4335.1     .07       0  4970.8     .05       0  4979.5     .07       0
Bank Sta=4970.8,4979.5
XS Rating Curve= 0 ,0
Exp/Cntr=0.3,0.1

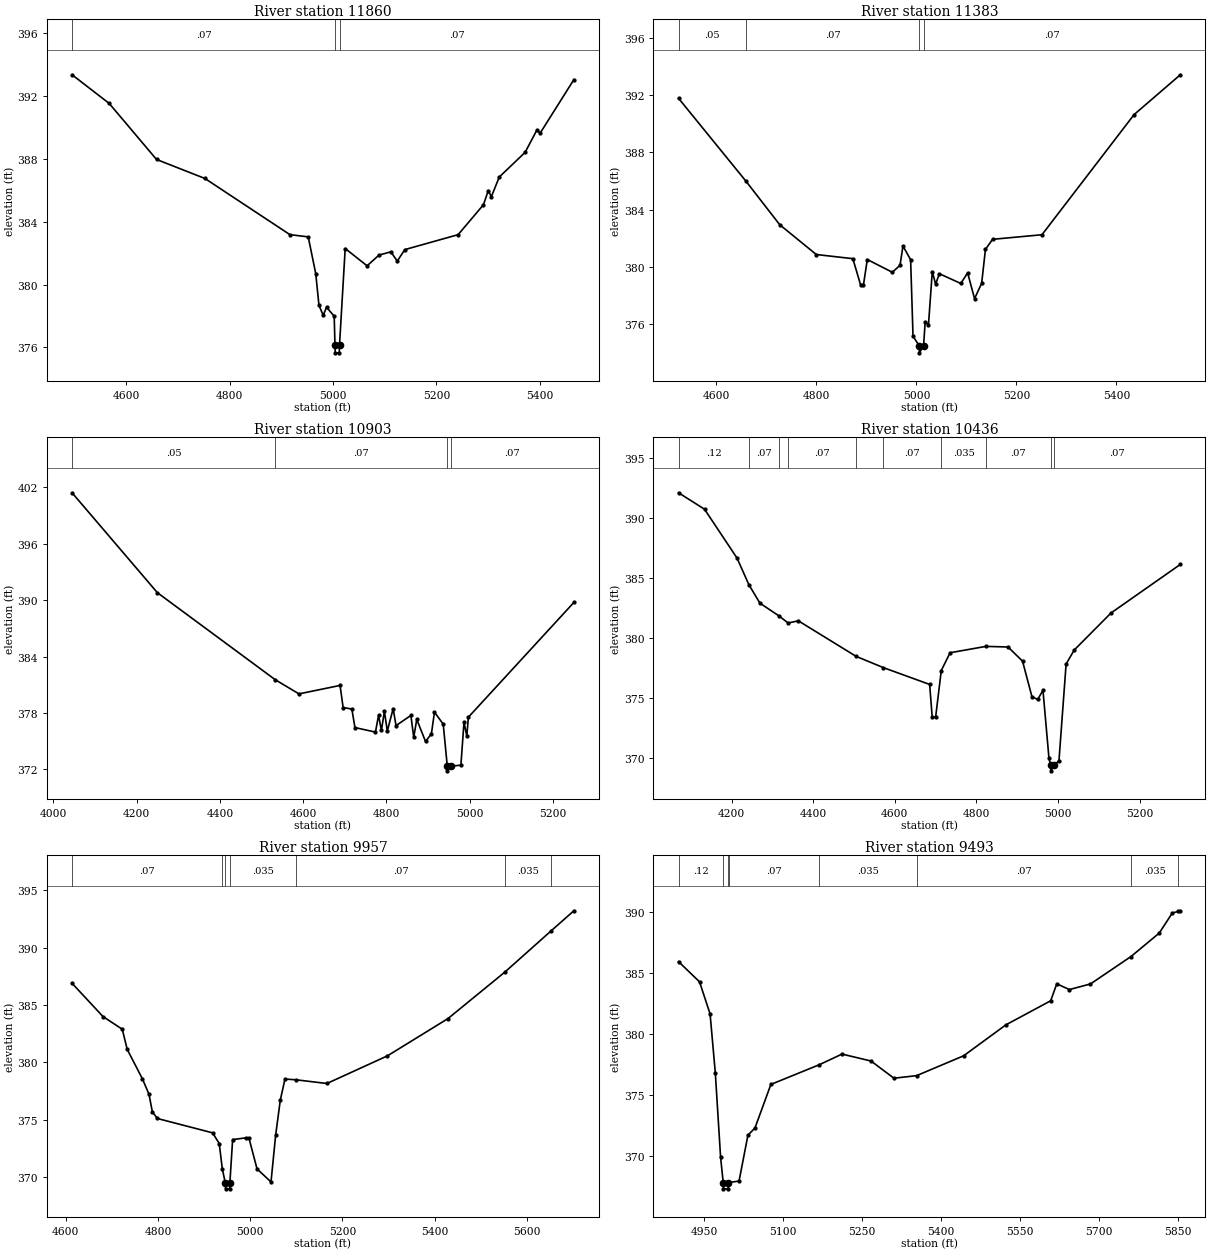
Type RM Length L Ch R = 1 ,11860   ,477,477,477
BEGIN DESCRIPTION:
Stream0552 24.0
END DESCRIPTION:
XS GIS Cut Line= 3
      2361075.02     13684524.99        2361475.       13684225.
      2361725.01     13683824.98
#Sta/Elev= 30
  4494.6  393.33  4566.5  391.51  4658.1  387.95  4751.9  386.74  4916.5  383.17
  4951.9  383.03  4966.5  380.69  4972.7  378.68    4981  378.04  4987.3  378.56
  5002.2  377.99  5003.7  376.16  5004.2  375.66    5012  375.66  5012.5  376.16
  5023.5  382.29  5065.9  381.19  5088.9  381.87  5111.9  382.08  5124.3  381.49
    5139  382.22  5242.2  383.17  5291.2  385.07  5300.6  385.97  5306.5  385.58
  5321.8  386.83  5371.9   388.4  5394.9  389.83  5400.8  389.61  5466.3  393.02
#Mann= 3 ,-1 , 0
  4494.6     .07       0  5003.7     .05       0  5012.5     .07       0
Bank Sta=5003.7,5012.5
XS Rating Curve= 0 ,0
Exp/Cntr=0.3,0.1

Type RM Length L Ch R = 1 ,11383   ,480,480,480
BEGIN DESCRIPTION:
Stream0552 23.0
END DESCRIPTION:
XS GIS Cut Line= 3
      2361624.99     13684825.01        2361875.       13684425.
      2362224.99     13684025.02
#Sta/Elev= 30
  4524.5  391.77  4659.2  385.99  4726.8  382.95  4799.9  380.87    4873  380.58
  4888.3  378.77  4894.2  378.75  4901.9  380.52    4952  379.63  4967.3  380.12
  4973.2  381.46  4988.5  380.51  4993.3  375.17  5005.6  374.51  5006.1  374.01
  5014.4  374.51  5017.6  376.17  5024.2  375.97  5031.8  379.68  5038.5   378.8
    5046  379.53  5088.8  378.85  5102.5  379.59  5116.3  377.79  5130.5  378.86
  5138.1  381.23  5152.3  381.93  5251.1  382.25  5435.2  390.63  5527.7  393.41
#Mann= 4 ,-1 , 0
  4524.5     .05       0  4659.2     .07       0  5005.6     .05       0
  5014.4     .07       0
Bank Sta=5005.6,5014.4
XS Rating Curve= 0 ,0
Exp/Cntr=0.3,0.1

Type RM Length L Ch R = 1 ,10903   ,467,467,467
BEGIN DESCRIPTION:
Stream0552 22.0
END DESCRIPTION:
XS GIS Cut Line= 3
      2361675.03     13685124.97        2362325.       13684425.
        2362325.       13684175.
#Sta/Elev= 30
  4044.9  401.41  4249.8  390.79  4532.8  381.54  4589.9  380.03  4688.6  380.93
  4695.9  378.58  4716.9  378.42  4724.3  376.45  4773.6  375.97    4781  377.76
  4787.8  376.14  4795.1  378.17    4802  376.08  4816.1  378.46    4823  376.66
  4858.7  377.74  4865.5  375.41  4872.8  377.32  4893.8  374.97    4908  375.79
  4915.3  378.09  4936.3  376.82  4946.1  372.35  4946.6  371.85    4955  372.35
  4978.8  372.45  4986.2  377.02    4993  375.54  4996.7  377.55  5250.1  389.75
#Mann= 4 ,-1 , 0
  4044.9     .05       0  4532.8     .07       0  4946.1     .05       0
    4955     .07       0
Bank Sta=4946.1,4955
XS Rating Curve= 0 ,0
Exp/Cntr=0.3,0.1

Type RM Length L Ch R = 1 ,10436   ,479,479,479
BEGIN DESCRIPTION:
Stream0552 21.0
END DESCRIPTION:
XS GIS Cut Line= 3
      2363325.02     13685125.02        2362775.       13684375.
        2362775.     13684074.98
#Sta/Elev= 30
  4069.9  392.12  4133.6  390.75  4213.1  386.69  4242.5  384.45  4269.5  382.92
  4315.2  381.88  4338.6  381.27  4363.6  381.45  4505.2  378.49  4572.1  377.55
  4685.5  376.15  4691.7  373.44  4700.1  373.41    4714  377.31  4735.6  378.79
  4823.3  379.32  4877.7  379.27  4913.2  378.09  4936.3  375.12  4950.4   374.9
  4963.3  375.66    4978  369.99    4982  369.45  4982.5  368.95  4990.9  369.45
  5002.5  369.79    5020  377.85    5040  379.02    5130   382.1    5300  386.15
#Mann= 10 ,-1 , 0
  4069.9     .12       0  4242.5     .07       0  4315.2     .12       0
  4338.6     .07       0  4505.2    .035       0  4572.1     .07       0
    4714    .035       0  4823.3     .07       0    4982     .05       0
  4990.9     .07       0
Bank Sta=4982,4990.9
XS Rating Curve= 0 ,0
Exp/Cntr=0.3,0.1

Type RM Length L Ch R = 1 ,9957    ,464,464,464
BEGIN DESCRIPTION:
Stream0552 20.0
END DESCRIPTION:
XS GIS Cut Line= 3
      2363374.99     13684824.97        2363225.       13684475.
        2363125.     13683774.97
#Sta/Elev= 30
  4613.8  386.88  4680.9  383.98  4722.6  382.88  4733.4  381.12  4766.1  378.57
  4780.6  377.21  4787.8  375.69  4798.7   375.1  4918.4  373.85  4932.9  372.92
  4939.4  370.74  4946.1  369.47  4946.6  368.97  4955.4  368.97  4955.9  369.47
  4961.9  373.26  4991.8  373.42  4997.1  373.42  5014.8  370.71  5045.1  369.57
  5055.2  373.66  5065.3  376.71  5075.4  378.54  5099.5  378.47  5166.3  378.15
  5297.6  380.56  5428.9  383.81  5552.2  387.86  5652.1  391.44  5701.7   393.2
#Mann= 7 ,-1 , 0
  4613.8     .07       0  4939.4    .035       0  4946.1    .035       0
  4955.9    .035       0  5099.5     .07       0  5552.2    .035       0
  5652.1     .07       0
Bank Sta=4946.1,4955.9
XS Rating Curve= 0 ,0
Exp/Cntr=0.3,0.1

Type RM Length L Ch R = 1 ,9493    ,440,440,440
BEGIN DESCRIPTION:
Stream0552 19.0
END DESCRIPTION:
XS GIS Cut Line= 3
        2363575.     13684724.96        2363575.       13684625.
      2363274.99     13683824.97
#Sta/Elev= 30
  4900.7  385.92  4940.7  384.26  4960.7  381.63  4970.7  376.77  4980.7  369.88
  4985.7  367.79  4986.2  367.29  4995.1  367.29  4995.6  367.79  4997.1  367.81
  5015.8  367.93  5032.7  371.69  5046.1  372.28  5076.3  375.85  5168.6  377.47
  5211.6  378.34  5266.8  377.77  5310.4  376.36  5353.5  376.57    5443   378.2
  5523.1  380.73  5608.5  382.71  5620.1   384.1  5644.1  383.63  5684.2  384.09
  5761.3  386.34    5815  388.26  5839.9  389.91  5851.6  390.04  5855.1  390.09
#Mann= 8 ,-1 , 0
  4900.7     .12       0  4985.7     .05       0  4995.6     .12       0
  4997.1     .07       0  5168.6    .035       0  5353.5     .07       0
  5761.3    .035       0  5851.6     .07       0
Bank Sta=4985.7,4995.6
XS Rating Curve= 0 ,0
Exp/Cntr=0.3,0.1

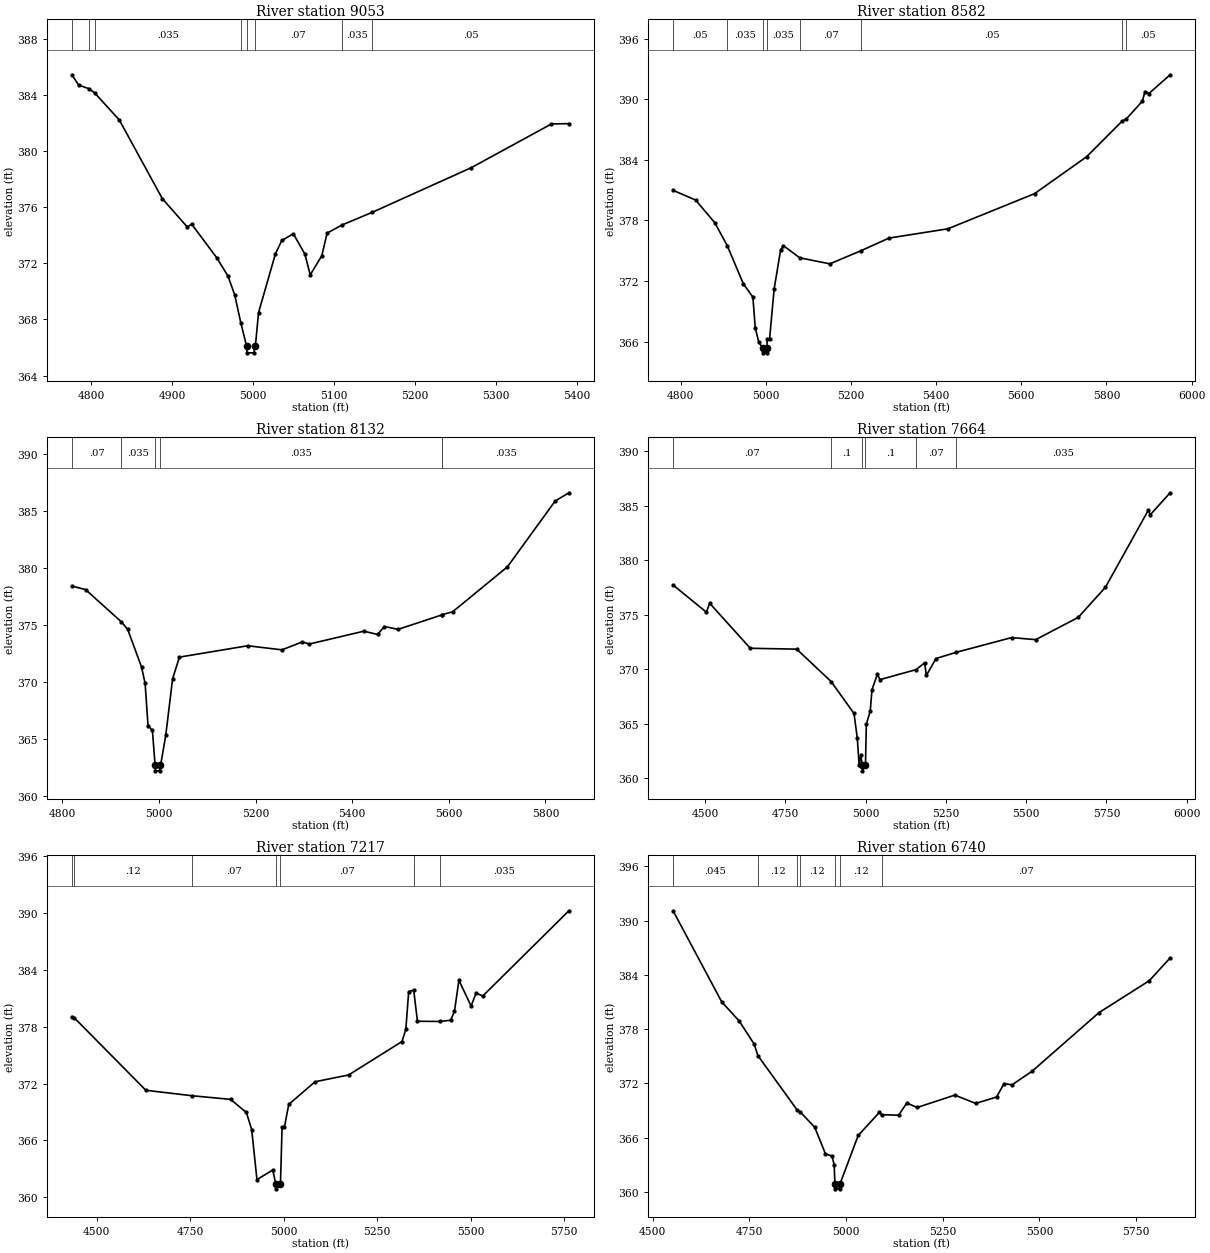
Type RM Length L Ch R = 1 ,9053    ,471,471,471
BEGIN DESCRIPTION:
Stream0552 18.0
END DESCRIPTION:
XS GIS Cut Line= 3
      2363974.99     13684524.98        2363875.       13684325.
        2363575.       13684075.
#Sta/Elev= 30
  4776.4  385.42  4784.8  384.69  4797.4  384.43  4804.6  384.13  4835.1   382.2
  4888.2   376.6  4918.9  374.59  4924.5  374.78  4955.3   372.4  4969.2   371.1
  4977.6  369.75  4985.1  367.78  4992.2  366.12  4992.7  365.62  5001.6  365.62
  5002.1  366.12  5003.2  366.12  5007.1  368.49    5028  372.68  5035.8  373.62
  5050.1   374.1  5064.4  372.64  5070.9  371.17  5085.2  372.53  5091.8  374.15
  5110.5  374.73  5147.7  375.63  5270.1  378.81    5369  381.92  5390.5  381.94
#Mann= 8 ,-1 , 0
  4776.4    .035       0  4797.4     .07       0  4804.6    .035       0
  4985.1     .07       0  4992.2     .05       0  5002.1     .07       0
  5110.5    .035       0  5147.7     .05       0
Bank Sta=4992.2,5002.1
XS Rating Curve= 0 ,0
Exp/Cntr=0.3,0.1

Type RM Length L Ch R = 1 ,8582    ,450,450,450
BEGIN DESCRIPTION:
Stream0552 17.0
END DESCRIPTION:
XS GIS Cut Line= 3
      2364325.01     13684275.03        2364225.       13684075.
      2363425.03     13683575.02
#Sta/Elev= 30
  4782.5  380.97  4835.6     380  4880.4  377.76  4909.6   375.5  4947.4  371.72
  4969.8   370.4  4975.4  367.36  4983.8  365.91  4992.8  365.38  4993.3  364.88
  5002.3  364.88  5002.8  365.38  5003.3  366.28  5009.1  366.28  5019.7   371.2
    5035  375.07  5041.5  375.49  5079.8  374.29  5150.6  373.69  5224.7  375.01
  5289.2  376.24  5427.7  377.16  5631.1  380.64  5753.2  384.29    5837  387.83
  5845.8     388  5884.1  389.79  5890.6  390.75  5899.4  390.55  5949.5  392.41
#Mann= 8 ,-1 , 0
  4782.5     .05       0  4909.6    .035       0  4992.8    .035       0
  5002.8    .035       0  5079.8     .07       0  5224.7     .05       0
    5837    .035       0  5845.8     .05       0
Bank Sta=4992.8,5002.8
XS Rating Curve= 0 ,0
Exp/Cntr=0.3,0.1

Type RM Length L Ch R = 1 ,8132    ,468,468,468
BEGIN DESCRIPTION:
Stream0552 16.0
END DESCRIPTION:
XS GIS Cut Line= 3
        2364625.       13683925.        2364525.       13683775.
        2363925.       13683175.
#Sta/Elev= 30
  4819.7  378.43  4848.2  378.11  4922.3  375.28  4935.4  374.61  4963.9  371.32
  4971.4  369.87  4977.4  366.16  4986.5  365.74    4992  362.69  4992.5  362.19
  5001.5  362.19    5002  362.69  5003.5  362.69  5014.1  365.31  5028.3  370.28
  5042.4  372.18  5183.8  373.18  5254.5  372.82    5297  373.52  5311.1  373.33
  5424.2  374.46  5452.5  374.17  5466.7  374.87    5495  374.62  5584.9  375.88
  5586.6  375.91  5608.1  376.17  5721.2  380.11  5820.2   385.9  5848.5  386.62
#Mann= 6 ,-1 , 0
  4819.7     .07       0  4922.3    .035       0    4992    .035       0
    5002    .035       0  5584.9     .07       0  5586.6    .035       0
Bank Sta=4992,5002
XS Rating Curve= 0 ,0
Exp/Cntr=0.3,0.1

Type RM Length L Ch R = 1 ,7664    ,447,447,447
BEGIN DESCRIPTION:
Stream0552 15.0
END DESCRIPTION:
XS GIS Cut Line= 3
      2364700.89     13684016.49        2364825.       13683425.
      2363943.91     13683086.91
#Sta/Elev= 30
  4400.3  377.71    4504  375.22  4514.2  376.04  4640.7  371.91  4785.3  371.83
  4892.4  368.86  4963.8  365.93    4974  363.66  4979.7   361.2  4984.8  362.16
  4989.4  361.17  4989.9  360.67  4999.5  361.17  5002.1  364.94  5014.3  366.14
  5019.7   368.1  5036.8  369.55  5044.3  369.03  5156.7  369.95  5183.8  370.57
  5189.1  369.42  5219.1  370.97  5282.2  371.54  5454.5  372.89  5529.5   372.7
    5662  374.74  5746.7   377.5  5880.8  384.59  5886.1  384.14  5948.4  386.17
#Mann= 6 ,-1 , 0
  4400.3     .07       0  4892.4      .1       0  4989.4     .05       0
  4999.5      .1       0  5156.7     .07       0  5282.2    .035       0
Bank Sta=4989.4,4999.5
XS Rating Curve= 0 ,0
Exp/Cntr=0.3,0.1

Type RM Length L Ch R = 1 ,7217    ,477,477,477
BEGIN DESCRIPTION:
Stream0552 14.0
END DESCRIPTION:
XS GIS Cut Line= 3
      2364724.98     13684075.02        2365125.       13683675.
      2365430.67     13682975.48
#Sta/Elev= 30
  4433.2  379.06  4439.8  378.94  4631.2  371.29  4755.4  370.71  4857.5  370.33
  4899.9  368.95  4914.1  367.14  4928.2  361.86  4970.6  362.87  4978.5  361.38
    4979  360.88    4991  361.38  4995.4  367.41  5001.6  367.41  5013.3   369.8
  5083.5  372.19  5173.5  372.91    5316  376.44  5326.3  377.72  5333.9  381.71
  5347.4  381.86  5357.3  378.58  5416.9  378.56  5446.3  378.69  5456.4  379.65
  5468.2  382.91  5500.9  380.18  5514.1  381.56    5532  381.25  5762.3  390.25
#Mann= 7 ,-1 , 0
  4433.2     .07       0  4439.8     .12       0  4755.4     .07       0
  4978.5     .05       0    4991     .07       0  5347.4    .033       0
  5416.9    .035       0
Bank Sta=4978.5,4991
XS Rating Curve= 0 ,0
Exp/Cntr=0.3,0.1

Type RM Length L Ch R = 1 ,6740    ,436,436,436
BEGIN DESCRIPTION:
Stream0552 13.0
END DESCRIPTION:
XS GIS Cut Line= 3
      2365124.98     13684475.03        2365325.       13684075.
        2365575.       13683275.
#Sta/Elev= 30
  4552.5  391.08  4678.3  381.01    4723  378.92  4762.2  376.35  4771.7  375.08
  4873.2  369.07  4880.3  368.89  4918.7  367.16  4946.6  364.21  4963.4  363.98
    4969  363.02  4971.1  360.85  4971.6  360.35  4983.2  360.35  4983.7  360.85
  5031.2  366.25  5086.2  368.81  5091.7  368.54  5135.9  368.49  5156.9  369.84
  5183.6  369.34  5281.1  370.71    5335  369.79    5389   370.5  5408.3  371.97
  5429.3  371.85  5481.2  373.36    5654  379.83  5783.9  383.35  5837.9  385.87
#Mann= 7 ,-1 , 0
  4552.5    .045       0  4771.7     .12       0  4873.2     .07       0
  4880.3     .12       0  4971.1     .05       0  4983.7     .12       0
  5091.7     .07       0
Bank Sta=4971.1,4983.7
XS Rating Curve= 0 ,0
Exp/Cntr=0.3,0.1