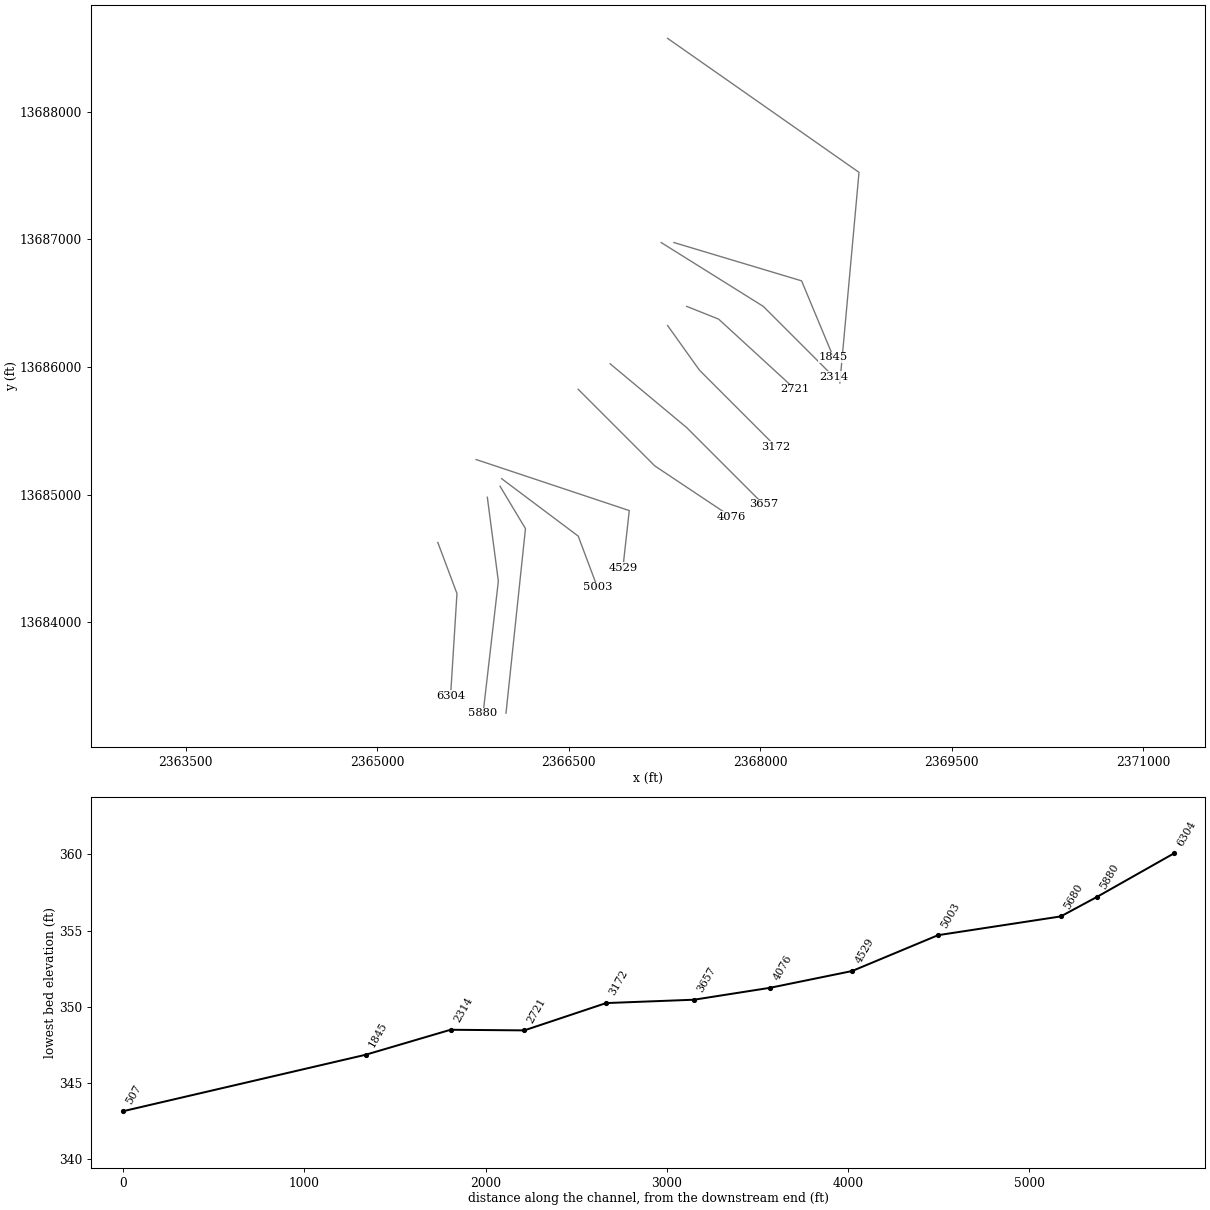
HEC-RAS study Stream0552.prj: Stream0552 Base Level Engineering

--- Stream0552.g01 (geometry) --- (continued)

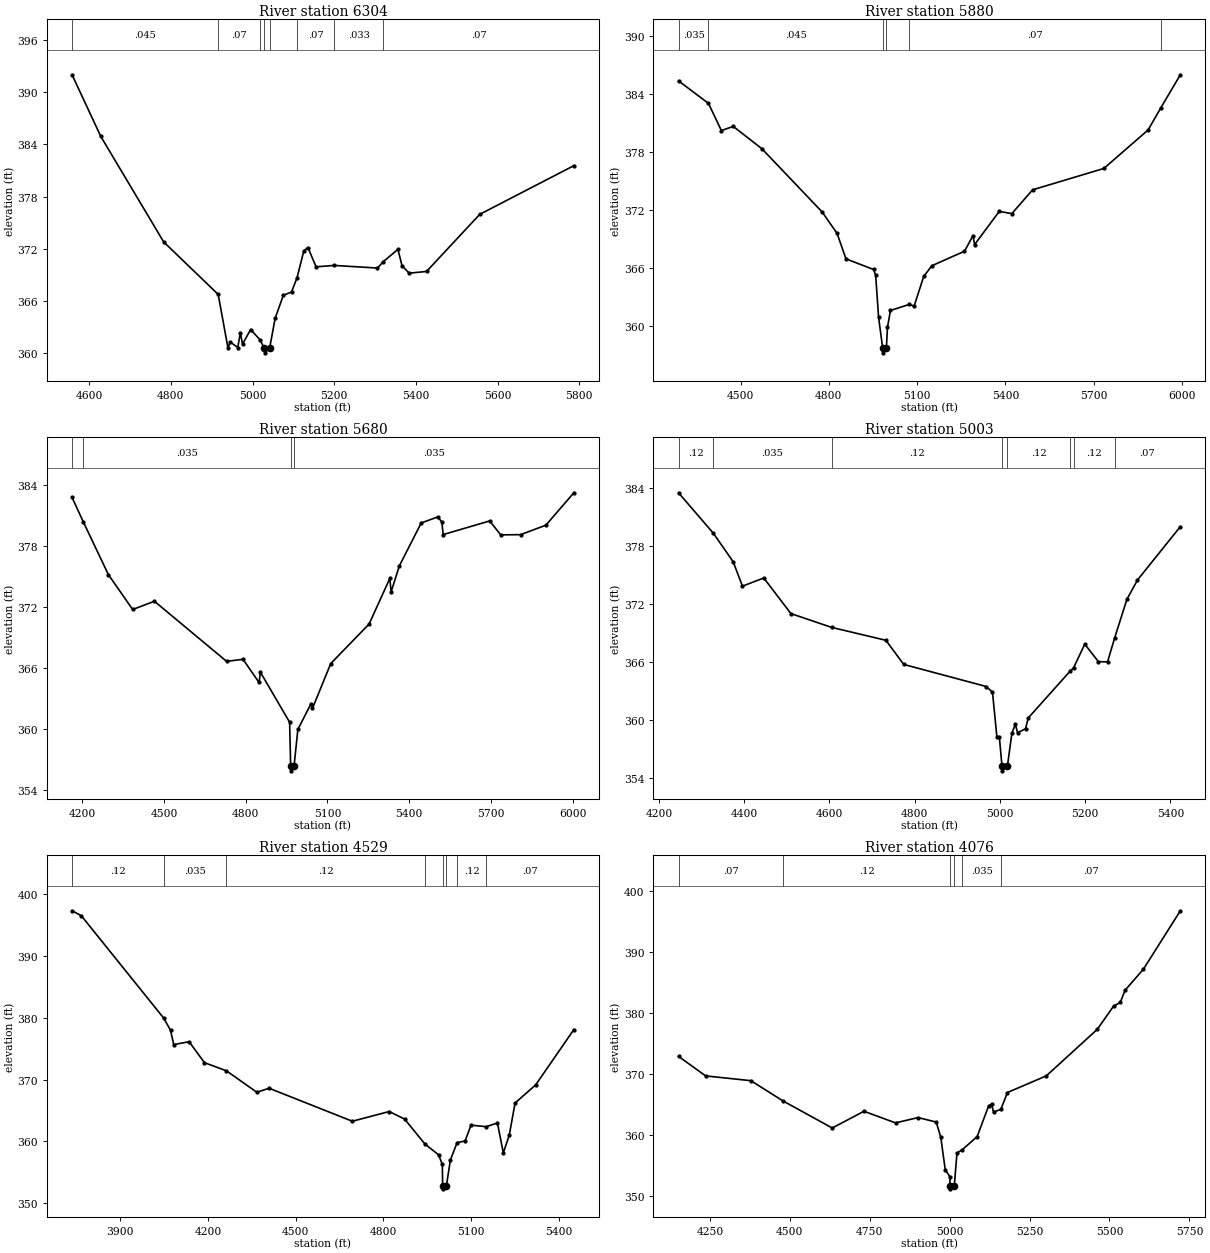
Type RM Length L Ch R = 1 ,6304    ,424,424,424
BEGIN DESCRIPTION:
Stream0552 12.0
END DESCRIPTION:
XS GIS Cut Line= 3
      2365475.01     13684624.97        2365625.       13684225.
        2365575.     13683425.03
#Sta/Elev= 30
  4558.1     392  4628.4  384.92  4782.4   372.8  4915.9  366.77  4939.9   360.6
  4945.2  361.31  4963.9  360.67  4970.1  362.37  4975.5  361.06  4995.3  362.74
  5018.2  361.56  5029.1  360.56  5029.6  360.06  5041.7  360.56  5055.4  364.04
  5075.4  366.67  5095.5  367.05  5109.1   368.7  5125.5  371.77  5135.6  372.16
  5155.6  369.94  5200.2   370.1  5305.9   369.8  5320.6  370.55    5356  371.95
    5366  370.07  5383.6  369.21  5426.1  369.41  5556.4  375.97  5786.8  381.56
#Mann= 8 ,-1 , 0
  4558.1    .045       0  4915.9     .07       0  5018.2    .033       0
  5029.1     .05       0  5041.7    .033       0  5109.1     .07       0
  5200.2    .033       0  5320.6     .07       0
Bank Sta=5029.1,5041.7
XS Rating Curve= 0 ,0
Exp/Cntr=0.3,0.1

Type RM Length L Ch R = 1 ,5880    ,200,200,200
BEGIN DESCRIPTION:
Stream0552 11.0
END DESCRIPTION:
XS GIS Cut Line= 3
       2365862.9     13684979.38      2365949.23     13684321.97
       2365829.7     13683286.09
#Sta/Elev= 30
  4289.1  385.34  4390.9  383.01  4434.7   380.2  4475.1  380.63  4572.5  378.32
  4777.6  371.77  4828.1  369.56  4858.3  366.93  4952.1  365.83  4959.2  365.24
  4969.2  360.88    4983  357.71  4983.5  357.21  4995.7  357.71  4999.4  359.86
  5009.5  361.59  5073.7  362.22    5090  362.04  5122.6  365.12  5150.4  366.22
  5261.2  367.72  5290.3  369.34  5295.4   368.4  5379.3  371.84  5422.2  371.61
  5492.7  374.07  5734.9  376.28  5885.3  380.26    5928  382.52  5994.9  385.97
#Mann= 6 ,-1 , 0
  4289.1    .035       0  4390.9    .045       0    4983    .045       0
  4995.7    .045       0  5073.7     .07       0    5928    .035       0
Bank Sta=4983,4995.7
XS Rating Curve= 0 ,0
Exp/Cntr=0.3,0.1

Type RM Length L Ch R = 1 ,5680    ,677,677,677
BEGIN DESCRIPTION:
Stream0552 10.0
END DESCRIPTION:
XS GIS Cut Line= 3
      2365962.52     13685065.65      2366161.71     13684733.66
      2366009.19     13683288.04
#Sta/Elev= 30
  4163.1  382.82  4204.8  380.39  4296.1  375.24  4385.4   371.8  4465.2  372.61
  4729.9   366.7  4790.2   366.9    4849  364.62    4854  365.63  4961.2  360.71
  4964.9  356.43  4965.4  355.93  4977.6  356.43  4991.4     360  5039.9  362.55
  5044.9  362.07    5112  366.48  5252.8  370.37  5328.6  374.85  5333.7  373.54
  5363.4  376.07  5443.9  380.31  5504.2   380.9  5519.5  380.42  5524.5  379.17
  5695.2  380.51  5735.5  379.14  5808.2  379.16  5901.1  380.09  6003.9  383.28
#Mann= 4 ,-1 , 0
  4163.1     .12       0  4204.8    .035       0  4964.9    .035       0
  4977.6    .035       0
Bank Sta=4964.9,4977.6
XS Rating Curve= 0 ,0
Exp/Cntr=0.3,0.1

Type RM Length L Ch R = 1 ,5003    ,474,474,474
BEGIN DESCRIPTION:
Stream0552 9.0
END DESCRIPTION:
XS GIS Cut Line= 3
      2365974.97     13685125.02        2366575.       13684675.
      2366724.99     13684275.04
#Sta/Elev= 30
  4246.1  383.52  4327.7  379.33  4374.3  376.37  4396.1  373.84  4446.1  374.69
  4509.7     371  4605.1  369.57  4732.6  368.23  4774.3  365.73    4968  363.44
  4982.6  362.86    4993   358.2  4998.8   358.2  5004.9   355.2  5005.4   354.7
  5017.7   355.2  5028.2  358.62  5036.2  359.53  5041.5  358.64  5060.2  359.07
  5066.5  360.18  5164.9  365.04  5172.7  365.36  5199.1  367.83  5231.1  366.02
  5252.5  365.99  5268.9  368.43  5297.9  372.47  5322.8  374.48  5423.3  380.01
#Mann= 8 ,-1 , 0
  4246.1     .12       0  4327.7    .035       0  4605.1     .12       0
  5004.9     .05       0  5017.7     .12       0  5164.9    .035       0
  5172.7     .12       0  5268.9     .07       0
Bank Sta=5004.9,5017.7
XS Rating Curve= 0 ,0
Exp/Cntr=0.3,0.1

Type RM Length L Ch R = 1 ,4529    ,453,453,453
BEGIN DESCRIPTION:
Stream0552 8.0
END DESCRIPTION:
XS GIS Cut Line= 3
      2365774.97     13685275.01        2366975.       13684875.
        2366925.     13684425.01
#Sta/Elev= 30
  3734.7  397.27  3766.3  396.47  4048.7  379.91    4072  377.93  4082.6  375.65
  4135.3  376.12    4188  372.73    4263  371.42  4367.2  367.95  4409.3   368.6
    4694  363.27  4820.4  364.84  4873.1  363.62  4942.8  359.58  4989.1  357.86
  5002.2   356.3  5003.2  352.85  5003.7  352.35  5016.1  352.85  5029.8  357.02
  5052.8  359.82  5080.1  360.08  5100.3  362.64  5152.2  362.39  5190.8  362.99
  5210.9  358.16  5231.1  360.97  5251.2  366.22  5321.6  369.14  5452.4  378.08
#Mann= 8 ,-1 , 0
  3734.7     .12       0  4048.7    .035       0    4263     .12       0
  4942.8    .035       0  5003.2    .035       0  5016.1    .035       0
  5052.8     .12       0  5152.2     .07       0
Bank Sta=5003.2,5016.1
XS Rating Curve= 0 ,0
Exp/Cntr=0.3,0.1

Type RM Length L Ch R = 1 ,4076    ,419,419,419
BEGIN DESCRIPTION:
Stream0552 7.0
END DESCRIPTION:
XS GIS Cut Line= 3
      2366574.98     13685825.02        2367175.       13685225.
      2367775.03     13684824.98
#Sta/Elev= 30
  4151.9  372.94  4236.8  369.74  4378.2  368.96  4478.8  365.64  4632.8  361.21
  4731.8  363.95  4830.8  362.05  4901.5  362.92    4958  362.18  4972.2   359.7
  4986.3  354.35  5000.5  353.26  5001.5  351.75    5002  351.25  5014.5  351.75
    5023  357.13  5039.3  357.65  5086.1  359.81  5122.1  364.85  5131.2  365.09
  5137.2  363.83    5160  364.25  5180.7  367.02  5302.4  369.75  5461.7  377.36
  5512.7  381.16  5533.8  381.78  5548.8  383.77  5605.9   387.2  5721.6  396.78
#Mann= 6 ,-1 , 0
  4151.9     .07       0  4478.8     .12       0  5001.5     .05       0
  5014.5     .12       0  5039.3    .035       0    5160     .07       0
Bank Sta=5001.5,5014.5
XS Rating Curve= 0 ,0
Exp/Cntr=0.3,0.1

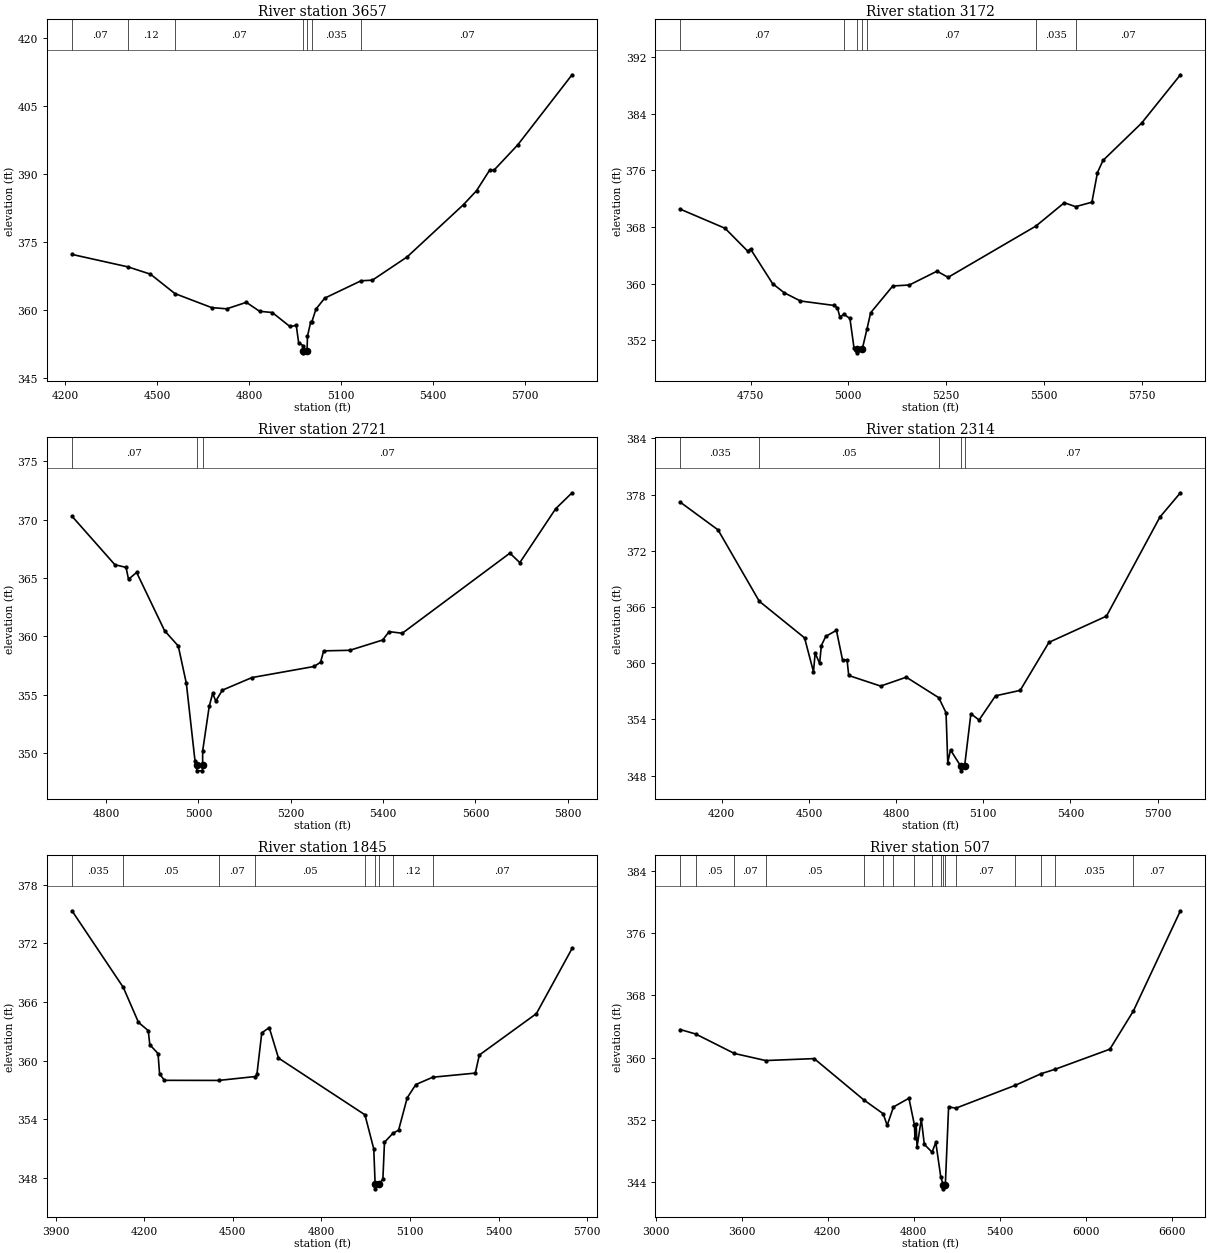
Type RM Length L Ch R = 1 ,3657    ,485,485,485
BEGIN DESCRIPTION:
Stream0552 6.0
END DESCRIPTION:
XS GIS Cut Line= 3
      2366824.99       13686025.        2367425.       13685525.
      2368025.03     13684924.97
#Sta/Elev= 30
  4223.3  372.18  4405.7  369.43  4479.1  367.82  4558.7  363.54  4678.3  360.45
  4727.7  360.18  4791.5  361.61  4834.5  359.64  4876.1  359.36  4933.4  356.28
  4954.2  356.51    4962   352.7  4976.3  352.06  4976.4  350.97  4976.9  350.47
  4989.4  350.97  4990.7  354.15  5001.1  357.24  5004.6  357.24  5018.5  360.13
  5046.8  362.53  5165.2  366.36  5202.3   366.5  5315.5  371.63  5499.3  383.17
  5541.7  386.24  5584.2  390.75  5598.3  390.74  5676.1  396.35  5852.9   411.8
#Mann= 7 ,-1 , 0
  4223.3     .07       0  4405.7     .12       0  4558.7     .07       0
  4976.4     .05       0  4989.4     .07       0  5004.6    .035       0
  5165.2     .07       0
Bank Sta=4976.4,4989.4
XS Rating Curve= 0 ,0
Exp/Cntr=0.3,0.1

Type RM Length L Ch R = 1 ,3172    ,451,451,451
BEGIN DESCRIPTION:
Stream0552 5.0
END DESCRIPTION:
XS GIS Cut Line= 3
      2367275.02     13686324.97        2367525.       13685975.
        2368125.       13685375.
#Sta/Elev= 30
  4570.5  370.53  4684.7  367.84  4742.5  364.62  4749.9  364.91  4806.4  360.02
  4835.9  358.74  4877.7  357.57  4963.7  356.94  4972.3  356.58  4978.5  355.29
  4988.4   355.7  5004.1   355.1  5014.7  350.88  5022.3  350.75  5022.8  350.25
  5035.5  350.75  5047.7  353.61  5057.1  355.91  5113.7  359.69  5156.1  359.83
  5226.8  361.78  5255.1  360.91  5479.9  368.16  5552.1  371.44  5581.3  370.89
  5622.8  371.52    5637   375.7  5651.1  377.41  5750.1   382.7  5849.1  389.51
#Mann= 7 ,-1 , 0
  4570.5     .07       0  4988.4     .12       0  5022.3     .05       0
  5035.5     .12       0  5047.7     .07       0  5479.9    .035       0
  5581.3     .07       0
Bank Sta=5022.3,5035.5
XS Rating Curve= 0 ,0
Exp/Cntr=0.3,0.1

Type RM Length L Ch R = 1 ,2721    ,407,407,407
BEGIN DESCRIPTION:
Stream0552 4.0
END DESCRIPTION:
XS GIS Cut Line= 3
        2367425.       13686475.        2367675.       13686375.
        2368275.       13685825.
#Sta/Elev= 30
    4726   370.3  4818.9  366.14  4843.1  365.91  4848.5  364.89    4866  365.48
  4926.6  360.48  4956.2  359.17  4973.7  355.97  4992.6  349.27  4995.8  348.96
  4996.3  348.46  5008.5  348.46    5009  348.96  5009.1  350.18  5023.3     354
  5030.7   355.1  5037.5  354.45  5051.7  355.38  5115.8  356.46  5250.2  357.41
  5264.4  357.77  5271.2  358.75  5327.9   358.8  5398.8  359.68    5413   360.4
  5441.4  360.26  5674.5  367.13  5696.1  366.32  5773.7  370.94  5809.2  372.31
#Mann= 3 ,-1 , 0
    4726     .07       0  4995.8     .05       0    5009     .07       0
Bank Sta=4995.8,5009
XS Rating Curve= 0 ,0
Exp/Cntr=0.3,0.1

Type RM Length L Ch R = 1 ,2314    ,469,469,469
BEGIN DESCRIPTION:
Stream0552 3.0
END DESCRIPTION:
XS GIS Cut Line= 3
      2367224.98     13686975.01        2368025.       13686475.
      2368574.97     13685925.03
#Sta/Elev= 30
  4057.4  377.18  4187.1  374.23    4329  366.61  4484.9   362.7  4515.6  359.08
  4521.5  361.08  4536.8  359.97  4542.7  361.88    4558  362.86  4594.6   363.5
  4615.8  360.32  4631.1  360.36    4637  358.68  4746.7  357.55  4835.1   358.5
  4946.8  356.31  4971.9   354.7  4977.8  349.39  4987.3  350.73  5022.5     349
    5023   348.5  5035.8     349  5057.4  354.59  5085.7  353.93  5142.2  356.51
  5227.1  357.09  5326.1  362.22  5524.1  365.02  5707.9  375.59  5778.6  378.19
#Mann= 5 ,-1 , 0
  4057.4    .035       0    4329     .05       0  4946.8     .07       0
  5022.5     .05       0  5035.8     .07       0
Bank Sta=5022.5,5035.8
XS Rating Curve= 0 ,0
Exp/Cntr=0.3,0.1

Type RM Length L Ch R = 1 ,1845    ,1338,1338,1338
BEGIN DESCRIPTION:
Stream0552 2.0
END DESCRIPTION:
XS GIS Cut Line= 3
      2367325.01       13686975.        2368325.       13686675.
      2368574.99     13686075.02
#Sta/Elev= 30
  3955.1  375.33    4129  367.48  4180.4   363.9  4213.5  363.06  4218.7  361.62
  4246.6  360.71  4251.8  358.63  4268.3  357.97  4452.3  357.96  4576.1  358.36
  4581.5  358.57    4598  362.83  4623.3  363.37  4654.6  360.25  4947.5  354.44
  4977.4  350.95    4982  347.36  4982.5  346.86  4995.3  347.36  5008.3  347.85
  5013.7  351.63  5042.7  352.56  5061.4  352.86  5090.7  356.18  5119.9  357.54
  5177.4  358.29  5321.4  358.71    5335  360.56  5528.3   364.8  5649.1  371.47
#Mann= 9 ,-1 , 0
  3955.1    .035       0    4129     .05       0  4452.3     .07       0
  4576.1     .05       0  4947.5     .07       0    4982     .05       0
  4995.3     .07       0  5042.7     .12       0  5177.4     .07       0
Bank Sta=4982,4995.3
XS Rating Curve= 0 ,0
Exp/Cntr=0.3,0.1

Type RM Length L Ch R = 1 ,507     ,0,0,0
BEGIN DESCRIPTION:
Stream0552 1.0
END DESCRIPTION:
XS GIS Cut Line= 3
        2367275.       13688575.        2368775.       13687525.
        2368625.     13685874.99
#Sta/Elev= 30
  3173.1  363.62  3280.1  363.05  3550.1  360.55  3768.7  359.64  4106.5  359.89
  4452.4  354.59  4587.6  352.81  4615.7  351.32  4659.7  353.68  4767.4   354.8
  4806.2  351.32  4809.2  349.68  4817.9  351.43    4824  348.53  4853.7  352.14
  4874.6  348.87  4928.9  347.87  4954.8  349.13  4989.4  344.69    5007  343.66
  5007.5  343.16  5021.3  343.66  5044.2  353.69  5094.4  353.52  5509.2  356.46
  5689.3  357.95  5788.5  358.53  6168.9   361.1  6332.9  366.01  6660.9  378.88
#Mann= 17 ,-1 , 0
  3173.1     .07       0  3280.1     .05       0  3550.1     .07       0
  3768.7     .05       0  4452.4     .07       0  4587.6     .05       0
  4659.7     .07       0  4806.2    .035       0  4928.9     .07       0
  4989.4     .12       0    5007     .05       0  5021.3     .12       0
  5094.4     .07       0  5509.2    .035       0  5689.3     .07       0
  5788.5    .035       0  6332.9     .07       0
Bank Sta=5007,5021.3
XS Rating Curve= 0 ,0
Exp/Cntr=0.3,0.1

Chan Stop Cuts=-1
Use User Specified Reach Order=0
Composite Channel Slope=5