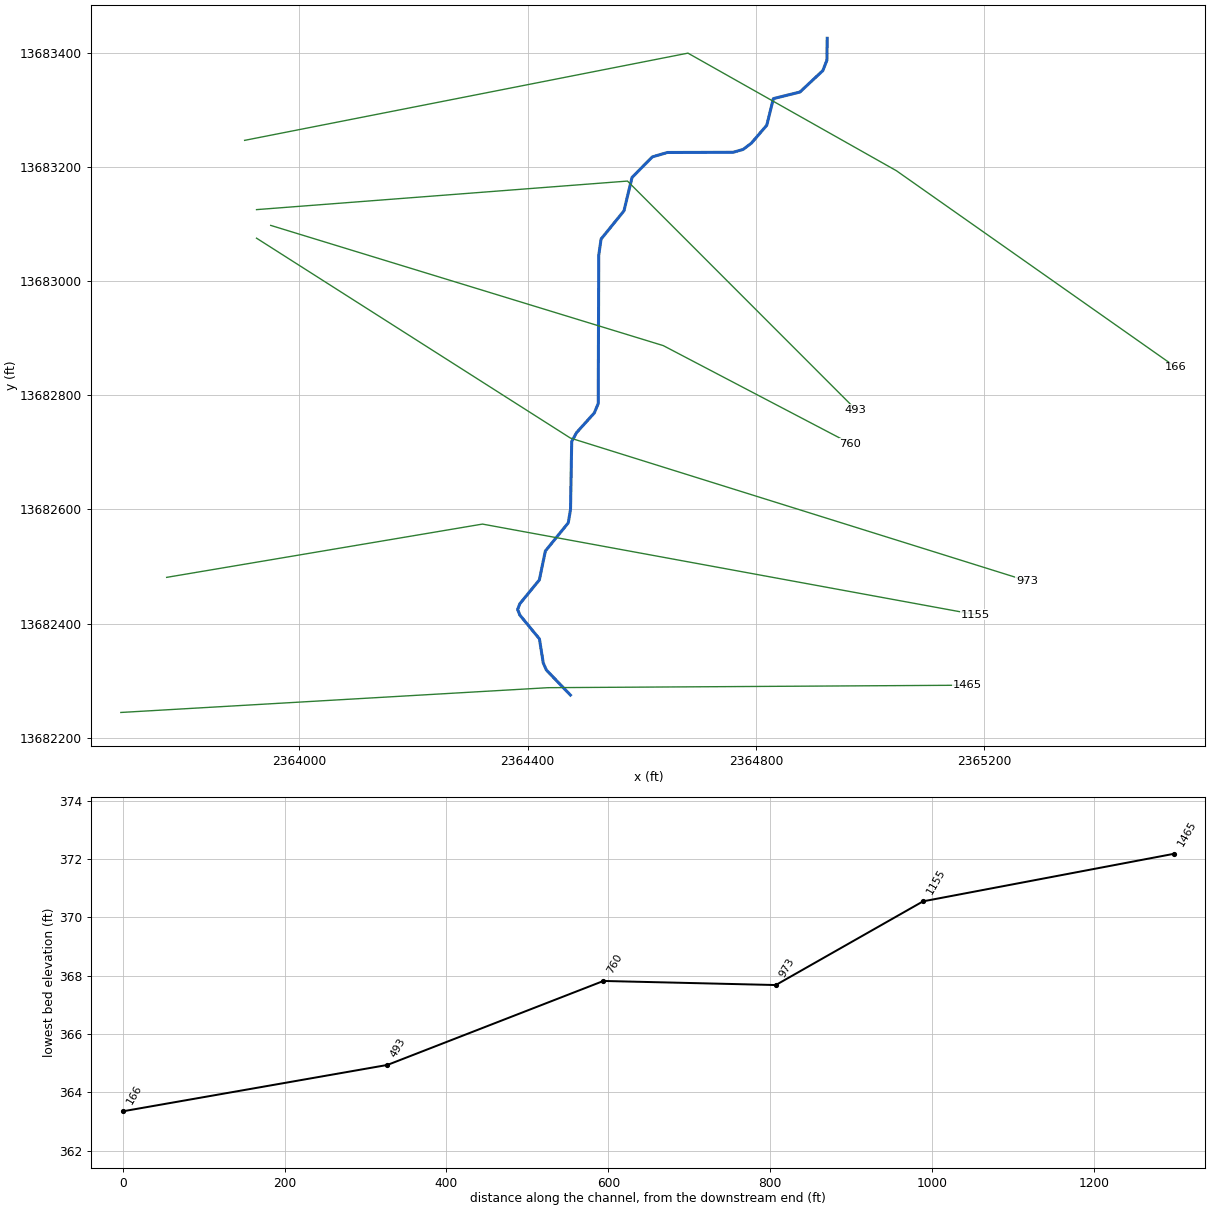
--- Stream0553.prj (project) ---

Proj Title=Stream0553 Base Level Engineering
Current Plan=p01
Default Exp/Contr=0.3,0.1
English Units
Geom File=g01
Flow File=f01
Plan File=p01
BEGIN DESCRIPTION:
Stream0553
END DESCRIPTION:

--- Stream0553.p01 (plan) ---

Plan Title=Multiple Run
Short Identifier=Multiple
Geom File=g01
Flow File=f01
Subcritical Flow
K Sum by GR= 0
Std Step Tol= 0.01
Critical Tol= 0.01
Num of Std Step Trials= 20
Max Error Tol= 0.3
Flow Tol Ratio= 0.001
Split Flow NTrial= 30
Split Flow Tol= 0.02
Split Flow Ratio= 0.02
Log Output Level= 0
Friction Slope Method= 1
Unsteady Friction Slope Method= 2
Unsteady Bridges Friction Slope Method= 1
Parabolic Critical Depth
Global Vel Dist=  1 , 1 , 1
Global Log Level= 0
CheckData=True
Encroach Param= -1, 0, 0, 0
BEGIN DESCRIPTION:
Multiple Run
END DESCRIPTION:

--- Stream0553.f01 (steady flow) ---

Flow Title=Multiple
Number of Profiles=7
Profile Names=10-year,25-year,50-year,1pct_min,100-year,1pct_plu,500-year
River Rch & RM= Stream0553,Reach-1,1465
     719    1178    1599    1050    2095    4180    3567
Boundary for River Rch & Prof#=Stream0553,Reach-1,1
Up Type=0
Dn Type=3
Dn Slope=0.005
Boundary for River Rch & Prof#=Stream0553,Reach-1,2
Up Type=0
Dn Type=3
Dn Slope=0.005
Boundary for River Rch & Prof#=Stream0553,Reach-1,3
Up Type=0
Dn Type=3
Dn Slope=0.005
Boundary for River Rch & Prof#=Stream0553,Reach-1,4
Up Type=0
Dn Type=3
Dn Slope=0.005
Boundary for River Rch & Prof#=Stream0553,Reach-1,5
Up Type=0
Dn Type=3
Dn Slope=0.005
Boundary for River Rch & Prof#=Stream0553,Reach-1,6
Up Type=0
Dn Type=3
Dn Slope=0.005
Boundary for River Rch & Prof#=Stream0553,Reach-1,7
Up Type=0
Dn Type=3
Dn Slope=0.005

--- Stream0553.g01 (geometry) ---

Geom Title=Existing Conditions

River Reach=Stream0553,Reach-1
Reach XY= 30
      2364475.00     13682275.00      2364432.88     13682318.86
      2364427.46     13682331.06      2364420.67     13682373.42
      2364386.37     13682415.08      2364382.48     13682425.00
      2364386.40     13682434.92      2364420.58     13682476.64
      2364431.09     13682527.17      2364471.24     13682576.56
      2364475.19     13682599.92      2364477.27     13682719.06
      2364485.86     13682734.64      2364516.86     13682768.94
      2364523.78     13682785.50      2364524.64     13683045.15
      2364528.75     13683073.45      2364568.85     13683122.86
      2364583.00     13683181.39      2364618.52     13683217.30
      2364644.89     13683225.06      2364759.95     13683225.36
      2364777.68     13683230.40      2364792.11     13683241.36
      2364819.13     13683272.75      2364830.63     13683319.37
      2364877.14     13683330.86      2364917.35     13683368.39
      2364924.48     13683386.63      2364925.00     13683425.00

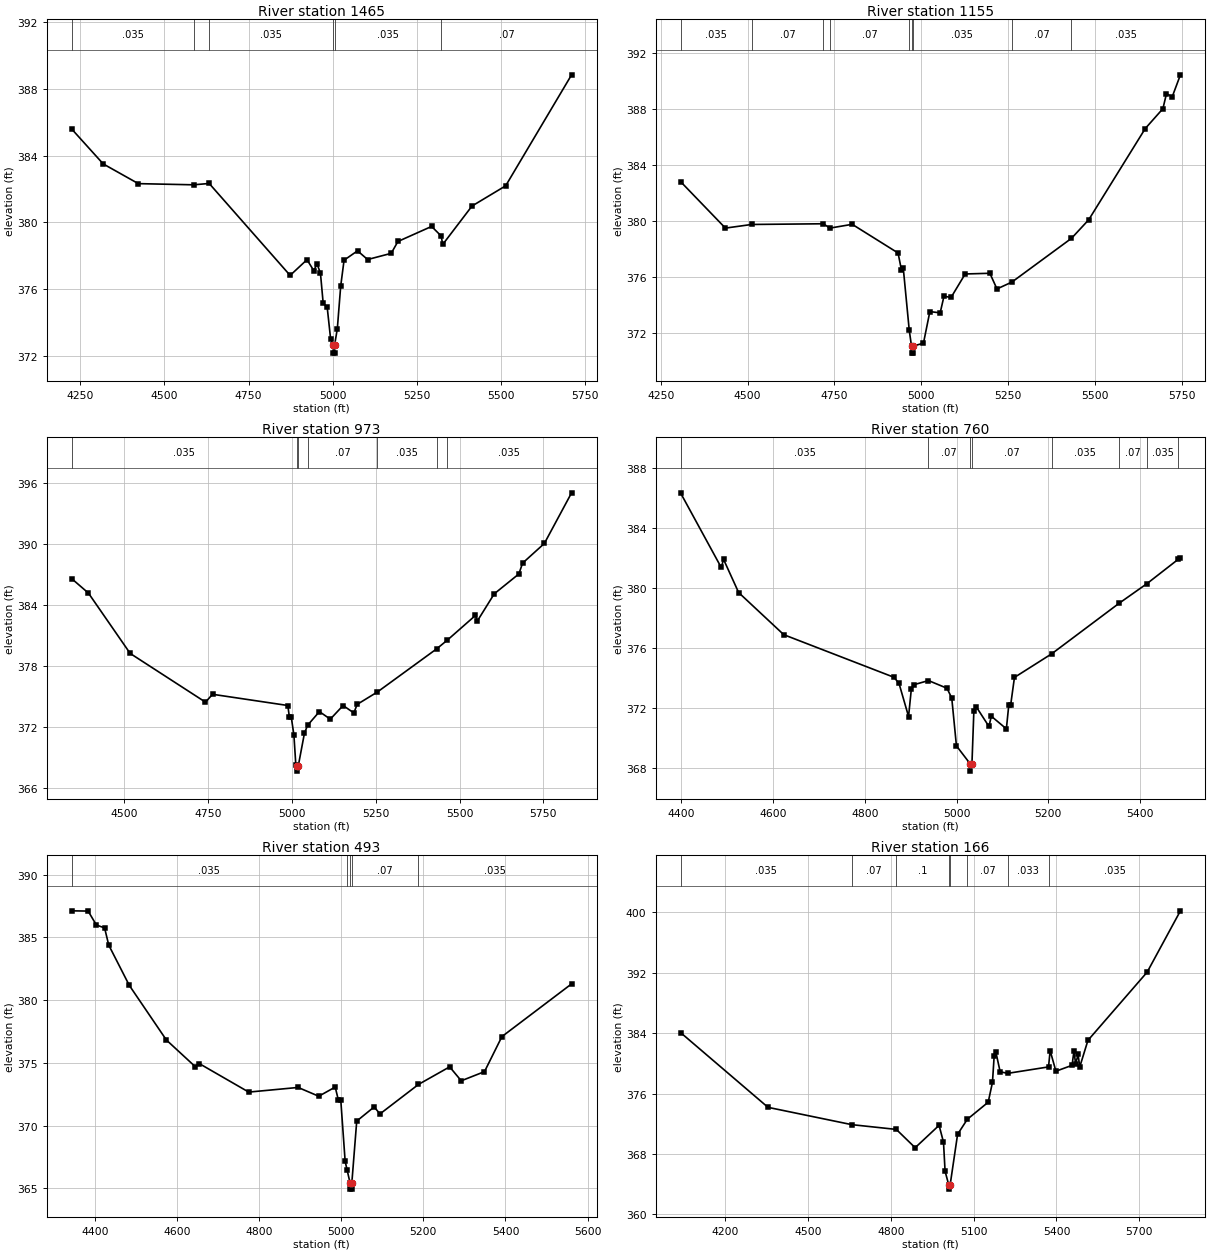
Type RM Length L Ch R = 1,1465,310,310,310
BEGIN DESCRIPTION:
Stream0553 3.0
END DESCRIPTION:
XS GIS Cut Line= 3
      2363687.19     13682244.53      2364435.90     13682287.93
      2365170.82     13682292.27
#Sta/Elev= 30
  4224.6  385.59  4318.3  383.50  4422.7  382.32  4586.6  382.25  4633.1  382.33
  4873.5  376.83  4923.6  377.77  4943.6  377.12  4953.6  377.51  4963.6  376.96
  4971.6  375.18  4983.7  374.91  4993.7  373.04  5001.7  372.68  5001.9  372.18
  5005.4  372.18  5005.7  372.68  5013.7  373.64  5023.7  376.19  5033.7  377.74
  5073.7  378.30  5103.7  377.78  5173.7  378.15  5193.7  378.86  5293.7  379.76
  5322.1  379.19  5326.7  378.68  5413.7  380.98  5513.7  382.19  5709.5  388.83
#Mann=6,-1,0
  4224.6   0.035       0  4586.6    0.07       0  4633.1   0.035       0
  5001.7   0.035       0  5005.7   0.035       0  5322.1    0.07       0
Bank Sta=5001.7,5005.7
Exp/Cntr=0.3,0.1

Type RM Length L Ch R = 1,1155,182,182,182
BEGIN DESCRIPTION:
E21160
END DESCRIPTION:
XS GIS Cut Line= 3
      2363767.49     13682481.08      2364320.89     13682574.39
      2365184.57     13682415.98
#Sta/Elev= 30
  4306.8  382.82  4436.1  379.49  4511.8  379.75  4718.0  379.80  4736.8  379.49
  4801.2  379.76  4933.2  377.71  4943.0  376.48  4948.1  376.65  4965.4  372.18
  4971.9  371.05  4972.1  370.55  4975.6  370.55  4975.9  371.05  5006.3  371.26
  5024.7  373.52  5054.4  373.43  5065.4  374.62  5085.7  374.53  5126.4  376.21
  5197.5  376.26  5217.9  375.14  5260.9  375.63  5432.5  378.76  5482.2  380.09
  5644.9  386.61  5695.7  388.03  5705.9  389.10  5722.5  388.88  5746.1  390.45
#Mann=9,-1,0
  4306.8   0.035       0  4511.8    0.07       0  4718.0   0.035       0
  4736.8    0.07       0  4965.4   0.035       0  4971.9   0.035       0
  4975.9   0.035       0  5260.9    0.07       0  5432.5   0.035       0
Bank Sta=4971.9,4975.9
Exp/Cntr=0.3,0.1

Type RM Length L Ch R = 1,973,213,213,213
BEGIN DESCRIPTION:
Stream0553 2.0
END DESCRIPTION:
XS GIS Cut Line= 3
      2363924.97     13683075.02      2364475.00     13682725.00
      2365274.99     13682475.00
#Sta/Elev= 30
  4343.9  386.57  4393.9  385.15  4518.3  379.23  4742.7  374.45  4763.9  375.22
  4988.2  374.12  4992.9  372.97  4998.5  372.97  5006.3  371.24  5012.1  368.28
  5015.3  368.18  5015.6  367.68  5019.3  368.18  5037.8  371.41  5047.2  372.18
  5082.3  373.52  5114.8  372.78  5153.0  374.12  5185.0  373.39  5194.9  374.23
  5255.4  375.45  5431.5  379.67  5463.5  380.53  5547.5  382.96  5552.7  382.39
  5603.5  385.08  5676.9  387.03  5687.9  388.09  5752.8  390.02  5834.0  394.99
#Mann=7,-1,0
  4343.9   0.035       0  5015.3   0.035       0  5019.3   0.035       0
  5047.2    0.07       0  5255.4   0.035       0  5431.5    0.07       0
  5463.5   0.035       0
Bank Sta=5015.3,5019.3
Exp/Cntr=0.3,0.1

Type RM Length L Ch R = 1,760,267,267,267
BEGIN DESCRIPTION:
E21161
END DESCRIPTION:
XS GIS Cut Line= 3
      2363949.84     13683097.38      2364637.73     13682886.89
      2364965.41     13682715.45
#Sta/Elev= 30
  4398.5  386.32  4487.2  381.36  4492.4  381.89  4525.2  379.69  4623.5  376.89
  4863.4  374.06  4874.5  373.66  4895.4  371.45  4901.4  373.27  4906.6  373.56
  4938.8  373.84  4979.1  373.33  4989.5  372.68  4999.7  369.50  5029.3  368.32
  5029.5  367.82  5033.5  368.32  5037.7  371.84  5043.0  372.09  5070.5  370.79
  5075.7  371.47  5108.5  370.63  5113.8  372.23  5117.9  372.23  5126.1  374.05
  5207.3  375.62  5354.2  378.98  5415.1  380.29  5483.3  381.91  5487.7  381.99
#Mann=8,-1,0
  4398.5   0.035       0  4938.8    0.07       0  5029.3    0.05       0
  5033.5    0.07       0  5207.3   0.035       0  5354.2    0.07       0
  5415.1   0.035       0  5483.3    0.07       0
Bank Sta=5029.3,5033.5
Exp/Cntr=0.3,0.1

Type RM Length L Ch R = 1,493,327,327,327
BEGIN DESCRIPTION:
Stream0553 1.0
END DESCRIPTION:
XS GIS Cut Line= 3
      2363925.01     13683125.00      2364575.00     13683175.00
      2364975.00     13682775.00
#Sta/Elev= 30
  4343.5  387.11  4383.6  387.09  4403.7  385.98  4423.7  385.75  4433.8  384.38
  4483.9  381.17  4574.2  376.82  4644.4  374.70  4654.4  374.94  4774.8  372.67
  4895.1  373.04  4945.3  372.34  4985.4  373.07  4992.9  372.06  4998.9  372.06
  5009.6  367.15  5014.5  366.45  5021.5  365.44  5021.8  364.94  5025.6  364.94
  5025.9  365.44  5037.8  370.36  5080.3  371.49  5094.4  370.93  5188.2  373.28
  5264.1  374.68  5292.4  373.57  5349.0  374.30  5391.4  377.09  5561.1  381.29
#Mann=5,-1,0
  4343.5   0.035       0  5014.5    0.07       0  5021.5   0.035       0
  5025.9    0.07       0  5188.2   0.035       0
Bank Sta=5021.5,5025.9
Exp/Cntr=0.3,0.1

Type RM Length L Ch R = 1,166,0,0,0
BEGIN DESCRIPTION:
XS7056
END DESCRIPTION:
XS GIS Cut Line= 4
      2363904.11     13683246.28      2364680.96     13683399.00
      2365046.17     13683193.15      2365535.99     13682848.96
#Sta/Elev= 30
  4039.1  384.07  4355.9  374.17  4659.1  371.88  4820.3  371.25  4888.5  368.83
  4975.1  371.79  4991.1  369.56  4996.8  365.72  5010.5  363.85  5010.8  363.35
  5014.9  363.85  5042.1  370.60  5077.3  372.59  5152.9  374.85  5168.3  377.47
  5174.5  380.96  5180.3  381.54  5196.2  378.87  5223.9  378.67  5371.3  379.52
  5377.1  381.68  5398.0  378.95  5456.4  379.73  5463.4  381.63  5469.5  379.87
  5478.2  381.20  5484.3  379.52  5513.9  383.03  5728.3  392.06  5848.7  400.17
#Mann=8,-1,0
  4039.1   0.035       0  4659.1    0.07       0  4820.3     0.1       0
  5010.5    0.05       0  5014.9     0.1       0  5077.3    0.07       0
  5223.9   0.033       0  5371.3   0.035       0
Bank Sta=5010.5,5014.9
Exp/Cntr=0.3,0.1

Chan Stop Cuts=-1