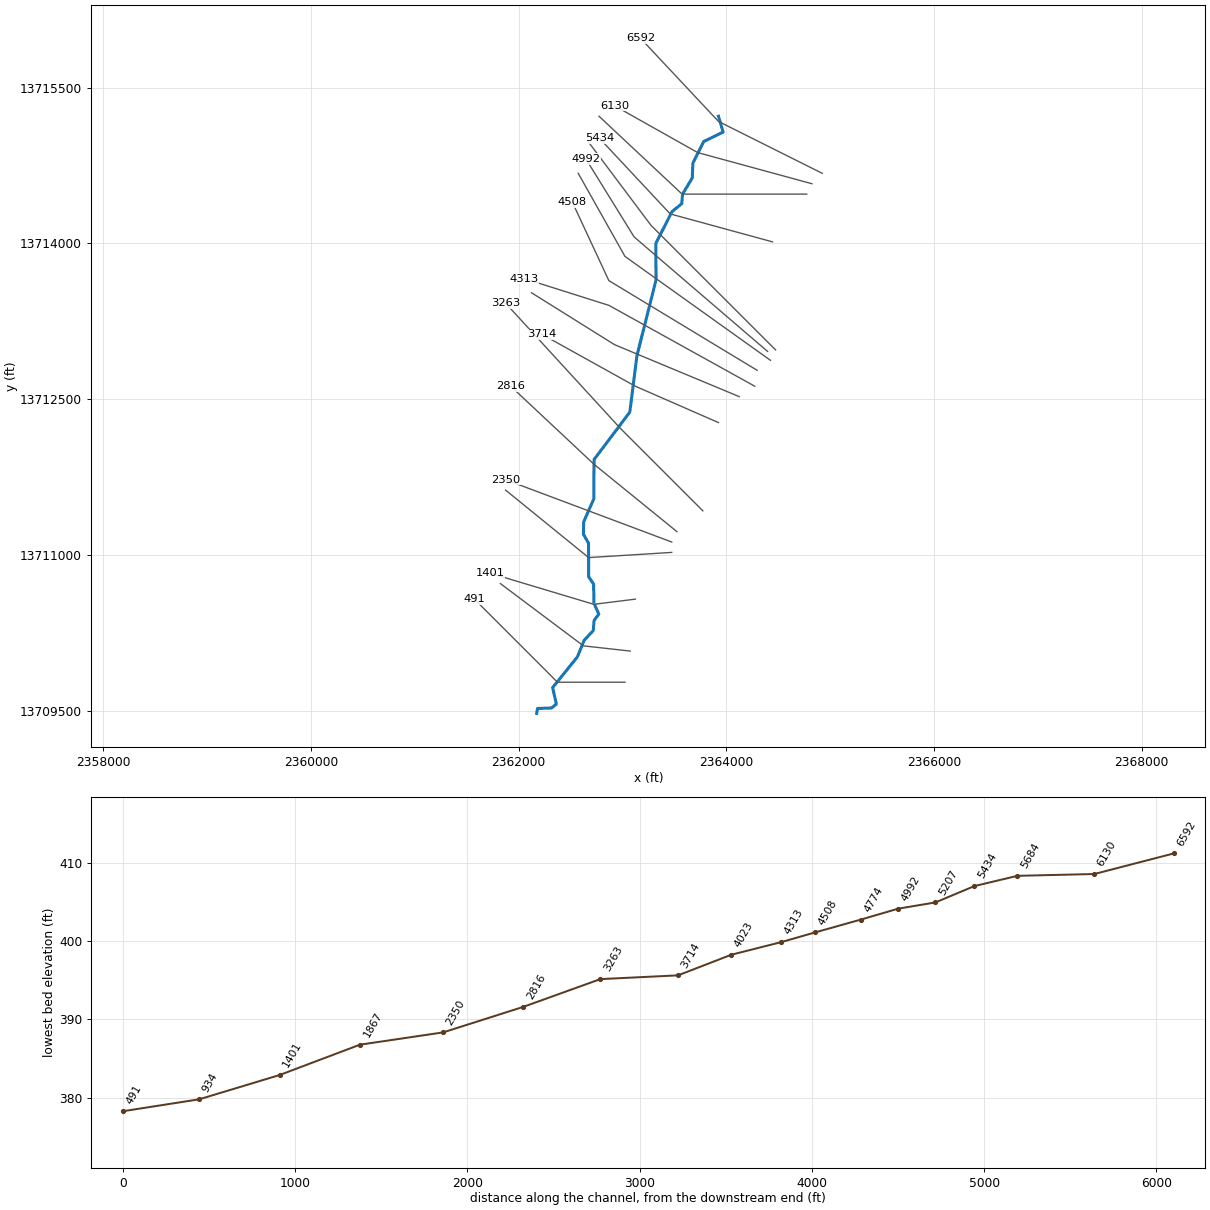
--- Stream0559.prj (project) ---

Proj Title=Stream0559 Base Level Engineering
Current Plan=p01
Default Exp/Contr=0.3,0.1
English Units
Geom File=g01
Flow File=f01
Plan File=p01
BEGIN DESCRIPTION:
Stream0559
END DESCRIPTION:

--- Stream0559.p01 (plan) ---

Plan Title=Multiple Run
Short Identifier=Multiple
Geom File=g01
Flow File=f01
Subcritical Flow
K Sum by GR= 0
Std Step Tol= 0.01
Critical Tol= 0.01
Num of Std Step Trials= 20
Max Error Tol= 0.3
Flow Tol Ratio= 0.001
Split Flow NTrial= 30
Split Flow Tol= 0.02
Split Flow Ratio= 0.02
Log Output Level= 0
Friction Slope Method= 1
Unsteady Friction Slope Method= 2
Unsteady Bridges Friction Slope Method= 1
Parabolic Critical Depth
Global Vel Dist=  1 , 1 , 1
Global Log Level= 0
CheckData=True
Encroach Param= -1, 0, 0, 0
BEGIN DESCRIPTION:
Multiple Run
END DESCRIPTION:

--- Stream0559.f01 (steady flow) ---

Flow Title=Multiple
Number of Profiles=7
Profile Names=10-year,25-year,50-year,1pct_min,100-year,1pct_plu,500-year
River Rch & RM= Stream0559,Reach-1,6592
     734    1198    1622    1063    2120    4231    3592
River Rch & RM= Stream0559,Reach-1,4992
    1363    2300    3184    2129    4248    8477    7504
Boundary for River Rch & Prof#=Stream0559,Reach-1,1
Up Type=0
Dn Type=3
Dn Slope=0.005
Boundary for River Rch & Prof#=Stream0559,Reach-1,2
Up Type=0
Dn Type=3
Dn Slope=0.005
Boundary for River Rch & Prof#=Stream0559,Reach-1,3
Up Type=0
Dn Type=3
Dn Slope=0.005
Boundary for River Rch & Prof#=Stream0559,Reach-1,4
Up Type=0
Dn Type=3
Dn Slope=0.005
Boundary for River Rch & Prof#=Stream0559,Reach-1,5
Up Type=0
Dn Type=3
Dn Slope=0.005
Boundary for River Rch & Prof#=Stream0559,Reach-1,6
Up Type=0
Dn Type=3
Dn Slope=0.005
Boundary for River Rch & Prof#=Stream0559,Reach-1,7
Up Type=0
Dn Type=3
Dn Slope=0.005

--- Stream0559.g01 (geometry) ---

Geom Title=Existing Conditions

River Reach=Stream0559,Reach-1
Reach XY= 30
      2363925.00     13715225.00      2363970.04     13715072.41
      2363783.01     13714981.38      2363678.76     13714773.44
      2363672.75     13714630.93      2363578.86     13714473.34
      2363571.84     13714383.34      2363477.57     13714306.09
      2363321.46     13713999.55      2363324.30     13713650.44
      2363139.81     13712918.16      2363071.45     13712376.47
      2362727.24     13711919.07      2362724.48     13711540.22
      2362627.25     13711319.06      2362624.77     13711199.93
      2362673.78     13711114.50      2362675.52     13710790.22
      2362722.74     13710719.06      2362726.24     13710535.50
      2362773.18     13710431.12      2362727.38     13710369.03
      2362719.46     13710272.58      2362630.85     13710177.29
      2362566.86     13710018.94      2362328.47     13709723.50
      2362364.06     13709564.56      2362319.55     13709527.05
      2362182.71     13709522.28      2362175.00     13709475.00

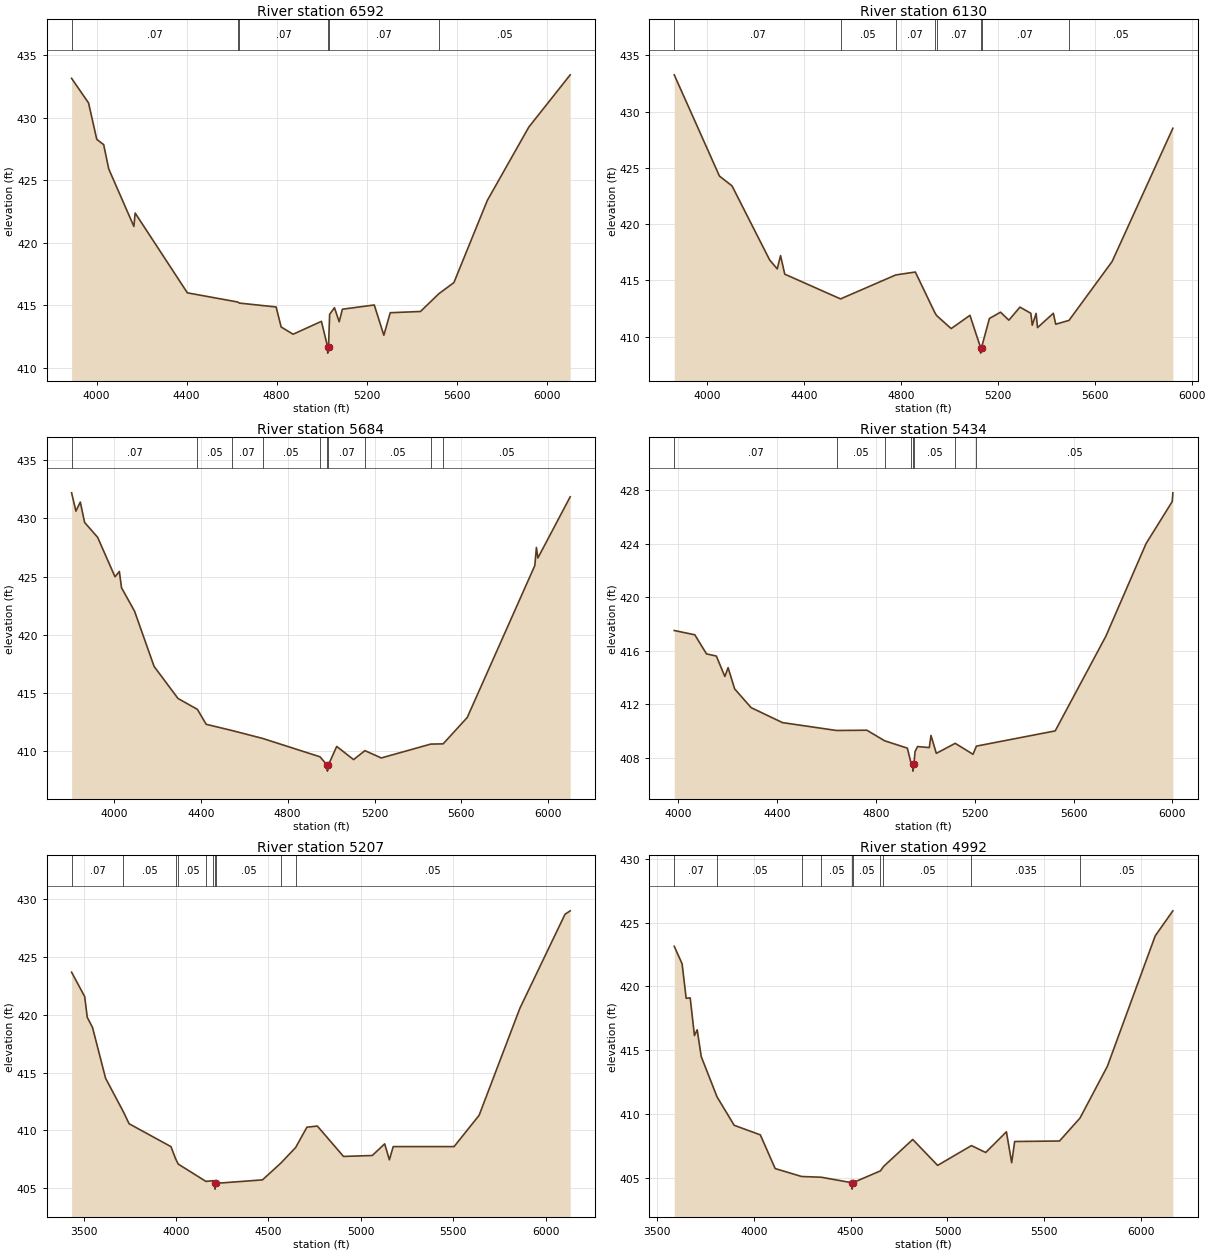
Type RM Length L Ch R = 1,6592,462,462,462
BEGIN DESCRIPTION:
Stream0559 15.0
END DESCRIPTION:
XS GIS Cut Line= 3
      2364924.97     13714675.01      2363925.00     13715175.00
      2363174.99     13715975.01
#Sta/Elev= 30
  3889.1  433.14  3964.5  431.17  4000.9  428.26  4031.6  427.84  4054.0  425.90
  4165.8  421.30  4171.4  422.37  4403.4  415.99  4626.2  415.26  4634.7  415.17
  4797.5  414.86  4819.8  413.26  4872.9  412.68  4998.7  413.71  5026.3  411.67
  5026.6  411.17  5030.3  411.67  5035.2  414.27  5056.7  414.80  5077.7  413.68
  5091.9  414.68  5233.5  415.02  5276.0  412.60  5304.3  414.40  5438.7  414.50
  5521.0  415.93  5587.2  416.81  5735.6  423.38  5919.8  429.24  6103.7  433.42
#Mann=6,-1,0
  3889.1    0.07       0  4626.2    0.05       0  4634.7    0.07       0
  5026.3    0.05       0  5030.3    0.07       0  5521.0    0.05       0
Bank Sta=5026.3,5030.3
Exp/Cntr=0.3,0.1

Type RM Length L Ch R = 1,6130,446,446,446
BEGIN DESCRIPTION:
Stream0559 14.0
END DESCRIPTION:
XS GIS Cut Line= 3
      2364825.00     13714575.00      2363725.00     13714875.00
      2362925.04     13715324.98
#Sta/Elev= 30
  3864.4  433.28  4051.0  424.28  4102.8  423.41  4258.3  416.82  4289.4  416.03
  4303.2  417.21  4320.5  415.56  4550.8  413.36  4778.6  415.49  4859.5  415.75
  4938.8  412.19  4946.9  411.89  5007.4  410.72  5084.9  411.90  5128.7  409.04
  5129.0  408.54  5132.8  409.04  5165.2  411.62  5211.1  412.18  5245.5  411.47
  5291.4  412.63  5336.3  412.08  5342.1  411.02  5358.0  412.07  5363.8  410.81
  5429.1  412.08  5439.0  411.11  5493.7  411.45  5671.6  416.68  5922.4  428.53
#Mann=8,-1,0
  3864.4    0.07       0  4550.8    0.05       0  4778.6    0.07       0
  4938.8    0.05       0  4946.9    0.07       0  5128.7    0.05       0
  5132.8    0.07       0  5493.7    0.05       0
Bank Sta=5128.7,5132.8
Exp/Cntr=0.3,0.1

Type RM Length L Ch R = 1,5684,250,250,250
BEGIN DESCRIPTION:
Stream0559 13.0
END DESCRIPTION:
XS GIS Cut Line= 3
      2364774.98     13714475.00      2363575.00     13714475.00
      2362774.97     13715225.03
#Sta/Elev= 30
  3804.7  432.20  3824.7  430.63  3844.7  431.41  3864.7  429.66  3924.7  428.38
  4004.7  424.99  4024.7  425.45  4034.7  424.05  4094.7  422.04  4184.7  417.30
  4294.7  414.55  4384.3  413.61  4424.7  412.33  4542.6  411.80  4684.2  411.12
  4948.8  409.54  4982.6  408.81  4982.9  408.31  4986.8  408.81  5025.9  410.43
  5103.6  409.30  5155.8  410.07  5231.1  409.44  5458.7  410.63  5516.1  410.65
  5627.2  412.92  5938.4  425.96  5945.7  427.51  5952.5  426.61  6101.3  431.86
#Mann=10,-1,0
  3804.7    0.07       0  4384.3    0.05       0  4542.6    0.07       0
  4684.2    0.05       0  4948.8    0.07       0  4982.6    0.05       0
  4986.8    0.07       0  5155.8    0.05       0  5458.7    0.07       0
  5516.1    0.05       0
Bank Sta=4982.6,4986.8
Exp/Cntr=0.3,0.1

Type RM Length L Ch R = 1,5434,227,227,227
BEGIN DESCRIPTION:
E21166
END DESCRIPTION:
XS GIS Cut Line= 3
      2364445.22     13714015.35      2363459.97     13714284.44
      2362779.26     13715012.85
#Sta/Elev= 30
  3983.2  417.52  4066.4  417.20  4113.9  415.77  4153.6  415.61  4188.1  414.08
  4201.1  414.74  4227.8  413.15  4294.4  411.75  4421.2  410.63  4640.3  410.04
  4763.0  410.06  4834.8  409.27  4926.8  408.72  4941.8  407.60  4949.1  407.50
  4949.3  407.00  4953.3  407.50  4957.9  408.46  4968.2  408.84  5015.6  408.76
  5022.5  409.67  5044.0  408.33  5120.5  409.08  5192.5  408.26  5206.3  408.87
  5525.2  410.01  5730.3  417.09  5893.0  424.02  5999.0  427.17  6001.5  427.82
#Mann=8,-1,0
  3983.2    0.07       0  4640.3    0.05       0  4834.8    0.07       0
  4941.8    0.05       0  4949.1    0.05       0  4953.3    0.05       0
  5120.5    0.07       0  5206.3    0.05       0
Bank Sta=4949.1,4953.3
Exp/Cntr=0.3,0.1

Type RM Length L Ch R = 1,5207,215,215,215
BEGIN DESCRIPTION:
Stream0559 12.0
END DESCRIPTION:
XS GIS Cut Line= 3
      2364474.98     13712975.02      2363275.00     13714175.00
      2362675.02     13714974.97
#Sta/Elev= 30
  3435.2  423.69  3505.9  421.58  3520.0  419.78  3548.3  418.91  3619.0  414.51
  3715.1  411.61  3746.3  410.57  3972.6  408.59  3998.1  407.53  4012.0  407.08
  4161.6  405.58  4200.9  405.64  4210.9  405.41  4211.1  404.91  4215.1  405.41
  4467.6  405.71  4567.5  407.17  4647.4  408.52  4708.0  410.27  4764.5  410.37
  4906.0  407.74  5061.5  407.82  5128.7  408.83  5154.1  407.45  5174.9  408.59
  5504.1  408.59  5639.5  411.30  5860.4  420.58  6104.1  428.70  6132.2  429.00
#Mann=10,-1,0
  3435.2    0.07       0  3715.1    0.05       0  3998.1    0.07       0
  4012.0    0.05       0  4161.6    0.07       0  4200.9    0.05       0
  4210.9    0.05       0  4215.1    0.05       0  4567.5    0.07       0
  4647.4    0.05       0
Bank Sta=4210.9,4215.1
Exp/Cntr=0.3,0.1

Type RM Length L Ch R = 1,4992,218,218,218
BEGIN DESCRIPTION:
E21165
END DESCRIPTION:
XS GIS Cut Line= 3
      2364397.46     13712960.68      2363112.75     13714063.09
      2362649.15     13714812.65
#Sta/Elev= 30
  3589.3  423.14  3629.9  421.77  3650.8  419.07  3671.6  419.10  3693.6  416.15
  3707.8  416.60  3728.7  414.50  3810.5  411.34  3898.8  409.12  4033.8  408.37
  4110.4  405.73  4246.7  405.11  4349.2  405.05  4506.9  404.62  4507.1  404.12
  4511.1  404.62  4653.9  405.55  4669.6  405.89  4820.7  408.01  4949.1  405.98
  5123.7  407.53  5197.1  406.99  5304.2  408.61  5331.4  406.19  5346.8  407.85
  5578.4  407.89  5684.2  409.69  5825.4  413.74  6072.5  423.96  6163.5  425.92
#Mann=10,-1,0
  3589.3    0.07       0  3810.5    0.05       0  4246.7    0.07       0
  4349.2    0.05       0  4506.9    0.05       0  4511.1    0.05       0
  4653.9    0.07       0  4669.6    0.05       0  5123.7   0.035       0
  5684.2    0.05       0
Bank Sta=4506.9,4511.1
Exp/Cntr=0.3,0.1

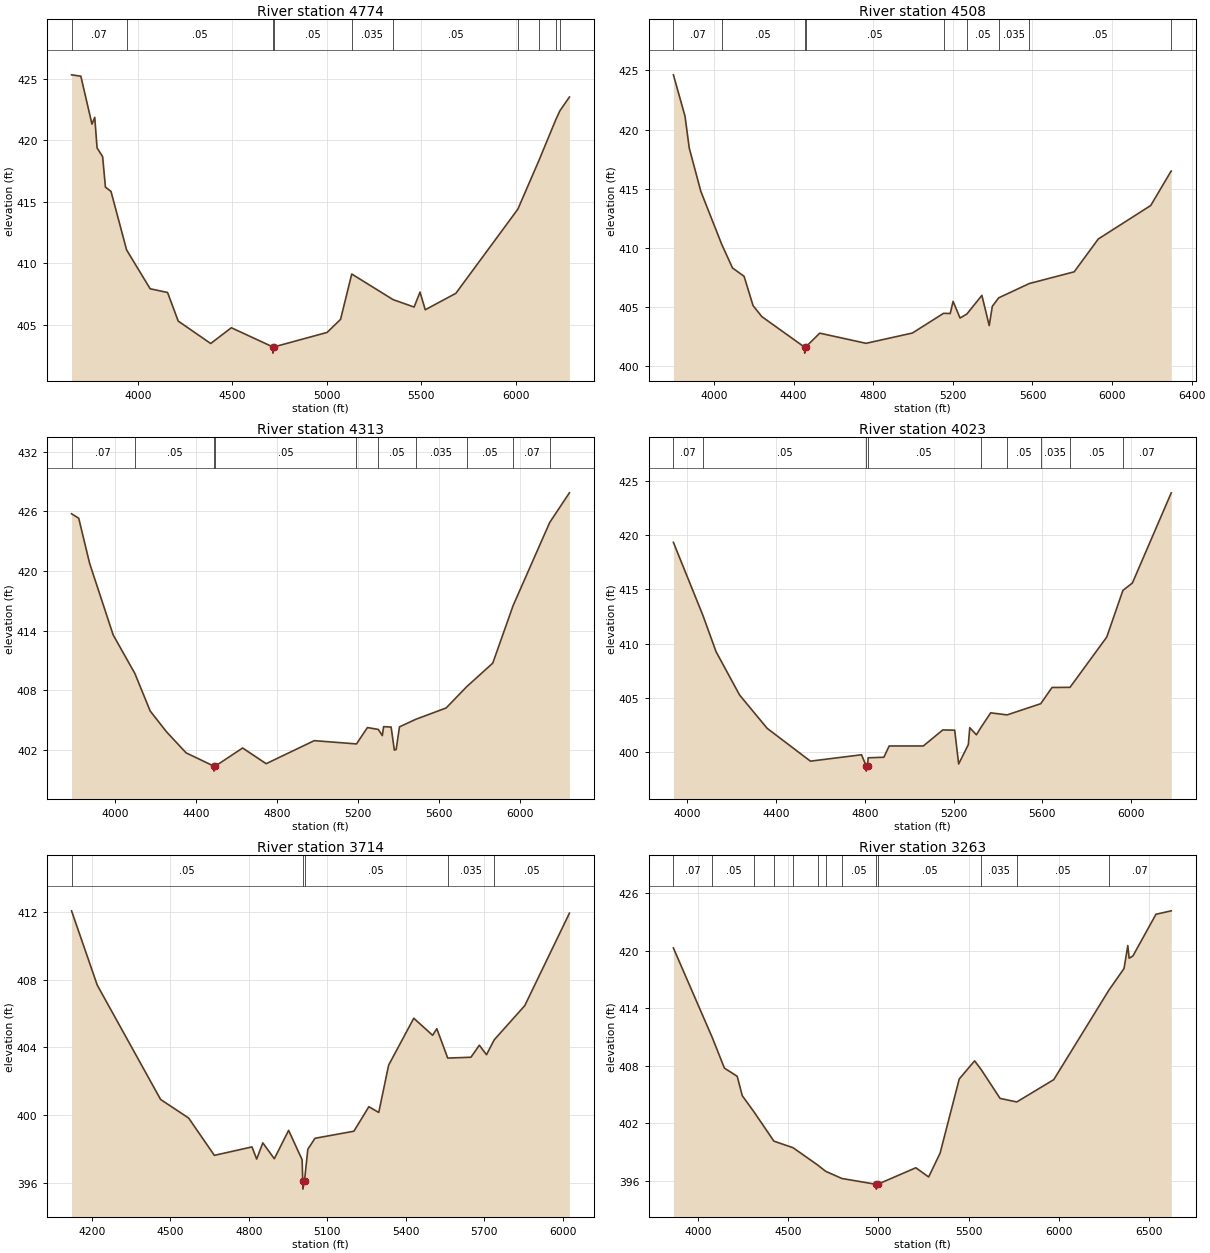
Type RM Length L Ch R = 1,4774,266,266,266
BEGIN DESCRIPTION:
Stream0559 11.0
END DESCRIPTION:
XS GIS Cut Line= 3
      2364425.04     13712874.97      2363025.00     13713875.00
      2362575.00     13714675.01
#Sta/Elev= 30
  3647.3  425.30  3696.5  425.19  3755.5  421.30  3770.2  421.85  3782.5  419.37
  3812.0  418.66  3826.8  416.19  3856.3  415.84  3939.1  411.09  4063.9  407.94
  4156.1  407.64  4212.6  405.32  4384.7  403.50  4494.1  404.78  4714.4  403.22
  4714.6  402.72  4718.6  403.22  5001.6  404.40  5072.9  405.46  5132.1  409.14
  5351.3  407.06  5462.5  406.46  5494.0  407.67  5521.7  406.24  5683.7  407.57
  6012.4  414.40  6123.5  418.33  6212.9  421.64  6234.7  422.37  6285.7  423.50
#Mann=10,-1,0
  3647.3    0.07       0  3939.1    0.05       0  4714.4    0.05       0
  4718.6    0.05       0  5132.1   0.035       0  5351.3    0.05       0
  6012.4   0.035       0  6123.5    0.05       0  6212.9   0.035       0
  6234.7    0.05       0
Bank Sta=4714.4,4718.6
Exp/Cntr=0.3,0.1

Type RM Length L Ch R = 1,4508,195,195,195
BEGIN DESCRIPTION:
E21164
END DESCRIPTION:
XS GIS Cut Line= 3
      2364297.63     13712778.38      2362869.70     13713642.08
      2362518.12     13714397.33
#Sta/Elev= 30
  3795.6  424.63  3854.0  421.13  3875.3  418.43  3933.5  414.77  4038.6  410.28
  4092.6  408.29  4150.8  407.58  4196.0  405.10  4240.0  404.17  4455.1  401.58
  4455.4  401.08  4459.5  401.58  4531.0  402.77  4763.8  401.91  4996.6  402.78
  5153.4  404.45  5186.7  404.43  5201.1  405.46  5236.2  404.05  5270.5  404.39
  5345.8  405.97  5382.7  403.41  5398.2  405.04  5430.3  405.76  5584.3  406.97
  5809.6  407.96  5930.9  410.74  6194.2  413.57  6296.6  416.48  6297.5  416.48
#Mann=9,-1,0
  3795.6    0.07       0  4038.6    0.05       0  4455.1    0.05       0
  4459.5    0.05       0  5153.4   0.035       0  5270.5    0.05       0
  5430.3   0.035       0  5584.3    0.05       0  6296.6    0.07       0
Bank Sta=4455.1,4459.5
Exp/Cntr=0.3,0.1

Type RM Length L Ch R = 1,4313,290,290,290
BEGIN DESCRIPTION:
Stream0559 10.0
END DESCRIPTION:
XS GIS Cut Line= 3
      2364275.00     13712625.00      2362870.65     13713403.59
      2362053.60     13713662.05
#Sta/Elev= 30
  3783.1  425.77  3818.6  425.32  3872.4  420.78  3988.9  413.57  4096.4  409.68
  4171.9  405.91  4252.4  403.82  4349.7  401.69  4487.2  400.35  4487.7  399.85
  4493.8  400.35  4629.2  402.18  4745.7  400.60  4983.7  402.92  5192.5  402.59
  5246.7  404.24  5300.3  404.05  5320.3  403.43  5326.7  404.33  5363.8  404.29
  5379.8  401.97  5388.8  402.03  5405.1  404.31  5486.9  405.08  5636.0  406.21
  5736.9  408.34  5866.7  410.73  5967.2  416.52  6148.4  424.90  6245.8  427.88
#Mann=10,-1,0
  3783.1    0.07       0  4096.4    0.05       0  4487.2    0.05       0
  4493.8    0.05       0  5192.5   0.035       0  5300.3    0.05       0
  5486.9   0.035       0  5736.9    0.05       0  5967.2    0.07       0
  6148.4   0.035       0
Bank Sta=4487.2,4493.8
Exp/Cntr=0.3,0.1

Type RM Length L Ch R = 1,4023,309,309,309
BEGIN DESCRIPTION:
Stream0559 9.0
END DESCRIPTION:
XS GIS Cut Line= 3
      2364124.98     13712525.01      2362925.00     13713025.00
      2362124.98     13713525.01
#Sta/Elev= 30
  3937.3  419.35  4070.5  412.60  4129.6  409.26  4235.7  405.26  4359.8  402.19
  4554.8  399.16  4785.0  399.75  4805.5  398.74  4806.0  398.24  4812.1  398.74
  4814.8  399.47  4885.7  399.52  4909.6  400.56  5063.4  400.56  5151.2  402.04
  5204.8  402.02  5222.7  398.90  5266.2  400.68  5272.7  402.25  5302.7  401.59
  5322.8  402.26  5367.0  403.62  5441.1  403.43  5592.4  404.46  5643.5  405.96
  5724.4  405.97  5890.0  410.61  5962.7  414.91  6005.6  415.60  6180.7  423.92
#Mann=9,-1,0
  3937.3    0.07       0  4070.5    0.05       0  4805.5    0.05       0
  4812.1    0.05       0  5322.8   0.035       0  5441.1    0.05       0
  5592.4   0.035       0  5724.4    0.05       0  5962.7    0.07       0
Bank Sta=4805.5,4812.1
Exp/Cntr=0.3,0.1

Type RM Length L Ch R = 1,3714,451,451,451
BEGIN DESCRIPTION:
Stream0559 8.0
END DESCRIPTION:
XS GIS Cut Line= 3
      2363925.01     13712275.00      2363125.00     13712625.00
      2362224.98     13713125.01
#Sta/Elev= 30
  4122.7  412.09  4220.9  407.69  4463.0  400.92  4570.2  399.82  4668.5  397.61
  4812.3  398.11  4830.2  397.39  4853.6  398.35  4897.7  397.41  4952.3  399.09
  5003.9  397.35  5006.3  396.11  5006.8  395.61  5013.0  396.11  5025.7  397.97
  5053.1  398.62  5201.8  399.04  5259.0  400.49  5296.8  400.15  5334.5  402.95
  5430.6  405.73  5502.7  404.72  5518.7  405.11  5560.4  403.37  5649.1  403.42
  5681.2  404.13  5708.6  403.57  5738.0  404.45  5855.0  406.48  6025.5  411.95
#Mann=5,-1,0
  4122.7    0.05       0  5006.3    0.05       0  5013.0    0.05       0
  5560.4   0.035       0  5738.0    0.05       0
Bank Sta=5006.3,5013
Exp/Cntr=0.3,0.1

Type RM Length L Ch R = 1,3263,447,447,447
BEGIN DESCRIPTION:
Stream0559 7.0
END DESCRIPTION:
XS GIS Cut Line= 3
      2363775.01     13711424.99      2362975.00     13712225.00
      2361874.97     13713425.03
#Sta/Elev= 30
  3863.7  420.30  4079.0  410.96  4146.5  407.76  4217.3  406.91  4245.5  404.88
  4313.1  403.12  4420.7  400.14  4527.1  399.45  4662.4  397.66  4707.5  396.99
  4797.7  396.24  4988.0  395.63  4988.5  395.13  4995.1  395.63  5207.5  397.36
  5278.4  396.40  5341.9  398.89  5448.0  406.63  5533.1  408.52  5570.2  407.59
  5674.3  404.60  5766.9  404.23  5971.8  406.56  6276.3  415.87  6361.2  418.16
  6382.2  420.55  6389.6  419.23  6410.5  419.47  6538.2  423.82  6623.0  424.18
#Mann=13,-1,0
  3863.7    0.07       0  4079.0    0.05       0  4313.1    0.07       0
  4420.7    0.05       0  4527.1   0.035       0  4662.4    0.05       0
  4707.5    0.07       0  4797.7    0.05       0  4988.0    0.05       0
  4995.1    0.05       0  5570.2   0.035       0  5766.9    0.05       0
  6276.3    0.07       0
Bank Sta=4988,4995.1
Exp/Cntr=0.3,0.1

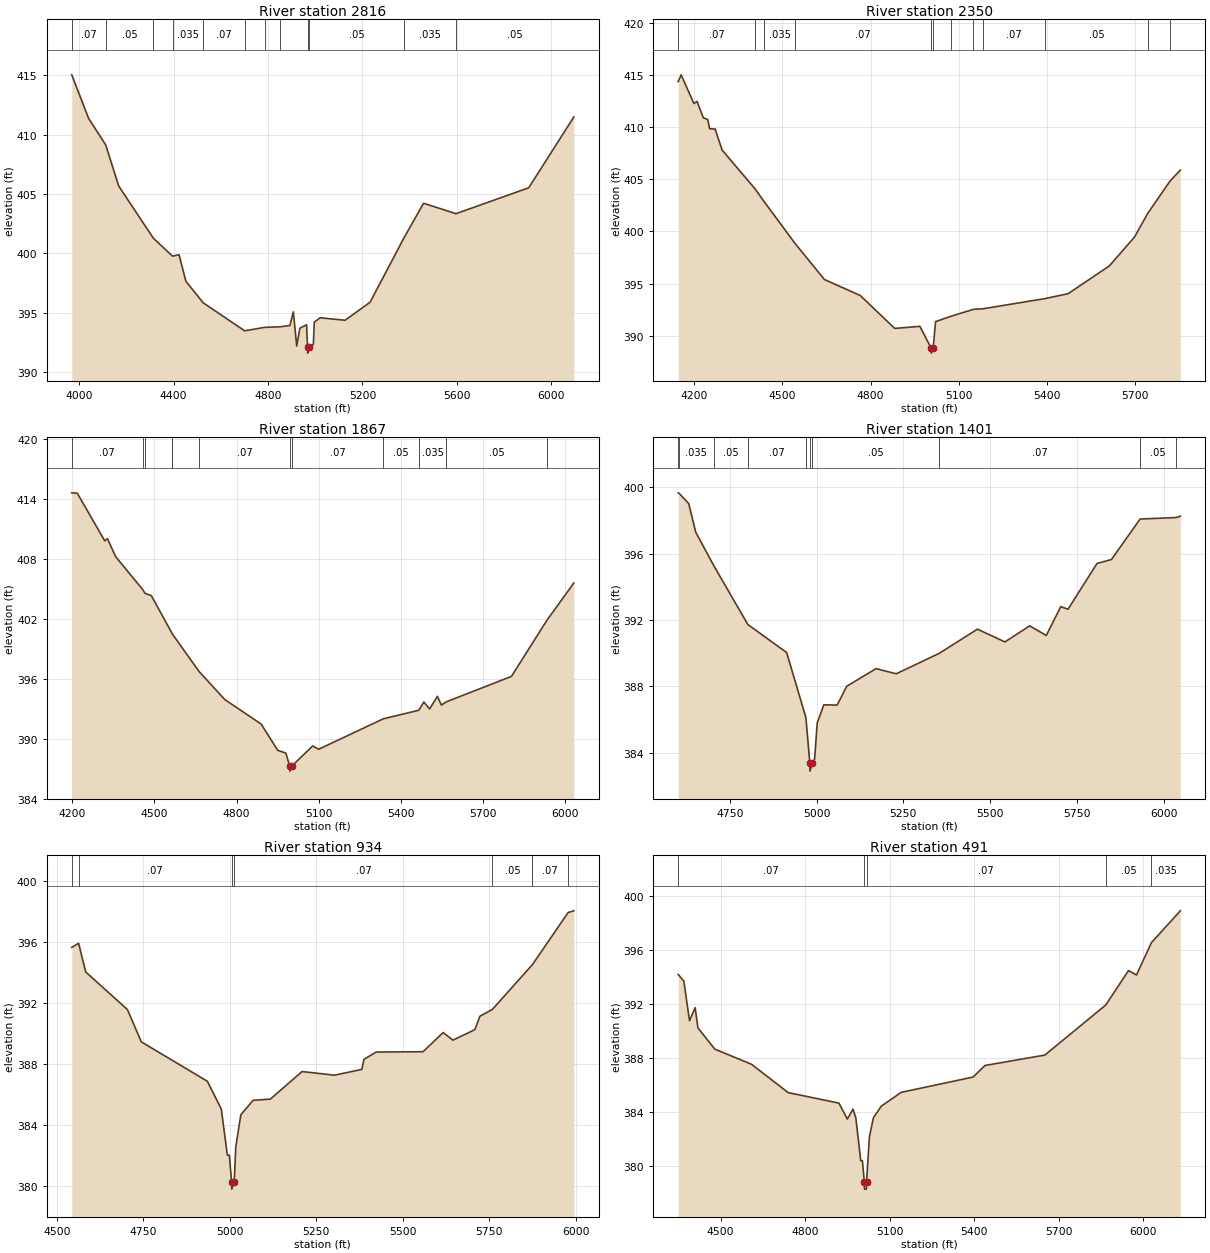
Type RM Length L Ch R = 1,2816,466,466,466
BEGIN DESCRIPTION:
Stream0559 6.0
END DESCRIPTION:
XS GIS Cut Line= 3
      2363524.97     13711225.02      2362725.00     13711875.00
      2361925.02     13712624.98
#Sta/Elev= 30
  3968.7  415.04  4039.8  411.38  4112.4  409.14  4167.6  405.67  4314.2  401.28
  4395.6  399.76  4423.3  399.88  4452.1  397.65  4525.5  395.83  4701.3  393.47
  4785.3  393.76  4852.0  393.81  4893.1  393.92  4907.5  395.07  4921.9  392.19
  4935.0  393.69  4963.5  393.98  4967.8  392.09  4968.3  391.59  4975.1  392.09
  4992.3  392.33  4996.2  394.20  5020.7  394.57  5126.7  394.36  5232.7  395.88
  5374.9  401.25  5459.3  404.22  5596.6  403.34  5904.8  405.52  6096.0  411.49
#Mann=12,-1,0
  3968.7    0.07       0  4112.4    0.05       0  4314.2    0.07       0
  4395.6   0.035       0  4525.5    0.07       0  4701.3    0.05       0
  4785.3   0.035       0  4852.0    0.05       0  4967.8    0.05       0
  4975.1    0.05       0  5374.9   0.035       0  5596.6    0.05       0
Bank Sta=4967.8,4975.1
Exp/Cntr=0.3,0.1

Type RM Length L Ch R = 1,2350,483,483,483
BEGIN DESCRIPTION:
Stream0559 5.0
END DESCRIPTION:
XS GIS Cut Line= 3
      2363475.00     13711125.00      2362675.00     13711425.00
      2361875.00     13711725.00
#Sta/Elev= 30
  4145.6  414.37  4155.4  415.02  4199.0  412.27  4209.7  412.47  4231.0  410.90
  4246.2  410.73  4252.4  409.85  4271.1  409.82  4295.1  407.80  4407.2  404.08
  4437.7  402.87  4544.0  398.82  4643.1  395.39  4765.0  393.86  4882.5  390.70
  4968.0  390.90  5006.1  388.83  5006.6  388.33  5013.4  388.83  5021.4  391.35
  5075.5  391.88  5150.3  392.53  5181.8  392.58  5394.4  393.56  5472.6  394.03
  5613.2  396.70  5698.7  399.47  5743.5  401.73  5819.6  404.84  5854.4  405.88
#Mann=12,-1,0
  4145.6    0.07       0  4407.2    0.05       0  4437.7   0.035       0
  4544.0    0.07       0  5006.1    0.05       0  5013.4    0.07       0
  5075.5    0.05       0  5150.3   0.035       0  5181.8    0.07       0
  5394.4    0.05       0  5743.5    0.07       0  5819.6    0.05       0
Bank Sta=5006.1,5013.4
Exp/Cntr=0.3,0.1

Type RM Length L Ch R = 1,1867,466,466,466
BEGIN DESCRIPTION:
Stream0559 4.0
END DESCRIPTION:
XS GIS Cut Line= 3
      2363474.97     13711025.00      2362675.00     13710975.00
      2361875.01     13711625.00
#Sta/Elev= 30
  4198.5  414.61  4218.5  414.58  4318.7  409.81  4328.7  410.02  4358.8  408.22
  4457.1  404.94  4466.2  404.55  4489.0  404.32  4563.6  400.59  4564.6  400.52
  4663.1  396.73  4757.1  393.92  4889.8  391.47  4949.9  388.85  4980.0  388.56
  4993.8  387.26  4994.3  386.76  5001.3  387.26  5077.6  389.28  5099.9  388.95
  5334.9  391.99  5464.8  392.85  5483.5  393.68  5504.3  392.98  5533.0  394.24
  5547.4  393.37  5565.9  393.70  5803.1  396.24  5931.7  401.82  6030.8  405.59
#Mann=12,-1,0
  4198.5    0.07       0  4457.1    0.05       0  4466.2   0.035       0
  4563.6    0.05       0  4564.6   0.035       0  4663.1    0.07       0
  4993.8    0.05       0  5001.3    0.07       0  5334.9    0.05       0
  5464.8   0.035       0  5565.9    0.05       0  5931.7    0.07       0
Bank Sta=4993.8,5001.3
Exp/Cntr=0.3,0.1

Type RM Length L Ch R = 1,1401,467,467,467
BEGIN DESCRIPTION:
Stream0559 3.0
END DESCRIPTION:
XS GIS Cut Line= 3
      2363125.04     13710575.01      2362725.00     13710525.00
      2361724.99     13710825.00
#Sta/Elev= 30
  4601.2  399.67  4604.2  399.63  4631.5  399.02  4651.6  397.30  4703.1  395.30
  4801.9  391.73  4913.7  390.04  4969.2  386.12  4980.4  383.39  4980.9  382.89
  4988.1  383.39  4994.3  383.62  5001.8  385.79  5020.9  386.89  5059.2  386.87
  5087.0  388.01  5171.4  389.07  5229.7  388.76  5353.3  389.99  5463.7  391.45
  5542.9  390.68  5614.2  391.65  5662.1  391.07  5703.9  392.81  5724.7  392.65
  5808.3  395.41  5850.0  395.65  5932.5  398.09  6036.2  398.18  6048.4  398.26
#Mann=10,-1,0
  4601.2    0.05       0  4604.2   0.035       0  4703.1    0.05       0
  4801.9    0.07       0  4969.2    0.05       0  4980.4    0.05       0
  4988.1    0.05       0  5353.3    0.07       0  5932.5    0.05       0
  6036.2   0.035       0
Bank Sta=4980.4,4988.1
Exp/Cntr=0.3,0.1

Type RM Length L Ch R = 1,934,443,443,443
BEGIN DESCRIPTION:
Stream0559 2.0
END DESCRIPTION:
XS GIS Cut Line= 3
      2363074.97     13710075.00      2362625.00     13710125.00
      2361825.03     13710724.98
#Sta/Elev= 30
  4542.5  395.66  4562.3  395.93  4582.7  394.05  4703.5  391.58  4743.7  389.46
  4934.9  386.87  4975.1  385.05  4992.7  382.02  4998.4  382.02  5004.9  380.29
  5005.4  379.79  5012.6  380.29  5017.1  382.57  5031.7  384.67  5067.1  385.62
  5117.1  385.70  5208.8  387.51  5302.5  387.27  5381.7  387.65  5387.9  388.31
  5423.4  388.79  5558.8  388.81  5617.1  390.07  5645.2  389.57  5708.8  390.26
  5723.4  391.14  5759.6  391.59  5875.4  394.53  5978.7  397.95  5995.2  398.06
#Mann=7,-1,0
  4542.5   0.035       0  4562.3    0.07       0  5004.9    0.05       0
  5012.6    0.07       0  5759.6    0.05       0  5875.4    0.07       0
  5978.7    0.05       0
Bank Sta=5004.9,5012.6
Exp/Cntr=0.3,0.1

Type RM Length L Ch R = 1,491,0,0,0
BEGIN DESCRIPTION:
Stream0559 1.0
END DESCRIPTION:
XS GIS Cut Line= 3
      2363024.97     13709775.00      2362375.00     13709775.00
      2361575.03     13710574.97
#Sta/Elev= 30
  4350.0  394.19  4370.0  393.69  4390.0  390.76  4410.0  391.73  4420.0  390.22
  4480.0  388.65  4610.0  387.53  4740.0  385.43  4920.0  384.65  4950.0  383.47
  4970.0  384.20  4980.0  383.57  4997.5  380.38  5003.5  380.38  5010.2  378.77
  5010.7  378.27  5017.5  378.27  5018.0  378.77  5028.3  382.15  5042.4  383.56
  5070.7  384.43  5141.4  385.45  5395.9  386.58  5438.4  387.44  5650.5  388.21
  5866.6  391.92  5947.5  394.48  5975.8  394.15  6028.8  396.55  6131.3  398.91
#Mann=5,-1,0
  4350.0    0.07       0  5010.2    0.05       0  5018.0    0.07       0
  5866.6    0.05       0  6028.8   0.035       0
Bank Sta=5010.2,5018
Exp/Cntr=0.3,0.1

Chan Stop Cuts=-1