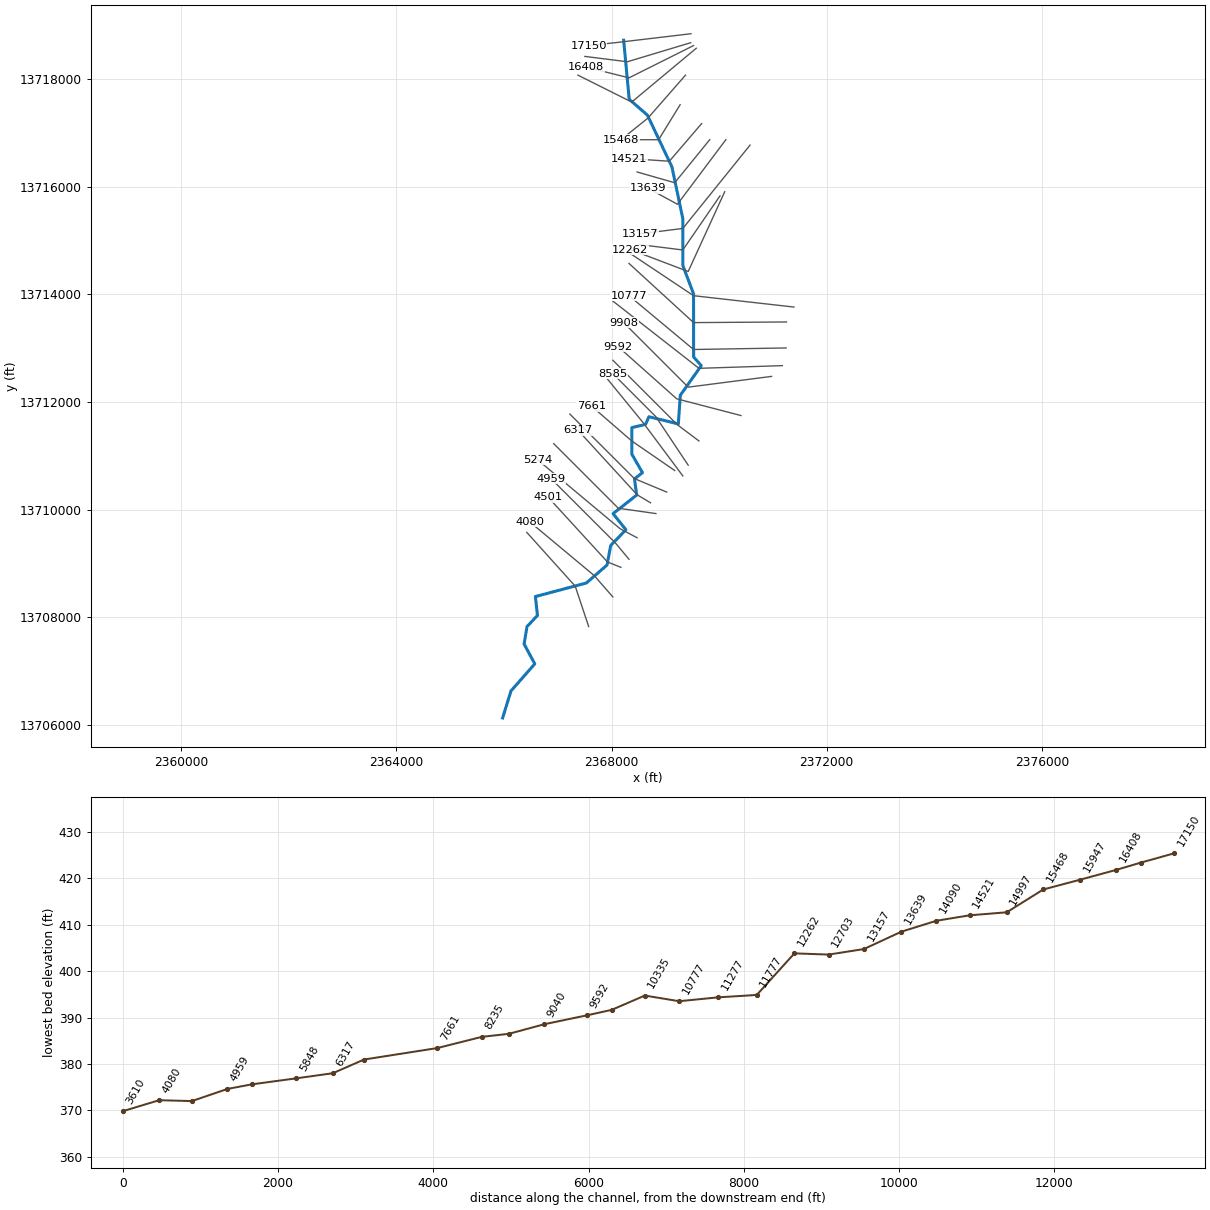
--- Stream0561.prj (project) ---

Proj Title=Stream0561 Base Level Engineering
Current Plan=p01
Default Exp/Contr=0.3,0.1
English Units
Geom File=g01
Flow File=f01
Plan File=p01
Y Axis Title=Elevation
X Axis Title(PF)=Main Channel Distance
X Axis Title(XS)=Station
BEGIN DESCRIPTION:
Stream0561
END DESCRIPTION:
DSS Export Rating Curves= 0
DSS Export Rating Curve Sorted= 0
DSS Export Volume Flow Curves= 0
DXF OffsetX= 0
DXF OffsetY= 0
DXF ScaleX= 1
DXF ScaleY= 10

--- Stream0561.p01 (plan) ---

Plan Title=Multiple Run
Short Identifier=Multiple
Geom File=g01
Flow File=f01
Subcritical Flow
K Sum by GR= 0
Std Step Tol= 0.01
Critical Tol= 0.01
Num of Std Step Trials= 20
Max Error Tol= 0.3
Flow Tol Ratio= 0.001
Split Flow NTrial= 30
Split Flow Tol= 0.02
Split Flow Ratio= 0.02
Log Output Level= 0
Friction Slope Method= 1
Unsteady Friction Slope Method= 2
Unsteady Bridges Friction Slope Method= 1
Parabolic Critical Depth
Global Vel Dist=  1 , 1 , 1
Global Log Level= 0
CheckData=True
Encroach Param= -1, 0, 0, 0
BEGIN DESCRIPTION:
Multiple Run
END DESCRIPTION:

--- Stream0561.f01 (steady flow) ---

Flow Title=Multiple
Number of Profiles=7
Profile Names=10-year,25-year,50-year,1pct_min,100-year,1pct_plu,500-year
River Rch & RM= Stream0561,Reach-1,17150
     719    1173    1587    1040    2075    4140    3512
River Rch & RM= Stream0561,Reach-1,15468
     862    1416    1924    1265    2525    5038    4309
River Rch & RM= Stream0561,Reach-1,11777
    1492    2516    3480    2324    4636    9251    8165
River Rch & RM= Stream0561,Reach-1,2730
    1647    2783    3855    2576    5140   10256    9065
Boundary for River Rch & Prof#=Stream0561,Reach-1,1
Up Type=0
Dn Type=3
Dn Slope=0.005
Boundary for River Rch & Prof#=Stream0561,Reach-1,2
Up Type=0
Dn Type=3
Dn Slope=0.005
Boundary for River Rch & Prof#=Stream0561,Reach-1,3
Up Type=0
Dn Type=3
Dn Slope=0.005
Boundary for River Rch & Prof#=Stream0561,Reach-1,4
Up Type=0
Dn Type=3
Dn Slope=0.005
Boundary for River Rch & Prof#=Stream0561,Reach-1,5
Up Type=0
Dn Type=3
Dn Slope=0.005
Boundary for River Rch & Prof#=Stream0561,Reach-1,6
Up Type=0
Dn Type=3
Dn Slope=0.005
Boundary for River Rch & Prof#=Stream0561,Reach-1,7
Up Type=0
Dn Type=3
Dn Slope=0.005

--- Stream0561.g01 (geometry) ---

Geom Title=Existing Conditions
Program Version=4.10

River Reach=Stream0561      ,Reach-1
Reach XY= 30
        2368225.       13718725.      2368328.75     13717626.55
      2368667.27      13717331.5      2369122.76     13716369.07
      2369324.48     13715409.78      2369326.05     13714535.43
      2369524.48     13714009.78      2369525.99     13712835.29
      2369668.42       13712675.      2369278.44     13712123.75
       2369241.8     13711591.42      2368694.76     13711725.04
      2368631.68     13711582.48      2368378.46     13711523.52
      2368376.98     13711030.67      2368574.67     13710685.87
      2368426.35     13710568.75      2368467.62     13710268.67
       2368028.1     13709923.35      2368268.02     13709624.79
      2367984.02     13709332.02      2367916.86     13708968.94
      2367531.73     13708634.15      2366584.01     13708382.02
      2366623.38     13708031.03      2366428.54     13707823.54
       2366374.5     13707499.96      2366573.04     13707130.89
      2366130.47     13706627.45        2365975.       13706125.

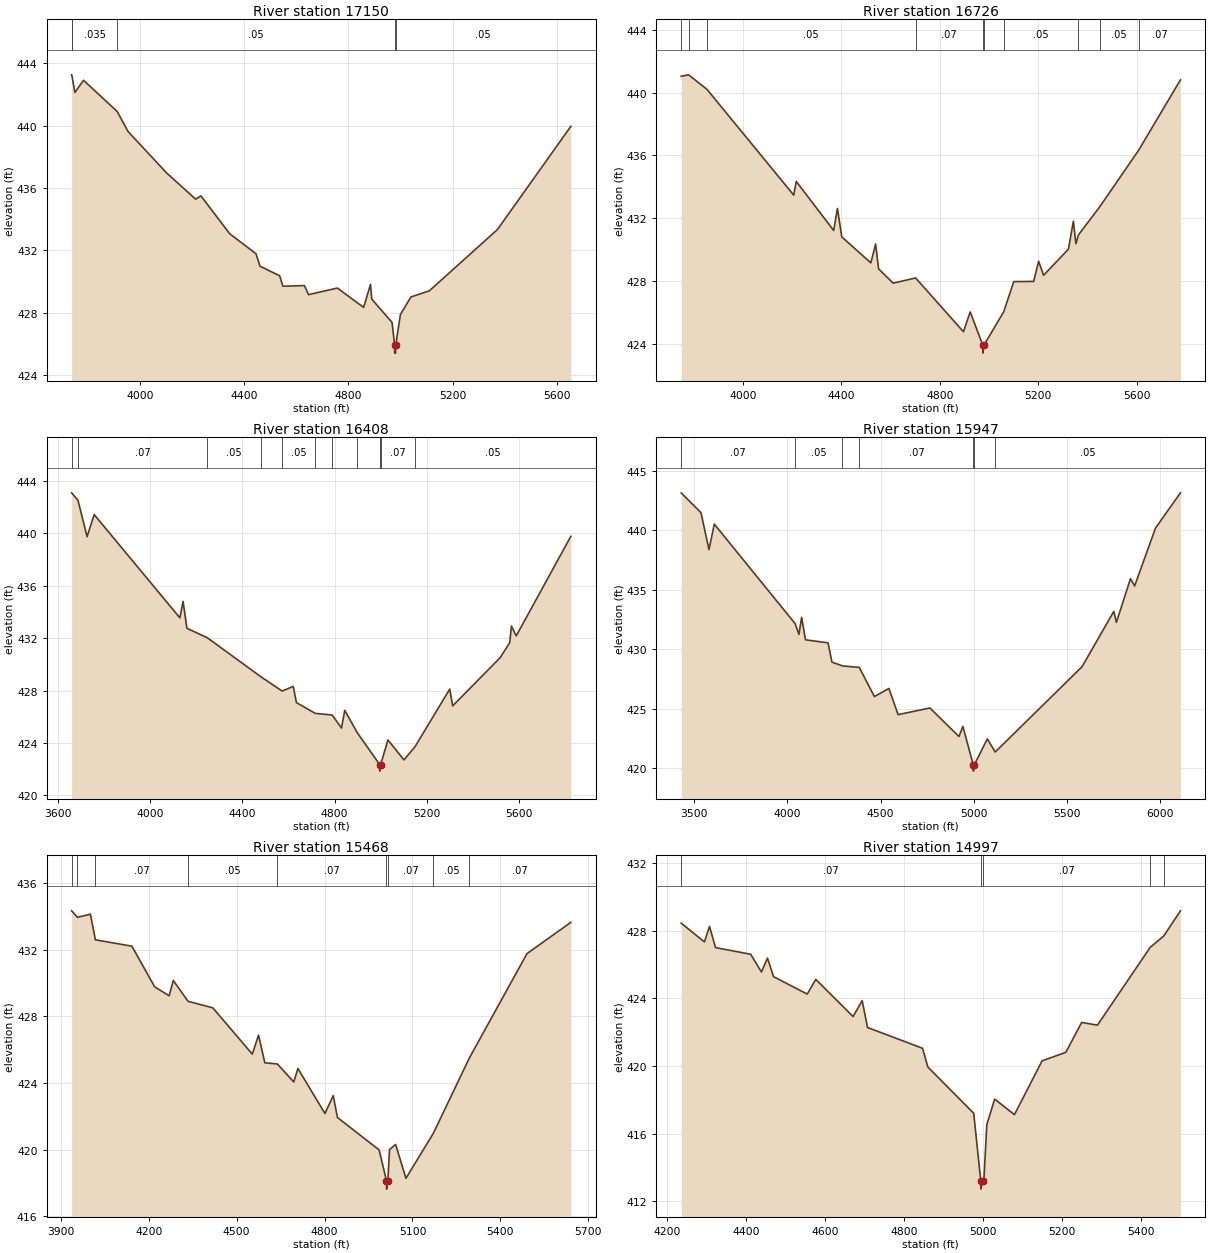
Type RM Length L Ch R = 1 ,17150   ,424,424,424
BEGIN DESCRIPTION:
Stream0561 36.0
END DESCRIPTION:
XS GIS Cut Line= 3
      2369477.48     13718845.13      2368159.81     13718688.88
      2367574.99       13718625.
#Sta/Elev= 30
  3738.5  443.25    3739  443.25  3751.1  442.12  3784.2   442.9  3913.4   440.9
  3954.7  439.62  4103.5  436.95  4214.3  435.28  4234.4  435.49  4345.2  433.06
  4445.9  431.78  4461.2  430.98  4536.5  430.37    4549   429.7  4631.7  429.74
  4647.3  429.16  4758.1  429.58  4858.8  428.34    4885  429.82    4890  428.87
  4967.8  427.38  4977.6  425.91  4977.8  425.41  4981.4  425.41  4981.7  425.91
  4999.8  427.88    5040  429.01  5110.5   429.4    5372  433.33  5653.7  439.95
#Mann= 5 ,-1 , 0
  3738.5     .07       0    3739    .035       0  3913.4     .05       0
  4977.6     .05       0  4981.7     .05       0
Bank Sta=4977.6,4981.7
XS Rating Curve= 0 ,0
Exp/Cntr=0.3,0.1

Type RM Length L Ch R = 1 ,16726   ,318,318,318
BEGIN DESCRIPTION:
XS7066
END DESCRIPTION:
XS GIS Cut Line= 3
      2369472.29     13718678.46      2368295.22      13718324.3
      2367503.57     13718423.26
#Sta/Elev= 30
  3750.4  441.04  3780.4  441.13  3854.8  440.21  4207.1  433.48  4217.5  434.35
  4369.4  431.23  4384.6  432.63  4402.4  430.82  4520.3  429.17  4539.7  430.37
  4551.7  428.79  4610.9  427.88  4702.1  428.21  4896.3  424.79  4923.7  426.05
    4975  423.93  4975.2  423.43  4979.2  423.93  5059.9  426.06  5100.7  427.98
  5181.4  427.99  5201.5  429.27  5221.7  428.38  5322.5  430.04  5342.6  431.82
  5352.9  430.39  5363.3  430.95  5449.4  432.73  5607.1  436.32  5777.4  440.81
#Mann= 10 ,-1 , 0
  3750.4    .035       0  3780.4     .07       0  3854.8     .05       0
  4702.1     .07       0    4975     .05       0  4979.2     .07       0
  5059.9     .05       0  5363.3     .07       0  5449.4     .05       0
  5607.1     .07       0
Bank Sta=4975,4979.2
XS Rating Curve= 0 ,0
Exp/Cntr=0.3,0.1

Type RM Length L Ch R = 1 ,16408   ,461,461,461
BEGIN DESCRIPTION:
Stream0561 35.0
END DESCRIPTION:
XS GIS Cut Line= 3
      2369524.99     13718624.99        2368325.       13718025.
      2367525.05     13718224.99
#Sta/Elev= 30
  3658.8   443.1  3686.4  442.53  3725.9  439.75  3756.6  441.44  4128.4  433.56
  4142.3  434.82  4159.1  432.76  4247.5  432.04  4481.8  429.04  4572.5  427.97
  4620.3  428.33  4634.3  427.09  4715.6  426.27  4789.5  426.14  4829.9  425.15
  4843.9   426.5    4898   424.8  4995.5  422.36  4995.8  421.86  4999.8  422.36
  5031.3  424.24  5100.9  422.72    5149  423.73  5299.4  428.12  5312.2  426.84
  5518.4  430.52  5559.6  431.66  5567.4  432.93    5588  432.18    5825  439.78
#Mann= 11 ,-1 , 0
  3658.8    .035       0  3686.4     .07       0  4247.5     .05       0
  4481.8     .07       0  4572.5     .05       0  4715.6     .07       0
  4789.5     .05       0    4898     .07       0  4995.5     .05       0
  4999.8     .07       0    5149     .05       0
Bank Sta=4995.5,4999.8
XS Rating Curve= 0 ,0
Exp/Cntr=0.3,0.1

Type RM Length L Ch R = 1 ,15947   ,479,479,479
BEGIN DESCRIPTION:
Stream0561 34.0
END DESCRIPTION:
XS GIS Cut Line= 3
      2369574.97     13718574.97        2368375.       13717575.
      2367375.04     13718074.98
#Sta/Elev= 30
  3430.2  443.15  3536.2  441.49  3579.2  438.39  3607.8  440.53  4041.7  432.16
  4062.1  431.26  4076.5  432.69  4097.3   430.8  4218.3  430.55  4239.2  428.93
  4295.4  428.61  4386.1  428.48    4467  426.03  4545.1  426.71  4594.5  424.51
  4765.1  425.07  4921.3  422.67  4942.1  423.53  4998.4  420.26  4998.7  419.76
  5002.7  420.26  5073.3  422.47  5115.9  421.37    5582  428.54  5752.5  433.19
  5766.4  432.27  5841.9  435.94  5864.3  435.33  5976.1  440.19  6110.2  443.16
#Mann= 7 ,-1 , 0
  3430.2     .07       0  4041.7     .05       0  4295.4    .035       0
  4386.1     .07       0  4998.4     .05       0  5002.7     .07       0
  5115.9     .05       0
Bank Sta=4998.4,5002.7
XS Rating Curve= 0 ,0
Exp/Cntr=0.3,0.1

Type RM Length L Ch R = 1 ,15468   ,471,471,471
BEGIN DESCRIPTION:
Stream0561 33.0
END DESCRIPTION:
XS GIS Cut Line= 3
      2369374.99     13718074.99        2368675.       13717275.
      2368175.01     13716875.01
#Sta/Elev= 30
  3937.1  434.33  3956.9  433.94  4001.2  434.13  4018.2  432.59  4142.6  432.21
  4220.4  429.77  4269.8  429.23    4284  430.15  4334.3   428.9  4418.8  428.51
  4553.5  425.73  4574.9  426.87  4596.3  425.21  4639.1  425.14    4695  424.06
  4709.2  424.87  4801.3  422.17  4829.7  423.24    4844  421.93  4986.3  419.98
  5011.4  418.13  5011.7  417.63  5016.1  418.13  5021.7     420  5042.5  420.31
  5077.7  418.28  5171.3  420.98  5294.5  425.51  5490.7  431.76  5640.4  433.64
#Mann= 9 ,-1 , 0
  3937.1     .07       0  3956.9     .05       0  4018.2     .07       0
  4334.3     .05       0  4639.1     .07       0  5011.4     .05       0
  5016.1     .07       0  5171.3     .05       0  5294.5     .07       0
Bank Sta=5011.4,5016.1
XS Rating Curve= 0 ,0
Exp/Cntr=0.3,0.1

Type RM Length L Ch R = 1 ,14997   ,476,476,476
BEGIN DESCRIPTION:
Stream0561 32.0
END DESCRIPTION:
XS GIS Cut Line= 3
      2369274.99     13717524.98        2368875.       13716875.
        2368375.       13716875.
#Sta/Elev= 30
  4236.5  428.46  4295.2  427.35    4308  428.27  4323.4  427.01  4412.2  426.62
  4439.4  425.57  4454.8  426.39  4470.2  425.29  4555.3  424.26    4577  425.13
  4671.3  422.93  4694.4  423.87    4708  422.28  4847.1  421.05  4860.6  419.94
  4976.6   417.2  4994.4  413.21  4994.7  412.71  4999.1  413.21  5002.2  413.21
  5009.7  416.53  5029.7  418.04  5079.7  417.12  5149.7  420.31  5209.7  420.81
  5249.7  422.58  5289.7  422.42  5423.3  427.03  5457.4   427.7  5499.7  429.19
#Mann= 5 ,-1 , 0
  4236.5     .07       0  4994.4     .05       0  4999.1     .07       0
  5423.3     .05       0  5457.4     .07       0
Bank Sta=4994.4,4999.1
XS Rating Curve= 0 ,0
Exp/Cntr=0.3,0.1

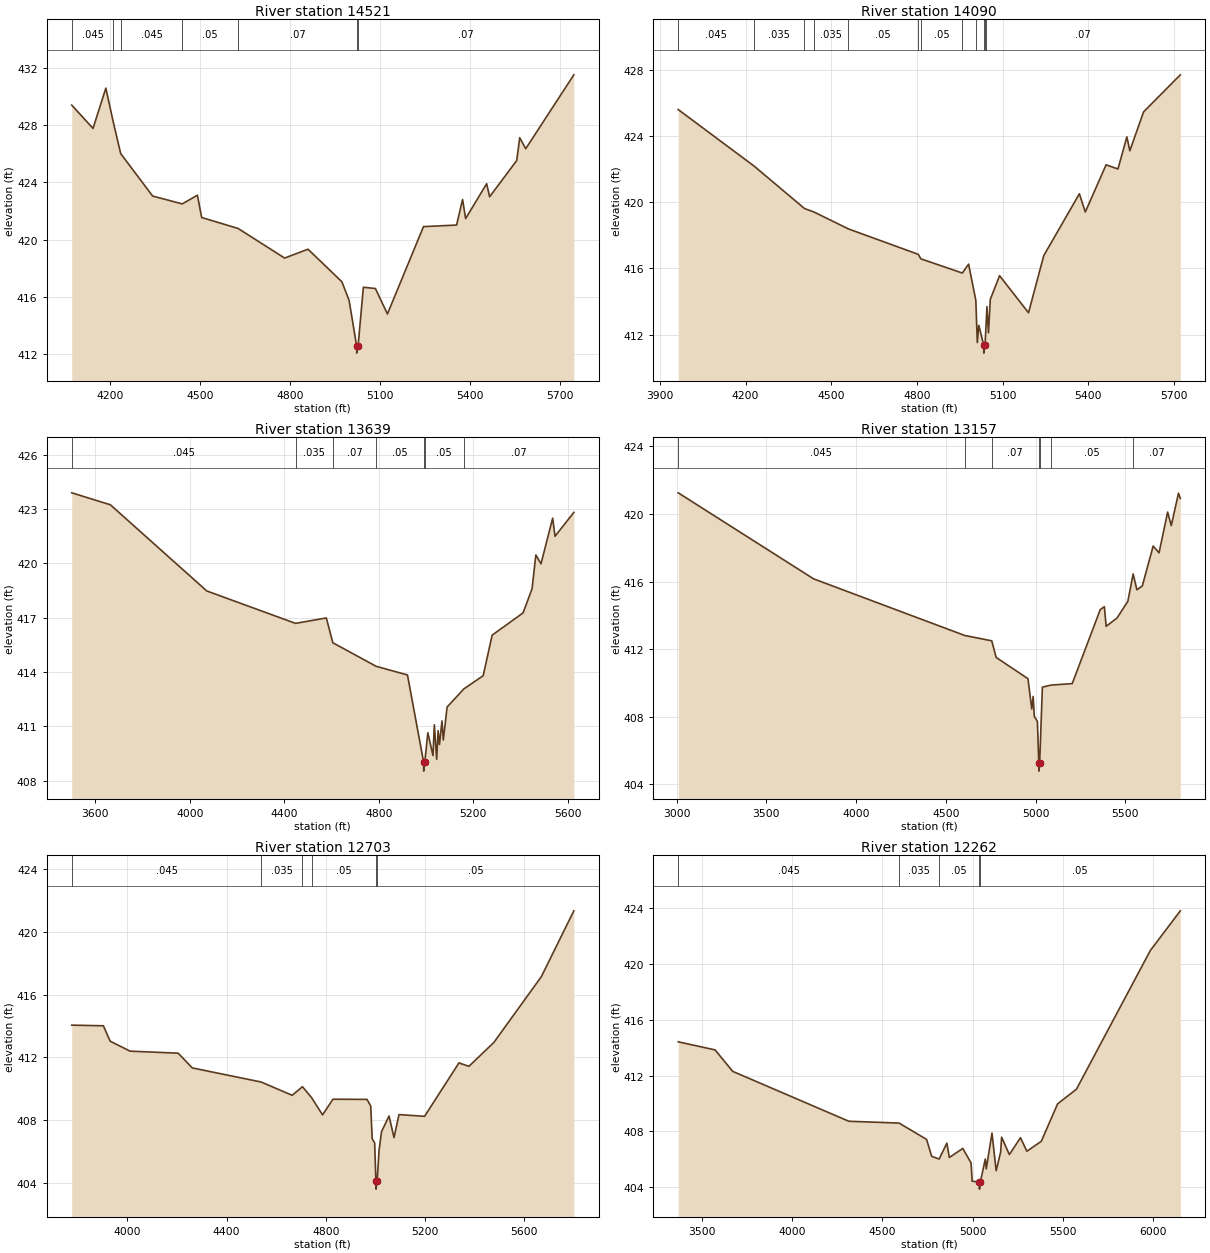
Type RM Length L Ch R = 1 ,14521   ,431,431,431
BEGIN DESCRIPTION:
Stream0561 31.0
END DESCRIPTION:
XS GIS Cut Line= 3
      2369675.02     13717175.03        2369075.       13716475.
      2368324.95       13716525.
#Sta/Elev= 30
  4073.1  429.41  4143.9  427.78  4186.7   430.6  4211.3  428.24  4236.2  426.02
  4342.6  423.05  4441.5   422.5  4491.9  423.11  4506.1  421.55  4627.7  420.78
  4782.7  418.71  4860.6  419.33  4973.7  417.05  4997.6  415.75  5022.8  412.56
  5023.1  412.06  5027.6  412.56  5045.2  416.67  5085.3  416.58  5125.4   414.8
  5245.6  420.91  5355.9  421.02  5375.9  422.81    5386  421.47  5456.1  423.91
  5466.1     423  5556.3  425.53  5566.4  427.13  5586.4  426.36  5746.8  431.53
#Mann= 7 ,-1 , 0
  4073.1    .045       0  4211.3    .035       0  4236.2    .045       0
  4441.5     .05       0  4627.7     .07       0  5022.8     .05       0
  5027.6     .07       0
Bank Sta=5022.8,5027.6
XS Rating Curve= 0 ,0
Exp/Cntr=0.3,0.1

Type RM Length L Ch R = 1 ,14090   ,451,451,451
BEGIN DESCRIPTION:
Stream0561 30.0
END DESCRIPTION:
XS GIS Cut Line= 3
      2369825.02     13716875.02        2369175.       13716075.
      2368475.02       13716275.
#Sta/Elev= 30
    3964   425.6  4229.4  422.19  4406.3  419.62  4439.4  419.41  4559.8  418.39
  4804.9  416.85  4813.9  416.58  4959.2  415.72  4981.2  416.26  5006.5  414.07
  5011.7  411.52  5016.9  412.56    5034  411.38  5034.4  410.88  5038.8  411.38
  5041.3  412.24  5045.5  413.69  5050.7  412.11  5057.2  414.13  5089.7  415.56
  5191.1  413.32  5244.4  416.77  5369.2  420.51    5390  419.41  5462.8  422.26
  5504.4  422.01  5535.6  423.95    5546  423.11  5594.1  425.46  5722.8   427.7
#Mann= 12 ,-1 , 0
    3964    .045       0  4229.4    .035       0  4406.3    .045       0
  4439.4    .035       0  4559.8     .05       0  4804.9     .07       0
  4813.9     .05       0  4959.2     .07       0  5006.5     .05       0
    5034     .05       0  5038.8     .05       0  5041.3     .07       0
Bank Sta=5034,5038.8
XS Rating Curve= 0 ,0
Exp/Cntr=0.3,0.1

Type RM Length L Ch R = 1 ,13639   ,482,482,482
BEGIN DESCRIPTION:
Stream0561 29.0
END DESCRIPTION:
XS GIS Cut Line= 3
        2370125.       13716875.        2369225.       13715675.
        2368675.       13715975.
#Sta/Elev= 30
    3500  423.89  3663.5  423.23  4071.9  418.47  4447.7  416.68  4578.1  416.98
  4605.7  415.61    4789  414.31  4921.9  413.83  4990.2  409.02  4990.6  408.52
  4995.2  409.02  5008.1  410.64  5029.9  409.38  5035.6  411.08  5045.6  409.17
  5051.7  410.76  5057.4  409.99  5067.9  411.29  5073.6  410.24  5089.7  412.06
  5160.5  413.06  5242.5  413.79  5280.5  416.03  5411.5  417.26  5449.5  418.59
  5465.6  420.46  5487.4  419.97  5536.8  422.49  5546.8  421.49  5626.5  422.81
#Mann= 7 ,-1 , 0
    3500    .045       0  4447.7    .035       0  4605.7     .07       0
    4789     .05       0  4990.2     .05       0  4995.2     .05       0
  5160.5     .07       0
Bank Sta=4990.2,4995.2
XS Rating Curve= 0 ,0
Exp/Cntr=0.3,0.1

Type RM Length L Ch R = 1 ,13157   ,454,454,454
BEGIN DESCRIPTION:
Stream0561 28.0
END DESCRIPTION:
XS GIS Cut Line= 3
        2370575.       13716775.        2369325.       13715225.
      2368524.96     13715124.99
#Sta/Elev= 30
  3008.9  421.25    3763  416.16  4604.5  412.81  4755.9  412.49  4780.2  411.51
  4957.7  410.25  4978.6  408.46  4986.5   409.2  4992.9  408.02  5010.2  407.72
  5017.8  405.28  5018.2  404.78  5022.8  405.28  5037.9  409.75  5085.5  409.87
  5204.2  409.96  5360.4  414.34  5383.1  414.51  5393.2  413.35  5453.6  413.84
  5514.1  414.83  5543.7  416.45  5564.5  415.51  5594.7  415.74  5655.2   418.1
  5687.9   417.7  5735.8  420.11    5756  419.31  5796.3  421.23  5806.4  420.92
#Mann= 7 ,-1 , 0
  3008.9    .045       0  4604.5    .035       0  4755.9     .07       0
  5017.8     .05       0  5022.8     .07       0  5085.5     .05       0
  5543.7     .07       0
Bank Sta=5017.8,5022.8
XS Rating Curve= 0 ,0
Exp/Cntr=0.3,0.1

Type RM Length L Ch R = 1 ,12703   ,441,441,441
BEGIN DESCRIPTION:
Stream0561 27.0
END DESCRIPTION:
XS GIS Cut Line= 3
       2370015.7     13715830.25        2369325.       13714825.
      2368524.99       13714925.
#Sta/Elev= 30
  3775.2  414.06  3902.9  414.02  3929.9  413.04  4010.4   412.4  4204.6  412.27
  4261.4  411.33  4539.2  410.43  4664.7  409.58    4706  410.13    4743  409.43
  4787.2  408.33  4829.1  409.33  4966.5  409.32  4981.4   408.9  4987.4  406.81
  4997.4  406.54  5002.4  404.09  5002.8  403.59  5007.4  404.09    5015  406.05
  5025.1  407.26  5055.3  408.26  5075.5  406.88  5095.6  408.35  5198.9  408.24
  5337.5  411.65  5377.8  411.43  5478.6  412.96  5670.1  417.16  5801.1  421.36
#Mann= 6 ,-1 , 0
  3775.2    .045       0  4539.2    .035       0    4706     .07       0
    4743     .05       0  5002.4     .05       0  5007.4     .05       0
Bank Sta=5002.4,5007.4
XS Rating Curve= 0 ,0
Exp/Cntr=0.3,0.1

Type RM Length L Ch R = 1 ,12262   ,485,485,485
BEGIN DESCRIPTION:
Stream0561 26.0
END DESCRIPTION:
XS GIS Cut Line= 3
      2370103.93     13715908.07        2369425.       13714425.
      2368349.57     13714833.26
#Sta/Elev= 30
  3369.2  414.42  3573.4  413.84    3671   412.3  4314.3  408.72  4592.4  408.59
  4744.9  407.42  4773.4   406.2  4814.8  406.01  4857.3  407.15    4871  406.12
  4945.5  406.77  4991.5  405.73  4997.5  404.42  5037.6  404.35    5038  403.85
  5042.6  404.35  5070.3  406.01  5075.6   405.3  5107.3  407.87  5130.5  405.17
  5155.3  406.51  5160.7  407.58  5203.5  406.33  5265.2  407.54  5300.6  406.57
  5380.3  407.28  5470.9  409.97  5575.2  411.02  5984.4  420.97  6150.6  423.82
#Mann= 5 ,-1 , 0
  3369.2    .045       0  4592.4    .035       0  4814.8     .05       0
  5037.6     .05       0  5042.6     .05       0
Bank Sta=5037.6,5042.6
XS Rating Curve= 0 ,0
Exp/Cntr=0.3,0.1

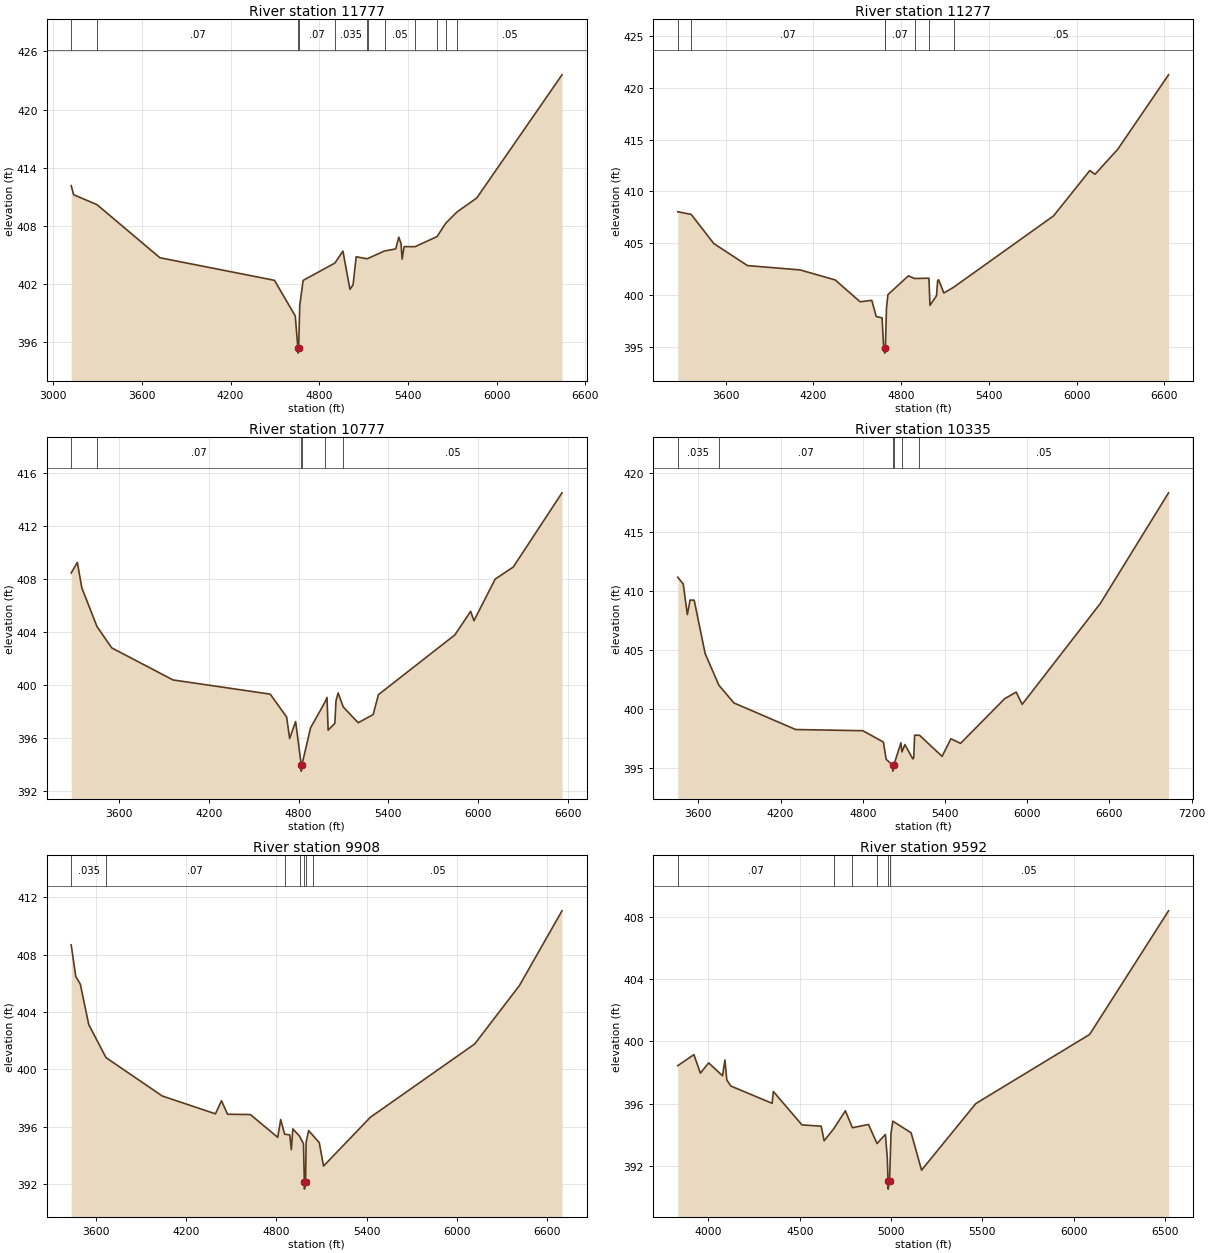
Type RM Length L Ch R = 1 ,11777   ,500,500,500
BEGIN DESCRIPTION:
Stream0561 25.0
END DESCRIPTION:
XS GIS Cut Line= 3
      2371391.49     13713763.93        2369525.       13713975.
        2368325.       13714775.
#Sta/Elev= 30
    3122  412.16  3138.6  411.22  3296.3   410.2  3722.3  404.72  4497.2  402.39
  4638.1  398.71  4655.7  395.38  4656.1  394.88  4660.8  395.38  4668.3  399.81
  4691.2  402.38  4905.8  404.17  4960.5  405.41  5007.9  401.46  5028.9  401.92
    5050  404.82  5120.4  404.62  5126.9  404.63  5241.7  405.42  5317.4  405.63
  5338.4  406.84  5353.4  406.19  5360.9  404.58  5374.5  405.87  5447.8  405.86
  5596.9   406.9  5656.5  408.29  5732.8  409.45  5865.7  410.88  6442.6  423.59
#Mann= 12 ,-1 , 0
    3122     .05       0  3296.3     .07       0  4655.7    .035       0
  4660.8     .07       0  4905.8    .035       0  5120.4     .05       0
  5126.9    .035       0  5241.7     .05       0  5447.8     .07       0
  5596.9     .05       0  5656.5     .07       0  5732.8     .05       0
Bank Sta=4655.7,4660.8
XS Rating Curve= 0 ,0
Exp/Cntr=0.3,0.1

Type RM Length L Ch R = 1 ,11277   ,500,500,500
BEGIN DESCRIPTION:
Stream0561 24.0
END DESCRIPTION:
XS GIS Cut Line= 3
      2371251.36     13713486.69        2369525.       13713475.
      2368324.99     13714575.01
#Sta/Elev= 30
  3273.6  408.02  3365.2  407.77    3520  404.95    3750  402.82    4110   402.4
    4350  401.43    4520  399.32    4600  399.46    4630   397.9    4670  397.77
    4680  395.18  4687.4  394.86  4687.8  394.36  4692.6  394.86    4700  398.67
    4710  400.01    4850  401.83  4891.8  401.57  4990.2   401.6  4997.5  398.98
  5042.2   399.9  5049.6  401.33  5056.4  401.45  5092.2  400.17  5160.7  400.74
    5842  407.62  6089.9     412  6125.6  411.64    6281  414.06  6627.9  421.25
#Mann= 7 ,-1 , 0
  3273.6     .05       0  3365.2     .07       0  4687.4     .05       0
  4692.6     .07       0  4891.8    .035       0  4990.2     .07       0
  5160.7     .05       0
Bank Sta=4687.4,4692.6
XS Rating Curve= 0 ,0
Exp/Cntr=0.3,0.1

Type RM Length L Ch R = 1 ,10777   ,442,442,442
BEGIN DESCRIPTION:
Stream0561 23.0
END DESCRIPTION:
XS GIS Cut Line= 3
      2371246.14     13713003.86        2369525.       13712975.
      2368325.02     13713974.98
#Sta/Elev= 30
  3278.6  408.48  3319.7  409.28  3349.7  407.36  3451.1  404.44  3549.8  402.83
  3959.8  400.41  4609.9  399.34  4719.9  397.61  4739.9  395.99  4779.9  397.27
  4817.4  394.03  4817.8  393.53  4822.6  394.03    4880   396.8  4975.7  398.72
    4990  399.09  4997.5  396.62  5042.3  397.14  5050.1  398.84  5064.4  399.43
  5098.9  398.37  5198.5  397.18  5298.7   397.8  5333.9   399.3  5845.4  403.81
  5950.9  405.59    5973  404.88  6114.9  408.02    6236  408.93    6562  414.53
#Mann= 6 ,-1 , 0
  3278.6    .035       0  3451.1     .07       0  4817.4    .035       0
  4822.6     .07       0  4975.7    .035       0  5098.9     .05       0
Bank Sta=4817.4,4822.6
XS Rating Curve= 0 ,0
Exp/Cntr=0.3,0.1

Type RM Length L Ch R = 1 ,10335   ,427,427,427
BEGIN DESCRIPTION:
Stream0561 22.0
END DESCRIPTION:
XS GIS Cut Line= 3
      2371175.02       13712675.        2369625.       13712625.
      2368025.02     13713874.99
#Sta/Elev= 30
  3449.6  411.16  3489.6  410.59  3519.7     408  3539.7  409.23  3569.7  409.21
  3649.7  404.69  3749.7  402.02  3859.8  400.52  4310.1  398.27  4800.3  398.17
  4950.4  397.21  4970.4  395.75  5018.1  395.25  5018.6  394.75  5026.1  395.25
  5078.2  397.15  5085.5  396.37  5107.2     397    5165  395.78  5171.4  395.87
  5178.1  397.79  5213.3  397.79  5378.5     396  5442.7  397.49  5513.2   397.1
  5834.3  400.87  5919.3  401.44  5962.7   400.4  6532.5  408.93  7030.8   418.3
#Mann= 6 ,-1 , 0
  3449.6    .035       0  3749.7     .07       0  5018.1     .05       0
  5026.1     .07       0  5085.5    .035       0  5213.3     .05       0
Bank Sta=5018.1,5026.1
XS Rating Curve= 0 ,0
Exp/Cntr=0.3,0.1

Type RM Length L Ch R = 1 ,9908    ,316,316,316
BEGIN DESCRIPTION:
Stream0561 21.0
END DESCRIPTION:
XS GIS Cut Line= 3
      2370974.98       13712475.        2369425.       13712275.
      2368224.99     13713475.01
#Sta/Elev= 30
  3437.2  408.69  3467.4  406.48  3497.7  405.95  3553.8  403.13  3668.1  400.83
  4042.2  398.15  4395.1  396.91  4435.4  397.82  4475.7  396.88    4627  396.86
  4809.1  395.27  4828.6  396.51  4854.7  395.49  4889.1  395.44  4899.2  394.41
  4909.3  395.86  4953.6  395.36  4979.9  394.82  4985.8  392.16  4986.3  391.66
    4994  392.16  4997.5  394.93  5014.2  395.74  5043.6  395.39  5084.9   394.9
  5113.2  393.27  5424.3  396.67  6117.3  401.78  6414.2  405.85  6697.1  411.06
#Mann= 7 ,-1 , 0
  3437.2    .035       0  3668.1     .07       0  4854.7    .035       0
  4953.6     .07       0  4985.8     .05       0    4994     .07       0
  5043.6     .05       0
Bank Sta=4985.8,4994
XS Rating Curve= 0 ,0
Exp/Cntr=0.3,0.1

Type RM Length L Ch R = 1 ,9592    ,552,552,552
BEGIN DESCRIPTION:
Stream0561 20.0
END DESCRIPTION:
XS GIS Cut Line= 3
      2370405.04     13711747.47      2369210.97     13712058.96
        2368125.       13713025.
#Sta/Elev= 30
  3831.7  398.44  3920.3  399.15  3955.6  397.96  4001.2  398.62    4077  397.79
  4090.1  398.81  4100.4  397.52  4122.7  397.13  4348.5  396.02  4355.2  396.78
  4511.9  394.63  4617.2  394.55  4633.4  393.61  4685.6  394.38  4749.6  395.54
  4788.2  394.45  4876.2  394.66    4923  393.43  4968.6  394.02  4978.9  392.59
  4983.2     391  4983.7   390.5  4991.4     391  4999.6  394.11  5009.9  394.87
  5109.8  394.12  5166.7  391.72  5463.5     396  6087.3  400.45  6519.2   408.4
#Mann= 6 ,-1 , 0
  3831.7     .07       0  4685.6    .035       0  4788.2     .07       0
    4923     .05       0  4983.2     .05       0  4991.4     .05       0
Bank Sta=4983.2,4991.4
XS Rating Curve= 0 ,0
Exp/Cntr=0.3,0.1

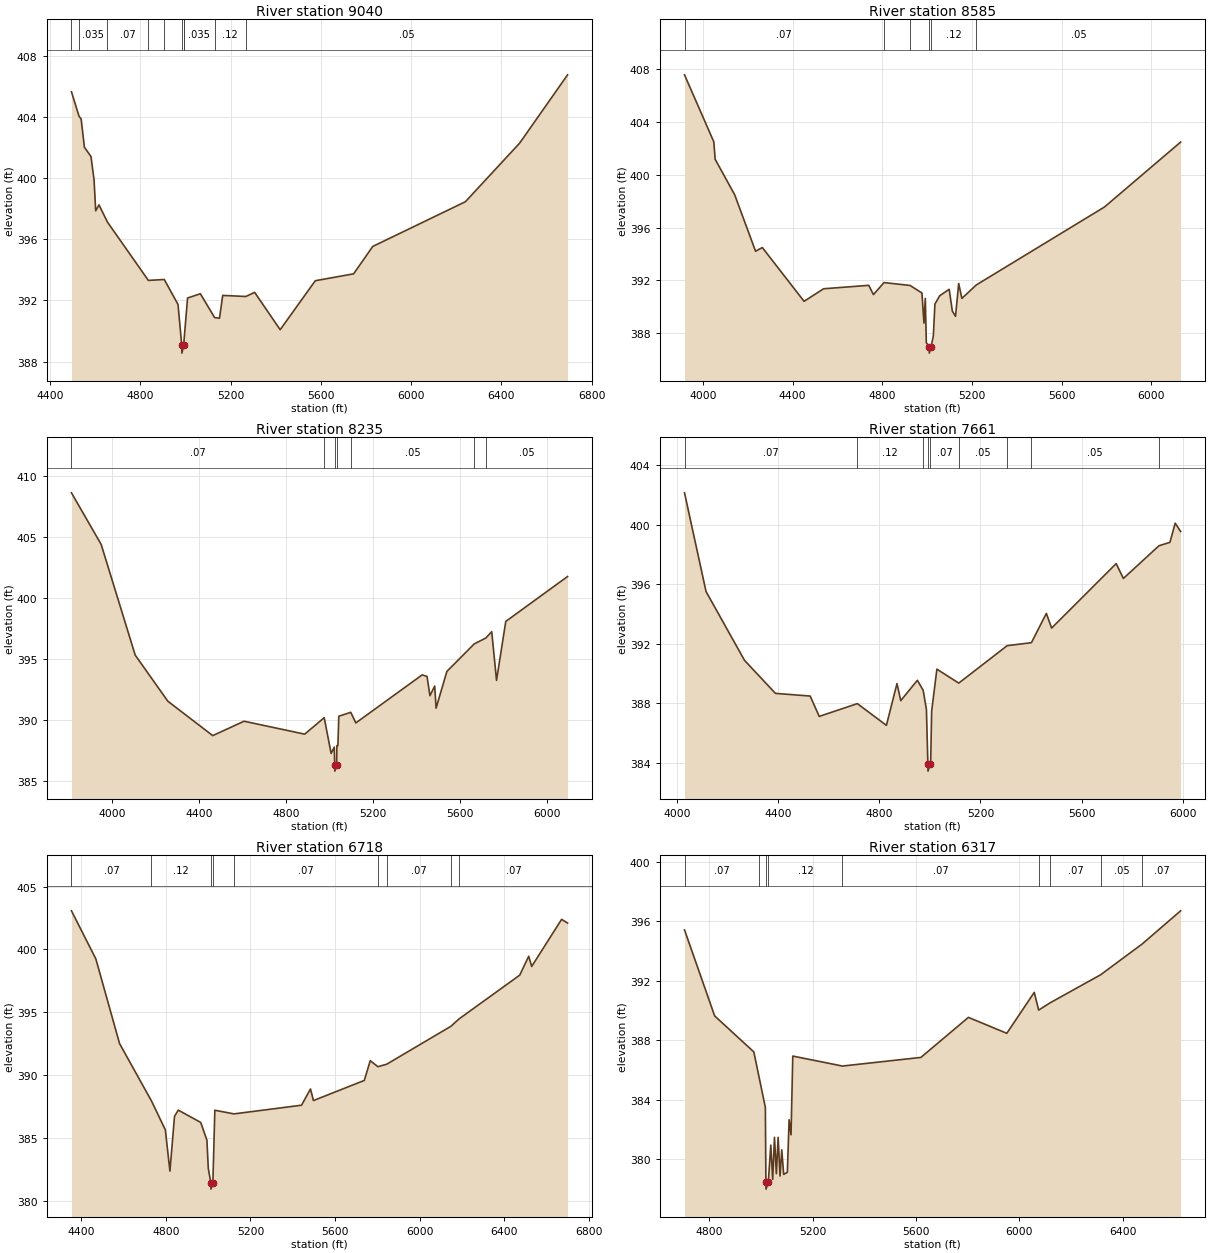
Type RM Length L Ch R = 1 ,9040    ,455,455,455
BEGIN DESCRIPTION:
Stream0561 19.0
END DESCRIPTION:
XS GIS Cut Line= 3
      2369625.04     13711274.97        2369225.       13711575.
        2368025.       13712775.
#Sta/Elev= 30
  4495.7  405.63  4529.3  404.03  4538.5  403.86    4553  402.01  4582.2   401.4
  4595.7  399.88    4603  397.86  4617.6  398.24  4655.1  397.12  4836.3  393.31
  4906.7  393.37  4967.6  391.74  4984.2  389.06  4984.7  388.56  4992.8  389.06
  4994.3  389.41  5009.9  392.16  5066.5  392.44  5129.8  390.88  5151.3  390.84
  5165.5  392.33  5268.1  392.26  5306.9  392.53    5420  390.09  5575.6  393.29
  5745.3  393.74  5830.1  395.53  6240.3  398.45  6480.7  402.28  6692.8  406.74
#Mann= 10 ,-1 , 0
  4495.7     .07       0  4529.3    .035       0  4655.1     .07       0
  4836.3    .035       0  4906.7     .07       0  4984.2    .035       0
  4992.8     .07       0  4994.3    .035       0  5129.8     .12       0
  5268.1     .05       0
Bank Sta=4984.2,4992.8
XS Rating Curve= 0 ,0
Exp/Cntr=0.3,0.1

Type RM Length L Ch R = 1 ,8585    ,350,350,350
BEGIN DESCRIPTION:
Stream0561 18.0
END DESCRIPTION:
XS GIS Cut Line= 3
      2369425.02     13710824.97        2368825.       13711725.
      2368024.98     13712525.02
#Sta/Elev= 30
  3917.7  407.56  4048.4  402.49  4054.4  401.17  4141.6  398.48  4234.7  394.21
  4264.8  394.49  4451.1  390.42  4538.2  391.37  4739.5  391.63  4760.5  390.93
  4807.8  391.84  4923.9  391.62  4976.9  391.05  4985.9  388.77  4991.9  390.64
  4996.4  387.29  5009.2     387  5009.7   386.5  5017.8     387  5027.7  387.79
  5034.8  390.21    5056  390.84  5098.4  391.33  5112.5  389.68  5126.7  389.29
  5140.8  391.77    5155  390.64  5219.4  391.66  5791.4  397.56  6130.8  402.47
#Mann= 6 ,-1 , 0
  3917.7     .07       0  4807.8    .035       0  4923.9     .12       0
  5009.2     .05       0  5017.8     .12       0  5219.4     .05       0
Bank Sta=5009.2,5017.8
XS Rating Curve= 0 ,0
Exp/Cntr=0.3,0.1

Type RM Length L Ch R = 1 ,8235    ,574,574,574
BEGIN DESCRIPTION:
Stream0561 17.0
END DESCRIPTION:
XS GIS Cut Line= 3
      2369324.99     13710625.01      2368593.16     13711607.28
        2367925.       13712425.
#Sta/Elev= 30
  3814.1  408.65  3950.7  404.42  4107.1  395.35  4257.2  391.57  4463.6  388.75
  4607.5  389.93  4886.5  388.87  4976.1  390.22  5007.9  387.29  5022.5  387.81
  5024.4  386.34  5024.9  385.84  5033.1  386.34  5034.5  387.93    5039  387.93
  5043.3  390.34  5098.2  390.66  5121.5  389.79  5426.6  393.73  5448.9   393.6
  5462.2  392.02  5484.1  392.81  5490.5     391  5540.1  394.01  5665.4  396.26
  5719.2  396.75  5746.3  397.27  5768.4  393.28  5810.9  398.11    6095  401.79
#Mann= 7 ,-1 , 0
  3814.1     .07       0  4976.1    .035       0  5024.4    .035       0
  5033.1    .035       0  5098.2     .05       0  5665.4    .035       0
  5719.2     .05       0
Bank Sta=5024.4,5033.1
XS Rating Curve= 0 ,0
Exp/Cntr=0.3,0.1

Type RM Length L Ch R = 1 ,7661    ,943,943,943
BEGIN DESCRIPTION:
Stream0561 16.0
END DESCRIPTION:
XS GIS Cut Line= 3
      2369175.01     13710724.99        2368375.       13711275.
      2367625.01     13711924.99
#Sta/Elev= 30
  4028.7  402.14  4113.9   395.5  4266.2  390.87  4388.6  388.65    4526  388.47
  4561.8   387.1  4712.6  387.96  4827.7   386.5  4869.6  389.31  4884.5  388.16
  4950.2  389.53  4973.1  388.86    4986  387.58  4991.8  383.92  4992.3  383.42
  5001.2  383.92  5002.8  383.92  5006.7  387.45  5027.5  390.28    5114  389.34
  5305.8  391.86  5401.6  392.06  5460.7  394.03  5481.5  393.04    5737  397.38
  5765.5  396.38  5906.4  398.58  5949.8  398.81  5970.6   400.1    5992  399.54
#Mann= 9 ,-1 , 0
  4028.7     .07       0  4712.6     .12       0  4973.1     .07       0
  4991.8     .05       0  5001.2     .07       0    5114     .05       0
  5305.8     .07       0  5401.6     .05       0  5906.4     .07       0
Bank Sta=4991.8,5001.2
XS Rating Curve= 0 ,0
Exp/Cntr=0.3,0.1

Type RM Length L Ch R = 1 ,6718    ,401,401,401
BEGIN DESCRIPTION:
Stream0561 15.0
END DESCRIPTION:
XS GIS Cut Line= 3
      2369024.97     13710325.01        2368425.       13710575.
      2367225.02     13711774.98
#Sta/Elev= 30
  4353.4  403.07  4468.7  399.25  4580.9  392.52  4731.9  387.96  4797.5  385.66
  4819.2  382.38  4840.9  386.74  4858.7  387.23  4964.9  386.25  4994.2  384.84
  5000.7   382.6  5012.8  381.45  5013.3  380.95  5022.3  381.45  5031.7  387.22
  5122.4  386.93  5441.8  387.62  5484.2  388.91  5498.3  387.99  5738.8  389.59
    5767  391.16  5803.1  390.68    5845  390.88  6148.3  393.89  6187.1  394.48
  6474.2  397.96  6516.6  399.46  6530.7  398.65  6672.1  402.39  6700.4   402.1
#Mann= 9 ,-1 , 0
  4353.4     .07       0  4731.9     .12       0  5012.8     .05       0
  5022.3     .12       0  5122.4     .07       0  5803.1     .05       0
    5845     .07       0  6148.3     .05       0  6187.1     .07       0
Bank Sta=5012.8,5022.3
XS Rating Curve= 0 ,0
Exp/Cntr=0.3,0.1

Type RM Length L Ch R = 1 ,6317    ,469,469,469
BEGIN DESCRIPTION:
Stream0561 14.0
END DESCRIPTION:
XS GIS Cut Line= 3
        2368725.       13710125.        2368475.       13710275.
      2367375.02     13711474.97
#Sta/Elev= 30
  4704.6  395.42  4821.2  389.64  4972.8  387.22  4992.3  385.59  5017.4  383.49
  5019.5   378.5    5020     378    5029   378.5  5038.4  380.96  5045.8  378.66
  5052.6  381.48    5060  379.04  5066.8  381.48  5074.2  378.88  5080.9  380.64
  5088.3  378.99  5102.5  379.13  5109.3  382.66  5116.7  381.65  5123.5  386.94
  5315.6  386.27  5619.2  386.85    5803  389.54  5951.6  388.47  6057.7  391.22
  6074.8  390.03  6120.3  390.53  6314.3   392.4  6475.2  394.47    6624   396.7
#Mann= 9 ,-1 , 0
  4704.6     .07       0  4992.3     .12       0  5019.5     .05       0
    5029     .12       0  5315.6     .07       0  6074.8     .05       0
  6120.3     .07       0  6314.3     .05       0  6475.2     .07       0
Bank Sta=5019.5,5029
XS Rating Curve= 0 ,0
Exp/Cntr=0.3,0.1

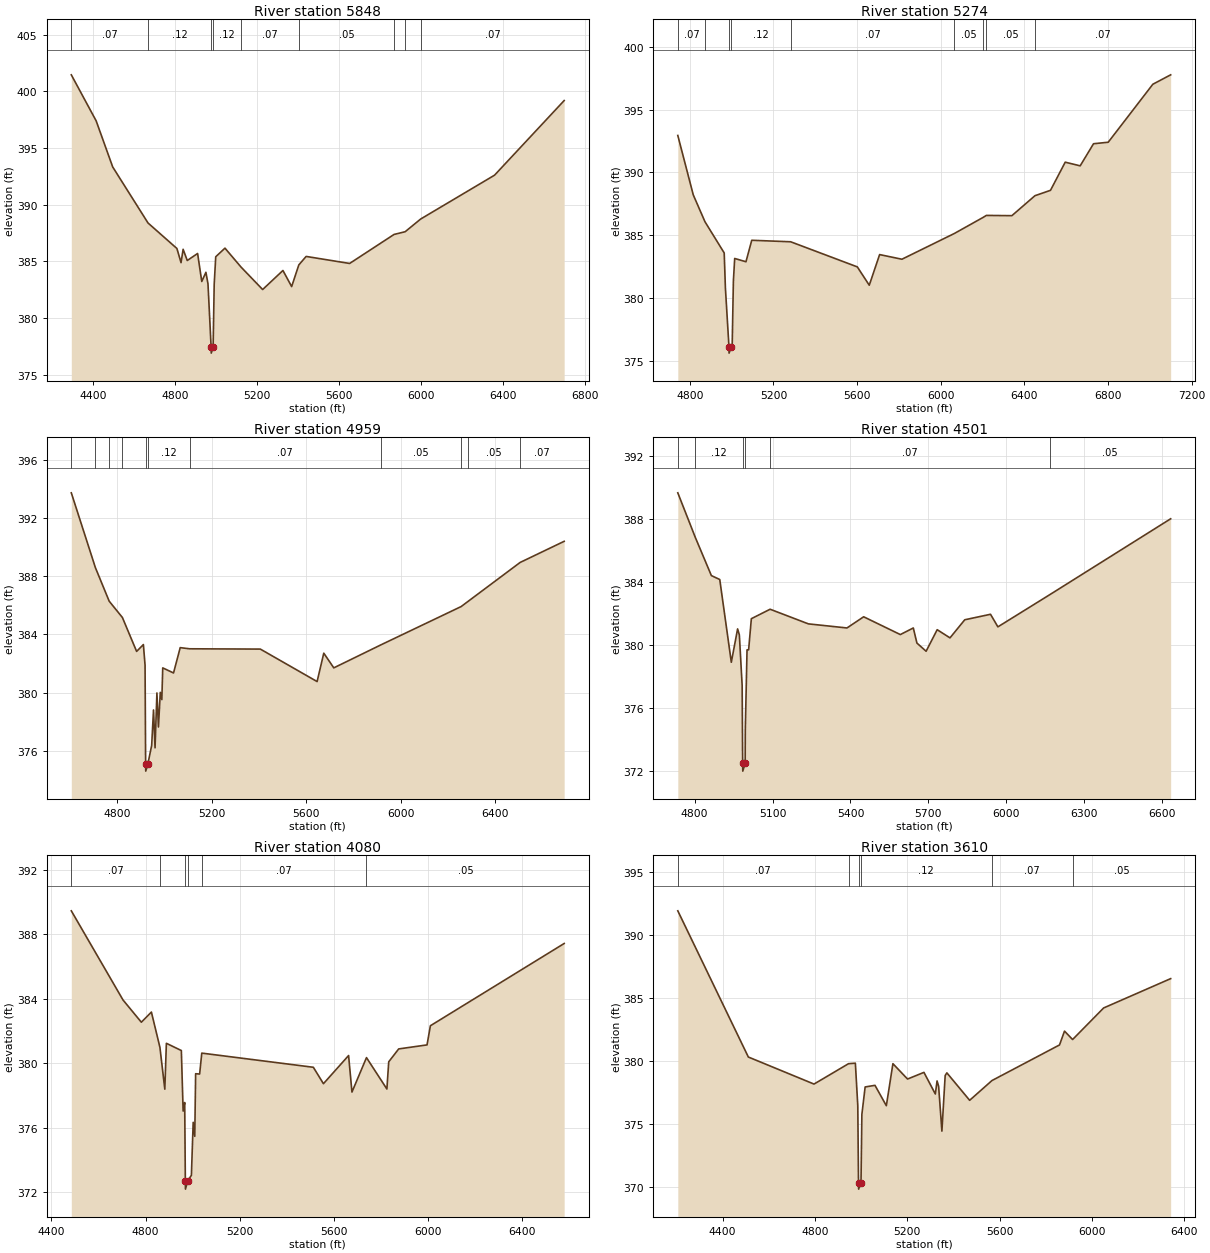
Type RM Length L Ch R = 1 ,5848    ,574,574,574
BEGIN DESCRIPTION:
Stream0561 13.0
END DESCRIPTION:
XS GIS Cut Line= 3
      2368824.95     13709925.01        2368125.       13710025.
      2366925.01     13711224.99
#Sta/Elev= 30
  4293.2  401.45  4414.4  397.39  4495.2  393.32  4667.4  388.38  4808.3  386.13
  4828.5  384.88  4838.6  386.06  4858.8  385.07  4909.3  385.69  4929.5  383.22
  4949.8  384.03  4959.9  383.01  4975.3   377.4  4975.8   376.9  4984.9   377.4
  4990.2  382.97  4997.7   385.4  5042.7  386.16  5121.2  384.49  5226.5  382.51
  5325.5  384.19    5368  382.77  5402.9  384.68  5438.7  385.43  5650.8  384.81
  5867.6  387.37  5921.7  387.61  5997.4  388.73  6357.9   392.6  6697.3  399.18
#Mann= 9 ,-1 , 0
  4293.2     .07       0  4667.4     .12       0  4975.3     .05       0
  4984.9     .12       0  5121.2     .07       0  5402.9     .05       0
  5867.6     .07       0  5921.7     .05       0  5997.4     .07       0
Bank Sta=4975.3,4984.9
XS Rating Curve= 0 ,0
Exp/Cntr=0.3,0.1

Type RM Length L Ch R = 1 ,5274    ,315,315,315
BEGIN DESCRIPTION:
Stream0561 12.0
END DESCRIPTION:
XS GIS Cut Line= 3
      2368474.96     13709475.02      2368157.05     13709644.81
      2366625.01     13710924.99
#Sta/Elev= 30
  4742.4  392.94  4816.3  388.21  4872.2  386.07  4964.3  383.58    4970   380.8
  4987.1   376.1  4987.6   375.6  4996.7   376.1  5002.6  376.33  5008.2  381.33
  5014.4  383.14  5068.4  382.88    5096  384.59  5282.2  384.47  5600.8  382.47
    5658  381.01  5707.5  383.45  5814.2  383.08  6064.8  385.13  6201.2   386.4
    6218  386.57    6340  386.55  6450.3  388.14  6524.7  388.57    6595  390.81
  6666.6  390.52  6730.4  392.28  6800.7   392.4  7014.1  397.02  7099.3  397.77
#Mann= 9 ,-1 , 0
  4742.4     .07       0  4872.2     .12       0  4987.1     .05       0
  4996.7     .12       0  5282.2     .07       0  6064.8     .05       0
  6201.2     .07       0    6218     .05       0  6450.3     .07       0
Bank Sta=4987.1,4996.7
XS Rating Curve= 0 ,0
Exp/Cntr=0.3,0.1

Type RM Length L Ch R = 1 ,4959    ,458,458,458
BEGIN DESCRIPTION:
Stream0561 11.0
END DESCRIPTION:
XS GIS Cut Line= 3
      2368325.02     13709074.98        2368075.       13709375.
        2366875.       13710575.
#Sta/Elev= 30
  4604.8  393.72  4706.9  388.58  4765.2  386.28  4821.2  385.16  4881.4  382.83
  4910.1   383.3  4917.2  381.88  4919.6  375.11  4920.1  374.61  4929.2  375.11
  4945.2  376.38    4953  378.81  4959.5  376.21  4967.4  379.98  4973.9  377.64
  4981.7  380.02  4988.2  379.52  4992.1   381.7  5037.8  381.35  5066.1  383.09
  5105.8  383.01  5405.5  382.99  5645.9  380.76  5674.2  382.71  5716.6   381.7
  5916.2  383.28    6256  385.91  6284.9  386.26    6506  388.94  6692.4  390.39
#Mann= 11 ,-1 , 0
  4604.8     .07       0  4706.9     .12       0  4765.2     .07       0
  4821.2     .12       0  4919.6     .05       0  4929.2     .12       0
  5105.8     .07       0  5916.2     .05       0    6256     .07       0
  6284.9     .05       0    6506     .07       0
Bank Sta=4919.6,4929.2
XS Rating Curve= 0 ,0
Exp/Cntr=0.3,0.1

Type RM Length L Ch R = 1 ,4501    ,421,421,421
BEGIN DESCRIPTION:
Stream0561 10.0
END DESCRIPTION:
XS GIS Cut Line= 3
      2368174.98     13708925.01        2367925.       13709025.
      2366825.01     13710224.98
#Sta/Elev= 30
  4735.3  389.68  4803.1  386.83  4864.5  384.42  4896.8  384.17  4941.3  378.91
  4965.5  381.03  4972.2  380.65    4983  377.43  4984.9  372.49  4985.4  371.99
  4994.6  372.49  4995.1  374.61  5001.8   379.7  5007.9   379.7  5018.4  381.68
  5090.7  382.28  5237.9  381.35  5386.5  381.09  5450.7   381.8  5591.9  380.67
  5641.8  381.09  5655.7  380.13  5691.1  379.61  5733.7  380.98    5783  380.46
  5839.8  381.61    5939  381.96  5967.4  381.16  6167.5  383.21  6632.4  388.03
#Mann= 6 ,-1 , 0
  4735.3     .07       0  4803.1     .12       0  4984.9     .05       0
  4994.6     .12       0  5090.7     .07       0  6167.5     .05       0
Bank Sta=4984.9,4994.6
XS Rating Curve= 0 ,0
Exp/Cntr=0.3,0.1

Type RM Length L Ch R = 1 ,4080    ,470,470,470
BEGIN DESCRIPTION:
Stream0561 9.0
END DESCRIPTION:
XS GIS Cut Line= 3
      2368024.98     13708375.03        2367675.       13708775.
      2366475.02     13709774.99
#Sta/Elev= 30
  4484.8  389.47  4704.5  383.93  4782.3  382.55    4825  383.18  4861.2  380.99
    4882  378.39  4888.6  381.24  4952.2  380.79  4959.8  377.03  4966.4  377.56
  4969.2  372.68  4969.7  372.18  4978.9  372.68  4994.9  373.04  5002.5  376.33
  5009.2  375.46  5012.9  379.35  5029.9  379.33    5039  380.63  5512.9  379.75
  5555.8  378.73  5662.6  380.48  5676.9  378.21  5738.6  380.35  5825.3   378.4
  5833.1  380.09  5875.4  380.89  5995.8  381.14  6010.1  382.33  6578.3  387.44
#Mann= 6 ,-1 , 0
  4484.8     .07       0  4861.2     .12       0  4969.2     .05       0
  4978.9     .12       0    5039     .07       0  5738.6     .05       0
Bank Sta=4969.2,4978.9
XS Rating Curve= 0 ,0
Exp/Cntr=0.3,0.1

Type RM Length L Ch R = 1 ,3610    ,429,429,429
BEGIN DESCRIPTION:
Stream0561 8.0
END DESCRIPTION:
XS GIS Cut Line= 3
        2367575.     13707825.01        2367325.       13708575.
      2366425.01     13709574.99
#Sta/Elev= 30
  4205.6  391.92  4511.3   380.3  4795.9  378.15  4945.5  379.77  4975.1  379.81
  4985.6  376.43  4988.7   370.3  4989.2   369.8  4998.4   370.3  4999.5   370.3
  5003.3  375.74  5017.5  377.92  5060.1  378.05  5109.4  376.43  5137.8  379.77
  5201.3  378.55  5272.3  379.08  5321.7  377.36  5329.1   378.4  5335.9  377.98
  5350.1  374.41  5364.3  378.83  5371.7  379.04  5470.4  376.86  5567.1  378.43
  5859.8  381.26  5881.5  382.36  5916.5  381.69  6051.1   384.2  6341.5  386.53
#Mann= 6 ,-1 , 0
  4205.6     .07       0  4945.5     .12       0  4988.7     .05       0
  4998.4     .12       0  5567.1     .07       0  5916.5     .05       0
Bank Sta=4988.7,4998.4
XS Rating Curve= 0 ,0
Exp/Cntr=0.3,0.1