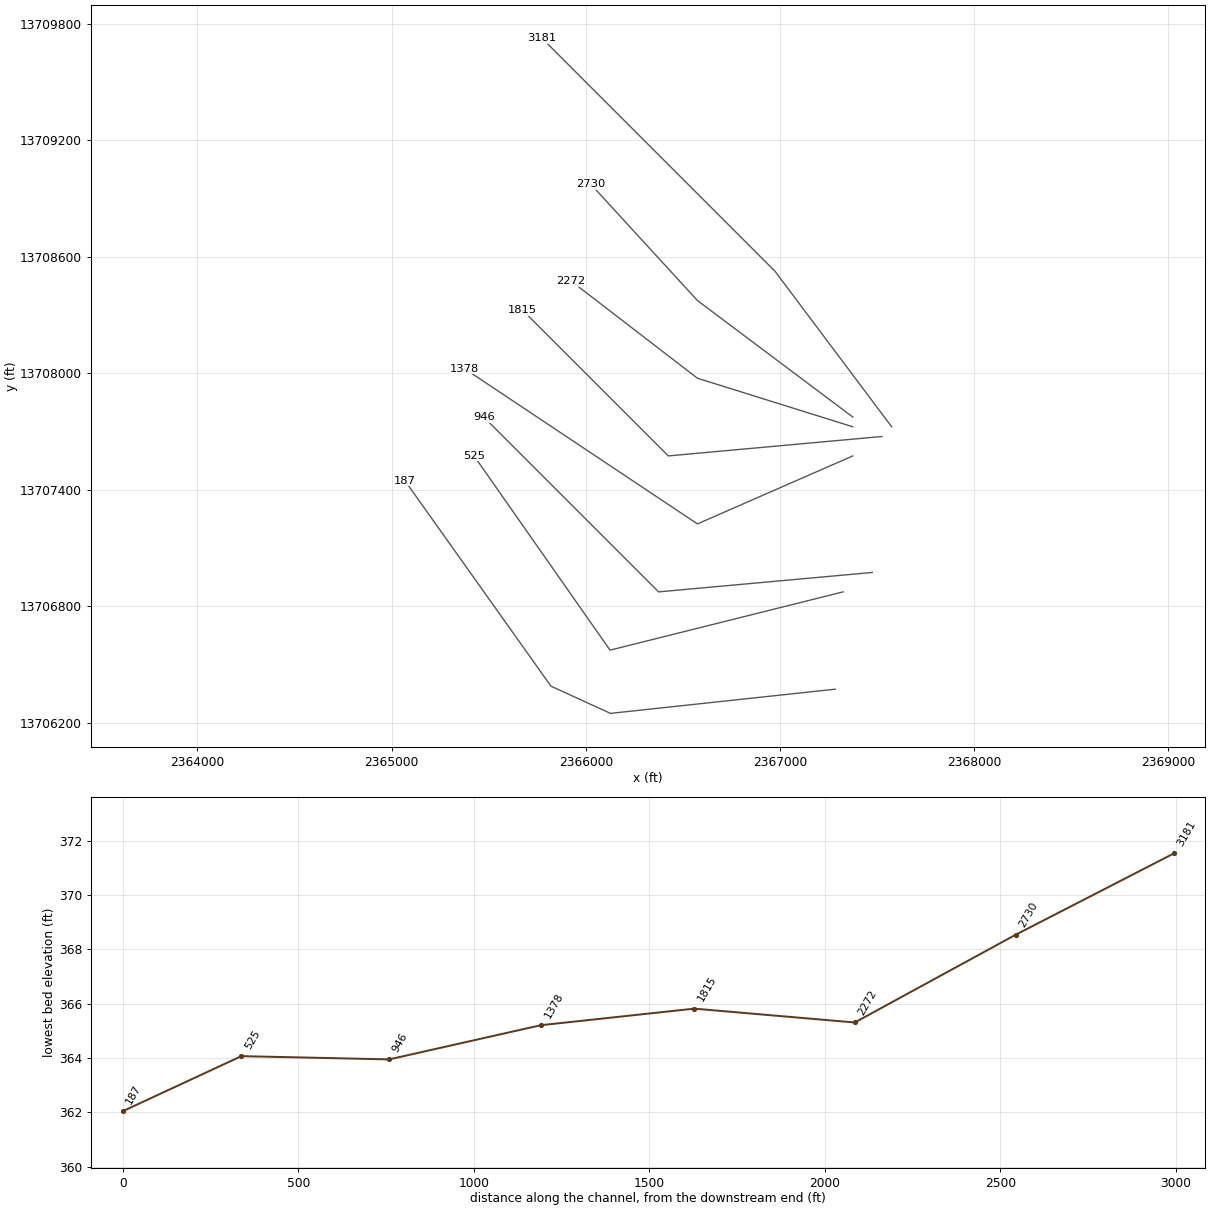
HEC-RAS study Stream0561.prj: Stream0561 Base Level Engineering

--- Stream0561.g01 (geometry) --- (continued)

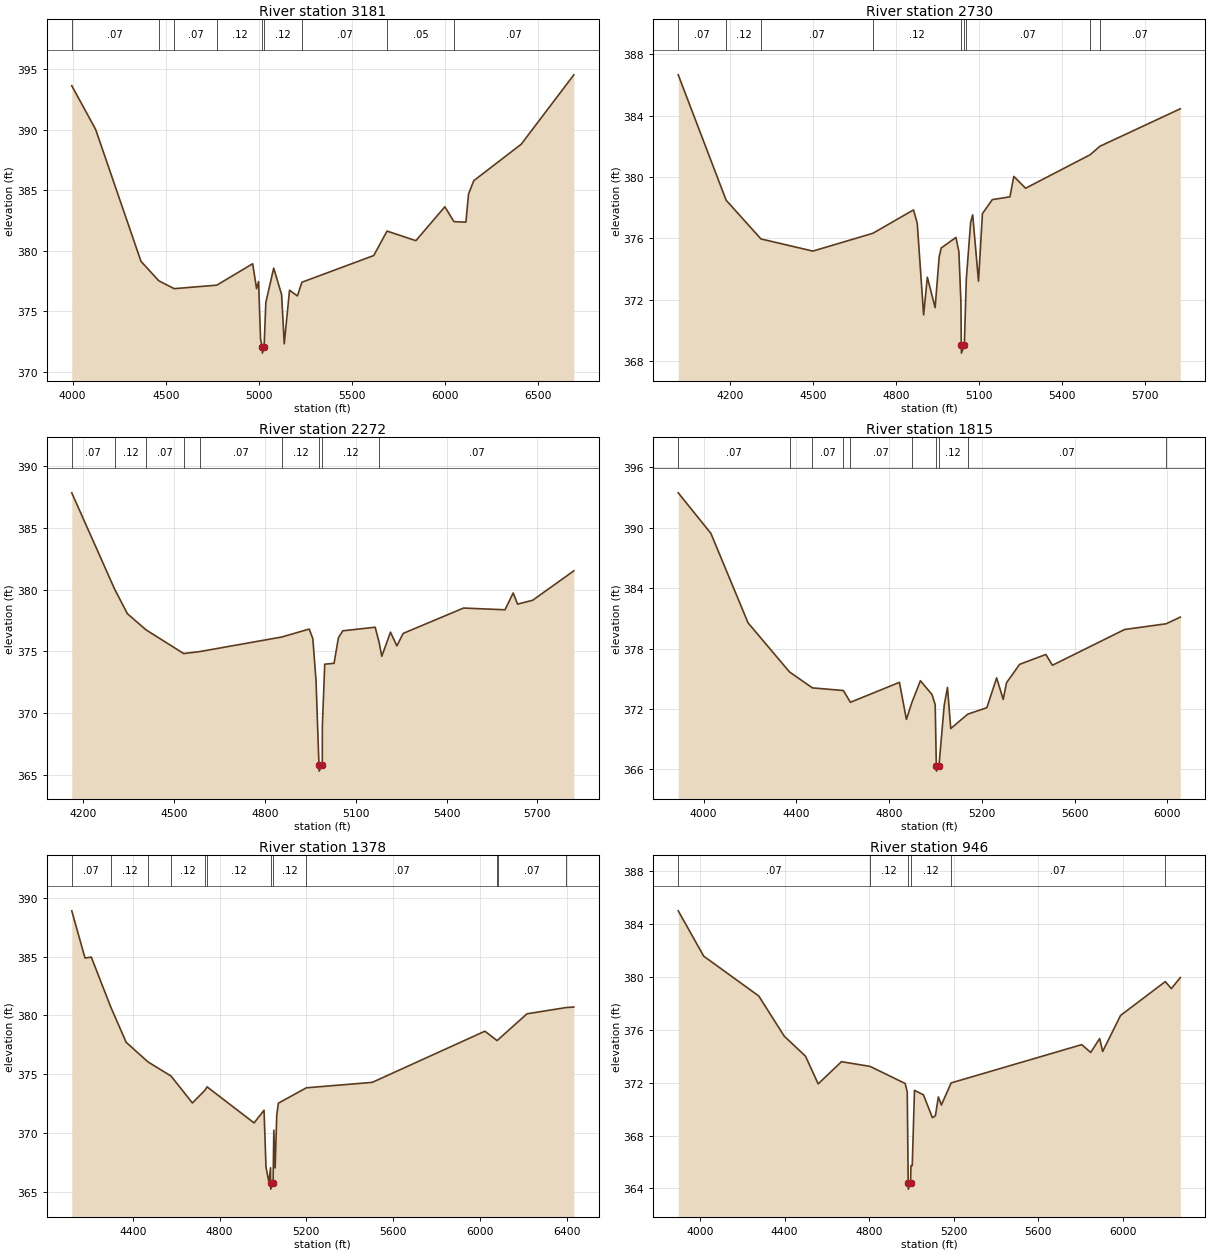
Type RM Length L Ch R = 1 ,3181    ,451,451,451
BEGIN DESCRIPTION:
Stream0561 7.0
END DESCRIPTION:
XS GIS Cut Line= 3
      2367574.98     13707725.03        2366975.       13708525.
      2365775.02     13709724.98
#Sta/Elev= 30
  3995.2  393.65  4123.3  390.04    4367  379.13  4462.8  377.52  4545.3  376.87
  4774.4  377.16    4967  378.93  4987.9  376.87  4998.7  377.46  5009.3  372.71
  5018.6  372.04  5019.1  371.54  5028.3  372.04  5037.6  375.72    5080  378.57
  5122.4  376.38  5136.6  372.31  5164.9  376.74  5207.3  376.27  5231.3   377.4
  5617.4  379.61  5688.6  381.63  5843.7  380.84  5999.3  383.64  6048.3  382.41
  6112.4  382.37  6126.5   384.7  6154.8   385.8  6409.4  388.81  6692.2  394.55
#Mann= 9 ,-1 , 0
  3995.2     .07       0  4462.8     .12       0  4545.3     .07       0
  4774.4     .12       0  5018.6     .05       0  5028.3     .12       0
  5231.3     .07       0  5688.6     .05       0  6048.3     .07       0
Bank Sta=5018.6,5028.3
XS Rating Curve= 0 ,0
Exp/Cntr=0.3,0.1

Type RM Length L Ch R = 1 ,2730    ,458,458,458
BEGIN DESCRIPTION:
Stream0561 6.0
END DESCRIPTION:
XS GIS Cut Line= 3
      2367375.01       13707775.        2366575.       13708375.
      2366025.03     13708974.96
#Sta/Elev= 30
  4012.3  386.65  4185.4  378.49  4311.2  375.97  4498.8  375.18  4715.7  376.34
  4862.3  377.86  4875.8  376.99  4898.8  371.03  4912.3  373.48  4940.4   371.5
    4955   374.8  4962.3  375.38  5015.7  376.07  5026.2  375.14  5033.6  371.85
  5034.9  369.04  5035.4  368.54  5045.9  369.04    5053  373.33  5068.7  377.06
  5076.1  377.54  5097.1  373.22  5111.3  377.62    5147  378.53  5210.6  378.71
  5224.7  380.04  5267.3  379.27  5500.5  381.45  5535.6     382  5826.2  384.44
#Mann= 9 ,-1 , 0
  4012.3     .07       0  4185.4     .12       0  4311.2     .07       0
  4715.7     .12       0  5034.9     .05       0  5045.9     .12       0
    5053     .07       0  5500.5     .05       0  5535.6     .07       0
Bank Sta=5034.9,5045.9
XS Rating Curve= 0 ,0
Exp/Cntr=0.3,0.1

Type RM Length L Ch R = 1 ,2272    ,457,457,457
BEGIN DESCRIPTION:
Stream0561 5.0
END DESCRIPTION:
XS GIS Cut Line= 3
      2367374.97     13707725.01        2366575.       13707975.
      2365924.98     13708475.01
#Sta/Elev= 30
  4162.2  387.82  4303.8  380.03    4346  378.04  4407.9  376.73  4531.8  374.82
  4585.3  374.98    4856  376.16  4946.4   376.8  4958.4  376.02  4968.9  372.64
  4978.6  365.81  4979.1  365.31  4989.6  365.81  4989.8  368.95  4997.7  373.96
  5028.4  374.03  5042.9   376.1  5057.4  376.66  5164.3  376.95  5177.3  375.72
  5186.1   374.6  5214.8  376.55  5235.9  375.44  5256.7  376.45  5456.1   378.5
    5593  378.36  5620.1  379.72  5634.6  378.82  5684.4  379.13  5820.4  381.51
#Mann= 9 ,-1 , 0
  4162.2     .07       0  4303.8     .12       0  4407.9     .07       0
  4531.8     .12       0  4585.3     .07       0    4856     .12       0
  4978.6     .05       0  4989.6     .12       0  5177.3     .07       0
Bank Sta=4978.6,4989.6
XS Rating Curve= 0 ,0
Exp/Cntr=0.3,0.1

Type RM Length L Ch R = 1 ,1815    ,437,437,437
BEGIN DESCRIPTION:
Stream0561 4.0
END DESCRIPTION:
XS GIS Cut Line= 3
        2367525.       13707675.        2366425.       13707575.
        2365675.       13708325.
#Sta/Elev= 30
  3890.9  393.47  4031.5  389.45  4192.1  380.55    4371  375.67  4469.6  374.09
  4603.1  373.83  4633.3  372.66  4844.8  374.64  4874.9  370.96  4897.6  372.58
  4935.2   374.8  4985.4  373.43    4999  372.42    5004  366.32  5004.5  365.82
  5015.1  366.32  5037.9  372.35    5052  374.14  5066.1  370.05  5139.4  371.48
  5221.7  372.12  5264.1  375.08  5292.4  372.95  5306.6   374.6  5363.1  376.43
  5476.3  377.41  5504.6  376.34  5815.7  379.89  5994.8  380.46  6056.1  381.12
#Mann= 10 ,-1 , 0
  3890.9     .07       0    4371    .035       0  4469.6     .07       0
  4603.1     .12       0  4633.3     .07       0  4897.6     .12       0
    5004     .05       0  5015.1     .12       0  5139.4     .07       0
  5994.8    .035       0
Bank Sta=5004,5015.1
XS Rating Curve= 0 ,0
Exp/Cntr=0.3,0.1

Type RM Length L Ch R = 1 ,1378    ,432,432,432
BEGIN DESCRIPTION:
Stream0561 3.0
END DESCRIPTION:
XS GIS Cut Line= 3
      2367374.96     13707574.98        2366575.       13707225.
        2365375.       13708025.
#Sta/Elev= 30
  4118.1  388.91  4179.3  384.89  4208.1  384.97  4297.9  380.72  4369.1  377.71
  4469.9  376.04    4576  374.84  4674.3  372.55  4731.4  373.61  4742.1  373.92
  4958.9  370.85  5004.8  371.93  5013.8   367.1  5027.3  365.79  5034.8  367.03
  5035.2  365.71  5035.7  365.21  5046.4  365.71  5049.9  370.23  5055.9  367.01
  5063.4  371.51  5070.9  372.53  5200.2  373.84  5503.6   374.3  6023.4  378.66
  6079.3  377.86  6085.1  377.95  6217.2  380.14  6397.1  380.67  6433.5  380.72
#Mann= 12 ,-1 , 0
  4118.1     .07       0  4297.9     .12       0  4469.9    .035       0
    4576     .12       0  4731.4     .07       0  4742.1     .12       0
  5035.2     .05       0  5046.4     .12       0  5200.2     .07       0
  6079.3    .035       0  6085.1     .07       0  6397.1    .035       0
Bank Sta=5035.2,5046.4
XS Rating Curve= 0 ,0
Exp/Cntr=0.3,0.1

Type RM Length L Ch R = 1 ,946     ,421,421,421
BEGIN DESCRIPTION:
Stream0561 2.0
END DESCRIPTION:
XS GIS Cut Line= 3
      2367474.96       13706975.        2366375.       13706875.
      2365474.99     13707775.01
#Sta/Elev= 30
  3896.2  385.02  4016.7  381.59  4277.7  378.57  4398.2  375.53  4498.6  374.02
  4558.9  371.92  4669.3   373.6  4804.8  373.24  4970.6  371.95  4980.6  371.31
  4985.1  364.45  4985.6  363.95  4996.3  364.45  4998.2  365.73  5004.2  365.73
  5014.8  371.43  5057.3  371.09  5099.7  369.36  5113.8   369.5    5128  370.93
  5142.1  370.32  5188.4  371.99  5806.8  374.89  5849.2   374.3  5891.7  375.35
  5905.8  374.37  5990.6   377.1  6202.3  379.66  6231.1  379.13  6273.5  379.97
#Mann= 6 ,-1 , 0
  3896.2     .07       0  4804.8     .12       0  4985.1     .05       0
  4996.3     .12       0  5188.4     .07       0  6202.3    .035       0
Bank Sta=4985.1,4996.3
XS Rating Curve= 0 ,0
Exp/Cntr=0.3,0.1

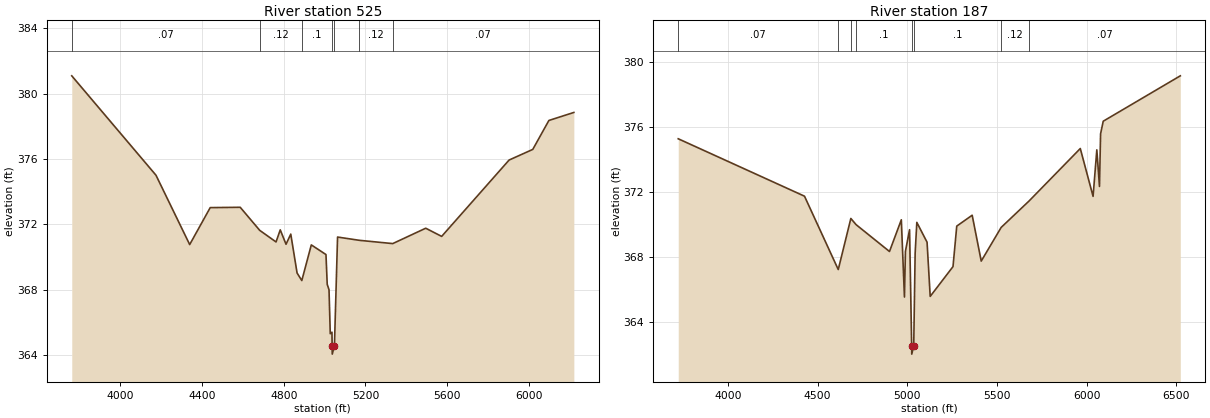
Type RM Length L Ch R = 1 ,525     ,338,338,338
BEGIN DESCRIPTION:
Stream0561 1.0
END DESCRIPTION:
XS GIS Cut Line= 3
        2367325.       13706875.        2366125.       13706575.
      2365424.99     13707575.01
#Sta/Elev= 30
  3762.3  381.09  4174.6  375.01  4339.5  370.77    4440  373.03  4586.9  373.05
  4682.3  371.64  4762.2  370.93  4782.8  371.67  4811.1  370.79  4834.3  371.41
  4865.2  369.03  4888.3  368.57  4934.8  370.75  5006.6  370.16  5012.7  368.34
  5021.5  368.01  5027.6  365.32  5035.9  365.41  5036.8  364.57  5037.3  364.07
    5048  364.57  5063.3  371.23  5170.1  371.03  5333.4  370.83  5494.9  371.77
  5572.9  371.27    5903  375.94  6018.9  376.59  6097.8  378.36  6219.9  378.85
#Mann= 7 ,-1 , 0
  3762.3     .07       0  4682.3     .12       0  4888.3      .1       0
  5036.8     .05       0    5048      .1       0  5170.1     .12       0
  5333.4     .07       0
Bank Sta=5036.8,5048
XS Rating Curve= 0 ,0
Exp/Cntr=0.3,0.1

Type RM Length L Ch R = 1 ,187     ,0,0,0
BEGIN DESCRIPTION:
XS7065
END DESCRIPTION:
XS GIS Cut Line= 4
      2367284.84     13706374.02      2366127.09     13706249.42
      2365820.78      13706389.6      2365068.96     13707447.32
#Sta/Elev= 30
  3723.1  375.28    4427  371.75  4615.2  367.24  4685.4  370.38  4714.6     370
  4900.8  368.35  4966.8   370.3  4984.2  365.55  4989.7  368.36  5012.7  369.69
  5024.5  362.54    5025  362.04  5035.9  362.54  5043.8  368.23  5053.2  370.14
  5110.3  368.92  5127.8  365.59  5254.9  367.42  5275.8  369.91  5361.8  370.58
  5412.3  367.76  5523.4  369.83  5678.5  371.45  5964.5  374.68  6035.8  371.74
  6056.7   374.6  6071.5  372.35  6077.6  375.58  6092.4  376.36  6522.1  379.15
#Mann= 8 ,-1 , 0
  3723.1     .07       0  4615.2     .12       0  4685.4     .07       0
  4714.6      .1       0  5024.5     .05       0  5035.9      .1       0
  5523.4     .12       0  5678.5     .07       0
Bank Sta=5024.5,5035.9
XS Rating Curve= 0 ,0
Exp/Cntr=0.3,0.1

Chan Stop Cuts=-1
Use User Specified Reach Order=0
Composite Channel Slope=5