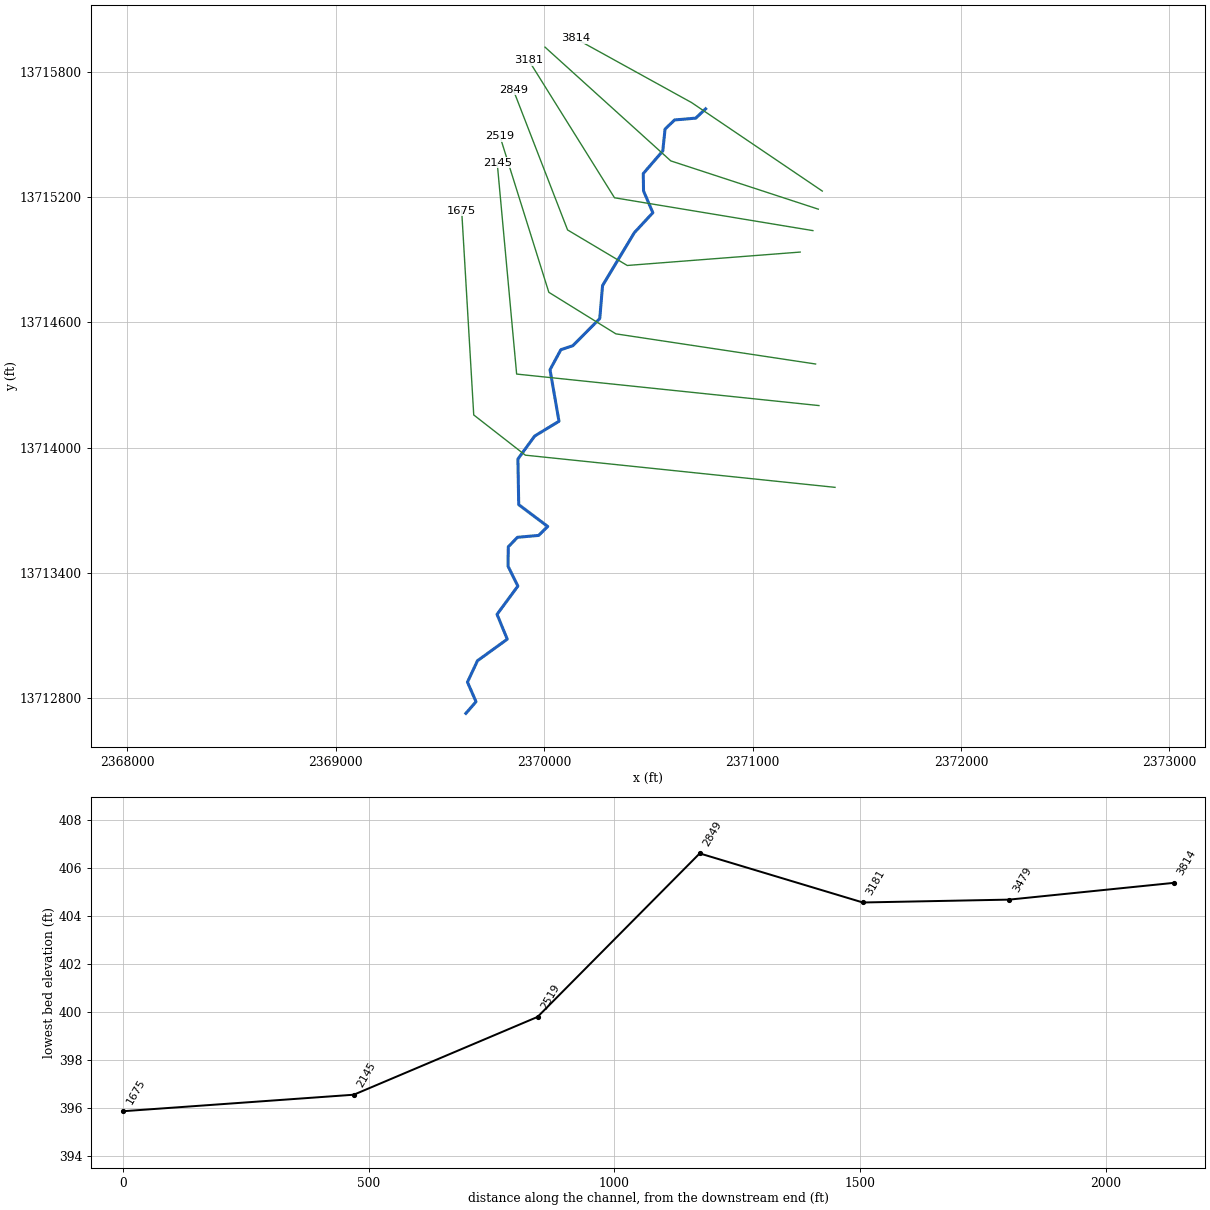
--- Stream0562.prj (project) ---

Proj Title=Stream0562 Base Level Engineering
Current Plan=p01
Default Exp/Contr=0.3,0.1
English Units
Geom File=g01
Flow File=f01
Plan File=p01
BEGIN DESCRIPTION:
Stream0562
END DESCRIPTION:

--- Stream0562.p01 (plan) ---

Plan Title=Multiple Run
Short Identifier=Multiple
Geom File=g01
Flow File=f01
Subcritical Flow
K Sum by GR= 0
Std Step Tol= 0.01
Critical Tol= 0.01
Num of Std Step Trials= 20
Max Error Tol= 0.3
Flow Tol Ratio= 0.001
Split Flow NTrial= 30
Split Flow Tol= 0.02
Split Flow Ratio= 0.02
Log Output Level= 0
Friction Slope Method= 1
Unsteady Friction Slope Method= 2
Unsteady Bridges Friction Slope Method= 1
Parabolic Critical Depth
Global Vel Dist=  1 , 1 , 1
Global Log Level= 0
CheckData=True
Encroach Param= -1, 0, 0, 0
BEGIN DESCRIPTION:
Multiple Run
END DESCRIPTION:

--- Stream0562.f01 (steady flow) ---

Flow Title=Multiple
Number of Profiles=7
Profile Names=10-year,25-year,50-year,1pct_min,100-year,1pct_plu,500-year
River Rch & RM= Stream0562,Reach-1,3814
     619     993    1327     859    1713    3419    2829
Boundary for River Rch & Prof#=Stream0562,Reach-1,1
Up Type=0
Dn Type=3
Dn Slope=0.005
Boundary for River Rch & Prof#=Stream0562,Reach-1,2
Up Type=0
Dn Type=3
Dn Slope=0.005
Boundary for River Rch & Prof#=Stream0562,Reach-1,3
Up Type=0
Dn Type=3
Dn Slope=0.005
Boundary for River Rch & Prof#=Stream0562,Reach-1,4
Up Type=0
Dn Type=3
Dn Slope=0.005
Boundary for River Rch & Prof#=Stream0562,Reach-1,5
Up Type=0
Dn Type=3
Dn Slope=0.005
Boundary for River Rch & Prof#=Stream0562,Reach-1,6
Up Type=0
Dn Type=3
Dn Slope=0.005
Boundary for River Rch & Prof#=Stream0562,Reach-1,7
Up Type=0
Dn Type=3
Dn Slope=0.005

--- Stream0562.g01 (geometry) ---

Geom Title=Existing Conditions

River Reach=Stream0562,Reach-1
Reach XY= 30
      2370775.00     13715625.00      2370727.55     13715580.23
      2370626.24     13715571.52      2370580.41     13715527.71
      2370569.46     13715422.58      2370475.94     13715314.52
      2370477.19     13715230.97      2370521.86     13715126.64
      2370433.18     13715031.04      2370280.71     13714777.35
      2370267.18     13714618.81      2370137.98     13714488.73
      2370080.59     13714469.39      2370028.66     13714373.44
      2370071.63     13714126.28      2369954.88     13714055.22
      2369874.57     13713945.18      2369878.45     13713726.25
      2370017.61     13713621.57      2369974.00     13713578.63
      2369872.29     13713569.59      2369828.36     13713523.75
      2369827.19     13713430.97      2369874.39     13713335.62
      2369774.52     13713200.03      2369823.45     13713080.85
      2369680.70     13712977.54      2369632.54     13712875.00
      2369673.67     13712781.06      2369625.00     13712725.00

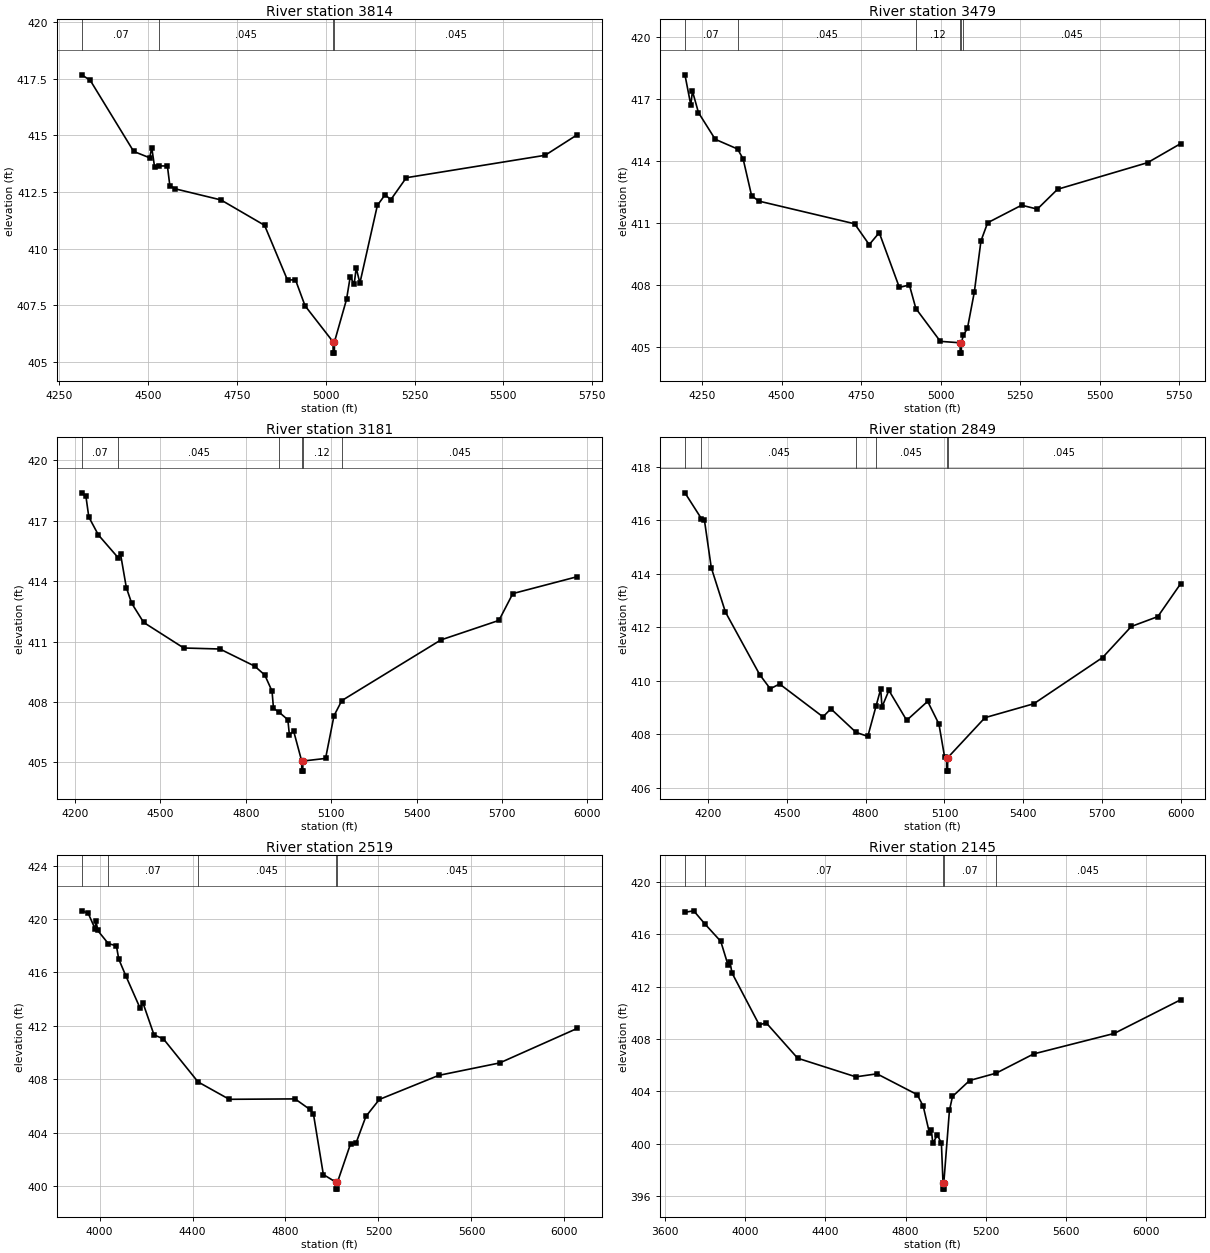
Type RM Length L Ch R = 1,3814,335,335,335
BEGIN DESCRIPTION:
XS7073
END DESCRIPTION:
XS GIS Cut Line= 3
      2371334.76     13715230.43      2370707.71     13715654.89
      2370149.09     13715963.09
#Sta/Elev= 30
  4313.1  417.67  4337.0  417.43  4459.4  414.29  4504.3  414.01  4510.3  414.45
  4518.1  413.62  4531.8  413.65  4554.3  413.65  4561.2  412.78  4576.2  412.64
  4705.0  412.15  4827.8  411.03  4892.4  408.61  4914.7  408.63  4941.7  407.48
  5020.5  405.89  5020.8  405.39  5024.3  405.39  5024.6  405.89  5058.5  407.76
  5068.9  408.76  5080.0  408.43  5085.7  409.15  5096.1  408.48  5145.3  411.91
  5167.1  412.38  5183.1  412.16  5226.7  413.13  5617.5  414.12  5708.3  415.03
#Mann=4,-1,0
  4313.1    0.07       0  4531.8   0.045       0  5020.5   0.045       0
  5024.6   0.045       0
Bank Sta=5020.5,5024.6
Exp/Cntr=0.3,0.1

Type RM Length L Ch R = 1,3479,298,298,298
BEGIN DESCRIPTION:
XS7072
END DESCRIPTION:
XS GIS Cut Line= 3
      2371315.43     13715143.64      2370608.03     13715375.15
      2370004.51     13715920.89
#Sta/Elev= 30
  4196.5  418.16  4214.9  416.70  4220.1  417.37  4239.0  416.33  4291.7  415.04
  4361.9  414.57  4379.4  414.09  4406.0  412.31  4428.4  412.05  4729.8  410.95
  4775.7  409.94  4807.2  410.52  4870.4  407.87  4901.9  407.99  4922.3  406.85
  4999.2  405.26  5061.4  405.19  5061.6  404.69  5065.2  404.69  5065.5  405.19
  5071.4  405.55  5084.4  405.89  5106.0  407.64  5126.9  410.12  5147.9  411.00
  5254.7  411.85  5304.0  411.66  5367.6  412.62  5650.8  413.91  5754.5  414.83
#Mann=6,-1,0
  4196.5    0.07       0  4361.9   0.045       0  4922.3    0.12       0
  5061.4    0.05       0  5065.5    0.12       0  5071.4   0.045       0
Bank Sta=5061.4,5065.5
Exp/Cntr=0.3,0.1

Type RM Length L Ch R = 1,3181,332,332,332
BEGIN DESCRIPTION:
XS7071
END DESCRIPTION:
XS GIS Cut Line= 3
      2371289.69     13715040.75      2370337.94     13715198.30
      2369926.36     13715857.46
#Sta/Elev= 30
  4223.4  418.38  4238.3  418.20  4248.4  417.18  4282.0  416.29  4352.7  415.14
  4359.9  415.34  4380.2  413.68  4399.0  412.90  4441.0  411.95  4582.0  410.68
  4709.1  410.63  4831.2  409.78  4866.7  409.34  4892.2  408.54  4897.3  407.69
  4917.3  407.49  4947.8  407.12  4953.2  406.37  4968.1  406.56  4996.4  405.07
  4996.7  404.57  5000.3  404.57  5000.5  405.07  5080.3  405.20  5110.0  407.32
  5137.4  408.07  5485.6  411.08  5689.6  412.05  5738.3  413.38  5965.2  414.22
#Mann=6,-1,0
  4223.4    0.07       0  4352.7   0.045       0  4917.3    0.12       0
  4996.4    0.05       0  5000.5    0.12       0  5137.4   0.045       0
Bank Sta=4996.4,5000.5
Exp/Cntr=0.3,0.1

Type RM Length L Ch R = 1,2849,330,330,330
BEGIN DESCRIPTION:
XS7070
END DESCRIPTION:
XS GIS Cut Line= 4
      2371228.59     13714937.85      2370399.03     13714873.54
      2370112.86     13715043.96      2369852.43     13715715.94
#Sta/Elev= 30
  4112.6  417.03  4175.5  416.06  4186.4  416.03  4212.8  414.23  4266.6  412.57
  4397.0  410.23  4437.2  409.70  4472.6  409.88  4637.8  408.65  4667.8  408.95
  4763.5  408.07  4808.3  407.92  4840.1  409.07  4857.3  409.69  4862.3  409.02
  4888.5  409.64  4956.2  408.52  5036.0  409.23  5078.9  408.38  5100.6  407.14
  5107.9  407.12  5108.2  406.62  5111.8  406.62  5112.1  407.12  5254.1  408.62
  5439.7  409.14  5701.6  410.87  5810.6  412.03  5911.6  412.40  5998.4  413.63
#Mann=6,-1,0
  4112.6    0.07       0  4175.5   0.045       0  4763.5    0.12       0
  4840.1   0.045       0  5107.9   0.045       0  5112.1   0.045       0
Bank Sta=5107.9,5112.1
Exp/Cntr=0.3,0.1

Type RM Length L Ch R = 1,2519,374,374,374
BEGIN DESCRIPTION:
XS7069
END DESCRIPTION:
XS GIS Cut Line= 4
      2371302.58     13714400.88      2370344.37     13714545.57
      2370022.83     13714744.93      2369788.10     13715494.11
#Sta/Elev= 30
  3923.3  420.61  3951.2  420.43  3980.4  419.28  3985.5  419.84  3991.6  419.15
  4037.7  418.16  4072.6  417.99  4082.7  417.00  4113.0  415.75  4173.7  413.36
  4187.1  413.71  4234.4  411.33  4274.8  411.03  4423.9  407.81  4558.0  406.51
  4841.2  406.54  4905.0  405.75  4920.4  405.40  4962.9  400.88  5019.0  400.29
  5019.3  399.79  5022.9  399.79  5023.2  400.29  5079.9  403.18  5103.4  403.23
  5146.0  405.23  5203.9  406.50  5459.4  408.30  5721.4  409.23  6055.8  411.82
#Mann=5,-1,0
  3923.3    0.05       0  4037.7    0.07       0  4423.9   0.045       0
  5019.0   0.045       0  5023.2   0.045       0
Bank Sta=5019,5023.2
Exp/Cntr=0.3,0.1

Type RM Length L Ch R = 1,2145,470,470,470
BEGIN DESCRIPTION:
XS7068
END DESCRIPTION:
XS GIS Cut Line= 3
      2371318.63     13714201.52      2369868.49     13714352.65
      2369775.24     13715365.46
#Sta/Elev= 30
  3698.6  417.67  3742.5  417.78  3796.4  416.81  3877.5  415.45  3913.4  413.66
  3923.4  413.89  3933.5  413.04  4069.5  409.08  4104.4  409.23  4261.5  406.53
  4552.0  405.11  4657.4  405.34  4858.5  403.75  4888.6  402.86  4918.8  400.86
  4928.9  401.07  4936.0  400.06  4959.0  400.65  4979.1  400.07  4987.1  397.04
  4987.3  396.54  4991.0  396.54  4991.3  397.04  5019.3  402.55  5034.5  403.61
  5119.9  404.83  5252.4  405.39  5440.1  406.86  5841.8  408.42  6173.7  410.99
#Mann=5,-1,0
  3698.6    0.05       0  3796.4    0.07       0  4987.1    0.05       0
  4991.3    0.07       0  5252.4   0.045       0
Bank Sta=4987.1,4991.3
Exp/Cntr=0.3,0.1

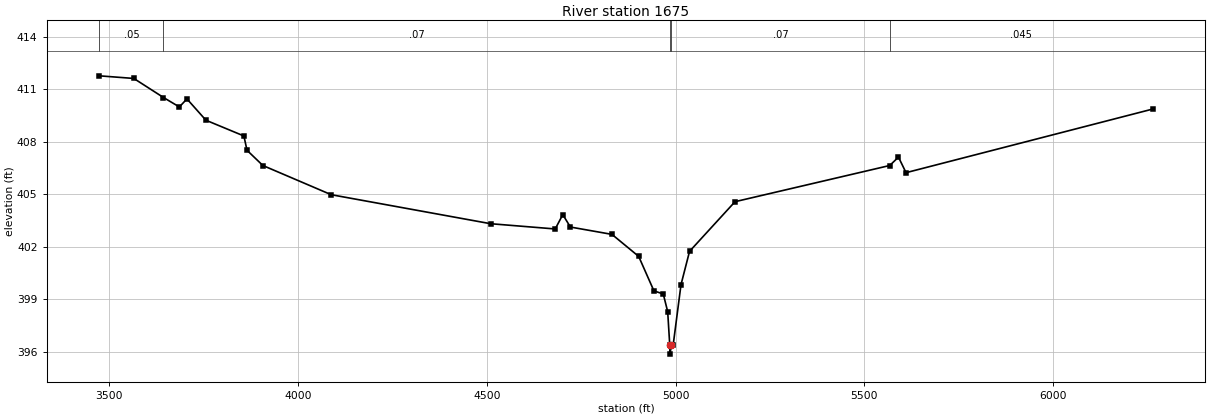
Type RM Length L Ch R = 1,1675,0,0,0
BEGIN DESCRIPTION:
XS7067
END DESCRIPTION:
XS GIS Cut Line= 4
      2371395.80     13713809.24      2369910.29     13713963.58
      2369662.70     13714156.51      2369604.82     13715137.22
#Sta/Elev= 30
  3473.9  411.77  3565.2  411.62  3643.8  410.53  3685.8  409.99  3705.9  410.45
  3756.2  409.23  3856.7  408.33  3865.0  407.51  3907.0  406.64  4088.0  404.97
  4510.2  403.31  4681.2  403.01  4701.3  403.83  4721.4  403.12  4831.5  402.70
  4902.3  401.44  4942.6  399.47  4967.4  399.29  4979.1  398.28  4984.6  396.35
  4984.9  395.85  4988.9  396.35  4993.6  396.37  5014.4  399.83  5037.0  401.73
  5157.4  404.57  5567.1  406.64  5590.3  407.12  5610.3  406.23  6263.7  409.87
#Mann=5,-1,0
  3473.9    0.05       0  3643.8    0.07       0  4984.6    0.05       0
  4988.9    0.07       0  5567.1   0.045       0
Bank Sta=4984.6,4988.9
Exp/Cntr=0.3,0.1

Chan Stop Cuts=-1