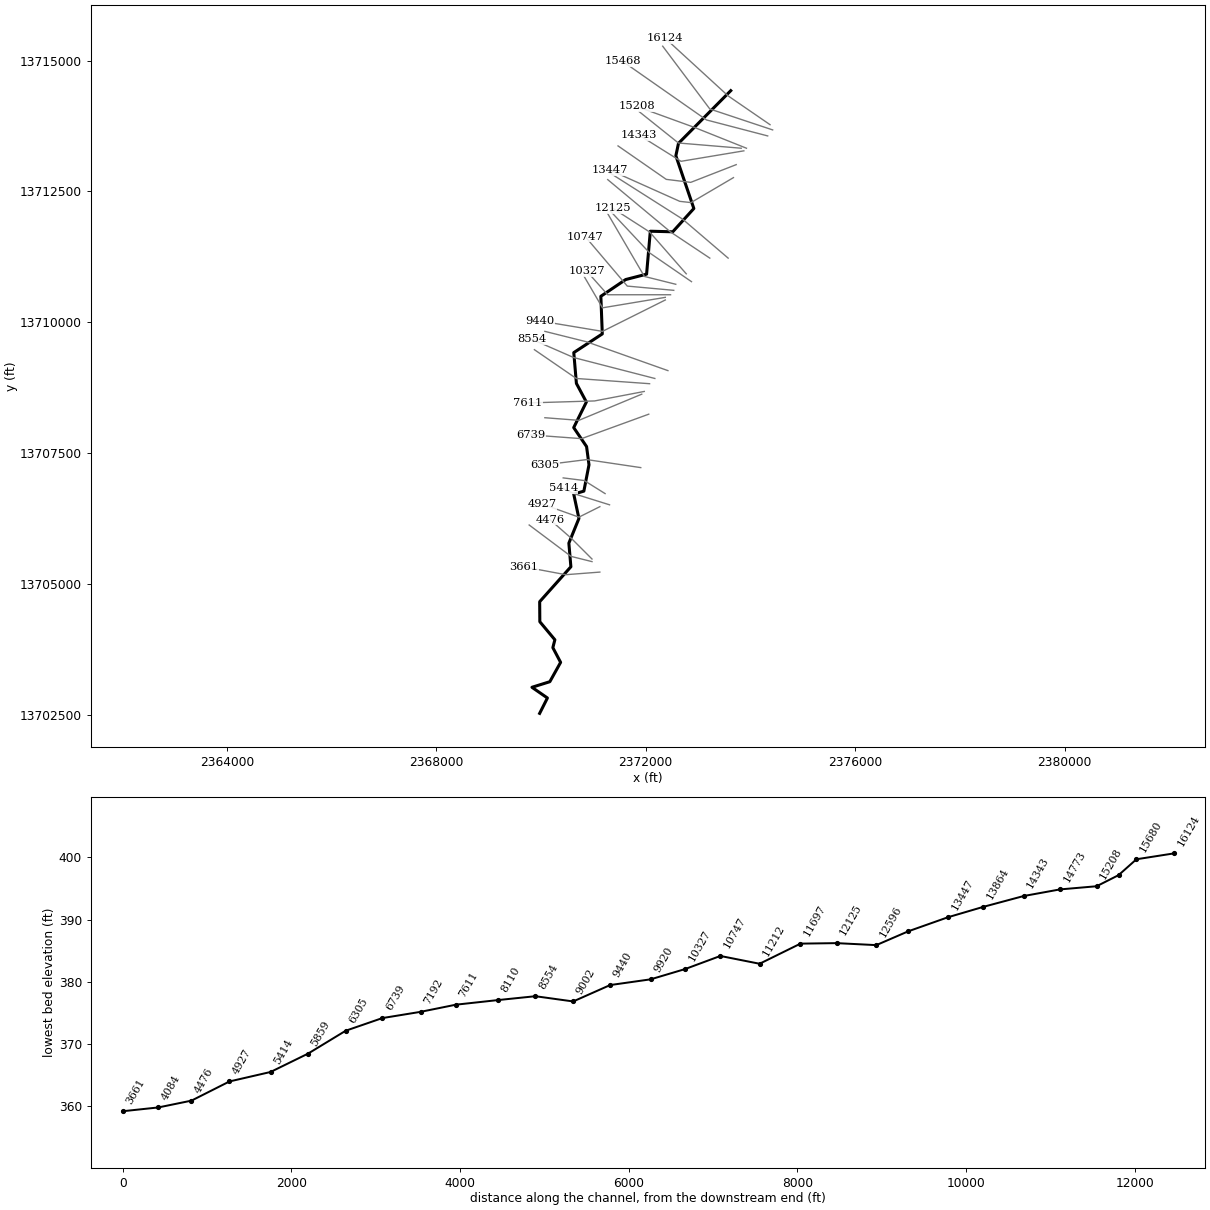
--- Stream0563.prj (project) ---

Proj Title=Stream0563 Base Level Engineering
Current Plan=p01
Default Exp/Contr=0.3,0.1
English Units
Geom File=g01
Flow File=f01
Plan File=p01
Y Axis Title=Elevation
X Axis Title(PF)=Main Channel Distance
X Axis Title(XS)=Station
BEGIN DESCRIPTION:
Stream0563
END DESCRIPTION:
DSS Export Rating Curves= 0
DSS Export Rating Curve Sorted= 0
DSS Export Volume Flow Curves= 0
DXF OffsetX= 0
DXF OffsetY= 0
DXF ScaleX= 1
DXF ScaleY= 10

--- Stream0563.p01 (plan) ---

Plan Title=Multiple Run
Short Identifier=Multiple
Geom File=g01
Flow File=f01
Subcritical Flow
K Sum by GR= 0
Std Step Tol= 0.01
Critical Tol= 0.01
Num of Std Step Trials= 20
Max Error Tol= 0.3
Flow Tol Ratio= 0.001
Split Flow NTrial= 30
Split Flow Tol= 0.02
Split Flow Ratio= 0.02
Log Output Level= 0
Friction Slope Method= 1
Unsteady Friction Slope Method= 2
Unsteady Bridges Friction Slope Method= 1
Parabolic Critical Depth
Global Vel Dist=  1 , 1 , 1
Global Log Level= 0
CheckData=True
Encroach Param= -1, 0, 0, 0
BEGIN DESCRIPTION:
Multiple Run
END DESCRIPTION:

--- Stream0563.f01 (steady flow) ---

Flow Title=Multiple
Number of Profiles=7
Profile Names=10-year,25-year,50-year,1pct_min,100-year,1pct_plu,500-year
River Rch & RM= Stream0563,Reach-1,16124
     705    1143    1539    1003    2002    3995    3356
River Rch & RM= Stream0563,Reach-1,15680
     774    1259    1700    1110    2215    4419    3726
River Rch & RM= Stream0563,Reach-1,12975
    1092    1805    2464    1624    3241    6467    5562
River Rch & RM= Stream0563,Reach-1,9440
    1326    2208    3027    2003    3996    7973    6906
River Rch & RM= Stream0563,Reach-1,4084
    1343    2233    3058    2021    4032    8046    6954
Boundary for River Rch & Prof#=Stream0563,Reach-1,1
Up Type=0
Dn Type=3
Dn Slope=0.005
Boundary for River Rch & Prof#=Stream0563,Reach-1,2
Up Type=0
Dn Type=3
Dn Slope=0.005
Boundary for River Rch & Prof#=Stream0563,Reach-1,3
Up Type=0
Dn Type=3
Dn Slope=0.005
Boundary for River Rch & Prof#=Stream0563,Reach-1,4
Up Type=0
Dn Type=3
Dn Slope=0.005
Boundary for River Rch & Prof#=Stream0563,Reach-1,5
Up Type=0
Dn Type=3
Dn Slope=0.005
Boundary for River Rch & Prof#=Stream0563,Reach-1,6
Up Type=0
Dn Type=3
Dn Slope=0.005
Boundary for River Rch & Prof#=Stream0563,Reach-1,7
Up Type=0
Dn Type=3
Dn Slope=0.005

--- Stream0563.g01 (geometry) ---

Geom Title=Existing Conditions
Program Version=4.10

River Reach=Stream0563      ,Reach-1
Reach XY= 30
        2373625.       13714425.      2372626.66     13713418.95
       2372576.6     13713181.05      2372920.07     13712173.04
      2372517.02     13711727.94      2372088.62     13711739.06
      2372017.28      13710918.5      2371618.39     13710815.57
      2371144.08     13710495.51      2371171.47     13709776.45
      2370626.97     13709419.33      2370677.06     13708830.86
      2370867.47     13708474.99       2370625.5     13707985.98
      2370871.25     13707623.45      2370917.44       13707275.
      2370819.64     13706772.22      2370626.03     13706714.89
       2370725.2     13706249.92      2370533.05     13705778.32
      2370571.66     13705326.72      2369975.66     13704659.17
      2369978.54     13704276.46      2370265.85     13703931.73
      2370227.17     13703780.98      2370375.59       13703500.
      2370169.59     13703130.18      2369827.99     13703023.59
      2370123.47     13702819.17        2369975.       13702525.

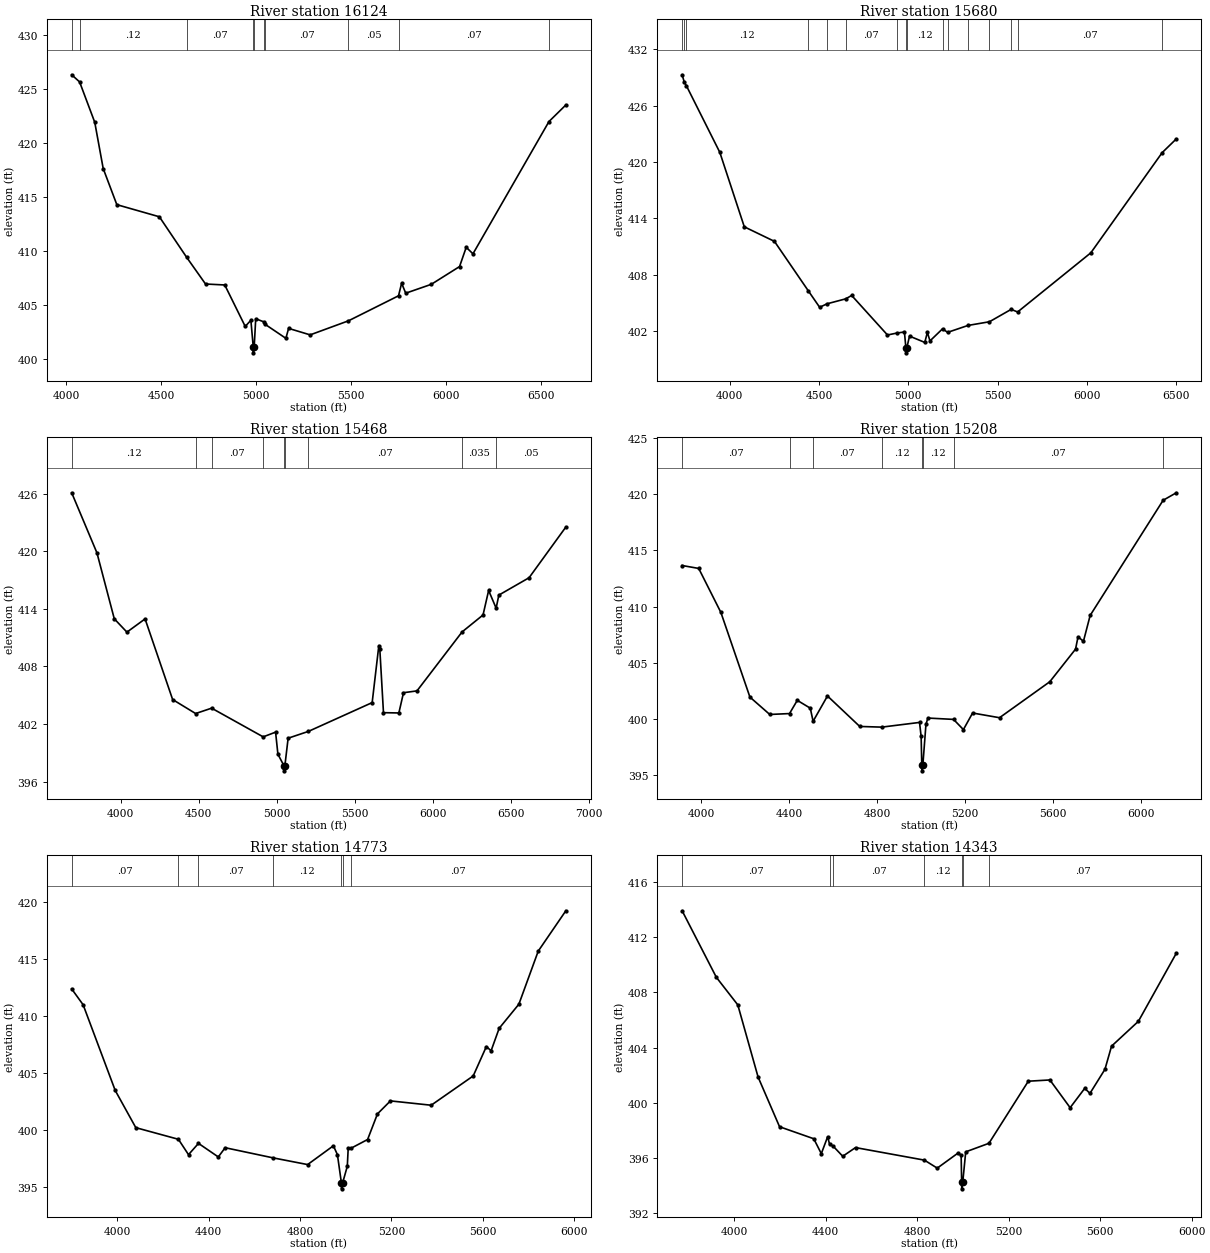
Type RM Length L Ch R = 1 ,16124   ,444,444,444
BEGIN DESCRIPTION:
Stream0563 31.0
END DESCRIPTION:
XS GIS Cut Line= 3
      2374374.97     13713775.02        2373575.       13714325.
      2372374.98     13715425.02
#Sta/Elev= 30
  4029.4   426.3    4071  425.64  4150.7  421.91  4195.1  417.64  4266.8   414.3
  4490.5  413.18  4633.4  409.45  4733.2  406.97  4834.4  406.88    4942  403.05
  4971.8  403.62  4984.4  401.11  4984.7  400.61    4989  401.11  4997.2  403.76
  5040.3  403.47  5047.9  403.23  5155.9  401.95  5170.1  402.87  5283.5  402.27
  5485.1  403.57  5748.1  405.88  5764.5  407.04  5786.1  406.12  5920.5  406.94
  6069.1  408.58  6104.2  410.36  6139.7  409.76  6539.4  421.98  6628.1  423.51
#Mann= 10 ,-1 , 0
  4029.4     .07       0    4071     .12       0  4633.4     .07       0
  4984.4     .05       0    4989     .07       0  5040.3     .12       0
  5047.9     .07       0  5485.1     .05       0  5748.1     .07       0
  6539.4    .035       0
Bank Sta=4984.4,4989
XS Rating Curve= 0 ,0
Exp/Cntr=0.3,0.1

Type RM Length L Ch R = 1 ,15680   ,212,212,212
BEGIN DESCRIPTION:
Stream0563 30.0
END DESCRIPTION:
XS GIS Cut Line= 3
      2374424.96     13713675.01        2373225.       13714075.
      2372324.98     13715275.03
#Sta/Elev= 30
  3734.9  429.28  3746.9  428.49  3759.1   428.1  3945.7  421.02  4082.7  413.09
  4251.4  411.54  4440.6  406.28  4504.3  404.52  4545.4  404.89  4650.1  405.42
  4683.5  405.78  4883.8  401.57  4937.5  401.78  4978.7  401.89  4986.9  400.17
  4987.2  399.67  4991.6  400.17  5007.1  401.45  5092.5  400.78  5107.1  401.85
  5121.6  400.94    5192  402.23  5220.2  401.85    5335  402.59  5454.4  402.98
  5575.9   404.3  5611.9  404.02  6021.6  410.32  6420.8  420.99  6499.8  422.45
#Mann= 16 ,-1 , 0
  3734.9     .12       0  3746.9     .07       0  3759.1     .12       0
  4440.6     .07       0  4545.4    .035       0  4650.1     .07       0
  4937.5     .12       0  4986.9     .05       0  4991.6     .12       0
    5192     .07       0  5220.2     .12       0    5335     .05       0
  5454.4     .12       0  5575.9     .05       0  5611.9     .07       0
  6420.8    .035       0
Bank Sta=4986.9,4991.6
XS Rating Curve= 0 ,0
Exp/Cntr=0.3,0.1

Type RM Length L Ch R = 1 ,15468   ,260,260,260
BEGIN DESCRIPTION:
XS7078
END DESCRIPTION:
XS GIS Cut Line= 3
      2374330.25     13713560.14      2373161.25     13713865.51
      2371558.98     13714986.14
#Sta/Elev= 30
  3687.1  426.09  3848.8  419.83  3959.8  412.96  4040.7  411.57  4156.9  412.95
  4333.3  404.55  4480.5  403.09    4583  403.65    4913  400.66  4992.4  401.15
  5007.3  398.85    5047  397.62  5047.3  397.12  5051.7  397.62  5072.7  400.52
  5202.6  401.23  5610.7  404.23  5653.4  410.17  5659.5  409.85  5683.1  403.18
  5781.6  403.15  5811.3  405.26  5897.6  405.45  6186.2  411.59  6320.5  413.36
  6356.3  415.91  6404.3  414.07  6421.7  415.43  6615.3  417.24  6850.6  422.52
#Mann= 9 ,-1 , 0
  3687.1     .12       0  4480.5    .035       0    4583     .07       0
    4913     .12       0    5047     .05       0  5051.7     .12       0
  5202.6     .07       0  6186.2    .035       0  6404.3     .05       0
Bank Sta=5047,5051.7
XS Rating Curve= 0 ,0
Exp/Cntr=0.3,0.1

Type RM Length L Ch R = 1 ,15208   ,435,435,435
BEGIN DESCRIPTION:
Stream0563 29.0
END DESCRIPTION:
XS GIS Cut Line= 3
      2373924.99     13713325.01        2372925.       13713725.
      2371824.99       13714125.
#Sta/Elev= 30
  3913.3  413.66  3988.7   413.4  4089.6  409.47  4221.6  401.92  4311.8  400.37
  4401.7  400.45    4437  401.63  4496.2  400.93  4508.9  399.76  4574.3  402.02
  4721.1   399.3  4821.1  399.24    4993  399.66  5000.3  398.41  5003.3  395.84
  5003.6  395.34    5008  395.84  5022.2  399.48  5030.9  400.05  5147.7  399.93
  5192.5  399.02  5234.4   400.5  5356.8  400.08  5585.5  403.29  5702.6   406.2
  5713.9   407.3  5738.5   406.9  5769.1  409.21  6100.9  419.48  6160.8  420.15
#Mann= 8 ,-1 , 0
  3913.3     .07       0  4401.7    .035       0  4508.9     .07       0
  4821.1     .12       0  5003.3     .05       0    5008     .12       0
  5147.7     .07       0  6100.9    .035       0
Bank Sta=5003.3,5008
XS Rating Curve= 0 ,0
Exp/Cntr=0.3,0.1

Type RM Length L Ch R = 1 ,14773   ,430,430,430
BEGIN DESCRIPTION:
Stream0563 28.0
END DESCRIPTION:
XS GIS Cut Line= 3
      2373824.97       13713325.        2372625.       13713425.
        2371875.       13714025.
#Sta/Elev= 30
  3799.7  412.38  3849.8  410.99  3990.3  403.47  4080.6   400.2  4267.2  399.18
  4311.4  397.83  4355.1  398.82  4441.9  397.63    4472  398.44  4681.7  397.55
  4833.2  396.96  4946.1  398.61  4963.7  397.83  4981.3  395.33  4981.7  394.83
  4986.2  395.33    5007  396.81    5011  398.41    5022  398.38  5095.9  399.16
  5139.1  401.41  5195.9  402.55  5374.4  402.17  5558.5  404.74  5616.1  407.32
  5636.9  406.95  5672.2  408.92  5758.6  411.04  5843.4   415.7  5964.3  419.24
#Mann= 7 ,-1 , 0
  3799.7     .07       0  4267.2    .035       0  4355.1     .07       0
  4681.7     .12       0  4981.3     .05       0  4986.2     .12       0
    5022     .07       0
Bank Sta=4981.3,4986.2
XS Rating Curve= 0 ,0
Exp/Cntr=0.3,0.1

Type RM Length L Ch R = 1 ,14343   ,479,479,479
BEGIN DESCRIPTION:
Stream0563 27.0
END DESCRIPTION:
XS GIS Cut Line= 3
      2373874.98       13713275.        2372675.       13713075.
      2371875.02     13713574.99
#Sta/Elev= 30
    3773  413.92  3922.5   409.1  4016.3   407.1    4105  401.87  4198.8  398.27
  4348.3   397.4  4381.3  396.32  4409.1  397.55  4417.5  396.99  4432.6  396.87
    4475  396.13  4530.8  396.76  4831.9  395.85  4888.1  395.27  4979.4  396.37
  4992.5  396.19  4994.7  394.27  4995.1  393.77  4999.6  394.27  5012.5  396.45
    5114  397.07  5286.1  401.57  5380.4  401.66  5468.9  399.65  5532.6  401.05
  5555.6  400.69    5621  402.43  5649.9  404.11  5767.2  405.91  5932.9  410.84
#Mann= 7 ,-1 , 0
    3773     .07       0  4417.5    .035       0  4432.6     .07       0
  4831.9     .12       0  4994.7     .05       0  4999.6     .12       0
    5114     .07       0
Bank Sta=4994.7,4999.6
XS Rating Curve= 0 ,0
Exp/Cntr=0.3,0.1

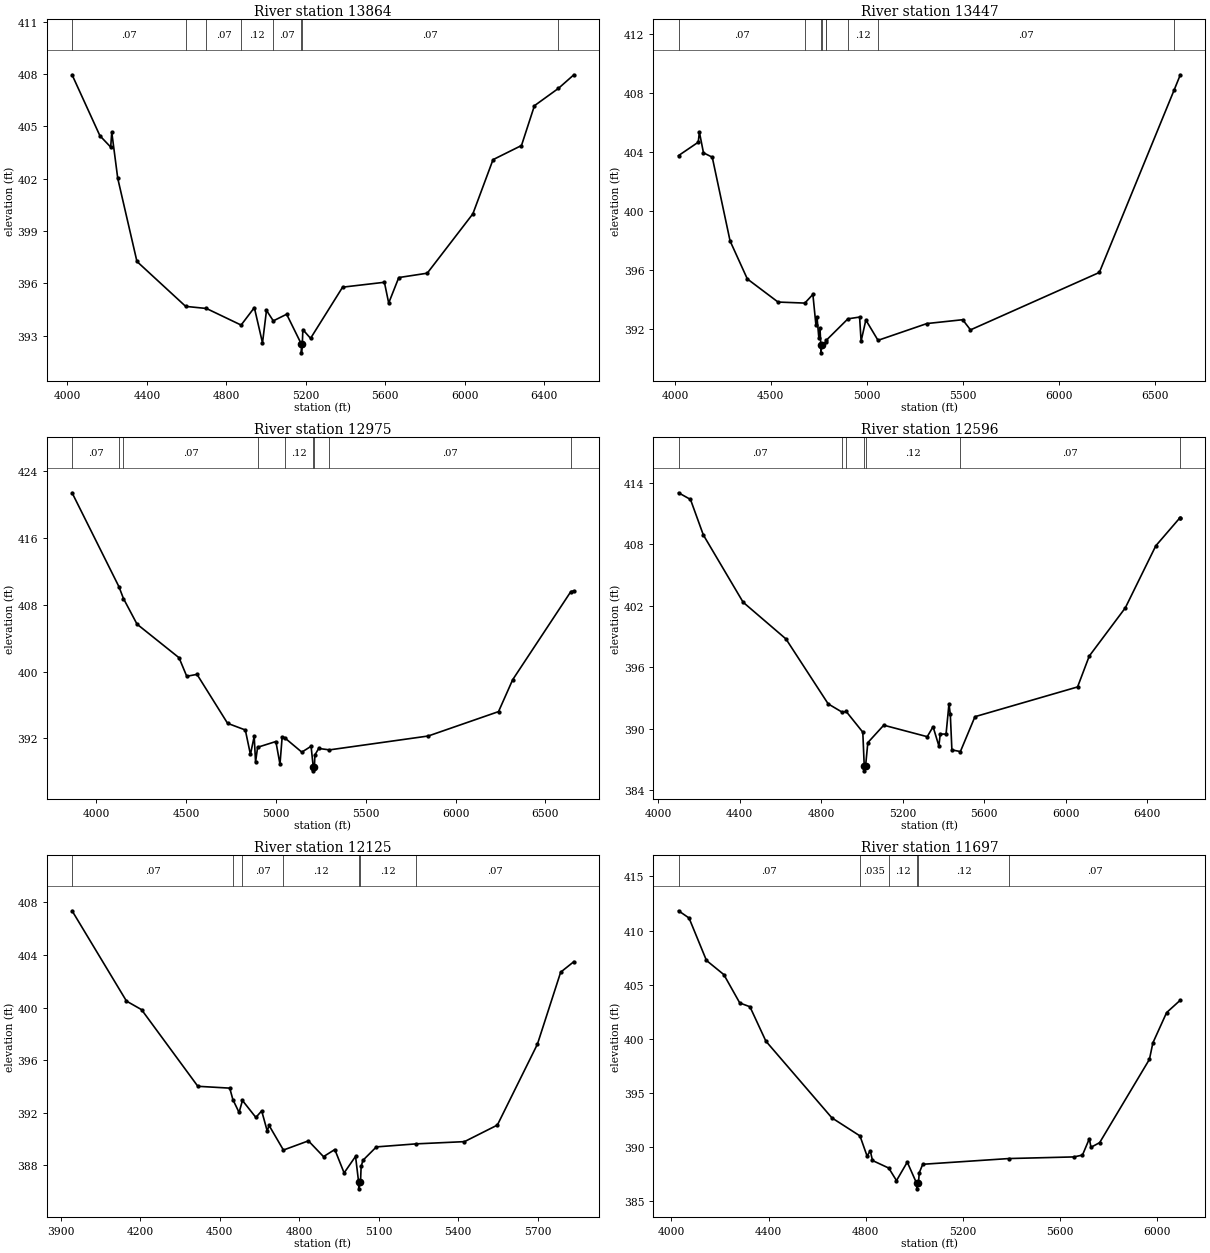
Type RM Length L Ch R = 1 ,13864   ,417,417,417
BEGIN DESCRIPTION:
XS7077
END DESCRIPTION:
XS GIS Cut Line= 4
      2373729.05      13713011.4      2372860.64     13712672.62
      2372393.03     13712729.88      2371472.09     13713369.29
#Sta/Elev= 30
  4023.9  407.95  4163.9  404.46  4218.2  403.81  4223.6  404.66  4253.7  402.02
  4350.3  397.26  4595.4  394.69  4699.9  394.57  4874.3  393.62  4940.9  394.62
  4981.9   392.6    5002  394.46  5036.3  393.86  5103.4  394.24  5177.4  392.53
  5177.7  392.03  5182.3  392.53  5184.9  393.36  5223.7  392.86  5384.9  395.79
  5595.2  396.07  5616.8  394.88  5667.5  396.34  5810.7  396.59  6040.3  399.99
  6141.6  403.09  6284.8   403.9    6350  406.18  6470.5  407.17  6548.3  407.95
#Mann= 8 ,-1 , 0
  4023.9     .07       0  4595.4    .035       0  4699.9     .07       0
  4874.3     .12       0  5036.3     .07       0  5177.4     .05       0
  5182.3     .07       0  6470.5    .035       0
Bank Sta=5177.4,5182.3
XS Rating Curve= 0 ,0
Exp/Cntr=0.3,0.1

Type RM Length L Ch R = 1 ,13447   ,472,472,472
BEGIN DESCRIPTION:
XS7076
END DESCRIPTION:
XS GIS Cut Line= 4
      2373676.57     13712763.28      2372865.41     13712286.13
      2372650.69     13712309.99       2371319.7     13712906.31
#Sta/Elev= 30
    4019  403.77  4121.8  404.68  4127.6  405.37    4149  403.96  4194.8  403.66
  4287.7  397.97  4377.6  395.39  4537.7  393.82  4677.4  393.75  4719.3  394.34
  4734.9  392.29  4740.7  392.81  4750.6  391.35  4756.4  392.04  4760.9  390.87
  4761.2  390.37  4765.8  390.87  4787.6  391.12  4789.7  391.23    4902  392.68
  4962.8   392.8  4970.6  391.16  4995.4   392.6  5058.8  391.22  5313.9  392.36
  5500.1  392.62  5540.8  391.93  6212.4  395.83  6602.2  408.22  6634.6  409.26
#Mann= 9 ,-1 , 0
    4019     .07       0  4677.4     .12       0  4760.9     .05       0
  4765.8     .12       0  4787.6     .07       0  4789.7    .035       0
    4902     .12       0  5058.8     .07       0  6602.2    .035       0
Bank Sta=4760.9,4765.8
XS Rating Curve= 0 ,0
Exp/Cntr=0.3,0.1

Type RM Length L Ch R = 1 ,12975   ,379,379,379
BEGIN DESCRIPTION:
Stream0563 26.0
END DESCRIPTION:
XS GIS Cut Line= 3
      2373574.96     13711225.03      2372703.18     13711971.21
      2371314.64     13712853.96
#Sta/Elev= 30
  3865.6   421.4  4126.1  410.17  4151.8  408.73  4227.2  405.67    4461  401.65
  4503.9  399.43  4560.9  399.66  4731.1   393.8  4829.9     393  4858.4  390.07
  4879.3  392.24  4886.9  389.16  4898.2  390.93    5000  391.62  5022.8   388.9
    5035  392.19  5048.3  392.08  5144.3  390.35  5195.9  391.05  5207.8  388.61
  5208.3  388.11  5214.6  388.61  5217.1  390.01  5238.3  390.79  5298.3  390.62
    5848  392.28  6239.2   395.2    6318  399.02    6642  409.58  6658.5  409.66
#Mann= 9 ,-1 , 0
  3865.6     .07       0  4126.1     .12       0  4151.8     .07       0
  4898.2    .035       0  5048.3     .12       0  5207.8    .035       0
  5214.6     .12       0  5298.3     .07       0    6642    .035       0
Bank Sta=5207.8,5214.6
XS Rating Curve= 0 ,0
Exp/Cntr=0.3,0.1

Type RM Length L Ch R = 1 ,12596   ,471,471,471
BEGIN DESCRIPTION:
Stream0563 25.0
END DESCRIPTION:
XS GIS Cut Line= 3
      2373224.97     13711225.02        2372475.       13711725.
      2371275.01       13712725.
#Sta/Elev= 30
  4099.6     413  4158.2  412.35  4221.3  408.89  4416.6  402.33  4626.9  398.75
  4834.2  392.42  4903.6   391.6  4922.6  391.68  5004.2  389.66  5011.2  386.39
  5011.7  385.89    5018  386.39  5028.9  388.64    5107  390.34  5320.5  389.22
  5349.2  390.19  5377.8  388.31  5384.3  389.48  5412.9  389.47  5427.3  392.43
  5433.8   391.4  5441.6  387.93  5483.3  387.77  5554.8  391.17  6058.6  394.07
  6115.9  397.08  6292.9  401.78  6442.6  407.83  6561.4  410.57    6563  410.57
#Mann= 7 ,-1 , 0
  4099.6     .07       0  4903.6    .035       0  4922.6     .12       0
  5011.2     .05       0    5018     .12       0  5483.3     .07       0
  6561.4    .035       0
Bank Sta=5011.2,5018
XS Rating Curve= 0 ,0
Exp/Cntr=0.3,0.1

Type RM Length L Ch R = 1 ,12125   ,428,428,428
BEGIN DESCRIPTION:
Stream0563 24.0
END DESCRIPTION:
XS GIS Cut Line= 3
      2372774.98     13710925.02        2372075.       13711725.
      2371375.04     13712174.97
#Sta/Elev= 30
  3941.8  407.36  4147.3  400.49  4204.2  399.84  4416.8  394.01  4537.3  393.87
  4549.1     393  4572.5  392.02  4585.3  392.93    4636  391.64  4657.9  392.14
  4678.8  390.61  4685.9  391.03    4740  389.16  4834.4  389.86  4891.4  388.66
  4934.1   389.2  4969.2  387.42  5012.4  388.68  5024.1  386.71  5024.6  386.21
  5031.1  386.71  5033.5  387.91  5040.4  388.38    5091   389.4  5240.5  389.63
  5423.8   389.8    5548  391.06  5699.2  397.21  5787.1  402.69  5836.9  403.49
#Mann= 7 ,-1 , 0
  3941.8     .07       0  4549.1    .035       0  4585.3     .07       0
    4740     .12       0  5024.1     .05       0  5031.1     .12       0
  5240.5     .07       0
Bank Sta=5024.1,5031.1
XS Rating Curve= 0 ,0
Exp/Cntr=0.3,0.1

Type RM Length L Ch R = 1 ,11697   ,485,485,485
BEGIN DESCRIPTION:
Stream0563 23.0
END DESCRIPTION:
XS GIS Cut Line= 3
      2372874.97     13710775.02        2372075.       13711325.
      2371324.98     13712125.02
#Sta/Elev= 30
  4029.3  411.83  4072.6  411.16  4144.3  407.24    4216  405.93  4281.6  403.31
  4323.5  402.96  4389.2  399.78  4661.1  392.69  4776.9  391.02  4805.9  389.17
  4819.4  389.64  4828.3  388.75  4895.4  388.05  4927.3  386.89  4971.7   388.6
  5010.5  386.63    5011  386.13  5017.5  386.63  5021.3  387.63  5035.5   388.4
  5390.5  388.93    5658  389.08  5693.5  389.25  5721.8  390.76  5728.6  389.97
  5764.3   390.4  5969.4   398.1  5983.6  399.62  6040.2  402.42  6096.7  403.57
#Mann= 6 ,-1 , 0
  4029.3     .07       0  4776.9    .035       0  4895.4     .12       0
  5010.5     .05       0  5017.5     .12       0  5390.5     .07       0
Bank Sta=5010.5,5017.5
XS Rating Curve= 0 ,0
Exp/Cntr=0.3,0.1

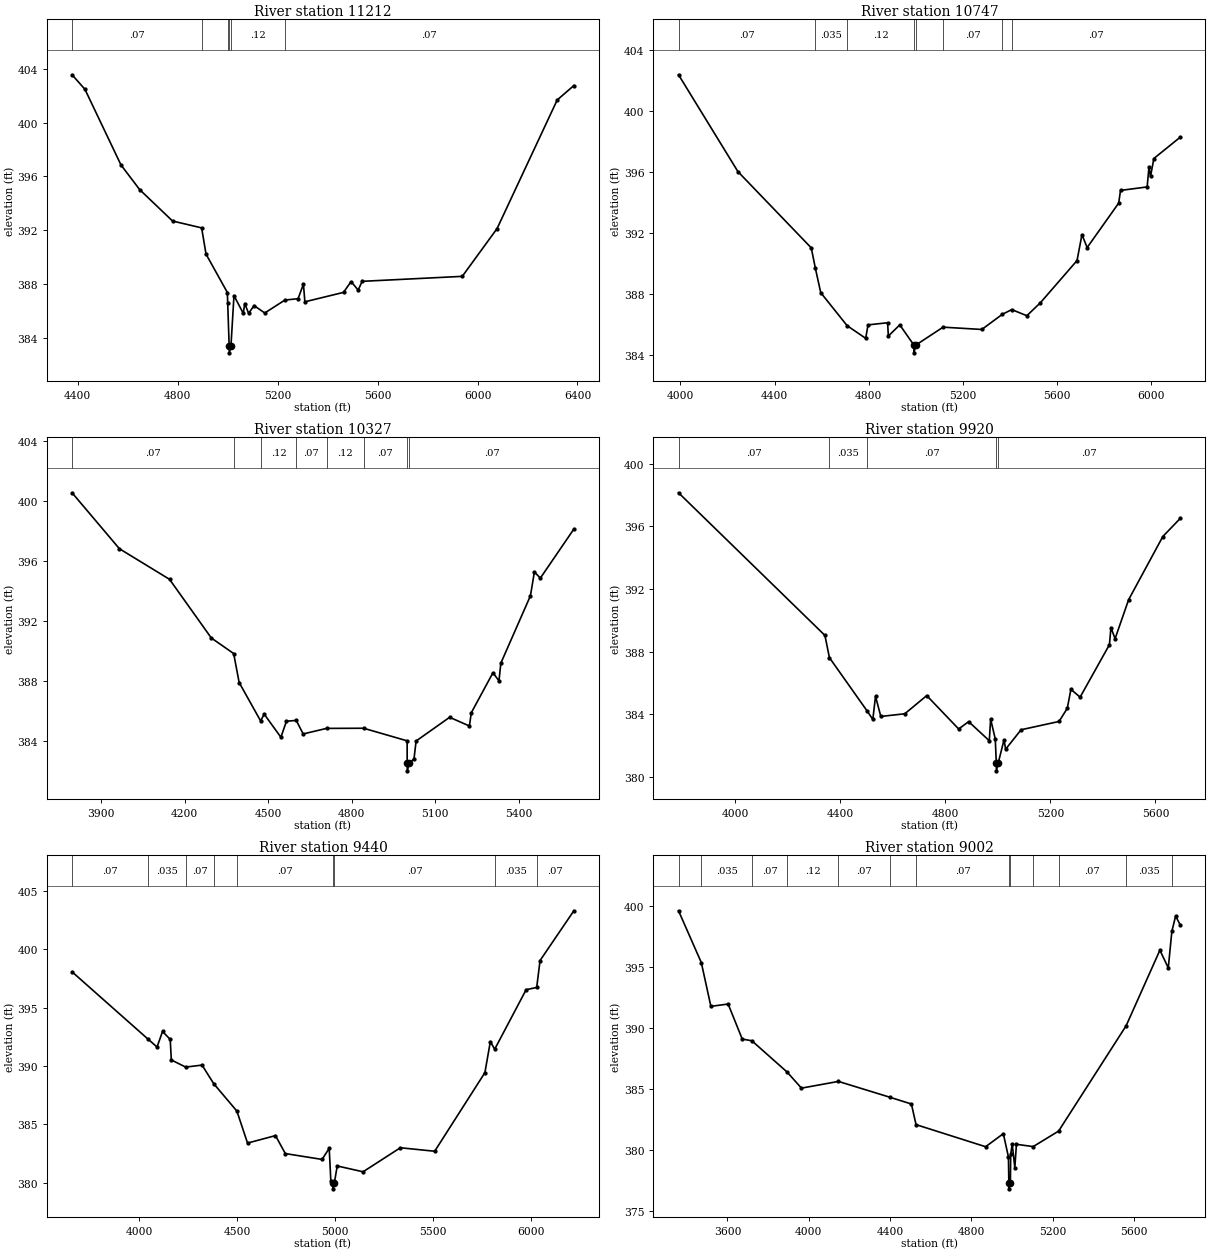
Type RM Length L Ch R = 1 ,11212   ,465,465,465
BEGIN DESCRIPTION:
Stream0563 22.0
END DESCRIPTION:
XS GIS Cut Line= 3
        2372575.       13710725.        2371975.       13710875.
        2371275.     13712074.99
#Sta/Elev= 30
  4377.8  403.55  4429.3  402.47  4573.6  396.85  4648.4  395.02  4779.8  392.69
  4896.2  392.18  4913.8  390.23  4999.2  387.38  5000.5  386.58  5006.4   383.4
  5006.9   382.9  5013.5   383.4  5025.6  387.15  5062.8  385.83  5068.6  386.56
  5084.3  385.83  5105.8  386.41  5148.8  385.86  5229.4  386.82    5282  386.92
  5303.5     388  5309.3  386.69  5463.9  387.39  5494.1  388.19  5522.6  387.56
  5538.3  388.21    5939  388.58  6078.3  392.13  6318.9  401.68  6385.5  402.75
#Mann= 6 ,-1 , 0
  4377.8     .07       0  4896.2    .035       0  5000.5     .12       0
  5006.4    .035       0  5013.5     .12       0  5229.4     .07       0
Bank Sta=5006.4,5013.5
XS Rating Curve= 0 ,0
Exp/Cntr=0.3,0.1

Type RM Length L Ch R = 1 ,10747   ,420,420,420
BEGIN DESCRIPTION:
XS7075
END DESCRIPTION:
XS GIS Cut Line= 3
      2372536.19     13710609.41      2371648.67     13710690.53
      2370847.08     13711635.26
#Sta/Elev= 30
  3992.2  402.35  4244.4  396.01  4555.7  391.02  4572.9   389.7  4595.9  388.09
  4707.8  385.93  4786.7   385.1  4796.7  385.98  4879.9  386.12  4882.8  385.25
  4931.5  385.98  4991.6  384.65  4992.1  384.15  4998.7  384.65  5115.2  385.83
  5279.7  385.68  5366.6  386.67  5406.7  386.98  5470.8  386.58  5527.9  387.42
  5683.9  390.19  5704.8  391.89  5726.8  391.04  5860.7  393.95  5868.5  394.78
  5981.6  395.01  5989.3  396.31  5995.9   395.7  6010.1  396.87  6122.4  398.27
#Mann= 8 ,-1 , 0
  3992.2     .07       0  4572.9    .035       0  4707.8     .12       0
  4991.6     .05       0  4998.7     .12       0  5115.2     .07       0
  5366.6    .035       0  5406.7     .07       0
Bank Sta=4991.6,4998.7
XS Rating Curve= 0 ,0
Exp/Cntr=0.3,0.1

Type RM Length L Ch R = 1 ,10327   ,407,407,407
BEGIN DESCRIPTION:
Stream0563 21.0
END DESCRIPTION:
XS GIS Cut Line= 3
      2372475.01       13710525.        2371275.       13710525.
        2370875.     13710975.01
#Sta/Elev= 30
  3795.5  400.58  3965.5  396.85  4145.5  394.81  4295.5   390.9  4375.9  389.86
  4395.5  387.93  4472.6  385.37  4485.5  385.82  4545.5  384.28  4565.5  385.35
  4600.7   385.4  4625.5   384.5  4709.3  384.87  4842.5  384.88  4998.9  384.04
    4999  382.54  4999.5  382.04  5006.2  382.54  5023.5  382.84  5031.1  384.03
  5151.5  385.61  5222.5  385.03  5229.2  385.91    5307  388.58  5328.7  388.04
  5335.4  389.22  5441.6  393.71  5455.9   395.3  5477.2  394.89  5597.6  398.16
#Mann= 8 ,-1 , 0
  3795.5     .07       0  4375.9    .035       0  4472.6     .12       0
  4600.7     .07       0  4709.3     .12       0  4842.5     .07       0
    4999     .05       0  5006.2     .07       0
Bank Sta=4999,5006.2
XS Rating Curve= 0 ,0
Exp/Cntr=0.3,0.1

Type RM Length L Ch R = 1 ,9920    ,480,480,480
BEGIN DESCRIPTION:
Stream0563 20.0
END DESCRIPTION:
XS GIS Cut Line= 3
      2372374.98       13710475.        2371175.       13710275.
      2370824.98     13710875.04
#Sta/Elev= 30
  3783.5  398.14  4341.1  389.04  4358.2  387.62  4501.7  384.22  4523.5  383.68
  4533.7  385.15    4554  383.87  4645.2  384.04  4728.8   385.2  4850.5  383.07
  4888.5  383.54  4967.1  382.32  4972.2   383.7  4989.9  382.43  4993.8   380.9
  4994.3   380.4  5001.1   380.9  5023.2  382.38  5029.4  381.78  5088.1  383.02
  5232.8  383.55  5264.2  384.39  5277.9   385.6    5313   385.1  5424.7  388.45
  5430.4  389.54  5446.2  388.83  5497.8  391.32  5628.1  395.35  5694.7  396.51
#Mann= 5 ,-1 , 0
  3783.5     .07       0  4358.2    .035       0  4501.7     .07       0
  4993.8     .05       0  5001.1     .07       0
Bank Sta=4993.8,5001.1
XS Rating Curve= 0 ,0
Exp/Cntr=0.3,0.1

Type RM Length L Ch R = 1 ,9440    ,438,438,438
BEGIN DESCRIPTION:
Stream0563 19.0
END DESCRIPTION:
XS GIS Cut Line= 3
      2372375.04     13710425.02        2371175.       13709825.
      2369975.04     13710024.99
#Sta/Elev= 30
  3658.8  398.07  4045.7  392.31  4092.1  391.63    4120  392.96  4159.2  392.28
  4164.8  390.52    4238  389.91  4321.3  390.08  4381.3  388.48  4499.1  386.14
  4553.3   383.4  4695.8  384.04  4746.1   382.5  4933.4     382  4969.7  382.95
  4978.1  380.15  4988.5  379.98    4989  379.48  4995.8  379.98  5010.6  381.44
  5142.4  380.94  5332.5     383  5507.4   382.7  5763.4  389.43  5791.2  392.09
  5813.4  391.44  5973.7  396.54  6027.5  396.73  6044.7  399.04    6217   403.3
#Mann= 9 ,-1 , 0
  3658.8     .07       0  4045.7    .035       0    4238     .07       0
  4381.3    .035       0  4499.1     .07       0  4988.5     .05       0
  4995.8     .07       0  5813.4    .035       0  6027.5     .07       0
Bank Sta=4988.5,4995.8
XS Rating Curve= 0 ,0
Exp/Cntr=0.3,0.1

Type RM Length L Ch R = 1 ,9002    ,448,448,448
BEGIN DESCRIPTION:
Stream0563 18.0
END DESCRIPTION:
XS GIS Cut Line= 3
      2372425.04     13709074.98        2370875.       13709625.
      2370074.96     13709825.01
#Sta/Elev= 30
  3359.6  399.63  3471.6  395.39  3518.8   391.8  3603.7  391.99  3673.1  389.12
  3720.5  388.98  3893.7  386.42  3964.5   385.1  4146.4  385.65  4398.4  384.36
  4505.6   383.8  4528.4  382.11  4870.7   380.3    4958  381.37  4983.1  379.46
  4985.1  377.35  4985.6  376.85  4992.7  377.35  4994.2  379.67  5001.7  380.53
  5014.6  378.58  5022.4   380.5  5104.8  380.31  5229.9  381.58  5562.3  390.21
  5728.5   396.4  5769.7  394.95  5787.3  397.94  5805.8   399.2    5829  398.46
#Mann= 13 ,-1 , 0
  3359.6     .05       0  3471.6    .035       0  3720.5     .07       0
  3893.7     .12       0  4146.4     .07       0  4398.4     .12       0
  4528.4     .07       0  4985.1     .05       0  4992.7     .07       0
  5104.8     .05       0  5229.9     .07       0  5562.3    .035       0
  5787.3     .07       0
Bank Sta=4985.1,4992.7
XS Rating Curve= 0 ,0
Exp/Cntr=0.3,0.1

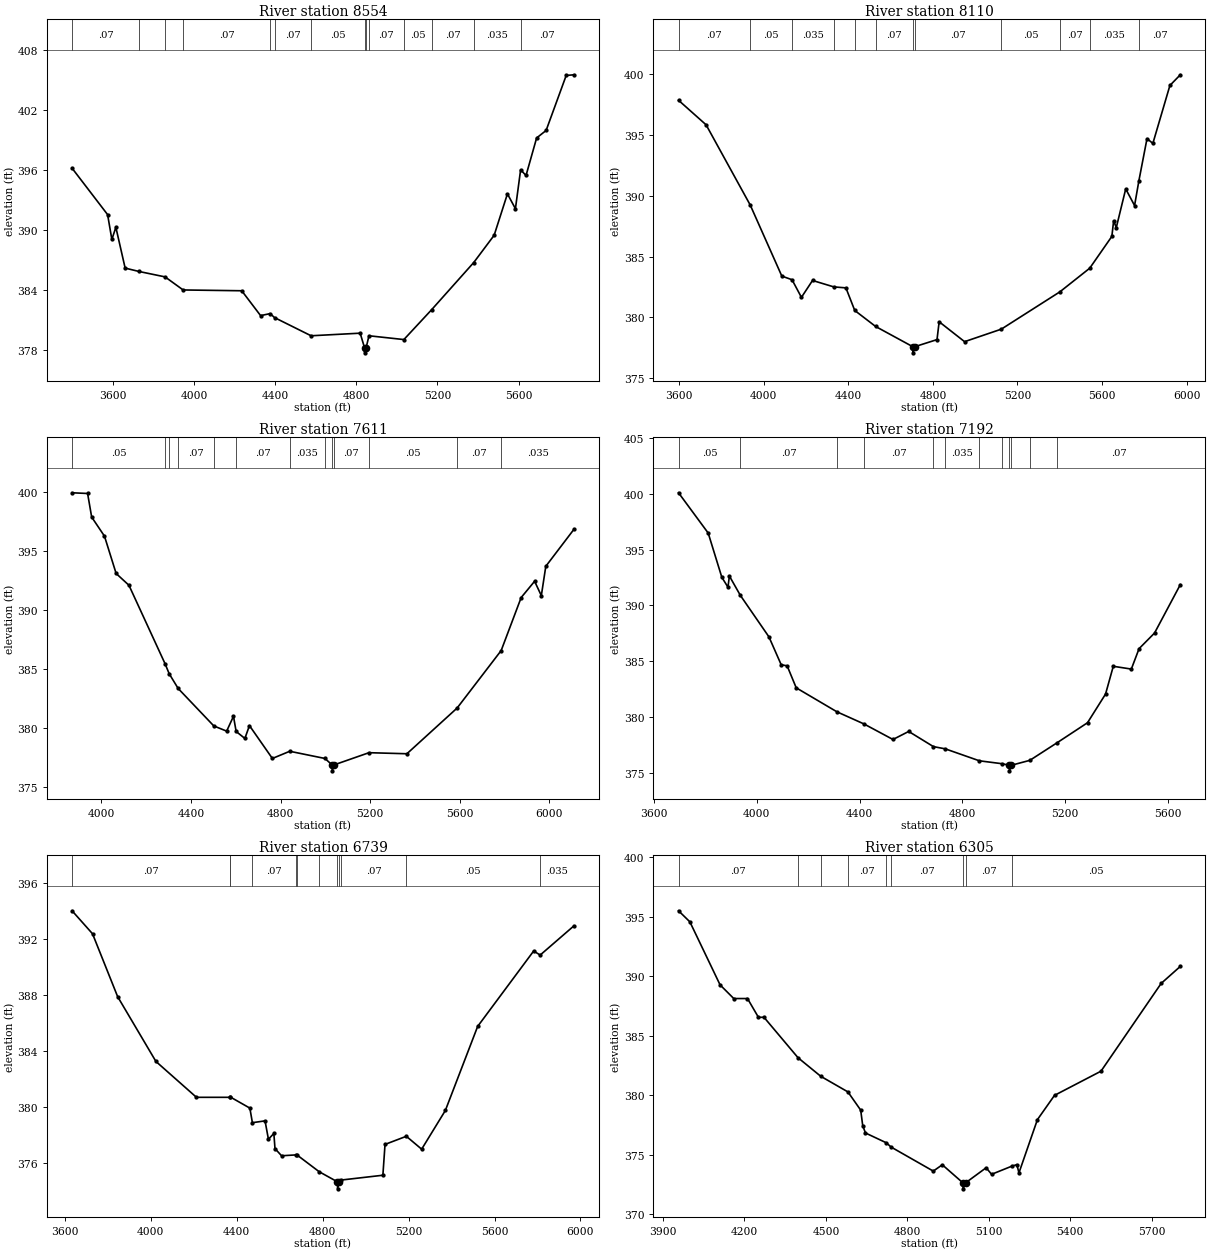
Type RM Length L Ch R = 1 ,8554    ,444,444,444
BEGIN DESCRIPTION:
Stream0563 17.0
END DESCRIPTION:
XS GIS Cut Line= 3
        2372175.       13708925.        2370625.       13709325.
        2369825.       13709675.
#Sta/Elev= 30
  3398.7  396.19  3573.9  391.54  3594.9  389.05  3614.6  390.27  3660.4  386.18
  3729.1  385.84  3857.2   385.3  3946.3  383.99  4235.2  383.91  4328.2  381.42
  4375.2  381.62    4397  381.22  4577.1   379.4  4819.1  379.66  4840.8  378.19
  4841.3  377.69  4848.4  378.19  4862.5   379.4  5034.6  379.02  5171.4  382.01
  5379.1  386.74  5479.7  389.47  5545.2  393.62  5584.6  392.13  5610.2  396.03
  5636.9  395.46  5689.1  399.22  5735.9  399.97  5834.9  405.48  5872.7  405.55
#Mann= 14 ,-1 , 0
  3398.7     .07       0  3729.1    .035       0  3857.2     .12       0
  3946.3     .07       0  4375.2     .12       0    4397     .07       0
  4577.1     .05       0  4840.8     .05       0  4848.4     .05       0
  4862.5     .07       0  5034.6     .05       0  5171.4     .07       0
  5379.1    .035       0  5610.2     .07       0
Bank Sta=4840.8,4848.4
XS Rating Curve= 0 ,0
Exp/Cntr=0.3,0.1

Type RM Length L Ch R = 1 ,8110    ,499,499,499
BEGIN DESCRIPTION:
Stream0563 16.0
END DESCRIPTION:
XS GIS Cut Line= 3
      2372075.03       13708825.        2370675.       13708925.
      2369875.02     13709474.99
#Sta/Elev= 30
  3596.3  397.87  3726.7  395.85  3935.6  389.24  4085.1  383.39  4133.4  383.09
  4177.8  381.64  4230.4  383.03  4331.2   382.5  4388.3  382.42  4430.1  380.56
    4529  379.24  4705.4  377.57  4705.9  377.07    4713  377.57  4819.4  378.16
  4829.5  379.63  4949.8  377.99  5123.6  379.02  5400.5  382.09    5542  384.04
  5646.7  386.66  5655.2  387.95  5667.6  387.38  5712.3  390.57  5754.2   389.2
  5774.6  391.24    5813  394.71  5840.8  394.32  5921.4  399.09  5970.7  399.97
#Mann= 12 ,-1 , 0
  3596.3     .07       0  3935.6     .05       0  4133.4    .035       0
  4331.2     .07       0  4430.1     .05       0    4529     .07       0
  4705.4     .05       0    4713     .07       0  5123.6     .05       0
  5400.5     .07       0    5542    .035       0  5774.6     .07       0
Bank Sta=4705.4,4713
XS Rating Curve= 0 ,0
Exp/Cntr=0.3,0.1

Type RM Length L Ch R = 1 ,7611    ,419,419,419
BEGIN DESCRIPTION:
Stream0563 15.0
END DESCRIPTION:
XS GIS Cut Line= 3
      2371973.14     13708676.94       2371023.6     13708495.62
      2369749.76     13708457.45
#Sta/Elev= 30
  3868.6  399.93    3938  399.87  3956.1  397.87  4013.3  396.25  4065.4  393.08
  4122.6  392.08  4283.7  385.43  4302.4  384.57  4342.4  383.32  4501.7  380.14
    4559   379.7  4589.5  380.96  4601.4  379.67  4640.4  379.08  4660.8  380.17
  4763.2  377.38  4840.8  377.99    4998  377.38  5030.1  376.83  5030.6  376.33
  5037.9  376.83  5194.7  377.87  5364.1  377.78  5588.3  381.66  5785.1  386.54
  5874.4  391.04  5934.4  392.42  5964.4   391.2  5984.4  393.69  6109.7  396.82
#Mann= 13 ,-1 , 0
  3868.6     .05       0  4283.7     .07       0  4302.4     .05       0
  4342.4     .07       0  4501.7    .035       0  4601.4     .07       0
  4840.8    .035       0    4998     .07       0  5030.1     .05       0
  5037.9     .07       0  5194.7     .05       0  5588.3     .07       0
  5785.1    .035       0
Bank Sta=5030.1,5037.9
XS Rating Curve= 0 ,0
Exp/Cntr=0.3,0.1

Type RM Length L Ch R = 1 ,7192    ,453,453,453
BEGIN DESCRIPTION:
Stream0563 14.0
END DESCRIPTION:
XS GIS Cut Line= 3
      2371925.04     13708625.02        2370725.       13708125.
      2370074.96       13708175.
#Sta/Elev= 30
  3695.6   400.1    3811  396.49  3864.1  392.52  3887.9  391.64  3893.4  392.64
  3936.2   390.9  4047.2  387.19  4094.9  384.69  4118.1  384.59  4153.4  382.62
  4311.8  380.47  4417.2  379.38  4529.8  377.99    4591  378.71  4687.2  377.35
  4733.3  377.15  4865.8  376.08  4953.5  375.82  4982.5  375.68    4983  375.18
  4990.3  375.68  5062.1  376.12  5166.4  377.67  5286.5  379.49  5356.7  382.06
  5386.8  384.55    5457   384.3  5487.1  386.13  5547.3  387.53  5647.6  391.87
#Mann= 12 ,-1 , 0
  3695.6     .05       0  3936.2     .07       0  4311.8    .035       0
  4417.2     .07       0  4687.2     .05       0  4733.3    .035       0
  4865.8     .05       0  4953.5    .035       0  4982.5    .035       0
  4990.3    .035       0  5062.1     .05       0  5166.4     .07       0
Bank Sta=4982.5,4990.3
XS Rating Curve= 0 ,0
Exp/Cntr=0.3,0.1

Type RM Length L Ch R = 1 ,6739    ,434,434,434
BEGIN DESCRIPTION:
Stream0563 13.0
END DESCRIPTION:
XS GIS Cut Line= 3
      2372059.06     13708242.74        2370775.       13707775.
      2369808.45     13707846.57
#Sta/Elev= 30
  3633.4  394.02  3728.6  392.38  3845.6  387.89  4023.7  383.27  4212.4  380.71
  4366.7  380.71  4369.2  380.74    4461  379.94  4472.8   378.9  4531.7  379.03
  4547.4  377.72  4572.7  378.13    4578  377.05  4608.6  376.54  4674.6   376.6
  4680.2   376.6  4783.8   375.4  4868.8  374.68  4869.3  374.18  4877.4  374.68
  4887.5  374.81  5080.2  375.15  5090.2  377.35  5189.4  377.93  5260.7  377.01
    5371  379.77  5521.4  385.77  5782.1  391.15  5812.4  390.86  5969.2  392.94
#Mann= 12 ,-1 , 0
  3633.4     .07       0  4366.7     .12       0  4369.2    .035       0
  4472.8     .07       0  4674.6     .05       0  4680.2     .07       0
  4783.8     .05       0  4868.8     .05       0  4877.4     .05       0
  4887.5     .07       0  5189.4     .05       0  5812.4    .035       0
Bank Sta=4868.8,4877.4
XS Rating Curve= 0 ,0
Exp/Cntr=0.3,0.1

Type RM Length L Ch R = 1 ,6305    ,446,446,446
BEGIN DESCRIPTION:
Stream0563 12.0
END DESCRIPTION:
XS GIS Cut Line= 3
      2371906.31     13707221.62        2370875.       13707375.
      2370074.98       13707275.
#Sta/Elev= 30
    3957   395.5  3998.8  394.57    4110  389.28  4160.5  388.13  4211.1  388.13
  4251.5  386.55  4271.7  386.56  4397.3  383.16  4481.1   381.6  4581.1  380.29
  4628.2  378.76  4635.7  377.45  4645.8  376.84  4722.3  376.02  4740.1  375.66
  4895.6  373.64  4928.9  374.17    5005  372.65  5005.5  372.15  5014.4  372.65
  5090.4  373.92  5110.5  373.37  5186.8  374.07  5203.7  374.18  5211.3  373.49
  5279.3  377.96  5342.3     380  5513.6  382.03  5735.3   389.4  5805.9  390.83
#Mann= 9 ,-1 , 0
    3957     .07       0  4397.3     .12       0  4481.1    .035       0
  4581.1     .07       0  4722.3     .05       0  4740.1     .07       0
    5005     .05       0  5014.4     .07       0  5186.8     .05       0
Bank Sta=5005,5014.4
XS Rating Curve= 0 ,0
Exp/Cntr=0.3,0.1

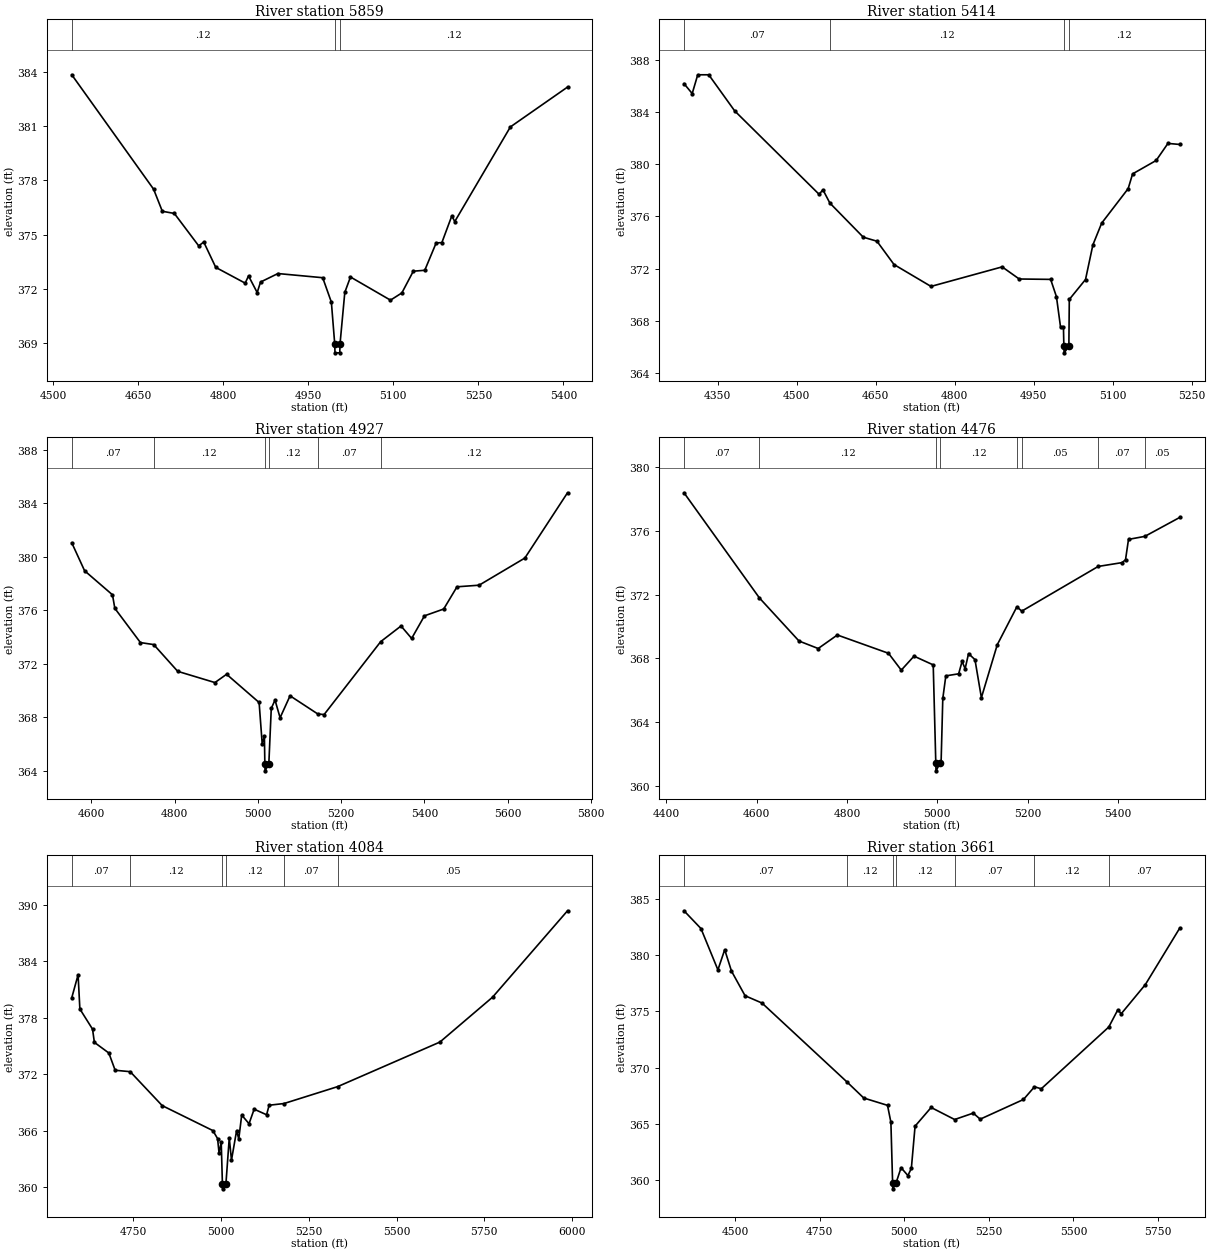
Type RM Length L Ch R = 1 ,5859    ,445,445,445
BEGIN DESCRIPTION:
Stream0563 11.0
END DESCRIPTION:
XS GIS Cut Line= 3
      2371224.99       13706725.        2370825.       13706975.
        2370425.       13707025.
#Sta/Elev= 30
  4532.5  383.84  4676.9  377.52  4692.3   376.3  4713.5  376.18  4756.5  374.39
  4765.4   374.6  4786.6   373.2  4838.5  372.33  4844.4  372.73  4859.7  371.81
  4865.6  372.39  4896.3  372.86  4975.3  372.63  4990.6  371.28  4996.5  368.98
    4997  368.48  5005.4  368.48  5005.9  368.98  5014.3  371.82  5024.3  372.67
  5094.9  371.39    5115  371.79  5135.2  372.99  5155.4  373.04  5175.5  374.55
  5185.6  374.57  5203.2  376.05  5208.3  375.73  5306.5  380.96  5407.3  383.16
#Mann= 3 ,-1 , 0
  4532.5     .12       0  4996.5     .05       0  5005.9     .12       0
Bank Sta=4996.5,5005.9
XS Rating Curve= 0 ,0
Exp/Cntr=0.3,0.1

Type RM Length L Ch R = 1 ,5414    ,487,487,487
BEGIN DESCRIPTION:
Stream0563 10.0
END DESCRIPTION:
XS GIS Cut Line= 3
       2371309.9     13706510.66        2370625.       13706725.
      2370424.97     13706825.02
#Sta/Elev= 30
    4286   386.2  4301.6  385.44  4312.1  386.88    4333  386.88  4382.2  384.11
  4542.6   377.7  4549.8  378.05    4563  377.03  4626.4  374.41  4652.4   374.1
  4684.8  372.31    4755  370.63  4890.1  372.13  4922.5   371.2  4982.2  371.17
  4993.2  369.84    5001   367.5  5006.5   367.5  5007.3  366.03  5007.8  365.53
  5016.8  366.03  5017.6  369.63  5048.4  371.16  5062.4  373.82  5079.1  375.49
  5129.4  378.14  5137.8  379.27  5182.5   380.3  5204.9  381.61  5227.3  381.53
#Mann= 4 ,-1 , 0
    4286     .07       0    4563     .12       0  5007.3     .05       0
  5016.8     .12       0
Bank Sta=5007.3,5016.8
XS Rating Curve= 0 ,0
Exp/Cntr=0.3,0.1

Type RM Length L Ch R = 1 ,4927    ,451,451,451
BEGIN DESCRIPTION:
Stream0563 9.0
END DESCRIPTION:
XS GIS Cut Line= 3
      2371125.02     13706475.01        2370725.       13706275.
      2370025.03     13706524.99
#Sta/Elev= 30
  4553.2  381.06    4584  378.97    4651  377.17  4656.6  376.16  4718.1   373.6
    4750  373.45  4807.6  371.45    4897  370.61    4925  371.23  5003.1  369.12
  5010.5  366.04  5015.8  366.58  5016.9  364.51  5017.4  364.01  5026.4  364.51
  5032.3  368.68  5041.3   369.3  5053.5  367.98  5077.4  369.62  5144.1  368.26
  5159.2  368.22  5295.1  373.67  5343.9  374.84  5369.4  373.91  5400.2   375.6
  5446.4  376.11  5478.3  377.77  5531.4  377.89  5641.3  379.92  5743.7   384.8
#Mann= 6 ,-1 , 0
  4553.2     .07       0    4750     .12       0  5016.9     .05       0
  5026.4     .12       0  5144.1     .07       0  5295.1     .12       0
Bank Sta=5016.9,5026.4
XS Rating Curve= 0 ,0
Exp/Cntr=0.3,0.1

Type RM Length L Ch R = 1 ,4476    ,392,392,392
BEGIN DESCRIPTION:
Stream0563 8.0
END DESCRIPTION:
XS GIS Cut Line= 3
      2370975.02     13705474.98        2370575.       13705875.
      2370175.01     13706224.99
#Sta/Elev= 30
  4439.3  378.41  4606.2   371.8  4693.9  369.09  4736.3  368.62  4778.7  369.47
  4891.9  368.32  4920.2  367.26  4948.4  368.14  4990.9  367.59  4996.6  361.43
  4997.1  360.93  5006.4  361.43  5008.3  361.43  5012.1  365.48  5018.8   366.9
  5047.2  367.03  5054.8  367.81  5061.5  367.35  5069.1   368.3  5083.3  367.92
  5097.5  365.53  5132.7  368.86    5176  371.24  5186.9  370.97  5356.1  373.78
  5408.9  374.02  5416.5   374.2  5423.1  375.48  5459.3  375.67  5536.5  376.86
#Mann= 8 ,-1 , 0
  4439.3     .07       0  4606.2     .12       0  4996.6     .05       0
  5006.4     .12       0    5176     .07       0  5186.9     .05       0
  5356.1     .07       0  5459.3     .05       0
Bank Sta=4996.6,5006.4
XS Rating Curve= 0 ,0
Exp/Cntr=0.3,0.1

Type RM Length L Ch R = 1 ,4084    ,423,423,423
BEGIN DESCRIPTION:
Stream0563 7.0
END DESCRIPTION:
XS GIS Cut Line= 3
      2370974.96     13705425.01        2370575.       13705525.
      2369774.97     13706125.02
#Sta/Elev= 30
  4574.6  380.11  4592.6  382.55  4597.7  378.92  4633.8  376.78    4639  375.38
  4680.2  374.25  4698.2  372.42  4741.1  372.27  4832.2  368.67  4976.6  366.02
    4990  365.17  4994.2  363.64  5000.4  364.79  5003.8  360.34  5004.3  359.84
  5013.7  360.34  5023.3  365.25  5029.6  362.88  5044.2  366.02  5050.4  365.13
  5058.7  367.67  5079.6  366.75  5094.2  368.29  5129.6   367.7  5136.9  368.71
  5179.2  368.89  5331.8  370.68  5623.3  375.41  5773.3  380.17  5986.9  389.34
#Mann= 6 ,-1 , 0
  4574.6     .07       0  4741.1     .12       0  5003.8     .05       0
  5013.7     .12       0  5179.2     .07       0  5331.8     .05       0
Bank Sta=5003.8,5013.7
XS Rating Curve= 0 ,0
Exp/Cntr=0.3,0.1

Type RM Length L Ch R = 1 ,3661    ,470,470,470
BEGIN DESCRIPTION:
Stream0563 6.0
END DESCRIPTION:
XS GIS Cut Line= 3
      2371125.03       13705225.        2370475.       13705175.
      2369674.99       13705325.
#Sta/Elev= 30
  4348.4  383.94  4398.6  382.36  4448.7  378.69  4468.8  380.48  4488.8  378.58
    4529  376.39  4579.1  375.74    4831  368.71    4880   367.3  4950.2  366.65
  4960.2  365.15  4965.3  359.73  4965.8  359.23  4975.2  359.73  4990.3  361.11
  5010.5  360.41  5020.7  361.05  5031.7   364.8  5079.2  366.46  5148.7  365.39
  5203.8  365.96  5224.2  365.42  5352.2  367.17  5384.8   368.3  5404.8  368.12
  5604.5  373.61  5631.2  375.14  5641.3  374.79  5712.6  377.38  5814.3   382.4
#Mann= 7 ,-1 , 0
  4348.4     .07       0    4831     .12       0  4965.3     .05       0
  4975.2     .12       0  5148.7     .07       0  5384.8     .12       0
  5604.5     .07       0
Bank Sta=4965.3,4975.2
XS Rating Curve= 0 ,0
Exp/Cntr=0.3,0.1