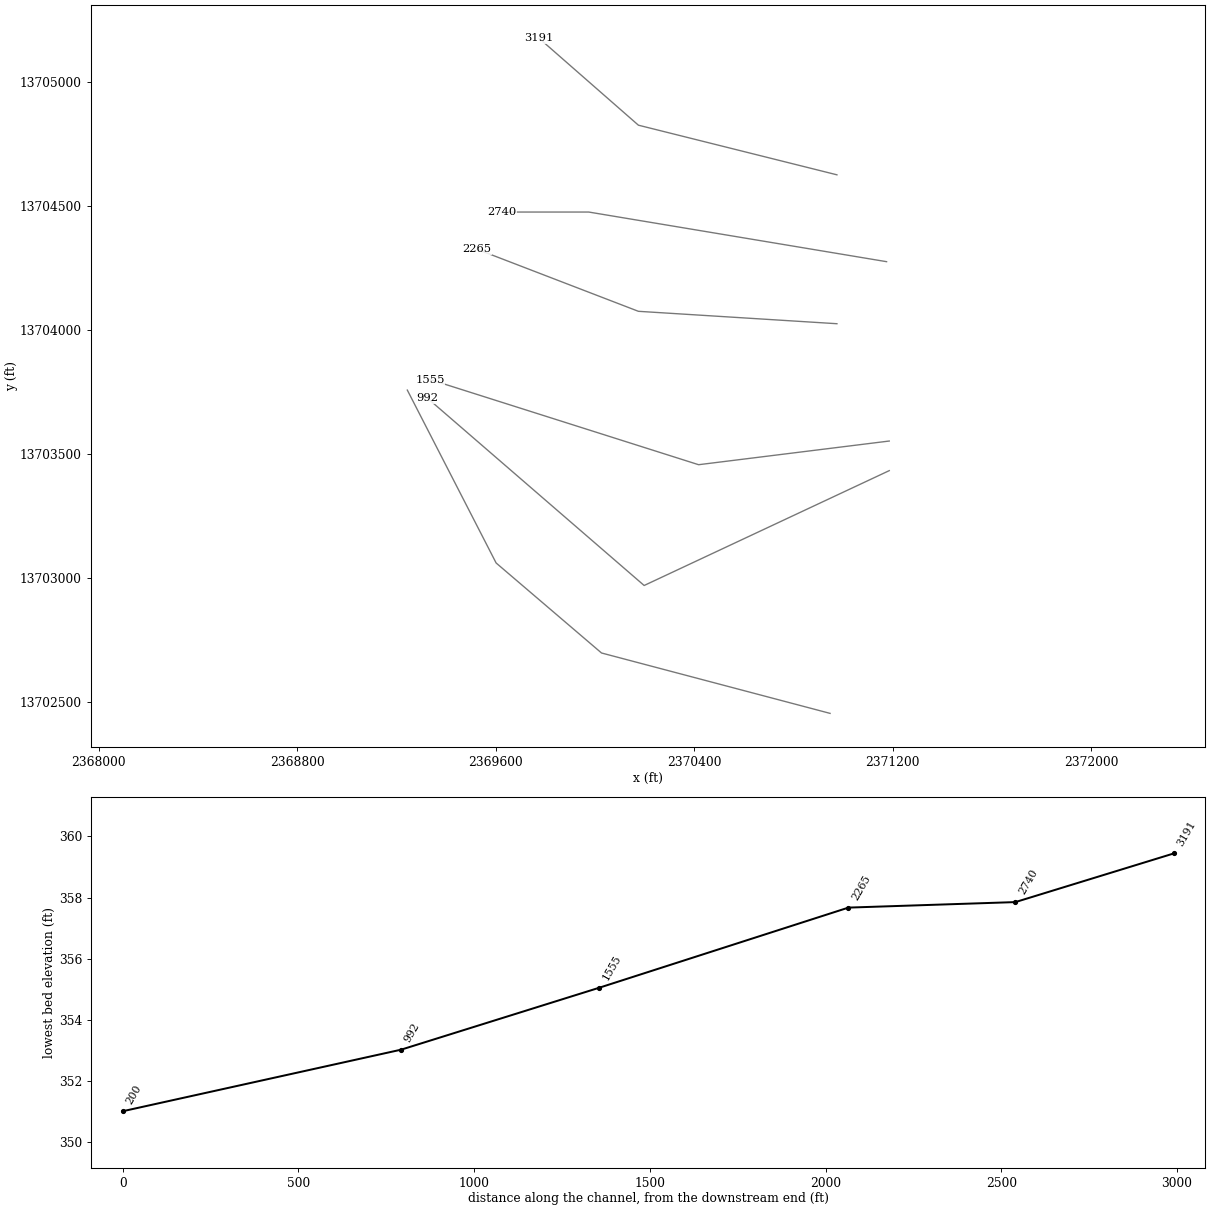
HEC-RAS study Stream0563.prj: Stream0563 Base Level Engineering

--- Stream0563.g01 (geometry) --- (continued)

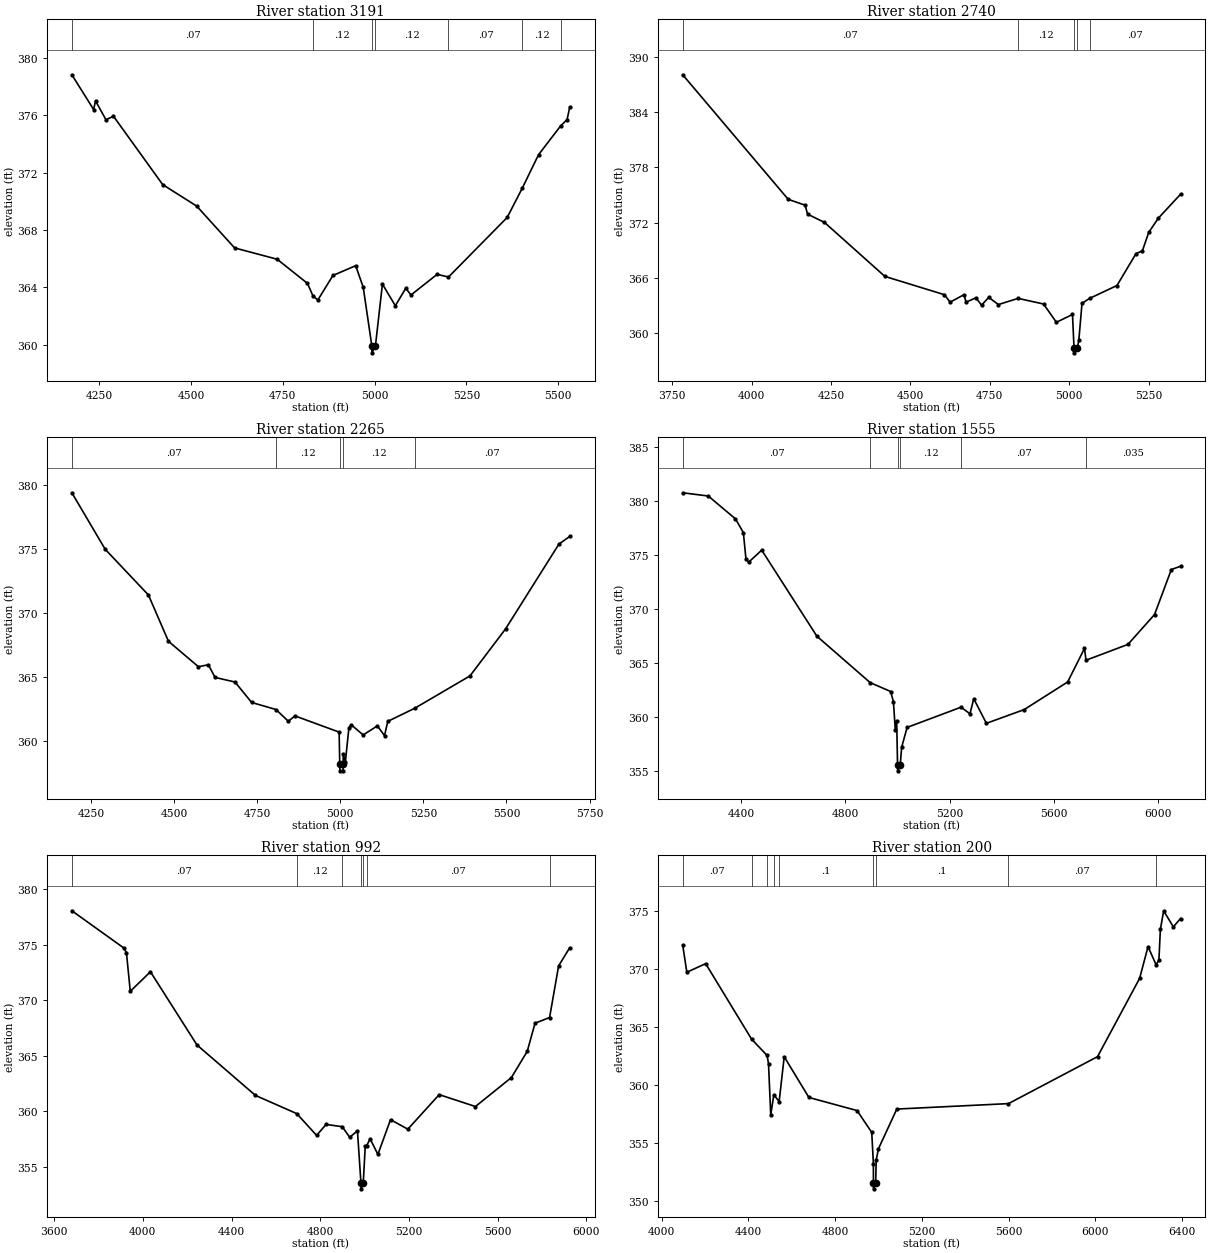
Type RM Length L Ch R = 1 ,3191    ,451,451,451
BEGIN DESCRIPTION:
Stream0563 5.0
END DESCRIPTION:
XS GIS Cut Line= 3
        2370975.       13704625.        2370175.       13704825.
      2369775.02     13705174.98
#Sta/Elev= 30
  4175.4  378.81  4234.7  376.39  4239.8  376.99  4268.2  375.68  4288.8  375.92
  4422.8  371.16  4515.6  369.66  4618.6  366.75  4734.6  365.96  4817.1  364.28
  4832.3   363.4  4845.4  363.12  4886.6  364.83  4948.5  365.51  4969.1  364.01
  4992.4  359.94  4992.9  359.44  5002.4  359.94  5021.4  364.23  5056.5  362.72
    5085  363.94  5099.2  363.47  5170.4  364.91  5201.3  364.72  5361.2  368.87
  5402.7  370.93  5446.6  373.24  5506.6  375.24  5524.4  375.69  5531.5  376.54
#Mann= 7 ,-1 , 0
  4175.4     .07       0  4832.3     .12       0  4992.4     .05       0
  5002.4     .12       0  5201.3     .07       0  5402.7     .12       0
  5506.6     .07       0
Bank Sta=4992.4,5002.4
XS Rating Curve= 0 ,0
Exp/Cntr=0.3,0.1

Type RM Length L Ch R = 1 ,2740    ,475,475,475
BEGIN DESCRIPTION:
Stream0563 4.0
END DESCRIPTION:
XS GIS Cut Line= 3
      2371175.02       13704275.        2369975.       13704475.
      2369624.97       13704475.
#Sta/Elev= 30
  3783.4  388.08  4115.4  374.54  4168.7   373.9  4176.3  372.93  4229.5  372.03
  4419.6  366.16  4607.1  364.17  4624.9  363.36    4668  364.16  4675.6  363.36
    4706  363.84  4723.7  363.03  4746.5  363.88  4776.9   363.1    4839  363.77
  4918.9  363.16  4959.4  361.17    5010  362.02  5014.9  358.35  5015.4  357.85
    5025  358.35    5030  359.23    5040  363.24    5064  363.77    5150  365.17
    5210  368.64    5230  368.94    5250  370.95    5280  372.48    5350  375.09
#Mann= 5 ,-1 , 0
  3783.4     .07       0    4839     .12       0  5014.9     .05       0
    5025     .12       0    5064     .07       0
Bank Sta=5014.9,5025
XS Rating Curve= 0 ,0
Exp/Cntr=0.3,0.1

Type RM Length L Ch R = 1 ,2265    ,710,710,710
BEGIN DESCRIPTION:
Stream0563 3.0
END DESCRIPTION:
XS GIS Cut Line= 3
      2370974.99       13704025.        2370175.       13704075.
      2369524.97     13704325.01
#Sta/Elev= 30
  4192.2  379.43  4292.4  375.01  4422.6  371.43  4482.8  367.81  4572.9  365.82
    4603  365.97    4623  364.98  4683.1  364.62  4733.2  363.02  4806.3  362.47
  4843.5  361.55  4863.5  361.97  4996.4   360.7  4998.3  358.17  4998.8  357.67
    5008  357.67  5008.5  358.17  5008.8  358.96  5015.2  358.38  5025.9  361.06
  5033.4  361.26  5068.7  360.48  5111.6  361.19    5133  360.42  5142.7  361.54
  5224.1  362.57  5390.2   365.1  5497.3  368.78    5658  375.42  5690.2  376.01
#Mann= 5 ,-1 , 0
  4192.2     .07       0  4806.3     .12       0  4998.3     .05       0
  5008.5     .12       0  5224.1     .07       0
Bank Sta=4998.3,5008.5
XS Rating Curve= 0 ,0
Exp/Cntr=0.3,0.1

Type RM Length L Ch R = 1 ,1555    ,563,563,563
BEGIN DESCRIPTION:
Stream0563 2.0
END DESCRIPTION:
XS GIS Cut Line= 3
      2371185.79      13703552.3      2370417.61     13703456.88
      2369335.14     13703800.21
#Sta/Elev= 30
  4175.5  380.74  4273.7  380.44  4377.8  378.33  4408.1  377.07  4418.1  374.64
  4428.2  374.32  4478.6  375.44  4690.2  367.49  4894.7   363.2  4973.3  362.38
  4983.8  361.44    4991  358.86  4996.3  359.69  4999.7  355.55  5000.2  355.05
  5009.9  355.55  5015.3  357.22  5036.3  359.06  5243.2  360.93  5277.5  360.32
    5292  361.71  5340.5  359.44  5485.6  360.71  5652.2  363.26  5716.8  366.36
  5722.7  365.27  5883.4  366.73  5985.5  369.49    6050  373.65  6085.2  373.95
#Mann= 6 ,-1 , 0
  4175.5     .07       0  4894.7     .12       0  4999.7     .05       0
  5009.9     .12       0  5243.2     .07       0  5722.7    .035       0
Bank Sta=4999.7,5009.9
XS Rating Curve= 0 ,0
Exp/Cntr=0.3,0.1

Type RM Length L Ch R = 1 ,992     ,792,792,792
BEGIN DESCRIPTION:
Stream0563 1.0
END DESCRIPTION:
XS GIS Cut Line= 3
      2371185.85     13703433.03      2370198.12     13702970.18
      2369324.97     13703725.02
#Sta/Elev= 30
  3679.8  378.06  3912.7  374.73  3925.9  374.29  3943.2  370.81  4034.1  372.57
    4244  365.98  4507.6  361.44  4694.1   359.8  4783.5  357.84  4826.2  358.83
  4899.2  358.62  4932.6  357.67  4967.7  358.25  4983.5  353.53    4984  353.03
  4993.8  353.53  5002.9  356.89  5009.5  356.93  5024.8  357.53  5059.9  356.13
  5116.9  359.26  5194.8   358.4  5336.3  361.51  5499.7  360.44  5662.1  363.05
  5733.4  365.41  5768.5  367.94  5834.1  368.45  5874.9   373.1  5924.8  374.73
#Mann= 7 ,-1 , 0
  3679.8     .07       0  4694.1     .12       0  4899.2      .1       0
  4983.5     .05       0  4993.8      .1       0  5009.5     .07       0
  5834.1    .035       0
Bank Sta=4983.5,4993.8
XS Rating Curve= 0 ,0
Exp/Cntr=0.3,0.1

Type RM Length L Ch R = 1 ,200     ,0,0,0
BEGIN DESCRIPTION:
XS7074
END DESCRIPTION:
XS GIS Cut Line= 4
      2370947.28     13702454.85      2370026.35      13702698.2
      2369601.68     13703060.84       2369243.8     13703757.52
#Sta/Elev= 30
  4097.7  372.04  4116.7   369.7  4203.5  370.44  4415.1  363.93  4486.7  362.52
  4493.1  361.81  4503.4  357.41  4517.7  359.14  4542.1  358.54  4565.5  362.41
  4679.3   358.9  4901.2  357.77  4968.9  355.89  4976.5  353.17  4976.6  351.52
  4977.1  351.02  4986.9  351.52  4989.6  353.52  4999.9  354.48  5084.4   357.9
  5599.1  358.37  6009.4  362.42  6203.4  369.17  6242.2  371.91  6279.1  370.35
  6292.2  370.73  6299.1  373.41  6314.3     375  6358.7  373.61  6391.9  374.33
#Mann= 9 ,-1 , 0
  4097.7     .07       0  4415.1     .12       0  4486.7      .1       0
  4517.7     .12       0  4542.1      .1       0  4976.6     .05       0
  4986.9      .1       0  5599.1     .07       0  6279.1    .035       0
Bank Sta=4976.6,4986.9
XS Rating Curve= 0 ,0
Exp/Cntr=0.3,0.1

Chan Stop Cuts=-1
Use User Specified Reach Order=0
Composite Channel Slope=5