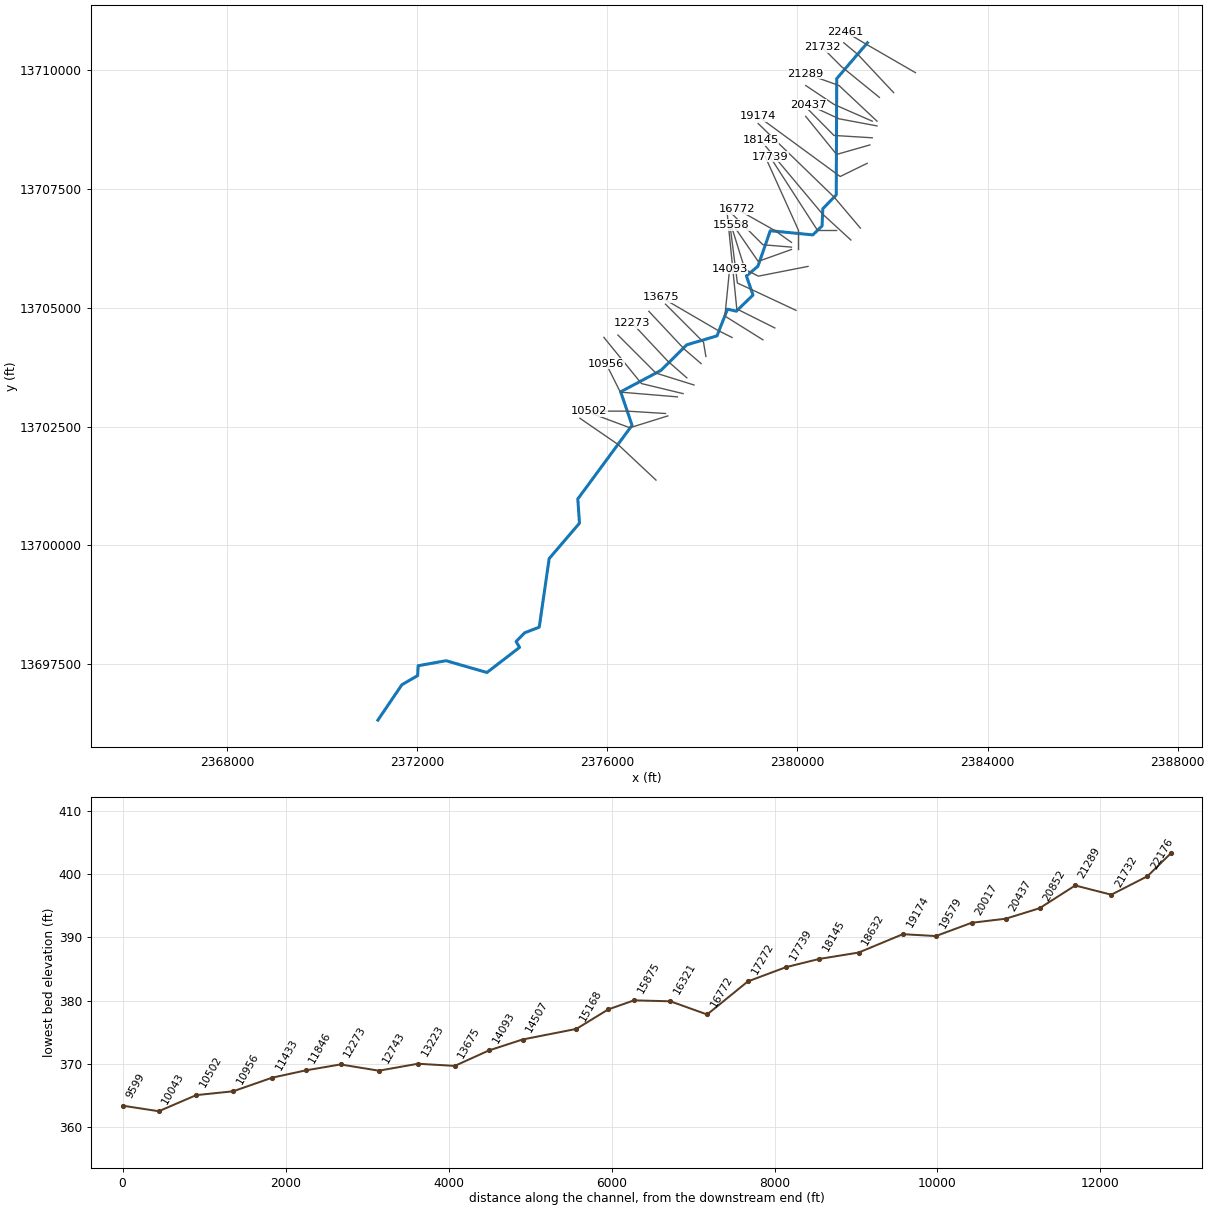
--- Stream0564.prj (project) ---

Proj Title=Stream0564 Base Level Engineering
Current Plan=p01
Default Exp/Contr=0.3,0.1
English Units
Geom File=g01
Flow File=f01
Plan File=p01
Y Axis Title=Elevation
X Axis Title(PF)=Main Channel Distance
X Axis Title(XS)=Station
BEGIN DESCRIPTION:
Stream0564
END DESCRIPTION:
DSS Export Rating Curves= 0
DSS Export Rating Curve Sorted= 0
DSS Export Volume Flow Curves= 0
DXF OffsetX= 0
DXF OffsetY= 0
DXF ScaleX= 1
DXF ScaleY= 10

--- Stream0564.p01 (plan) ---

Plan Title=Multiple Run
Short Identifier=Multiple
Geom File=g01
Flow File=f01
Subcritical Flow
K Sum by GR= 0
Std Step Tol= 0.01
Critical Tol= 0.01
Num of Std Step Trials= 20
Max Error Tol= 0.3
Flow Tol Ratio= 0.001
Split Flow NTrial= 30
Split Flow Tol= 0.02
Split Flow Ratio= 0.02
Log Output Level= 0
Friction Slope Method= 1
Unsteady Friction Slope Method= 2
Unsteady Bridges Friction Slope Method= 1
Parabolic Critical Depth
Global Vel Dist=  1 , 1 , 1
Global Log Level= 0
CheckData=True
Encroach Param= -1, 0, 0, 0
BEGIN DESCRIPTION:
Multiple Run
END DESCRIPTION:

--- Stream0564.f01 (steady flow) ---

Flow Title=Multiple
Number of Profiles=7
Profile Names=10-year,25-year,50-year,1pct_min,100-year,1pct_plu,500-year
River Rch & RM= Stream0564,Reach-1,22461
     759    1240    1680    1102    2199    4387    3732
River Rch & RM= Stream0564,Reach-1,18632
     967    1597    2178    1437    2867    5720    4923
River Rch & RM= Stream0564,Reach-1,16321
    1186    1978    2715    1800    3592    7166    6236
River Rch & RM= Stream0564,Reach-1,13675
    1455    2446    3374    2247    4484    8946    7854
River Rch & RM= Stream0564,Reach-1,10956
    1648    2777    3838    2559    5105   10186    8962
River Rch & RM= Stream0564,Reach-1,7303
    1759    2962    4091    2724    5436   10846    9522
Boundary for River Rch & Prof#=Stream0564,Reach-1,1
Up Type=0
Dn Type=3
Dn Slope=0.005
Boundary for River Rch & Prof#=Stream0564,Reach-1,2
Up Type=0
Dn Type=3
Dn Slope=0.005
Boundary for River Rch & Prof#=Stream0564,Reach-1,3
Up Type=0
Dn Type=3
Dn Slope=0.005
Boundary for River Rch & Prof#=Stream0564,Reach-1,4
Up Type=0
Dn Type=3
Dn Slope=0.005
Boundary for River Rch & Prof#=Stream0564,Reach-1,5
Up Type=0
Dn Type=3
Dn Slope=0.005
Boundary for River Rch & Prof#=Stream0564,Reach-1,6
Up Type=0
Dn Type=3
Dn Slope=0.005
Boundary for River Rch & Prof#=Stream0564,Reach-1,7
Up Type=0
Dn Type=3
Dn Slope=0.005

--- Stream0564.g01 (geometry) ---

Geom Title=Existing Conditions
Program Version=4.10

River Reach=Stream0564      ,Reach-1
Reach XY= 30
        2381475.       13710575.      2380827.14     13709819.03
      2380817.68      13707374.9      2380534.29     13707081.67
      2380519.48     13706722.57      2380325.09     13706532.29
      2379430.08     13706619.97      2379169.48     13705872.56
      2378927.04     13705669.15      2379066.17       13705268.
      2378716.52     13704927.63      2378530.11     13704970.04
      2378308.56     13704408.21       2377672.3     13704219.64
      2377131.09     13703683.16      2376282.64     13703231.45
      2376522.04     13702527.01      2375380.52     13700977.43
      2375415.85     13700468.27      2374778.54     13699723.53
      2374569.42     13698280.58       2374261.7      13698161.6
      2374082.61     13697978.33      2374155.79       13697855.
      2373469.11     13697326.96      2372609.84     13697574.62
      2372022.26     13697469.66      2372011.48     13697261.59
      2371680.51     13697069.72        2371175.       13696325.

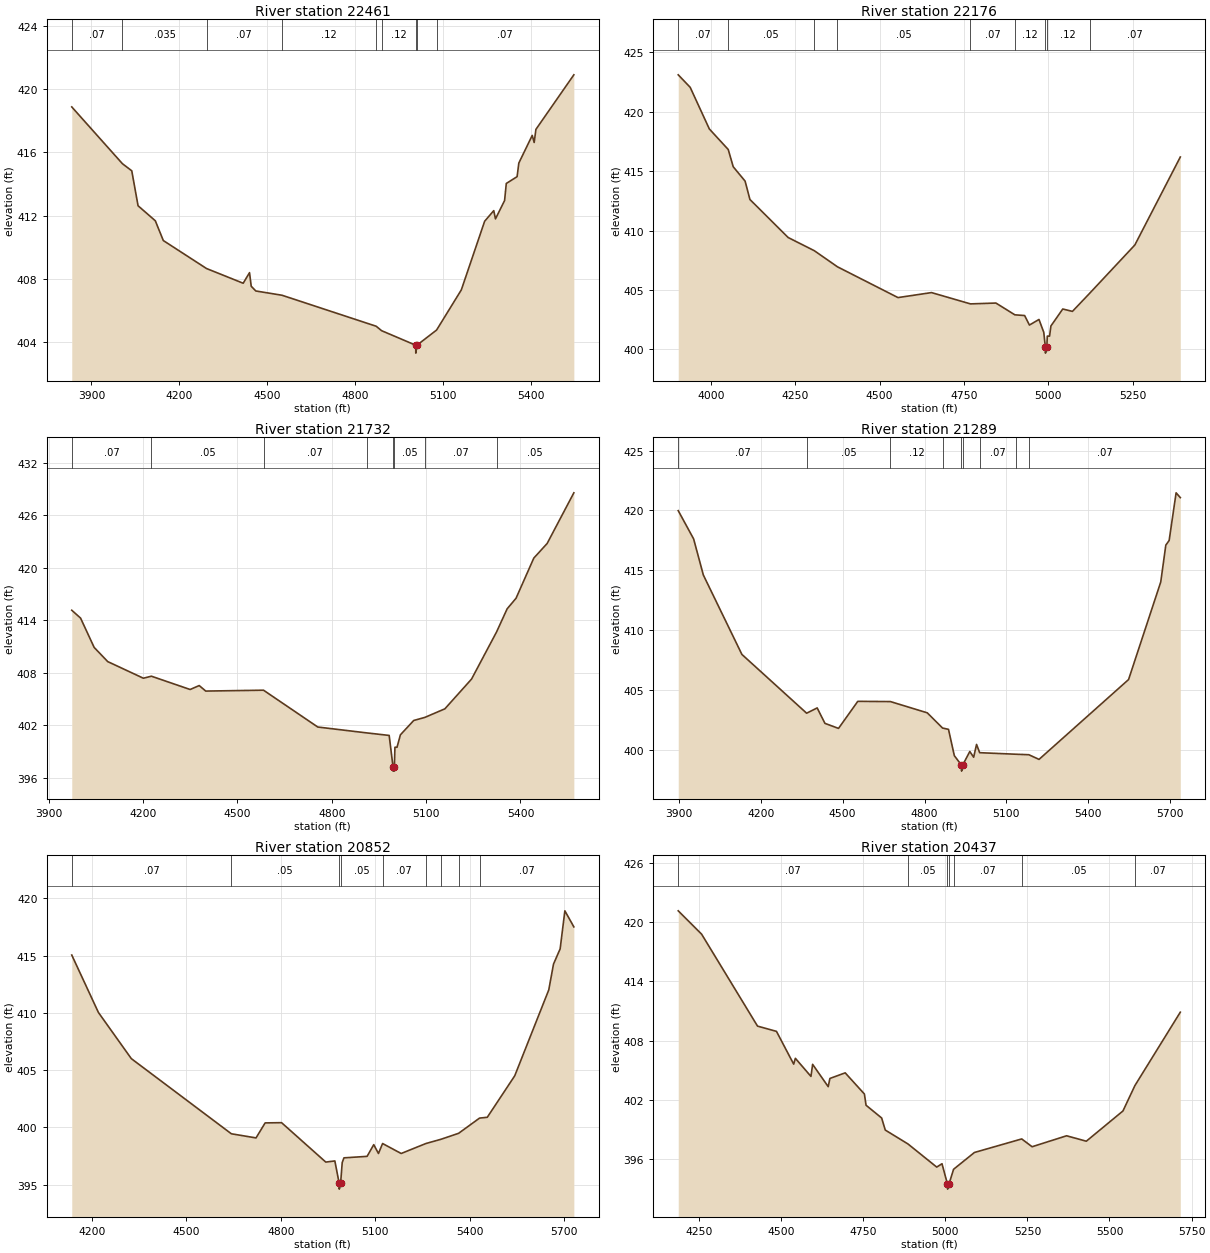
Type RM Length L Ch R = 1 ,22461   ,285,285,285
BEGIN DESCRIPTION:
XS7084
END DESCRIPTION:
XS GIS Cut Line= 3
      2382483.42      13709945.3      2381395.95     13710573.62
      2381003.25     13710809.23
#Sta/Elev= 30
  3832.7  418.87  4005.6  415.28  4037.5  414.83    4059  412.62  4117.9  411.67
  4145.2  410.42  4292.7  408.65  4417.9  407.72  4439.5  408.39  4445.3  407.53
    4461  407.23  4550.5  406.96  4871.9     405  4890.3  404.72  5006.8   403.8
  5007.1   403.3  5010.9   403.8  5078.1  404.76  5162.5   407.3  5242.1  411.64
  5273.2  412.31  5279.1  411.79  5310.2  412.95    5316  414.03  5352.9  414.46
  5358.8  415.32  5404.6  417.07  5411.2  416.62  5417.1  417.45  5546.6   420.9
#Mann= 9 ,-1 , 0
  3832.7     .07       0  4005.6    .035       0  4292.7     .07       0
  4550.5     .12       0  4871.9     .07       0  4890.3     .12       0
  5006.8     .05       0  5010.9     .12       0  5078.1     .07       0
Bank Sta=5006.8,5010.9
XS Rating Curve= 0 ,0
Exp/Cntr=0.3,0.1

Type RM Length L Ch R = 1 ,22176   ,444,444,444
BEGIN DESCRIPTION:
Stream0564 44.0
END DESCRIPTION:
XS GIS Cut Line= 3
      2382025.03     13709524.97        2381275.       13710325.
      2380975.03     13710574.98
#Sta/Elev= 30
  3903.6  423.09    3939  422.04  3995.7  418.54  4051.7  416.81  4066.5  415.36
  4101.7  414.15  4115.9  412.61  4229.2  409.41  4306.8   408.3  4375.1  406.95
  4554.5  404.36  4653.7  404.78  4769.2  403.83  4844.6   403.9  4900.6  402.91
  4929.6  402.85  4943.8  402.05  4972.1  402.52  4986.3  401.44    4991  400.19
  4991.3  399.69  4995.2  400.19  4996.8  401.12  5003.5  401.12  5007.4  401.97
  5042.5   403.4  5071.2   403.2  5122.5  404.73    5256  408.78  5390.7  416.18
#Mann= 9 ,-1 , 0
  3903.6     .07       0  4051.7     .05       0  4306.8     .07       0
  4375.1     .05       0  4769.2     .07       0  4900.6     .12       0
    4991     .05       0  4995.2     .12       0  5122.5     .07       0
Bank Sta=4991,4995.2
XS Rating Curve= 0 ,0
Exp/Cntr=0.3,0.1

Type RM Length L Ch R = 1 ,21732   ,443,443,443
BEGIN DESCRIPTION:
Stream0564 43.0
END DESCRIPTION:
XS GIS Cut Line= 3
      2381725.03     13709424.98        2380925.       13710075.
        2380525.       13710475.
#Sta/Elev= 30
  3973.2  415.15  4001.2  414.25  4044.4   410.9  4087.5  409.28  4200.9  407.38
  4226.4  407.61  4349.6  406.09  4378.4  406.54  4399.2  405.91  4582.9  406.01
  4755.5   401.8  4911.1  401.13  4982.5  400.84  4994.7  397.26    4995  396.76
  4998.7  396.76    4999  397.26  5000.8  399.49  5007.5  399.49  5018.2  400.91
  5060.6  402.55  5095.8   402.9  5159.6  403.88  5244.4  407.28    5324  412.67
  5357.6  415.31  5385.9  416.52  5442.4  421.11  5484.8  422.78  5569.7  428.57
#Mann= 8 ,-1 , 0
  3973.2     .07       0  4226.4     .05       0  4582.9     .07       0
  4911.1     .05       0  4994.7     .05       0    4999     .05       0
  5095.8     .07       0    5324     .05       0
Bank Sta=4994.7,4999
XS Rating Curve= 0 ,0
Exp/Cntr=0.3,0.1

Type RM Length L Ch R = 1 ,21289   ,437,437,437
BEGIN DESCRIPTION:
Stream0564 42.0
END DESCRIPTION:
XS GIS Cut Line= 3
        2381675.       13708925.        2380875.       13709675.
      2380174.99       13709925.
#Sta/Elev= 30
  3897.5  419.98  3953.9  417.62  3989.6   414.6  4130.8  407.97    4368  403.06
  4406.7   403.5  4435.1  402.21  4484.9  401.79  4555.5  404.05  4675.1  404.03
  4810.2  403.09    4866  401.82  4887.9  401.71  4909.3  399.51  4935.5  398.72
  4935.8  398.22  4939.8  398.72    4966  399.86  4980.1  399.38  4990.7  400.45
  5002.2  399.76  5136.2  399.63  5182.3  399.59  5219.7   399.2  5547.8  405.87
  5665.7  414.02  5684.3   417.1  5696.5  417.49    5722  421.47  5737.4  421.07
#Mann= 9 ,-1 , 0
  3897.5     .07       0    4368     .05       0  4675.1     .12       0
    4866     .05       0  4935.5     .05       0  4939.8     .05       0
  5002.2     .07       0  5136.2     .05       0  5182.3     .07       0
Bank Sta=4935.5,4939.8
XS Rating Curve= 0 ,0
Exp/Cntr=0.3,0.1

Type RM Length L Ch R = 1 ,20852   ,415,415,415
BEGIN DESCRIPTION:
Stream0564 41.0
END DESCRIPTION:
XS GIS Cut Line= 3
      2381575.02     13708924.99        2380775.       13709275.
      2380175.03     13709674.98
#Sta/Elev= 30
    4136  415.05  4220.6  410.04  4325.1  406.01  4642.8  399.45  4721.1  399.09
    4750   400.4  4802.2  400.42  4942.6  396.98  4971.4  397.08  4985.2  395.12
  4985.5  394.62  4989.6  395.12  4994.8  396.94  5000.3  397.35  5073.8  397.48
  5094.9   398.5  5109.9  397.73    5123   398.6    5182  397.73  5260.5   398.6
  5308.3  398.97  5364.3  399.49  5430.9  400.82  5455.4  400.89  5542.6  404.51
  5650.7  412.01  5665.7  414.26  5686.8  415.59  5701.8  418.91  5730.3  417.51
#Mann= 9 ,-1 , 0
    4136     .07       0  4642.8     .05       0  4985.2     .05       0
  4989.6     .05       0    5123     .07       0  5260.5     .05       0
  5308.3     .07       0  5364.3     .05       0  5430.9     .07       0
Bank Sta=4985.2,4989.6
XS Rating Curve= 0 ,0
Exp/Cntr=0.3,0.1

Type RM Length L Ch R = 1 ,20437   ,420,420,420
BEGIN DESCRIPTION:
Stream0564 40.0
END DESCRIPTION:
XS GIS Cut Line= 3
      2381674.97       13708825.        2380875.       13708975.
      2380225.01       13709275.
#Sta/Elev= 30
    4186  421.13  4257.2  418.77  4427.6  409.46  4485.3  408.93  4537.8  405.61
  4542.9   406.2  4590.4  404.37  4595.5  405.59    4643  403.33  4648.1  404.16
  4694.7  404.73  4753.2  402.59  4758.3  401.45  4805.8  400.16  4816.8  398.94
  4886.1  397.53  4973.6  395.19  4989.7  395.53  5006.4  393.46  5006.7  392.96
  5010.8  393.46    5025  394.97  5088.5  396.67  5232.6  398.04  5264.2  397.25
  5369.3  398.36  5429.4  397.81    5541  400.87  5577.6  403.45  5715.8  410.87
#Mann= 7 ,-1 , 0
    4186     .07       0  4886.1     .05       0  5006.4     .05       0
  5010.8     .05       0    5025     .07       0  5232.6     .05       0
  5577.6     .07       0
Bank Sta=5006.4,5010.8
XS Rating Curve= 0 ,0
Exp/Cntr=0.3,0.1

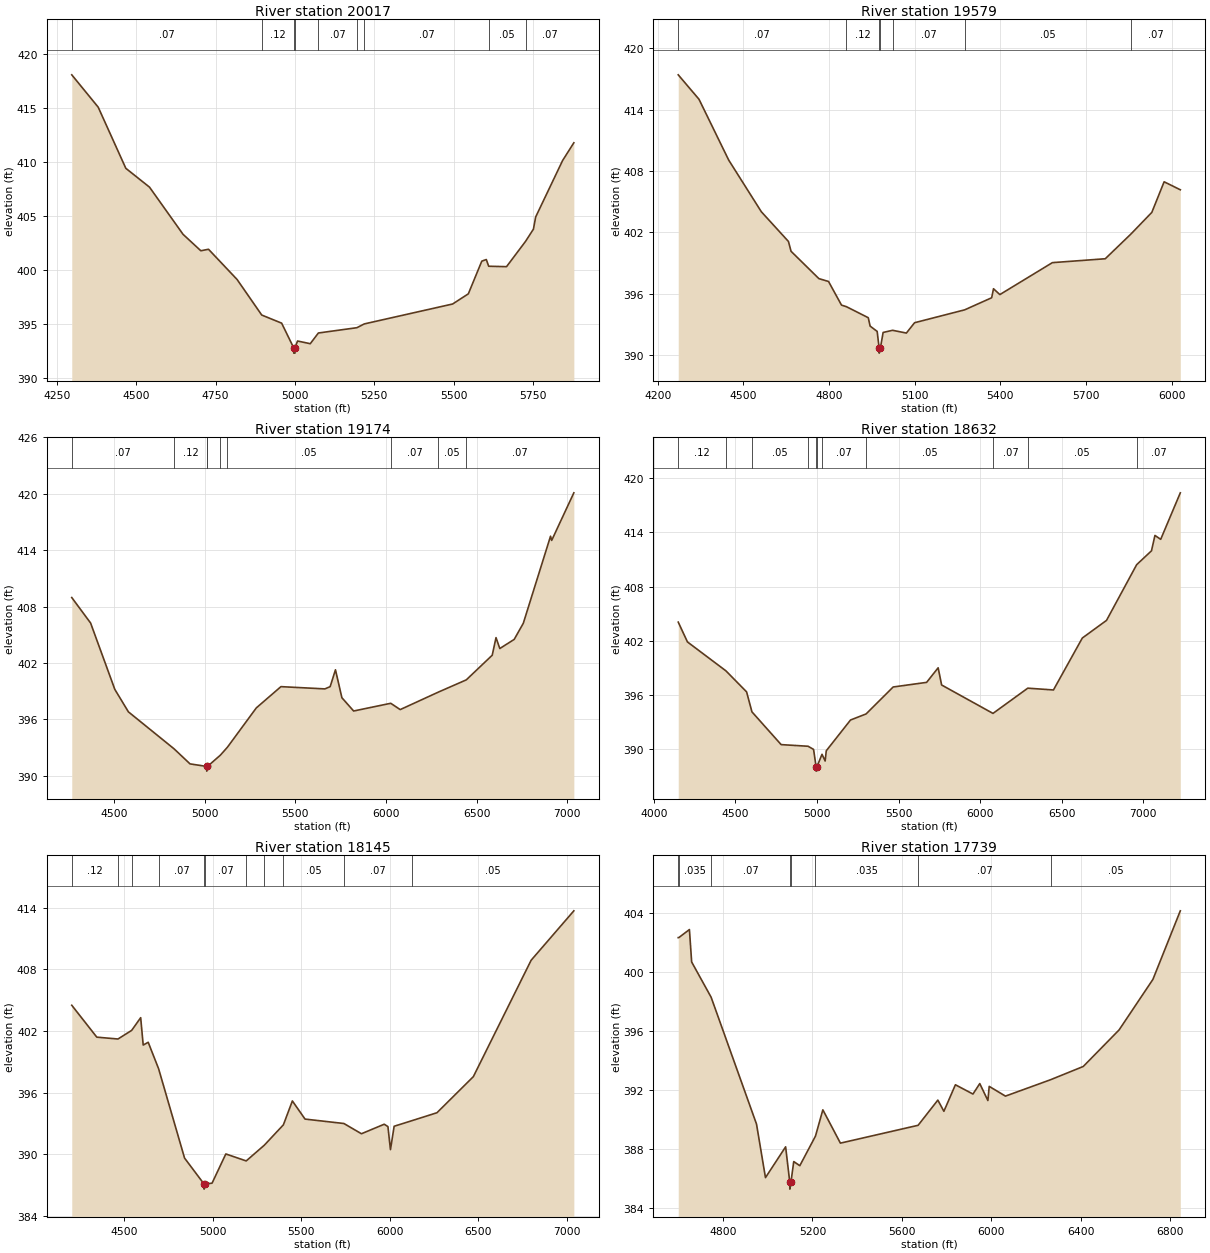
Type RM Length L Ch R = 1 ,20017   ,438,438,438
BEGIN DESCRIPTION:
Stream0564 39.0
END DESCRIPTION:
XS GIS Cut Line= 3
      2381574.98       13708575.      2380767.63     13708624.63
      2380224.97     13709175.03
#Sta/Elev= 30
    4297  418.03  4380.3  415.04  4467.3  409.39  4541.9  407.65  4647.6  403.29
  4703.6  401.77  4727.8  401.91    4818  399.11  4895.5  395.83  4958.2  395.08
    4996  392.81  4996.4  392.31  5000.2  392.31  5000.5  392.81  5008.3  393.43
  5048.4  393.18  5073.9  394.17  5195.3  394.66  5218.7  395.01  5496.9  396.85
  5546.4  397.79  5588.8  400.81    5603  400.96  5610.5  400.34  5666.7   400.3
  5726.7  402.64  5751.5  403.77  5758.5  404.89  5843.4  410.11  5878.8  411.75
#Mann= 9 ,-1 , 0
    4297     .07       0  4895.5     .12       0    4996     .05       0
  5000.5     .12       0  5073.9     .07       0  5195.3     .05       0
  5218.7     .07       0  5610.5     .05       0  5726.7     .07       0
Bank Sta=4996,5000.5
XS Rating Curve= 0 ,0
Exp/Cntr=0.3,0.1

Type RM Length L Ch R = 1 ,19579   ,405,405,405
BEGIN DESCRIPTION:
Stream0564 38.0
END DESCRIPTION:
XS GIS Cut Line= 3
      2381525.04     13708425.01        2380825.       13708225.
      2380175.02     13709024.98
#Sta/Elev= 30
  4271.8   417.4  4344.6  415.01  4448.6  409.07    4563  404.02  4657.9  401.12
    4667  400.16  4764.5  397.49  4798.3  397.21  4843.8   394.9  4860.8  394.75
  4937.5  393.67    4944  392.85  4968.7  392.33  4975.5  390.71  4975.8  390.21
    4980  390.71  4989.5  392.23  5022.7  392.44    5071  392.17  5099.7  393.18
  5275.4  394.44  5369.8  395.62  5376.2   396.5  5398.5  395.93  5582.4  399.05
  5767.7  399.43  5857.4  401.84  5930.8  403.96  5973.9  406.95  6030.6  406.17
#Mann= 7 ,-1 , 0
  4271.8     .07       0  4860.8     .12       0  4975.5     .05       0
    4980     .12       0  5022.7     .07       0  5275.4     .05       0
  5857.4     .07       0
Bank Sta=4975.5,4980
XS Rating Curve= 0 ,0
Exp/Cntr=0.3,0.1

Type RM Length L Ch R = 1 ,19174   ,542,542,542
BEGIN DESCRIPTION:
Stream0564 37.0
END DESCRIPTION:
XS GIS Cut Line= 3
      2381468.42      13708038.6      2380900.54      13707760.7
      2379174.98     13709025.02
#Sta/Elev= 30
  4265.7  408.96  4369.7  406.25  4503.3   399.2  4578.3  396.81  4830.4  392.88
  4918.5  391.28  5010.4  391.01  5010.7  390.51  5014.9  391.01  5086.1  392.21
  5124.9  393.05  5284.4  397.23  5420.3  399.49  5662.7  399.25    5692  399.49
  5721.3  401.28  5756.8  398.31  5821.6   396.9  6026.4  397.72  6078.7  397.05
  6287.1  398.89  6443.4  400.21  6586.6  402.83  6607.5   404.7  6628.4  403.54
  6707.8  404.51    6758  406.22  6908.5  415.48  6914.7  415.03  7037.1  420.09
#Mann= 9 ,-1 , 0
  4265.7     .07       0  4830.4     .12       0  5010.4     .05       0
  5014.9     .12       0  5086.1     .07       0  5124.9     .05       0
  6026.4     .07       0  6287.1     .05       0  6443.4     .07       0
Bank Sta=5010.4,5014.9
XS Rating Curve= 0 ,0
Exp/Cntr=0.3,0.1

Type RM Length L Ch R = 1 ,18632   ,487,487,487
BEGIN DESCRIPTION:
Stream0564 36.0
END DESCRIPTION:
XS GIS Cut Line= 3
      2381324.99     13706675.02        2380775.       13707325.
      2379175.01     13708874.99
#Sta/Elev= 30
  4148.9  404.07  4205.4  401.88  4441.6  398.68  4568.1  396.36    4601  394.15
    4780  390.53  4945.2  390.35  4978.9     390  4994.3   388.1  4994.7   387.6
  4999.9   388.1  5030.7  389.46  5049.9  388.72  5056.8  389.85  5205.5  393.25
  5300.9  393.92  5467.1   396.9  5672.1  397.41  5742.9  399.02  5764.2  397.12
  6079.2  393.98  6292.7  396.77    6450  396.57    6627  402.31  6775.4  404.26
  6960.4  410.42  7051.2  411.95  7072.5  413.65  7107.8  413.22    7228  418.36
#Mann= 11 ,-1 , 0
  4148.9     .12       0  4441.6    .035       0    4601     .05       0
  4945.2     .12       0  4994.3     .05       0  4999.9     .12       0
  5030.7     .07       0  5300.9     .05       0  6079.2     .07       0
  6292.7     .05       0  6960.4     .07       0
Bank Sta=4994.3,4999.9
XS Rating Curve= 0 ,0
Exp/Cntr=0.3,0.1

Type RM Length L Ch R = 1 ,18145   ,406,406,406
BEGIN DESCRIPTION:
Stream0564 35.0
END DESCRIPTION:
XS GIS Cut Line= 3
        2381125.       13706425.        2380525.       13706975.
      2379225.02     13708524.97
#Sta/Elev= 30
  4204.5  404.51    4346   401.4  4465.6  401.22  4542.9  402.06  4593.9   403.3
  4608.1  400.63  4636.4   400.9  4695.2  398.32  4841.8  389.61  4951.8  387.08
  4952.2  386.58  4957.5  387.08  4997.2  387.16    5075  390.01  5190.1  389.33
  5292.2  390.86  5400.2  392.85    5451  395.18  5522.6  393.41    5742  392.98
  5841.3  391.98  5970.1  392.91  5990.9  392.68  6005.2  390.43    6026  392.71
  6129.1  393.27    6268  394.03  6473.6  397.55  6800.1   408.9  7041.4  413.72
#Mann= 11 ,-1 , 0
  4204.5     .12       0  4465.6     .07       0  4542.9    .035       0
  4695.2     .07       0  4951.8     .05       0  4957.5     .07       0
  5190.1     .05       0  5292.2    .035       0  5400.2     .05       0
    5742     .07       0  6129.1     .05       0
Bank Sta=4951.8,4957.5
XS Rating Curve= 0 ,0
Exp/Cntr=0.3,0.1

Type RM Length L Ch R = 1 ,17739   ,467,467,467
BEGIN DESCRIPTION:
Stream0564 34.0
END DESCRIPTION:
XS GIS Cut Line= 3
      2380824.96       13706625.        2380425.       13706625.
      2379425.03     13708174.96
#Sta/Elev= 30
  4600.1  402.34  4602.4  402.34  4650.1  402.89  4660.1  400.69  4747.1   398.3
  4950.1  389.69  4990.1  386.06  5080.2  388.15  5098.5  385.78    5099  385.28
  5104.2  385.78  5116.5  387.15  5143.6  386.87  5213.7  388.88  5246.6  390.66
  5325.1   388.4  5672.5  389.61  5760.7  391.32  5787.7  390.56  5839.2  392.36
  5917.7  391.73  5948.1  392.44  5984.4  391.29  5990.3  392.25  6062.9  391.59
  6264.3   392.7  6410.7   393.6  6570.9  396.08  6722.2  399.51  6844.6  404.16
#Mann= 8 ,-1 , 0
  4600.1     .07       0  4602.4    .035       0  4747.1     .07       0
  5098.5     .05       0  5104.2     .07       0  5213.7    .035       0
  5672.5     .07       0  6264.3     .05       0
Bank Sta=5098.5,5104.2
XS Rating Curve= 0 ,0
Exp/Cntr=0.3,0.1

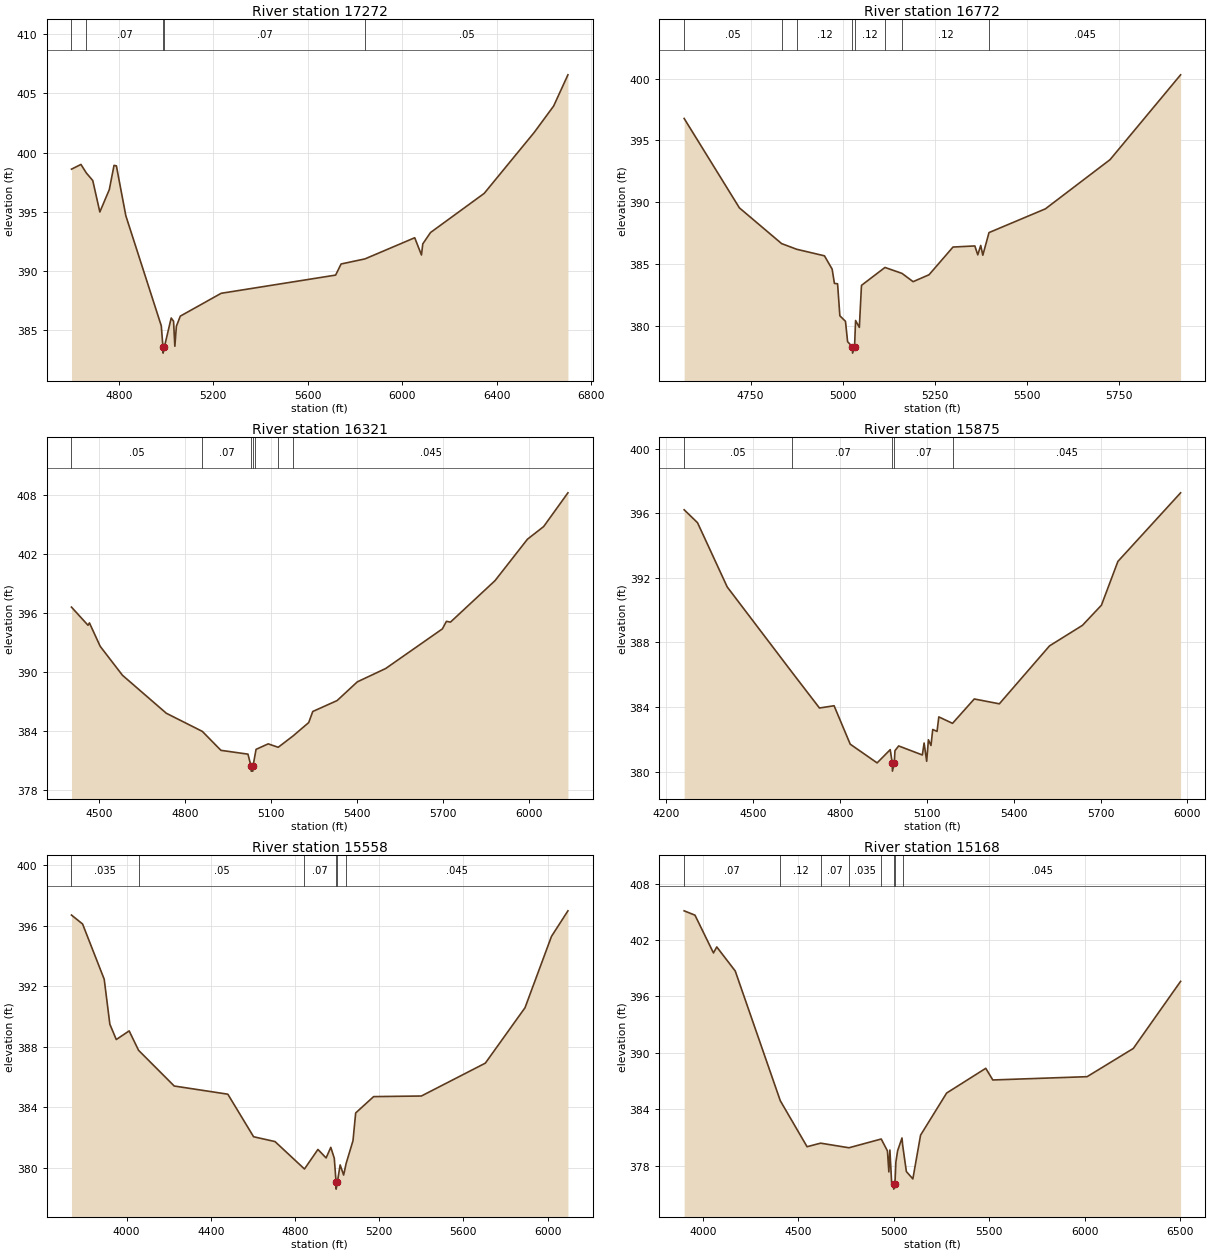
Type RM Length L Ch R = 1 ,17272   ,500,500,500
BEGIN DESCRIPTION:
Stream0564 33.0
END DESCRIPTION:
XS GIS Cut Line= 3
        2380025.     13706225.02        2380025.       13706625.
      2379325.01     13708174.98
#Sta/Elev= 30
    4600  398.59    4640  398.99  4662.8  398.27    4690  397.63    4720  394.97
    4760  396.86    4780  398.91    4790  398.87    4830  394.65    4980  385.34
  4987.1  383.53  4987.6  383.03  4992.8  383.53  5021.9     386  5031.9  385.73
  5037.4  383.61  5043.9  385.31  5060.5  386.16  5233.3  388.09  5717.7  389.63
  5740.8  390.57  5841.8     391  6052.4  392.79    6081  391.33  6086.5  392.27
  6119.2  393.23  6346.3  396.54  6558.1   401.7  6640.2  403.93  6700.7  406.57
#Mann= 5 ,-1 , 0
    4600     .05       0  4662.8     .07       0  4987.1     .05       0
  4992.8     .07       0  5841.8     .05       0
Bank Sta=4987.1,4992.8
XS Rating Curve= 0 ,0
Exp/Cntr=0.3,0.1

Type RM Length L Ch R = 1 ,16772   ,451,451,451
BEGIN DESCRIPTION:
Stream0564 32.0
END DESCRIPTION:
XS GIS Cut Line= 3
      2379875.02     13706374.99        2379525.       13706625.
      2378725.02     13707074.99
#Sta/Elev= 30
  4569.6  396.77  4719.6  389.54  4834.2  386.65  4875.3  386.19  4950.6  385.66
  4971.5  384.58  4977.6  383.43  4986.2   383.4  4992.4  380.81  5007.7  380.36
  5013.4  378.72  5026.5  378.29    5027  377.79  5032.3  378.29  5035.1  380.43
  5045.3  379.87  5051.1  383.27  5114.9  384.72  5161.1  384.24  5191.3  383.57
  5234.6  384.13  5299.6  386.37  5358.9  386.46  5366.9  385.74  5374.9   386.5
  5380.6  385.71  5397.4  387.54  5550.5  389.46  5726.1  393.44  5917.6   400.3
#Mann= 8 ,-1 , 0
  4569.6     .05       0  4834.2     .07       0  4875.3     .12       0
  5026.5     .05       0  5032.3     .12       0  5114.9     .07       0
  5161.1     .12       0  5397.4    .045       0
Bank Sta=5026.5,5032.3
XS Rating Curve= 0 ,0
Exp/Cntr=0.3,0.1

Type RM Length L Ch R = 1 ,16321   ,446,446,446
BEGIN DESCRIPTION:
Stream0564 31.0
END DESCRIPTION:
XS GIS Cut Line= 3
      2379874.98       13706275.        2379275.       13706325.
      2378475.02     13707124.98
#Sta/Elev= 30
  4402.6   396.6  4460.3  394.75  4465.3  394.99  4502.9   392.6  4580.7  389.65
  4733.7  385.78  4859.5  383.93  4924.4     382  5018.8  381.61  5029.6  380.38
  5030.1  379.88  5035.8  379.88  5036.3  380.38  5041.9  381.27  5047.1   382.1
  5089.5  382.66  5124.4  382.31  5177.2  383.49  5230.9  384.83  5245.1  385.96
  5329.9  387.07  5400.6  388.98  5499.6  390.34  5697.6  394.38  5711.8  395.15
  5725.9  395.07  5881.5   399.3  5994.6  403.52  6051.2  404.81    6136  408.25
#Mann= 7 ,-1 , 0
  4402.6     .05       0  4859.5     .07       0  5029.6     .05       0
  5036.3     .07       0  5041.9      .1       0  5124.4     .07       0
  5177.2    .045       0
Bank Sta=5029.6,5036.3
XS Rating Curve= 0 ,0
Exp/Cntr=0.3,0.1

Type RM Length L Ch R = 1 ,15875   ,317,317,317
BEGIN DESCRIPTION:
Stream0564 30.0
END DESCRIPTION:
XS GIS Cut Line= 3
      2379875.02     13706225.01        2379175.       13705975.
      2378625.03     13706774.96
#Sta/Elev= 30
  4262.3  396.22  4308.5  395.42    4411  391.44  4636.2  386.12  4729.5  383.94
    4780  384.08  4835.7   381.7  4928.6  380.54  4973.8  381.36    4981  380.53
  4981.5  380.03  4987.8  380.53  4990.2   381.3    5003  381.59  5084.8  381.03
  5090.8  381.77  5099.7  380.64  5105.7  381.97  5114.6  381.62  5120.6  382.61
  5135.5  382.49  5141.6  383.39  5188.9  382.99    5264   384.5  5350.6   384.2
  5523.9  387.79  5637.5  389.06  5703.1  390.31  5759.9  393.02  5976.4  397.27
#Mann= 5 ,-1 , 0
  4262.3     .05       0  4636.2     .07       0    4981     .05       0
  4987.8     .07       0  5188.9    .045       0
Bank Sta=4981,4987.8
XS Rating Curve= 0 ,0
Exp/Cntr=0.3,0.1

Type RM Length L Ch R = 1 ,15558   ,390,390,390
BEGIN DESCRIPTION:
XS7083
END DESCRIPTION:
XS GIS Cut Line= 4
       2380223.9     13705869.72      2379178.72     13705664.31
      2378894.77      13705809.3      2378604.79     13706739.66
#Sta/Elev= 30
    3738  396.69  3790.7   396.1  3893.5  392.45  3920.3  389.48  3950.9  388.47
    4012  389.04  4056.6  387.76  4226.1   385.4  4480.8  384.86  4603.1  382.05
    4705  381.73  4844.9  379.92  4908.8  381.21  4947.7  380.65  4969.9  381.35
  4986.5  380.63  4994.8  379.09  4995.3  378.59  5001.6  379.09  5014.3  380.19
  5030.9  379.52  5042.7  380.28  5075.4  381.79  5088.1  383.62  5173.4   384.7
  5400.3  384.74  5704.1  386.91  5892.6  390.57  6018.3  395.28  6096.5  396.97
#Mann= 6 ,-1 , 0
    3738    .035       0  4056.6     .05       0  4844.9     .07       0
  4994.8     .05       0  5001.6     .07       0  5042.7    .045       0
Bank Sta=4994.8,5001.6
XS Rating Curve= 0 ,0
Exp/Cntr=0.3,0.1

Type RM Length L Ch R = 1 ,15168   ,661,661,661
BEGIN DESCRIPTION:
XS7082
END DESCRIPTION:
XS GIS Cut Line= 4
      2379970.12     13704945.39      2379118.31     13705344.11
      2378737.69     13705519.31      2378580.72     13706750.93
#Sta/Elev= 30
  3901.5  405.11  3958.2  404.65  4055.1  400.63  4072.4  401.27  4169.2  398.71
  4405.3  384.91  4545.6  380.02  4616.6   380.4    4765  379.91  4934.1  380.84
  4966.7  379.57    4974  377.34  4979.5  379.67  4988.8  376.13    4999  376.01
  4999.5  375.51  5005.8  376.01  5010.8  378.38  5019.9  379.59  5042.9  380.95
  5046.6  380.15  5065.8  377.38  5099.8   376.6  5140.2  381.25  5276.8  385.73
  5481.8  388.36  5518.8  387.12  6012.7  387.47  6254.7  390.47  6502.6  397.61
#Mann= 8 ,-1 , 0
  3901.5     .07       0  4405.3     .12       0  4616.6     .07       0
    4765    .035       0  4934.1     .07       0    4999     .05       0
  5005.8     .07       0  5046.6    .045       0
Bank Sta=4999,5005.8
XS Rating Curve= 0 ,0
Exp/Cntr=0.3,0.1

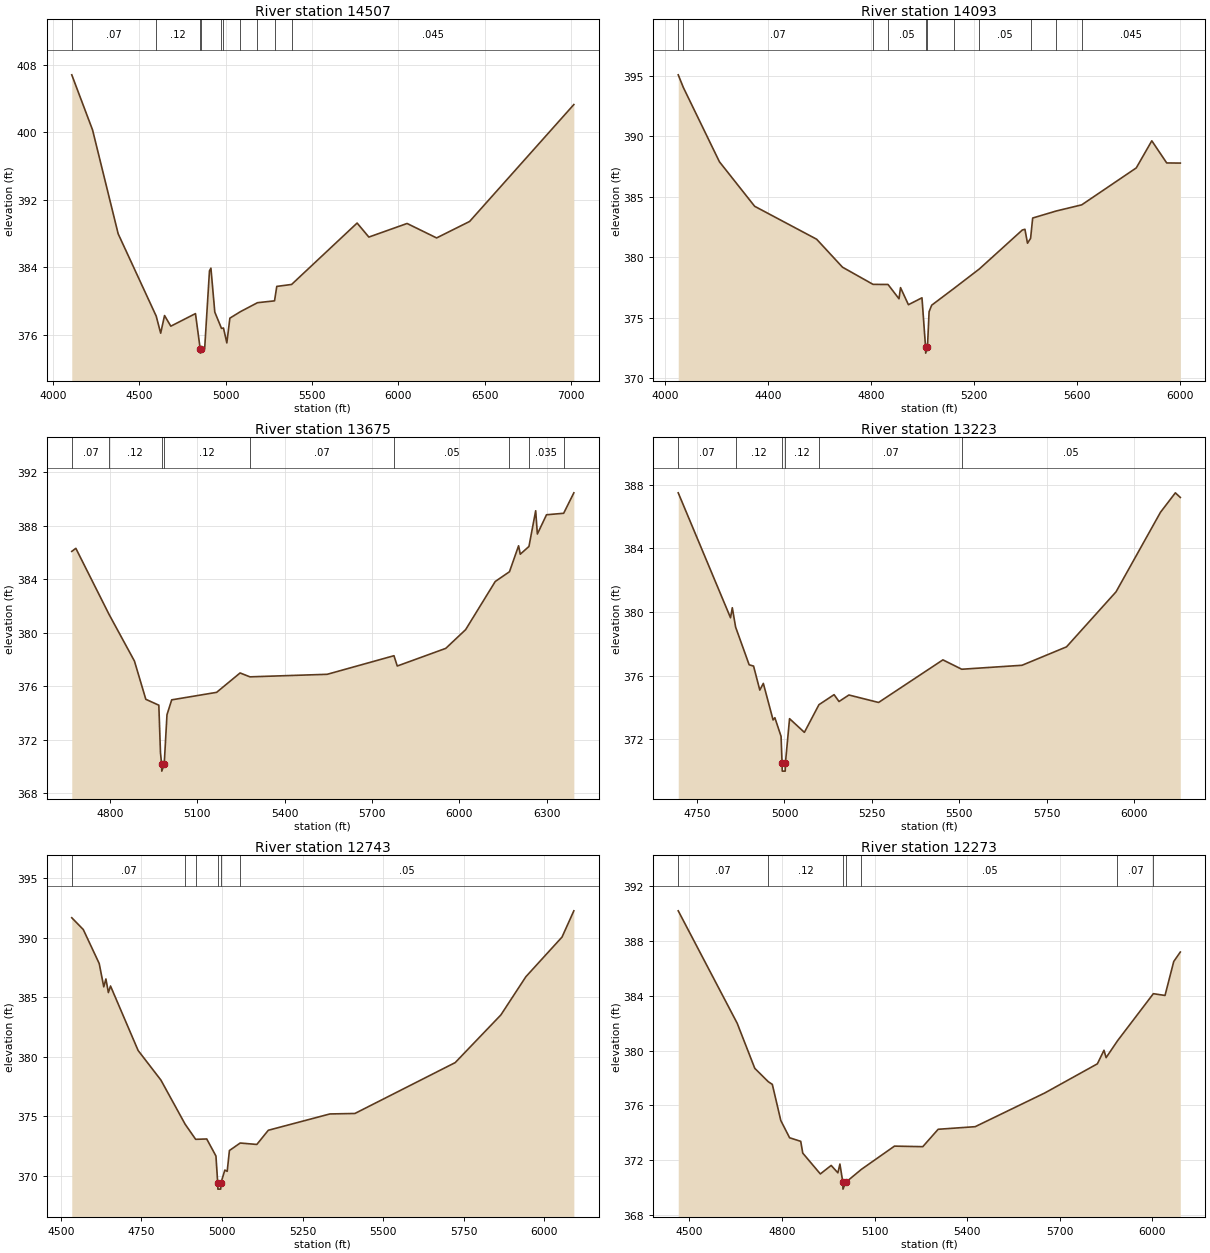
Type RM Length L Ch R = 1 ,14507   ,414,414,414
BEGIN DESCRIPTION:
Stream0564 29.0
END DESCRIPTION:
XS GIS Cut Line= 3
      2379525.04     13704574.98        2378725.       13704975.
        2378525.     13706974.96
#Sta/Elev= 30
  4110.2  406.78  4230.4  400.26  4378.6  387.96  4598.7  378.21  4624.5  376.19
  4646.9  378.28  4683.2  377.02  4825.8  378.51  4853.1  374.33  4853.6  373.83
    4860  374.33  4878.9  374.35  4906.8  383.57  4915.2  383.89  4937.6  378.69
  4976.3  376.76  4987.9   376.8  5007.2  375.04  5024.8  377.97  5085.9  378.74
  5184.5   379.8  5283.2  380.02  5296.1  381.73  5381.9  381.96  5760.9  389.23
  5828.8  387.57  6049.9  389.18  6220.7  387.47  6411.7  389.42  7014.6  403.26
#Mann= 10 ,-1 , 0
  4110.2     .07       0  4598.7     .12       0  4853.1     .05       0
    4860     .12       0  4976.3     .05       0  4987.9     .12       0
  5085.9     .07       0  5184.5     .05       0  5283.2    .035       0
  5381.9    .045       0
Bank Sta=4853.1,4860
XS Rating Curve= 0 ,0
Exp/Cntr=0.3,0.1

Type RM Length L Ch R = 1 ,14093   ,418,418,418
BEGIN DESCRIPTION:
Stream0564 28.0
END DESCRIPTION:
XS GIS Cut Line= 3
      2379274.99     13704325.01        2378475.       13704825.
        2378575.     13705825.02
#Sta/Elev= 30
  4051.8  395.08  4071.5  394.04  4211.6   387.9  4348.4  384.22  4588.9   381.5
  4689.2  379.19  4807.8  377.77    4866  377.76  4908.5  376.58  4914.4   377.5
  4945.1  376.09  4997.7  376.66  5011.6  372.59  5012.1  372.09    5019  372.59
  5025.3  375.51  5035.4  376.05  5121.5  377.43  5220.7  379.05  5387.1  382.26
  5397.2  382.32  5407.2  381.17  5419.2  381.57  5427.3  383.25  5518.5  383.83
  5617.7  384.34  5829.3  387.39  5889.6  389.63  5947.4   387.8  6000.2  387.79
#Mann= 11 ,-1 , 0
  4051.8     .12       0  4071.5     .07       0  4807.8     .12       0
    4866     .05       0  5011.6     .05       0    5019     .05       0
  5121.5     .07       0  5220.7     .05       0  5419.2    .045       0
  5518.5    .035       0  5617.7    .045       0
Bank Sta=5011.6,5019
XS Rating Curve= 0 ,0
Exp/Cntr=0.3,0.1

Type RM Length L Ch R = 1 ,13675   ,452,452,452
BEGIN DESCRIPTION:
Stream0564 27.0
END DESCRIPTION:
XS GIS Cut Line= 3
      2378625.04     13704374.98        2378325.       13704525.
        2377125.       13705225.
#Sta/Elev= 30
  4668.5  386.08  4682.5  386.31  4796.6  381.37  4883.8  377.88  4922.9  375.02
  4967.6  374.58  4973.2  371.04  4977.2  370.15  4977.7  369.65    4986  370.15
  4995.6  373.87  5011.8  374.98    5166  375.54  5246.7  376.99  5280.7   376.7
    5546  376.89  5775.3  378.28  5786.6  377.51  5953.3  378.83  6021.5  380.23
  6123.2  383.83  6172.1  384.56  6203.4   386.5  6209.2  385.87    6239  386.45
  6262.1  389.12  6267.9  387.38  6299.3  388.82  6358.2  388.93  6393.2  390.46
#Mann= 9 ,-1 , 0
  4668.5     .07       0  4796.6     .12       0  4977.2     .05       0
    4986     .12       0  5280.7     .07       0  5775.3     .05       0
  6172.1     .07       0    6239    .035       0  6358.2     .05       0
Bank Sta=4977.2,4986
XS Rating Curve= 0 ,0
Exp/Cntr=0.3,0.1

Type RM Length L Ch R = 1 ,13223   ,480,480,480
BEGIN DESCRIPTION:
Stream0564 26.0
END DESCRIPTION:
XS GIS Cut Line= 3
        2378075.       13703975.        2378025.       13704275.
        2377225.       13705075.
#Sta/Elev= 30
  4696.2   387.5  4845.7  379.64  4850.8  380.27  4860.3  379.05    4899  376.68
  4911.6   376.6  4929.4  375.09  4939.5  375.51  4967.4  373.21  4972.5  373.35
  4990.2  372.18  4993.1  370.49  4993.6  369.99  5002.1  369.99  5002.6  370.49
  5014.5  373.29  5056.9  372.43  5098.5  374.17  5141.8   374.8  5155.9  374.37
  5184.2  374.78    5269  374.31  5452.9  376.99  5506.8   376.4  5679.2  376.65
  5806.4  377.81  5947.9  381.27  6075.1  386.28  6117.6   387.5  6131.7  387.21
#Mann= 6 ,-1 , 0
  4696.2     .07       0  4860.3     .12       0  4993.1     .05       0
  5002.6     .12       0  5098.5     .07       0  5506.8     .05       0
Bank Sta=4993.1,5002.6
XS Rating Curve= 0 ,0
Exp/Cntr=0.3,0.1

Type RM Length L Ch R = 1 ,12743   ,470,470,470
BEGIN DESCRIPTION:
Stream0564 25.0
END DESCRIPTION:
XS GIS Cut Line= 3
        2377975.       13703825.        2377625.       13704125.
      2376874.98     13704925.03
#Sta/Elev= 30
  4534.1  391.67  4569.8  390.68  4619.2  387.83  4633.4  385.87    4640  386.53
  4647.7  385.39  4654.3  385.94  4739.9  380.53  4810.7  378.04  4885.8  374.34
  4918.5  373.07  4952.8   373.1  4981.4  371.67  4986.9  369.39  4987.4  368.89
  4996.1  368.89  4996.6  369.39    5009  370.49  5016.3  370.38  5023.2  372.13
  5056.6  372.76  5108.2  372.64  5143.8  373.83  5334.8   375.2  5412.5  375.24
  5723.6  379.51  5865.3  383.51  5942.9  386.72  6055.1  390.05  6091.7  392.25
#Mann= 6 ,-1 , 0
  4534.1     .07       0  4885.8     .05       0  4918.5     .12       0
  4986.9     .05       0  4996.6     .12       0  5056.6     .05       0
Bank Sta=4986.9,4996.6
XS Rating Curve= 0 ,0
Exp/Cntr=0.3,0.1

Type RM Length L Ch R = 1 ,12273   ,427,427,427
BEGIN DESCRIPTION:
Stream0564 24.0
END DESCRIPTION:
XS GIS Cut Line= 3
      2377674.97     13703525.03        2377275.       13703875.
      2376524.97     13704675.03
#Sta/Elev= 30
  4463.5   390.2  4654.7  381.99  4711.7   378.7  4755.6  377.72  4768.6  377.53
  4796.1  374.89  4824.6  373.63  4860.7  373.37  4867.3  372.51  4924.3  370.99
  4959.4  371.61  4981.2  371.07  4987.8  371.71  4997.2  370.38  4997.7  369.88
  5006.9  370.38  5057.2  371.32  5164.7  373.02  5256.5  372.98  5306.4  374.25
  5426.5  374.44  5652.9  376.91  5822.7  379.03  5844.1  380.02    5851  379.48
  5887.9  380.71  6004.2  384.15    6042  384.02  6070.3   386.5  6091.6  387.19
#Mann= 7 ,-1 , 0
  4463.5     .07       0  4755.6     .12       0  4997.2     .05       0
  5006.9     .12       0  5057.2     .05       0  5887.9     .07       0
  6004.2    .035       0
Bank Sta=4997.2,5006.9
XS Rating Curve= 0 ,0
Exp/Cntr=0.3,0.1

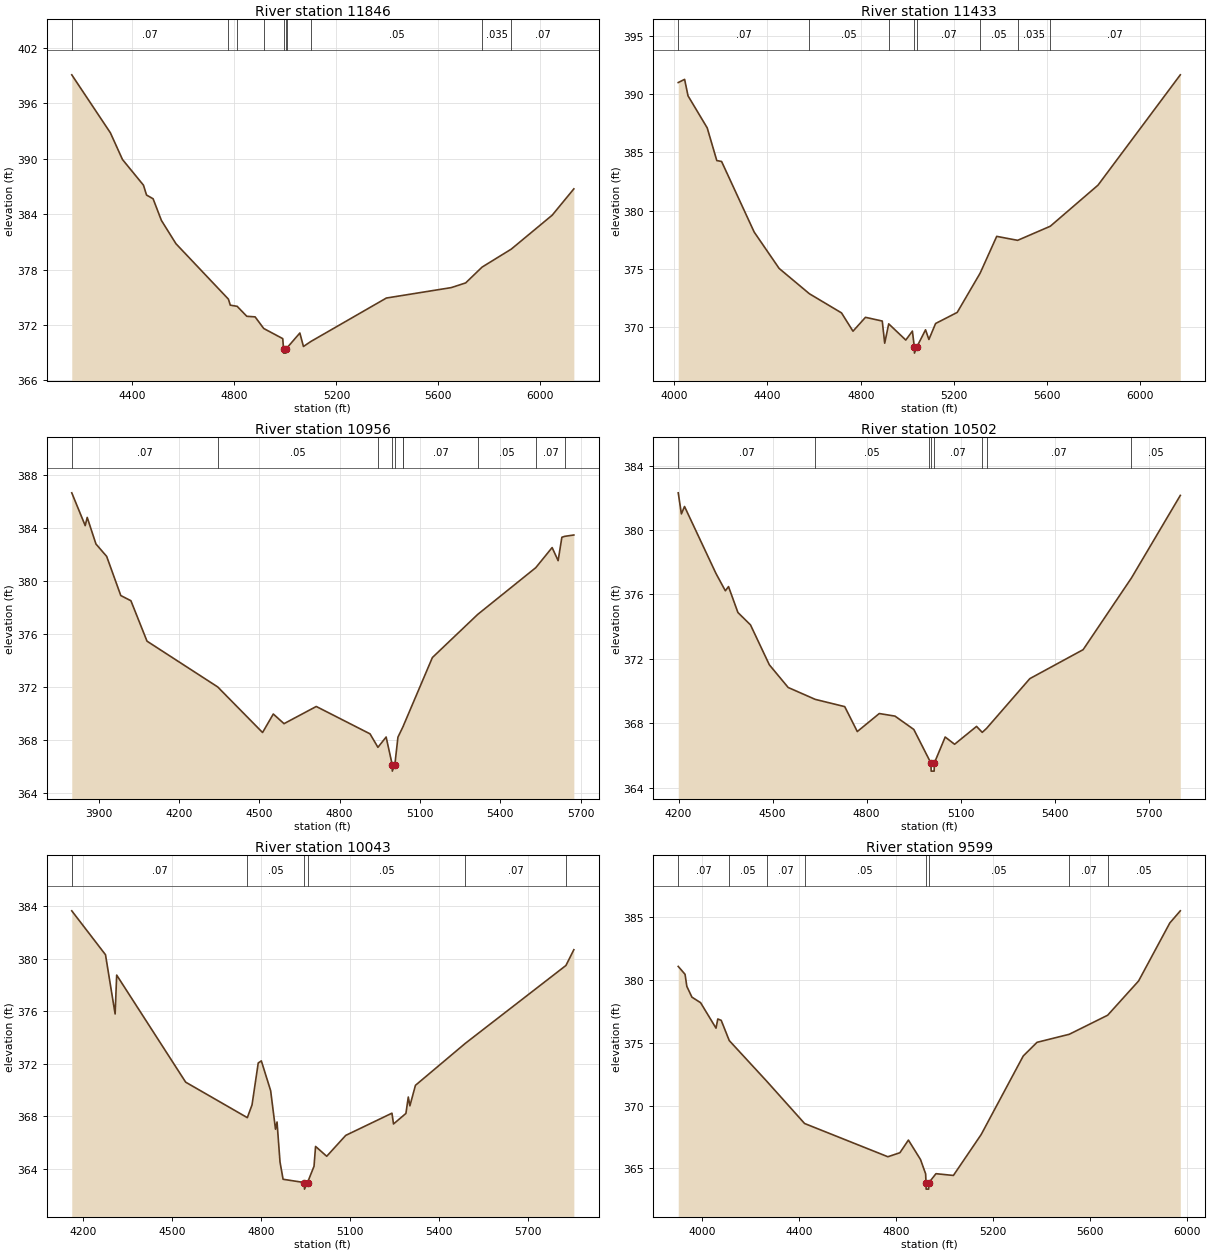
Type RM Length L Ch R = 1 ,11846   ,413,413,413
BEGIN DESCRIPTION:
Stream0564 23.0
END DESCRIPTION:
XS GIS Cut Line= 3
      2377824.98     13703375.01        2377025.       13703625.
        2376225.       13704425.
#Sta/Elev= 30
  4161.9   399.1  4313.3  392.82  4360.9  389.92  4443.2  387.14  4455.2  386.07
  4480.9  385.67  4513.4  383.33  4570.5   380.8  4776.4  374.79  4783.7  374.14
  4810.8  374.01  4848.6  372.93  4881.1  372.87  4914.9  371.61  4989.6  370.51
  4992.5  369.44    4993  368.94  5001.9  368.94  5002.4  369.44  5004.3  369.45
  5056.6  371.12  5070.7  369.66  5099.7   370.2    5396  374.91  5650.6  376.04
  5707.1  376.55  5771.3  378.26  5885.9  380.21  6046.5  383.89  6131.4  386.74
#Mann= 10 ,-1 , 0
  4161.9     .07       0  4776.4     .12       0  4810.8     .07       0
  4914.9     .05       0  4992.5     .05       0  5002.4     .05       0
  5004.3     .12       0  5099.7     .05       0  5771.3    .035       0
  5885.9     .07       0
Bank Sta=4992.5,5002.4
XS Rating Curve= 0 ,0
Exp/Cntr=0.3,0.1

Type RM Length L Ch R = 1 ,11433   ,477,477,477
BEGIN DESCRIPTION:
XS7081
END DESCRIPTION:
XS GIS Cut Line= 3
      2377595.81     13703193.35      2376719.84     13703404.79
      2375929.23     13704376.46
#Sta/Elev= 30
  4017.2  390.98  4044.6  391.25  4059.2  389.84  4141.5  387.09  4182.6  384.29
  4203.2  384.21    4343  378.16  4450.1  375.04  4579.9  372.87  4717.6  371.23
  4766.9  369.66  4820.4  370.85  4892.4  370.53  4902.9  368.63  4920.1  370.29
  4993.4   368.9  5021.7  369.67  5030.1  368.28  5030.6  367.78    5040  368.28
  5078.1  369.78  5092.5  368.95  5121.2  370.32  5213.9  371.27  5312.4  374.64
  5383.4  377.79  5473.2  377.45  5613.3  378.66  5817.9  382.18    6171  391.64
#Mann= 8 ,-1 , 0
  4017.2     .07       0  4579.9     .05       0  4920.1     .07       0
  5030.1     .05       0    5040     .07       0  5312.4     .05       0
  5473.2    .035       0  5613.3     .07       0
Bank Sta=5030.1,5040
XS Rating Curve= 0 ,0
Exp/Cntr=0.3,0.1

Type RM Length L Ch R = 1 ,10956   ,454,454,454
BEGIN DESCRIPTION:
Stream0564 22.0
END DESCRIPTION:
XS GIS Cut Line= 3
      2377474.99       13703125.        2376275.       13703225.
      2375974.99     13703825.02
#Sta/Elev= 30
  3799.7  386.68  3849.9   384.2  3857.4  384.82    3890  382.81  3930.1  381.87
  3982.8  378.91  4020.5  378.52  4080.7  375.46  4344.6     372  4512.2  368.55
  4552.3  369.95  4592.4  369.22  4712.8  370.52  4913.5  368.45  4943.1  367.43
  4973.7  368.21  4996.3  366.13  4996.8  365.63  5006.3  366.13  5017.8   368.2
  5037.9  369.04  5038.3  369.07  5146.4  374.22  5315.5  377.48  5532.6  381.02
  5593.6  382.54    5616  381.55    5630  383.32  5641.1  383.39  5674.7  383.49
#Mann= 10 ,-1 , 0
  3799.7     .07       0  4344.6     .05       0  4943.1     .07       0
  4996.3     .05       0  5006.3     .07       0  5037.9     .05       0
  5038.3     .07       0  5315.5     .05       0  5532.6     .07       0
  5641.1    .035       0
Bank Sta=4996.3,5006.3
XS Rating Curve= 0 ,0
Exp/Cntr=0.3,0.1

Type RM Length L Ch R = 1 ,10502   ,459,459,459
BEGIN DESCRIPTION:
Stream0564 21.0
END DESCRIPTION:
XS GIS Cut Line= 3
      2377225.04       13702775.        2376425.       13702825.
      2375625.01       13702825.
#Sta/Elev= 30
  4198.9  382.32    4209  381.01    4219  381.47  4319.2  377.31  4349.2  376.23
  4359.3  376.49  4389.3  374.88  4429.4  374.11  4489.5  371.63  4549.6  370.22
    4636  369.48    4730  369.03  4770.1  367.48  4840.2   368.6  4890.3  368.44
  4950.4  367.61  4997.9  365.79  5005.2  365.52  5005.7  365.02  5015.3  365.02
  5015.8  365.52  5050.5  367.14  5080.5  366.69  5150.5   367.8  5168.7  367.43
  5182.6  367.68  5320.5  370.77  5490.5  372.57  5644.7  377.03  5800.5  382.16
#Mann= 8 ,-1 , 0
  4198.9     .07       0    4636     .05       0  4997.9     .07       0
  5005.2     .05       0  5015.8     .07       0  5168.7     .05       0
  5182.6     .07       0  5644.7     .05       0
Bank Sta=5005.2,5015.8
XS Rating Curve= 0 ,0
Exp/Cntr=0.3,0.1

Type RM Length L Ch R = 1 ,10043   ,444,444,444
BEGIN DESCRIPTION:
Stream0564 20.0
END DESCRIPTION:
XS GIS Cut Line= 3
      2377275.01       13702725.        2376475.       13702475.
      2375674.97     13702775.01
#Sta/Elev= 30
  4161.9  383.65  4275.6  380.31  4308.1   375.8  4313.3  378.76  4545.9  370.61
  4753.7  367.91  4769.6  368.88  4790.5  372.07    4801  372.23  4832.4  369.96
  4848.7  367.03  4853.9  367.58  4863.9  364.54  4874.3  363.22    4946  362.97
  4946.5  362.47  4956.7  362.97  4978.6  364.21  4983.8  365.72  5021.4  364.97
  5085.5  366.56  5241.3  368.25  5246.6  367.43  5288.4  368.23  5296.4  369.48
  5301.8  368.81  5320.5  370.37  5488.4  373.56  5827.8  379.49  5854.5  380.69
#Mann= 6 ,-1 , 0
  4161.9     .07       0  4753.7     .05       0    4946     .05       0
  4956.7     .05       0  5488.4     .07       0  5827.8     .05       0
Bank Sta=4946,4956.7
XS Rating Curve= 0 ,0
Exp/Cntr=0.3,0.1

Type RM Length L Ch R = 1 ,9599    ,463,463,463
BEGIN DESCRIPTION:
Stream0564 19.0
END DESCRIPTION:
XS GIS Cut Line= 3
      2377024.98     13701375.02        2376225.       13702125.
      2375424.99     13702675.01
#Sta/Elev= 30
  3903.2   381.1  3931.3  380.47  3938.6  379.51  3959.6  378.65  3995.2  378.21
  4058.8  376.18  4066.1  376.91  4080.2   376.8  4113.3  375.19  4268.1  371.94
  4423.5  368.58  4766.5  365.93  4815.9  366.25    4851  367.26  4900.8  365.71
  4921.9  364.57  4923.5  363.85    4924  363.35  4934.3  363.35  4934.8  363.85
  4964.4  364.58  5036.2  364.44  5150.6   367.7  5323.8  373.96  5380.6  375.05
  5513.3  375.69  5671.5  377.21  5798.8  379.94  5927.3  384.56  5970.6  385.53
#Mann= 8 ,-1 , 0
  3903.2     .07       0  4113.3     .05       0  4268.1     .07       0
  4423.5     .05       0  4923.5     .05       0  4934.8     .05       0
  5513.3     .07       0  5671.5     .05       0
Bank Sta=4923.5,4934.8
XS Rating Curve= 0 ,0
Exp/Cntr=0.3,0.1