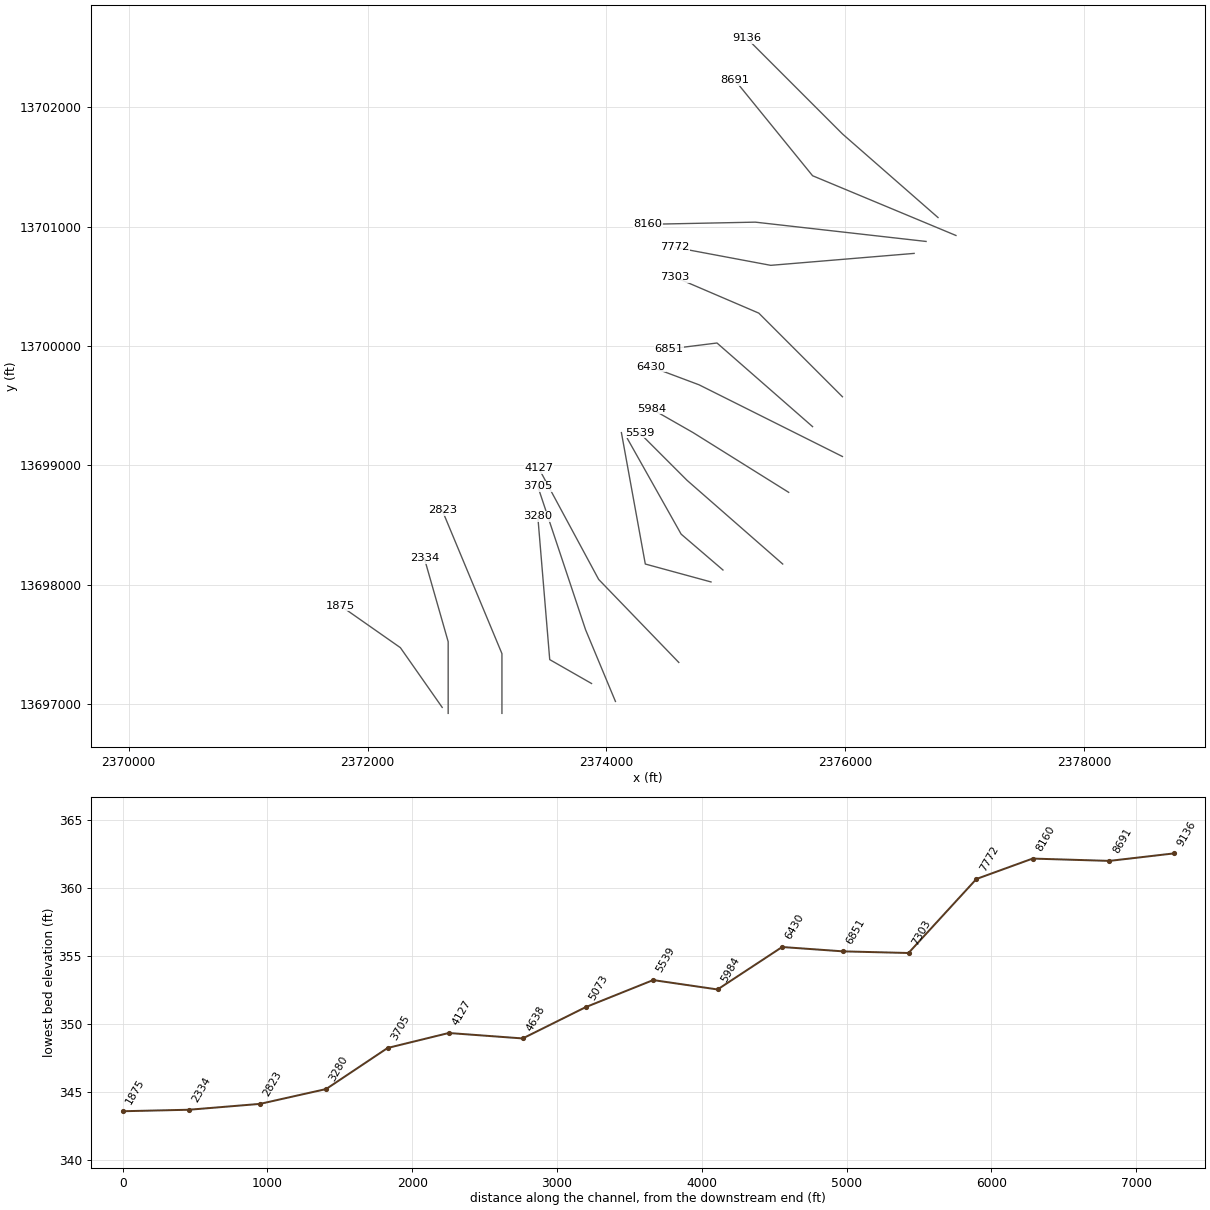
HEC-RAS study Stream0564.prj: Stream0564 Base Level Engineering

--- Stream0564.g01 (geometry) --- (continued)

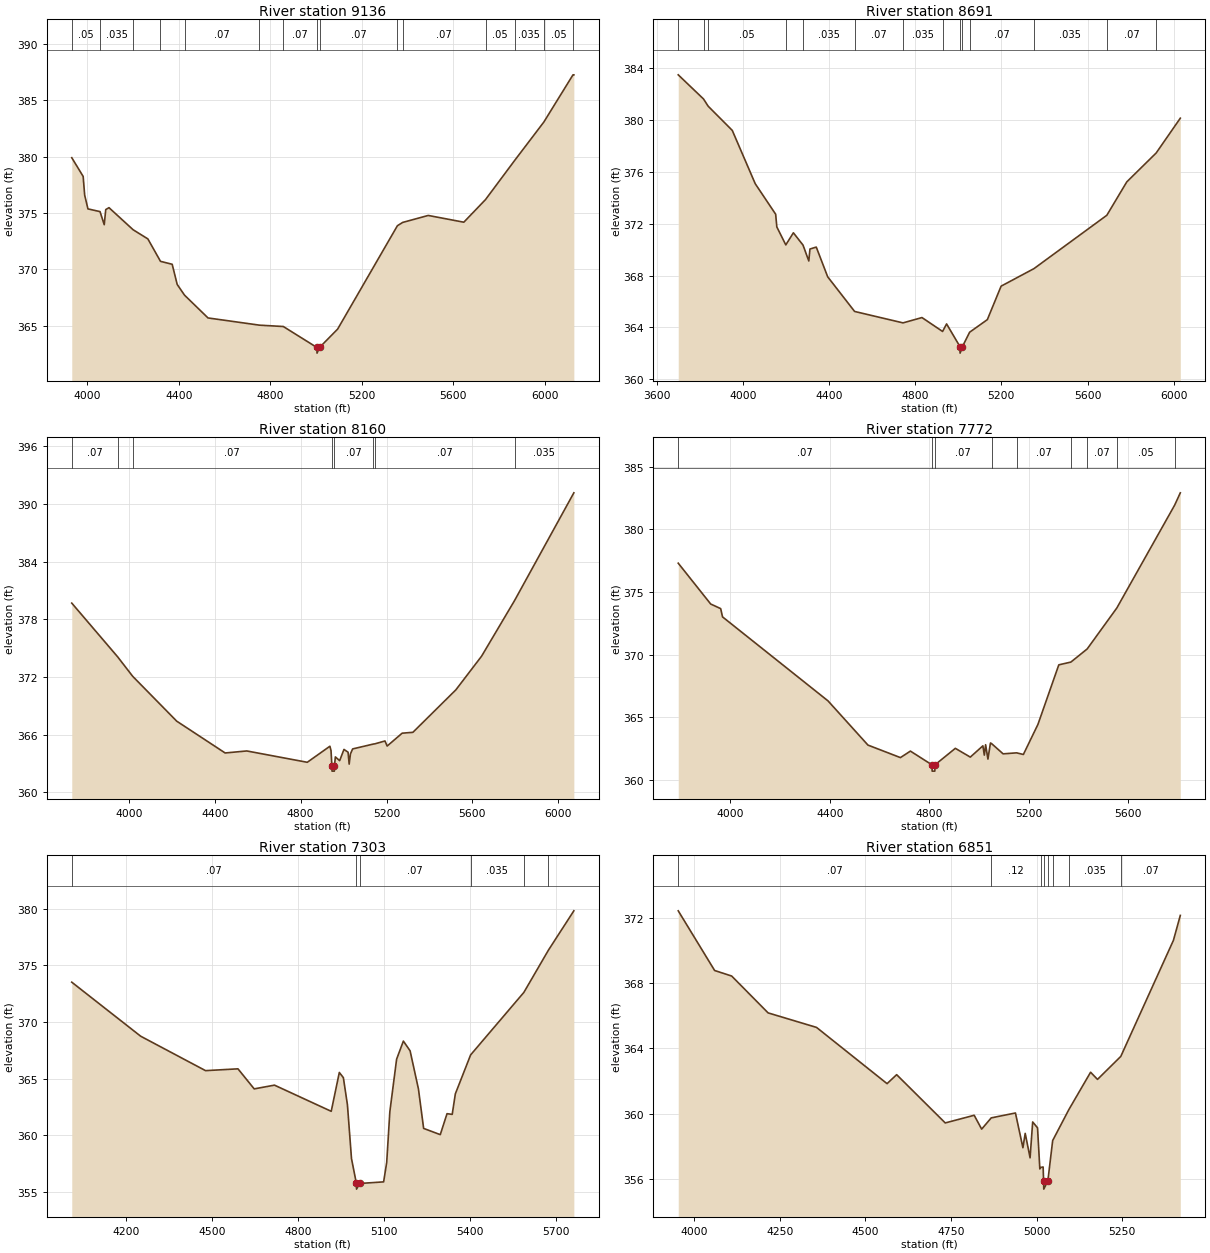
Type RM Length L Ch R = 1 ,9136    ,445,445,445
BEGIN DESCRIPTION:
Stream0564 18.0
END DESCRIPTION:
XS GIS Cut Line= 3
      2376774.98     13701075.02        2375975.       13701775.
      2375174.97     13702575.03
#Sta/Elev= 30
    3932   379.9  3981.8  378.24  3988.4  376.58  4002.7  375.36  4055.5  375.12
  4073.9  373.96  4080.5   375.3  4094.7  375.47  4200.2  373.51  4264.6   372.7
  4319.8  370.71  4370.9  370.45  4392.8  368.66  4424.9  367.71  4527.5  365.69
  4752.4  365.05  4856.6  364.93  5003.5  363.07    5004  362.57  5014.8  363.07
    5094   364.7  5355.3  373.87  5378.3  374.16    5490  374.78  5645.5  374.18
  5740.5  376.19  5868.2  379.67  5995.2  383.06  6122.7  387.25  6126.4  387.25
#Mann= 15 ,-1 , 0
    3932     .05       0  4055.5    .035       0  4200.2     .07       0
  4319.8     .05       0  4424.9     .07       0  4752.4    .035       0
  4856.6     .07       0  5003.5     .05       0  5014.8     .07       0
  5355.3     .05       0  5378.3     .07       0  5740.5     .05       0
  5868.2    .035       0  5995.2     .05       0  6122.7     .07       0
Bank Sta=5003.5,5014.8
XS Rating Curve= 0 ,0
Exp/Cntr=0.3,0.1

Type RM Length L Ch R = 1 ,8691    ,531,531,531
BEGIN DESCRIPTION:
Stream0564 17.0
END DESCRIPTION:
XS GIS Cut Line= 3
      2376924.98     13700925.01        2375725.       13701425.
      2375074.97     13702225.04
#Sta/Elev= 30
    3700  383.46  3817.3   381.6  3839.1  381.04  3950.8  379.18  4057.5  375.07
  4152.3  372.72  4157.7  371.74  4199.4  370.36  4234.6  371.29  4279.4  370.34
  4306.1  369.12  4311.5  370.04  4340.8  370.19  4393.8   367.9  4518.8  365.23
  4743.6  364.35  4831.5  364.76  4927.2  363.69  4945.8  364.27    5008  362.52
  5008.5  362.02  5019.3  362.52  5052.7  363.63    5135   364.6  5198.9  367.18
  5351.4  368.53  5689.7  372.64  5782.2  375.21  5918.8  377.44  6030.8  380.12
#Mann= 14 ,-1 , 0
    3700     .05       0  3817.3     .07       0  3839.1     .05       0
  4199.4     .07       0  4279.4    .035       0  4518.8     .07       0
  4743.6    .035       0  4927.2     .15       0    5008     .05       0
  5019.3     .15       0  5052.7     .07       0  5351.4    .035       0
  5689.7     .07       0  5918.8    .035       0
Bank Sta=5008,5019.3
XS Rating Curve= 0 ,0
Exp/Cntr=0.3,0.1

Type RM Length L Ch R = 1 ,8160    ,388,388,388
BEGIN DESCRIPTION:
Stream0564 16.0
END DESCRIPTION:
XS GIS Cut Line= 3
      2376675.01       13700875.      2375245.72     13701036.53
      2374345.49     13701018.41
#Sta/Elev= 30
  3733.7  379.68  3947.7  374.08  4017.5  372.06  4222.6  367.39  4448.2  364.08
  4548.9  364.29  4830.7  363.11  4936.1  364.78  4941.4  364.33  4945.5  362.69
    4946  362.19  4956.8  362.19  4957.3  362.69  4961.5  363.67  4981.6  363.28
  5001.7  364.45  5020.8  364.16  5025.9  362.92  5031.9  363.98    5042   364.5
  5139.1  365.01  5145.7  365.03  5192.8  365.33  5202.8   364.8  5272.8  366.14
  5322.8  366.23  5522.9  370.65  5642.9  374.16  5796.2  379.94  6072.5  391.16
#Mann= 8 ,-1 , 0
  3733.7     .07       0  3947.7     .05       0  4017.5     .07       0
  4945.5     .05       0  4957.3     .07       0  5139.1     .12       0
  5145.7     .07       0  5796.2    .035       0
Bank Sta=4945.5,4957.3
XS Rating Curve= 0 ,0
Exp/Cntr=0.3,0.1

Type RM Length L Ch R = 1 ,7772    ,469,469,469
BEGIN DESCRIPTION:
Stream0564 15.0
END DESCRIPTION:
XS GIS Cut Line= 3
      2376574.99       13700775.        2375375.       13700675.
      2374574.99       13700825.
#Sta/Elev= 30
  3790.7   377.3  3921.1  374.04  3961.3  373.67  3968.8  373.01  4392.8   366.3
  4553.3  362.77  4683.8  361.77  4723.9  362.29  4810.8  361.19  4811.3  360.69
  4822.1  360.69  4822.6  361.19  4904.5  362.51  4964.7  361.81  5015.2  362.71
  5021.1  361.97  5026.2   362.8  5035.5  361.65  5045.7  362.94  5050.1  362.89
  5096.6  362.07  5150.8  362.15    5178  362.02  5236.5  364.42  5320.4  369.18
  5368.9   369.4  5434.5  370.45  5553.6  373.72  5786.2  381.94  5808.8  382.92
#Mann= 9 ,-1 , 0
  3790.7     .07       0  4810.8     .05       0  4822.6     .07       0
  5050.1     .12       0  5150.8     .07       0  5368.9    .035       0
  5434.5     .07       0  5553.6     .05       0  5786.2     .07       0
Bank Sta=4810.8,4822.6
XS Rating Curve= 0 ,0
Exp/Cntr=0.3,0.1

Type RM Length L Ch R = 1 ,7303    ,452,452,452
BEGIN DESCRIPTION:
Stream0564 14.0
END DESCRIPTION:
XS GIS Cut Line= 3
        2375975.       13699575.        2375275.       13700275.
      2374575.02     13700574.99
#Sta/Elev= 30
  4010.5  373.52  4250.9  368.75  4477.2  365.71  4590.3  365.87  4646.9   364.1
  4717.6  364.43  4915.6  362.12  4943.9  365.55    4958  365.09  4972.2  362.69
  4986.3  357.95  5003.4  355.75  5003.9  355.25  5015.7  355.75  5098.4  355.89
  5109.2  357.61  5120.1  362.08  5143.7  366.72  5167.3  368.32  5190.8  367.46
  5219.9  364.09    5238  360.61    5296  360.06  5319.6  361.91  5337.7  361.85
  5348.6  363.66  5401.9   367.1  5587.7  372.62  5673.4  376.35    5762  379.82
#Mann= 6 ,-1 , 0
  4010.5     .07       0  5003.4     .05       0  5015.7     .07       0
  5401.9    .035       0  5587.7     .05       0  5673.4     .07       0
Bank Sta=5003.4,5015.7
XS Rating Curve= 0 ,0
Exp/Cntr=0.3,0.1

Type RM Length L Ch R = 1 ,6851    ,421,421,421
BEGIN DESCRIPTION:
Stream0564 13.0
END DESCRIPTION:
XS GIS Cut Line= 3
      2375724.99       13699325.        2374925.       13700025.
      2374525.02       13699975.
#Sta/Elev= 30
  3953.3  372.44  4059.6  368.78  4109.4  368.44  4215.7  366.18  4357.1  365.29
  4563.1  361.84  4591.1  362.39    4733  359.43  4817.5   359.9  4839.3  359.05
  4867.3  359.74    4938  360.04  4959.8  357.91  4966.5  358.79  4980.7  357.29
  4988.3  359.49  5002.5  359.13  5009.2  356.61  5012.1   356.7  5018.8  356.73
  5020.2  355.87  5020.7  355.37  5032.6  355.87  5046.7  358.35    5094  360.25
  5157.4  362.54  5177.6   362.1  5245.6  363.51  5399.3  370.63  5419.4  372.16
#Mann= 8 ,-1 , 0
  3953.3     .07       0  4867.3     .12       0  5012.1     .07       0
  5020.2     .05       0  5032.6     .07       0  5046.7     .12       0
    5094    .035       0  5245.6     .07       0
Bank Sta=5020.2,5032.6
XS Rating Curve= 0 ,0
Exp/Cntr=0.3,0.1

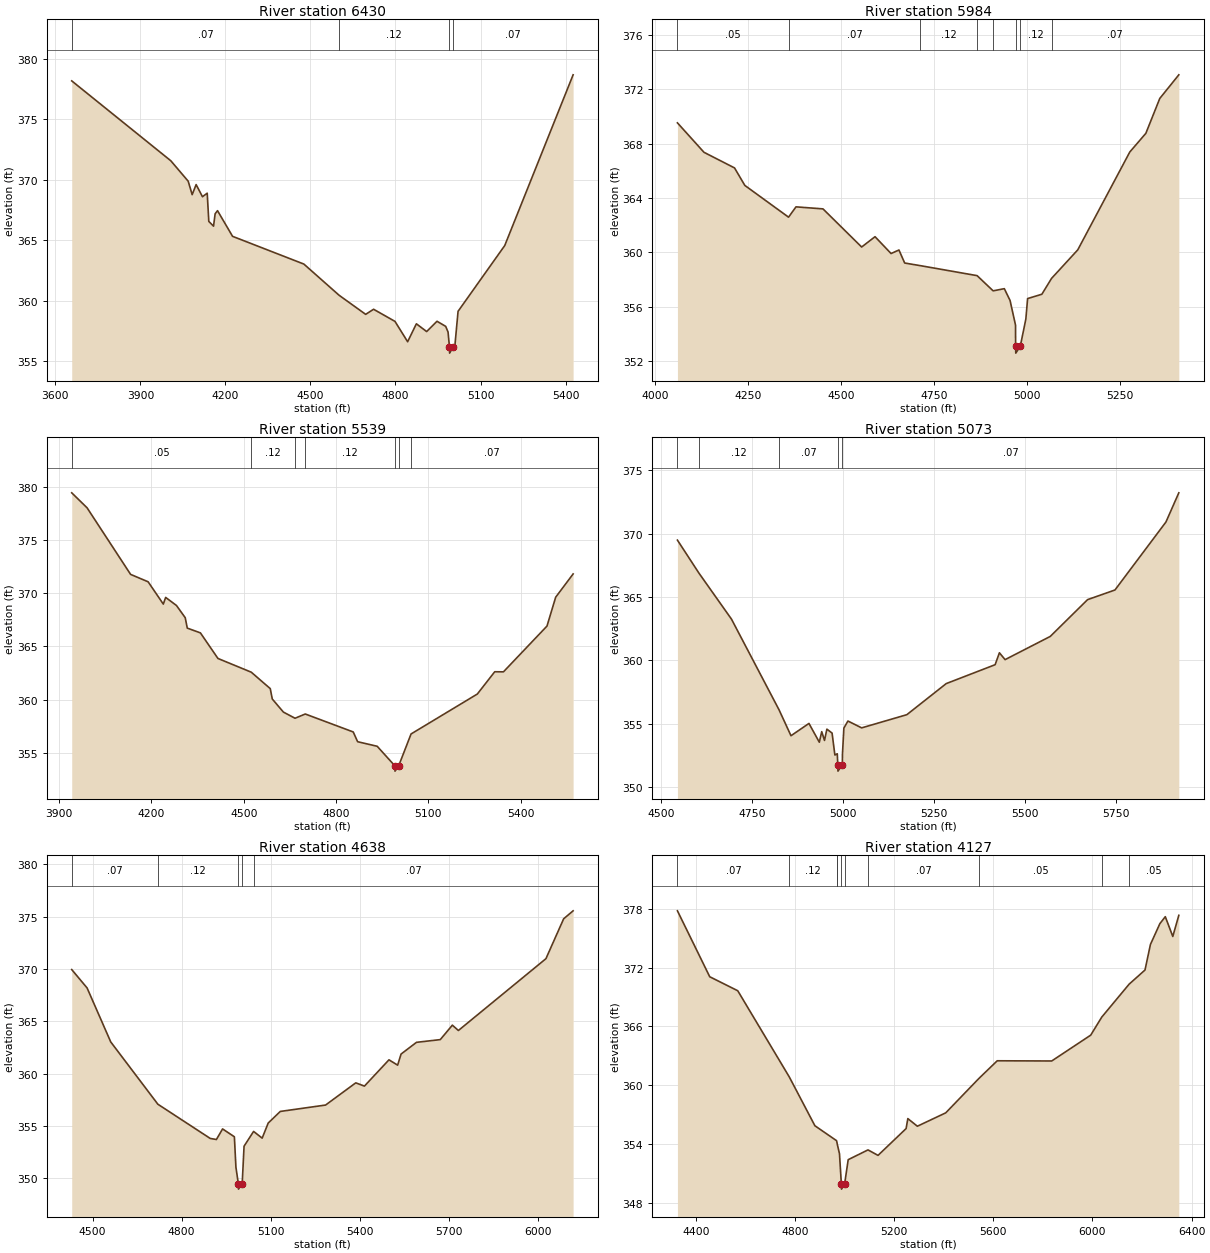
Type RM Length L Ch R = 1 ,6430    ,446,446,446
BEGIN DESCRIPTION:
Stream0564 12.0
END DESCRIPTION:
XS GIS Cut Line= 3
      2375975.02     13699074.99        2374775.       13699675.
      2374374.97     13699825.01
#Sta/Elev= 30
  3657.8  378.16  4007.2  371.57  4068.7  369.88  4082.7  368.77  4096.7   369.6
    4119   368.6  4135.8  368.89  4141.4  366.56  4158.1  366.17  4163.7  367.19
  4172.1  367.45  4225.2  365.33  4476.8  363.04  4600.9  360.47  4694.8  358.89
  4722.8  359.31  4798.2  358.31  4842.9  356.63  4873.7  358.11    4910  357.47
  4946.4  358.32  4977.1   357.9  4985.5  357.43  4990.5  356.19    4991  355.69
  5002.9  356.19  5009.3  356.23  5020.8  359.14  5185.5  364.57  5426.7  378.66
#Mann= 4 ,-1 , 0
  3657.8     .07       0  4600.9     .12       0  4990.5     .05       0
  5002.9     .07       0
Bank Sta=4990.5,5002.9
XS Rating Curve= 0 ,0
Exp/Cntr=0.3,0.1

Type RM Length L Ch R = 1 ,5984    ,445,445,445
BEGIN DESCRIPTION:
Stream0564 11.0
END DESCRIPTION:
XS GIS Cut Line= 3
      2375524.99       13698775.        2374725.       13699275.
        2374375.       13699475.
#Sta/Elev= 30
  4060.8  369.54  4132.1  367.37  4214.1  366.22  4241.8  364.93  4359.2  362.59
  4379.2  363.35  4451.7   363.2  4555.5  360.39  4591.5  361.15  4634.5  359.91
  4655.7  360.17  4671.1  359.21  4712.5  359.02  4865.6  358.28  4908.6  357.16
  4938.7  357.32  4954.1  356.45  4968.8  354.63    4969  353.07  4969.5  352.57
  4981.5  353.07  4996.5  355.08  5001.2  356.59  5039.5  356.91  5065.6  358.08
  5135.9  360.18  5275.6  367.39  5318.8  368.77  5356.2  371.34  5407.3  373.08
#Mann= 8 ,-1 , 0
  4060.8     .05       0  4359.2     .07       0  4712.5     .12       0
  4865.6     .07       0  4908.6     .12       0    4969     .05       0
  4981.5     .12       0  5065.6     .07       0
Bank Sta=4969,4981.5
XS Rating Curve= 0 ,0
Exp/Cntr=0.3,0.1

Type RM Length L Ch R = 1 ,5539    ,466,466,466
BEGIN DESCRIPTION:
Stream0564 10.0
END DESCRIPTION:
XS GIS Cut Line= 3
      2375474.97     13698175.03        2374675.       13698875.
      2374274.97     13699275.03
#Sta/Elev= 30
  3941.4  379.47  3991.2  378.06  4132.6  371.79  4189.6  371.09  4238.9  368.99
  4246.5  369.62  4281.6  368.86  4310.1  367.71  4316.7  366.73  4359.4  366.28
  4416.4  363.87  4524.5  362.58  4586.3  361.03  4592.9  360.05    4629  358.82
  4666.8  358.24    4700  358.64  4855.8  356.95  4870.1  356.03  4933.7   355.6
    4991  353.76  4991.5  353.26  5003.5  353.76  5043.7  356.76  5258.9  360.52
  5315.5  362.62  5343.8  362.61  5485.2  366.92  5513.5  369.64  5570.1  371.83
#Mann= 7 ,-1 , 0
  3941.4     .05       0  4524.5     .12       0  4666.8     .07       0
    4700     .12       0    4991     .05       0  5003.5     .12       0
  5043.7     .07       0
Bank Sta=4991,5003.5
XS Rating Curve= 0 ,0
Exp/Cntr=0.3,0.1

Type RM Length L Ch R = 1 ,5073    ,435,435,435
BEGIN DESCRIPTION:
Stream0564 9.0
END DESCRIPTION:
XS GIS Cut Line= 3
        2374975.       13698125.        2374625.       13698425.
      2374174.98     13699225.04
#Sta/Elev= 30
  4543.9  369.48  4602.8  366.89  4692.6  363.25  4823.4   356.1  4856.2  354.06
  4905.6  355.03  4934.1  353.55  4940.7  354.38  4948.4  353.69  4954.9  354.58
  4969.2  354.27  4976.9  352.54  4983.5  352.64  4984.9  351.77  4985.4  351.27
  4997.5  351.77  4997.7  352.57  5001.6  354.66  5012.8  355.22  5050.5  354.68
  5174.8  355.72  5283.1  358.17  5417.6  359.66  5429.4   360.6    5445  360.06
  5569.3  361.89  5671.9  364.79  5747.2  365.55  5887.4  370.91  5922.8  373.21
#Mann= 5 ,-1 , 0
  4543.9     .07       0  4602.8     .12       0  4823.4     .07       0
  4984.9     .05       0  4997.5     .07       0
Bank Sta=4984.9,4997.5
XS Rating Curve= 0 ,0
Exp/Cntr=0.3,0.1

Type RM Length L Ch R = 1 ,4638    ,511,511,511
BEGIN DESCRIPTION:
Stream0564 8.0
END DESCRIPTION:
XS GIS Cut Line= 3
      2374874.98     13698025.01        2374325.       13698175.
        2374125.       13699275.
#Sta/Elev= 30
  4429.9  369.94  4481.7  368.18  4561.2  363.03  4719.9  357.08  4896.3  353.81
    4917  353.71  4937.8  354.72  4977.5  353.97  4982.7  351.07  4990.9  349.47
  4991.4  348.97  5003.8  349.47  5010.1  353.07  5042.2  354.48  5071.1  353.84
  5091.4  355.28  5132.1  356.39  5284.6     357  5386.2  359.12  5415.4  358.81
    5498  361.32  5527.2  360.81  5538.7  361.87  5590.7  362.99  5670.8  363.25
  5711.4  364.63  5731.8  364.12  6026.5  370.98  6086.2  374.79    6118  375.55
#Mann= 5 ,-1 , 0
  4429.9     .07       0  4719.9     .12       0  4990.9     .05       0
  5003.8     .12       0  5042.2     .07       0
Bank Sta=4990.9,5003.8
XS Rating Curve= 0 ,0
Exp/Cntr=0.3,0.1

Type RM Length L Ch R = 1 ,4127    ,422,422,422
BEGIN DESCRIPTION:
XS7080
END DESCRIPTION:
XS GIS Cut Line= 3
      2374605.33     13697351.22      2373934.72       13698046.
      2373433.29     13698976.35
#Sta/Elev= 30
  4325.8  377.82  4456.1  371.08  4569.1  369.65    4777  360.84  4880.3  355.85
  4967.8  354.32  4971.4  353.87  4979.4     353  4987.1  349.87  4987.6  349.37
    5000  349.87  5014.6  352.38  5094.5  353.38    5135  352.82  5248.2  355.56
  5255.2  356.58  5293.7   355.8  5408.2  357.17  5541.7  360.68  5615.8  362.49
  5835.6  362.47  5992.9  365.11  6037.6  366.96  6147.8  370.32  6211.9  371.77
  6233.8  374.38  6271.9  376.51  6293.8  377.22    6324   375.2  6348.3  377.36
#Mann= 10 ,-1 , 0
  4325.8     .07       0    4777     .12       0  4967.8     .07       0
  4971.4     .12       0  4987.1     .05       0    5000     .12       0
  5094.5     .07       0  5541.7     .05       0  6037.6    .035       0
  6147.8     .05       0
Bank Sta=4987.1,5000
XS Rating Curve= 0 ,0
Exp/Cntr=0.3,0.1

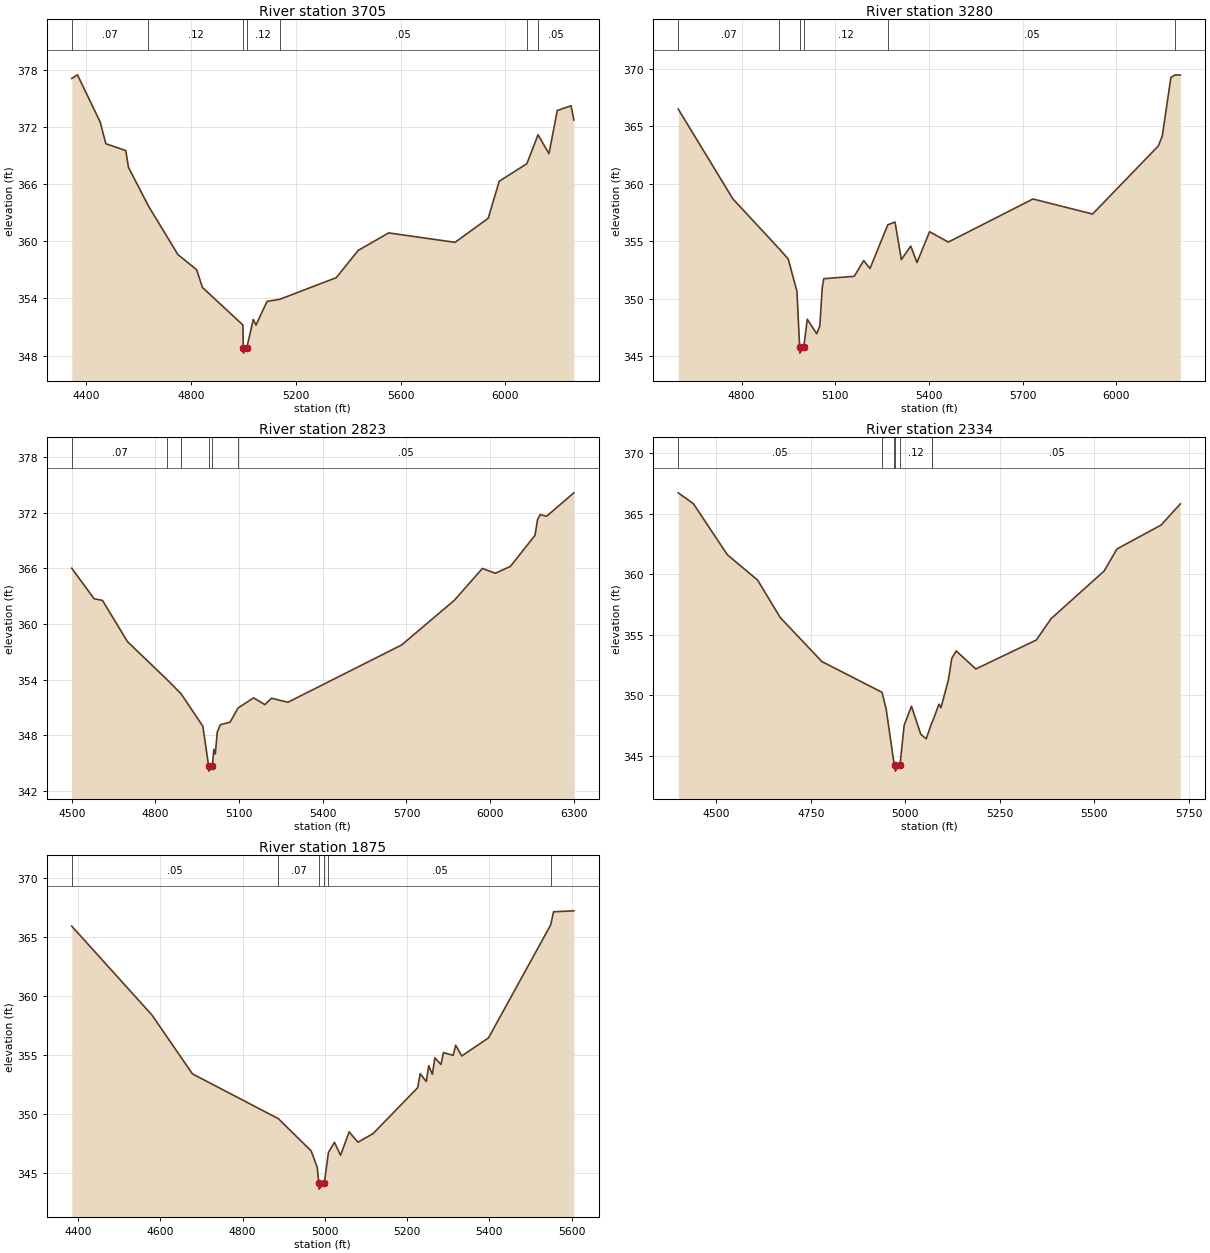
Type RM Length L Ch R = 1 ,3705    ,425,425,425
BEGIN DESCRIPTION:
Stream0564 7.0
END DESCRIPTION:
XS GIS Cut Line= 3
      2374075.01     13697024.97        2373825.       13697625.
      2373425.02     13698824.95
#Sta/Elev= 30
    4346  377.08  4367.7  377.46  4454.4  372.51    4476  370.23  4551.9  369.52
  4562.2  367.76  4637.9  363.73  4750.7  358.61  4822.2  357.02  4844.4  355.16
  4998.7  351.22  5000.1  348.77  5000.6  348.27  5013.1  348.77  5038.2   351.8
  5048.7  351.21  5090.9   353.7  5138.7  353.91  5354.4  356.18  5438.8  359.05
  5554.7  360.88  5807.7  359.89  5934.2  362.41  5976.3   366.3  6081.7  368.14
  6124.3  371.17  6166.1  369.19  6197.7  373.72  6250.4  374.21  6260.9  372.72
#Mann= 7 ,-1 , 0
    4346     .07       0  4637.9     .12       0  5000.1     .05       0
  5013.1     .12       0  5138.7     .05       0  6081.7    .035       0
  6124.3     .05       0
Bank Sta=5000.1,5013.1
XS Rating Curve= 0 ,0
Exp/Cntr=0.3,0.1

Type RM Length L Ch R = 1 ,3280    ,457,457,457
BEGIN DESCRIPTION:
Stream0564 6.0
END DESCRIPTION:
XS GIS Cut Line= 3
      2373874.97     13697175.02        2373525.       13697375.
        2373425.     13698574.96
#Sta/Elev= 30
  4597.2   366.5  4772.1  358.68  4920.2  354.34  4949.2  353.45  4977.2  350.63
  4985.9  345.75  4986.4  345.25  4998.9  345.75  5010.3   348.2  5040.4  346.94
  5050.5  347.62    5058  350.89    5063  351.73  5160.8  351.94  5190.9  353.31
    5211  352.62  5268.1  356.43  5291.3  356.66  5311.4  353.39  5341.5  354.57
  5361.5  353.14  5401.7  355.82  5461.9  354.92  5732.8  358.67  5923.5  357.36
  6134.2  363.29  6146.7  364.16  6174.3  369.25  6188.4  369.48  6204.4  369.46
#Mann= 6 ,-1 , 0
  4597.2     .07       0  4920.2     .12       0  4985.9     .05       0
  4998.9     .12       0  5268.1     .05       0  6188.4    .035       0
Bank Sta=4985.9,4998.9
XS Rating Curve= 0 ,0
Exp/Cntr=0.3,0.1

Type RM Length L Ch R = 1 ,2823    ,489,489,489
BEGIN DESCRIPTION:
Stream0564 5.0
END DESCRIPTION:
XS GIS Cut Line= 3
        2373125.     13696925.04        2373125.       13697425.
      2372624.98     13698625.04
#Sta/Elev= 30
    4500     366    4580  362.72    4610  362.54    4700  358.09    4841  354.03
  4891.9  352.49    4970  348.99  4990.9  344.66  4991.4  344.16    5004  344.66
  5009.2   346.5  5014.6  346.01  5021.6  348.36  5032.5  349.15  5067.7  349.43
  5095.6  350.94  5151.6  352.05  5192.2  351.32  5216.1  352.01  5274.6  351.57
  5682.5  357.74  5871.5  362.55  5972.2  365.98  6018.3  365.46  6072.5   366.2
  6160.7  369.54    6170  371.26  6179.2  371.77  6202.5   371.6    6300  374.12
#Mann= 6 ,-1 , 0
    4500     .07       0    4841     .05       0  4891.9     .12       0
  4990.9     .05       0    5004     .12       0  5095.6     .05       0
Bank Sta=4990.9,5004
XS Rating Curve= 0 ,0
Exp/Cntr=0.3,0.1

Type RM Length L Ch R = 1 ,2334    ,459,459,459
BEGIN DESCRIPTION:
Stream0564 4.0
END DESCRIPTION:
XS GIS Cut Line= 3
        2372675.     13696924.97        2372675.       13697525.
      2372475.01     13698224.96
#Sta/Elev= 30
  4399.4  366.72  4439.4  365.83  4529.4   361.6  4609.4  359.51  4669.4  356.41
  4779.4  352.78  4938.5  350.24  4949.4  348.85  4969.3  344.55  4972.8  344.23
  4973.3  343.73    4986  344.23  4996.9  347.51  5016.3  349.09    5041  346.77
  5055.3   346.4  5069.9  347.72  5071.9  347.82  5089.1  349.26  5094.3  348.97
  5113.8  351.24  5122.9  353.04  5134.6  353.66  5186.6  352.17  5346.5  354.56
  5385.5  356.32  5525.9  360.26  5559.7  362.08  5676.7  364.06  5727.4  365.81
#Mann= 7 ,-1 , 0
  4399.4     .05       0  4938.5     .07       0  4969.3     .12       0
  4972.8     .05       0    4986     .12       0  5069.9     .07       0
  5071.9     .05       0
Bank Sta=4972.8,4986
XS Rating Curve= 0 ,0
Exp/Cntr=0.3,0.1

Type RM Length L Ch R = 1 ,1875    ,915,915,915
BEGIN DESCRIPTION:
Stream0564 3.0
END DESCRIPTION:
XS GIS Cut Line= 3
      2372625.01     13696974.99        2372275.       13697475.
      2371774.98     13697825.02
#Sta/Elev= 30
  4384.9  365.91  4579.8  358.38  4678.3  353.39  4887.3  349.59  4966.9  346.86
  4981.7  345.47  4985.6  344.12  4986.1  343.62  4998.8  344.12  5008.9  346.72
  5023.6  347.59  5038.4  346.49  5059.3  348.47  5080.7   347.6  5117.3  348.32
  5225.9  352.22    5232  353.41  5246.8  352.74  5252.9  354.08  5261.6  353.35
  5267.7  354.75  5282.5  354.19  5288.6  355.19  5312.2  354.96  5318.3  355.82
  5333.1  354.91  5398.1  356.44  5549.2  366.01  5556.3  367.13  5605.6  367.21
#Mann= 6 ,-1 , 0
  4384.9     .05       0  4887.3     .07       0  4985.6     .05       0
  4998.8     .07       0  5008.9     .05       0  5549.2     .07       0
Bank Sta=4985.6,4998.8
XS Rating Curve= 0 ,0
Exp/Cntr=0.3,0.1