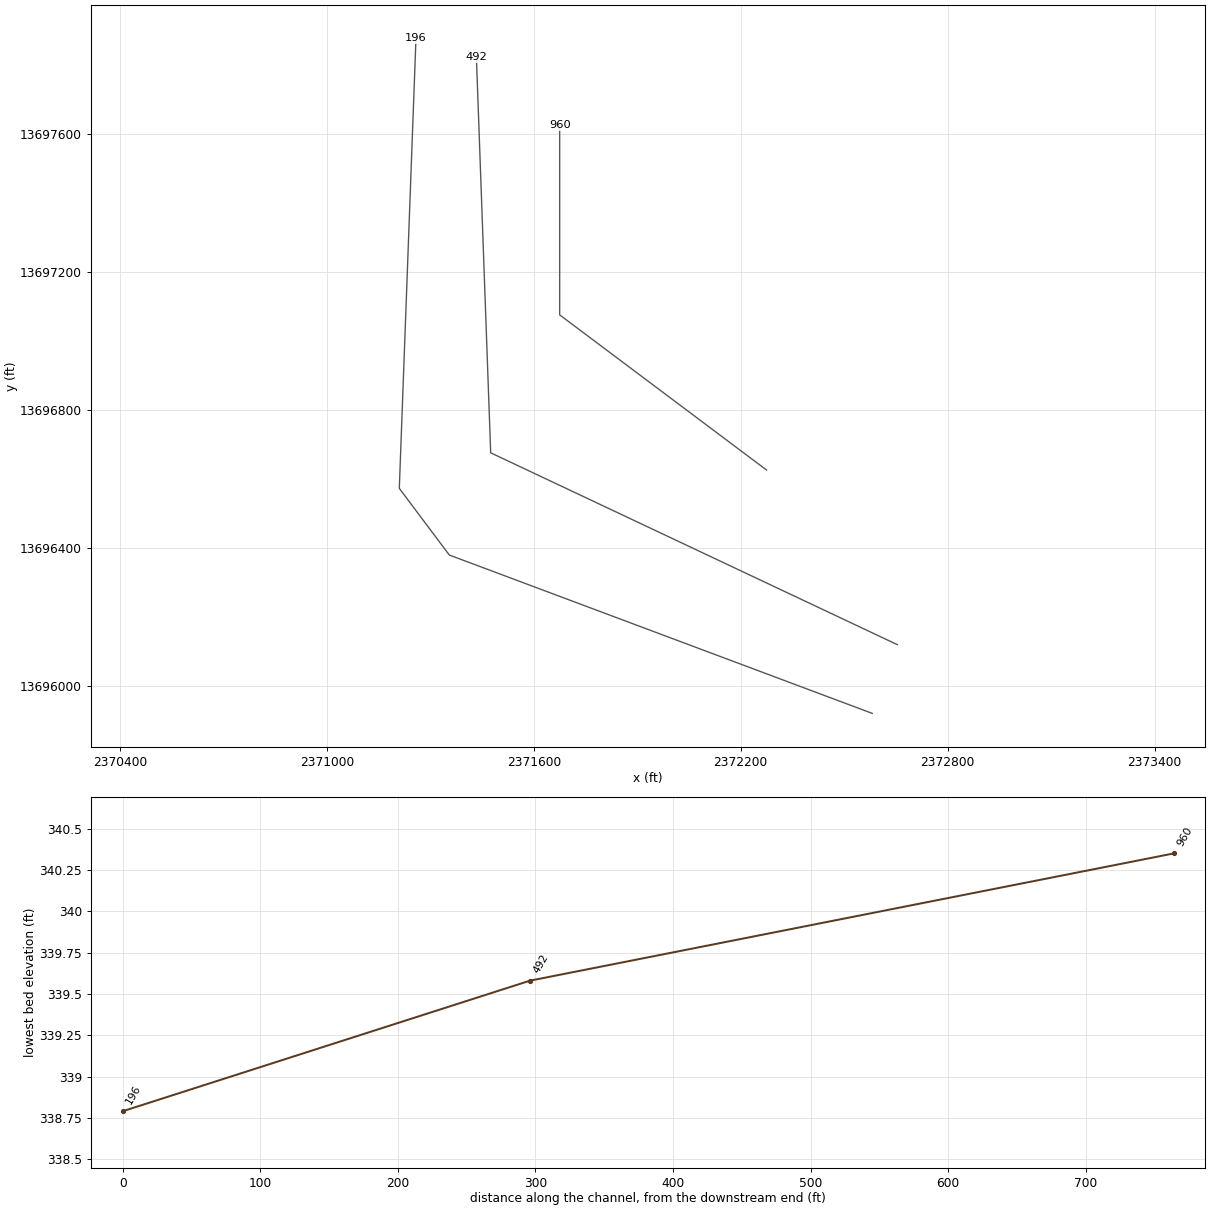
HEC-RAS study Stream0564.prj: Stream0564 Base Level Engineering

--- Stream0564.g01 (geometry) --- (continued)

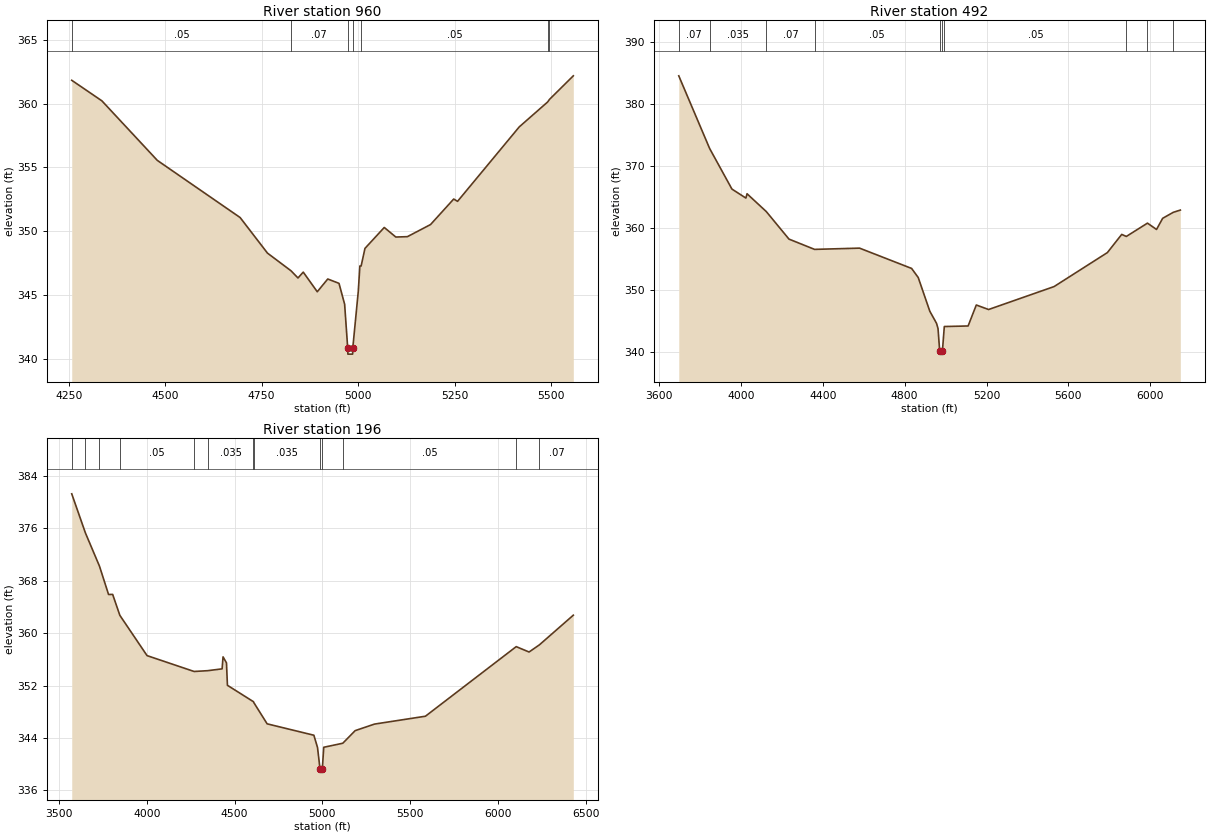
Type RM Length L Ch R = 1 ,960     ,468,468,468
BEGIN DESCRIPTION:
Stream0564 2.0
END DESCRIPTION:
XS GIS Cut Line= 3
      2372274.97     13696625.02        2371675.       13697075.
        2371675.     13697625.04
#Sta/Elev= 30
  4257.9  361.82    4336  360.21  4479.7  355.54  4694.3  351.06  4765.2  348.27
    4826  346.89  4844.3  346.32  4857.9  346.78  4894.3  345.24  4921.4  346.24
  4950.6   345.9  4965.2  344.26  4973.1  340.85  4973.6  340.35  4985.9  340.35
  4986.4  340.85  5000.6  345.28  5004.7  347.26    5008  347.26  5017.9  348.64
  5067.9  350.28  5097.9  349.53  5127.9  349.56  5187.9  350.51  5247.9  352.51
  5257.9  352.33  5417.9  358.17  5491.4  360.12  5496.1  360.32  5557.9  362.17
#Mann= 7 ,-1 , 0
  4257.9     .05       0    4826     .07       0  4973.1     .05       0
  4986.4     .07       0    5008     .05       0  5491.4     .07       0
  5496.1     .05       0
Bank Sta=4973.1,4986.4
XS Rating Curve= 0 ,0
Exp/Cntr=0.3,0.1

Type RM Length L Ch R = 1 ,492     ,296,296,296
BEGIN DESCRIPTION:
Stream0564 1.0
END DESCRIPTION:
XS GIS Cut Line= 3
      2372653.96     13696118.75        2371475.       13696675.
      2371433.59     13697821.26
#Sta/Elev= 30
  3696.4  384.56  3847.3  372.81  3956.1  366.26  4024.4   364.8    4030   365.5
  4124.3  362.61  4234.9  358.17  4359.9  356.51  4579.8  356.71  4834.1  353.43
  4866.4  351.96    4923  346.51  4955.8  344.56  4963.1  343.71  4971.2  340.08
  4971.7  339.58  4984.6  340.08  4993.8  344.04  5110.1  344.13  5150.1  347.52
  5210.1  346.79  5530.3   350.5  5790.5  355.99  5860.6  358.93  5883.1   358.6
  5986.4  360.75  6030.7  359.73  6060.7  361.53  6112.6   362.5    6147  362.86
#Mann= 10 ,-1 , 0
  3696.4     .07       0  3847.3    .035       0  4124.3     .07       0
  4359.9     .05       0  4971.2     .05       0  4984.6     .05       0
  4993.8     .05       0  5883.1    .035       0  5986.4     .07       0
  6112.6    .035       0
Bank Sta=4971.2,4984.6
XS Rating Curve= 0 ,0
Exp/Cntr=0.3,0.1

Type RM Length L Ch R = 1 ,196     ,0,0,0
BEGIN DESCRIPTION:
XS7079
END DESCRIPTION:
XS GIS Cut Line= 4
      2372581.39     13695919.41        2371355.     13696378.55
      2371210.01     13696571.88      2371258.34     13697876.81
#Sta/Elev= 30
  3572.3  381.26  3650.2  375.29  3730.3  370.22    3782   365.9  3805.4  365.91
  3846.3  362.72  4001.3  356.57  4269.3  354.15  4346.6  354.27  4428.8  354.55
  4434.1  356.38  4453.7  355.46  4459.1  352.04  4607.2  349.54  4609.9  349.38
  4685.3  346.16  4951.5  344.42  4972.3  342.55  4986.4  339.29  4986.9  338.79
  4999.8  339.29  5007.7  342.58  5116.3   343.2  5186.6  345.12  5296.7  346.12
  5586.9  347.32  6104.1  357.94  6177.3  357.12  6236.5  358.22  6429.3  362.74
#Mann= 13 ,-1 , 0
  3572.3     .07       0  3650.2     .05       0  3730.3     .07       0
  3846.3     .05       0  4269.3     .07       0  4346.6    .035       0
  4607.2     .05       0  4609.9    .035       0  4986.4    .035       0
  4999.8    .035       0  5116.3     .05       0  6104.1    .035       0
  6236.5     .07       0
Bank Sta=4986.4,4999.8
XS Rating Curve= 0 ,0
Exp/Cntr=0.3,0.1

Chan Stop Cuts=-1
Use User Specified Reach Order=0
Composite Channel Slope=5