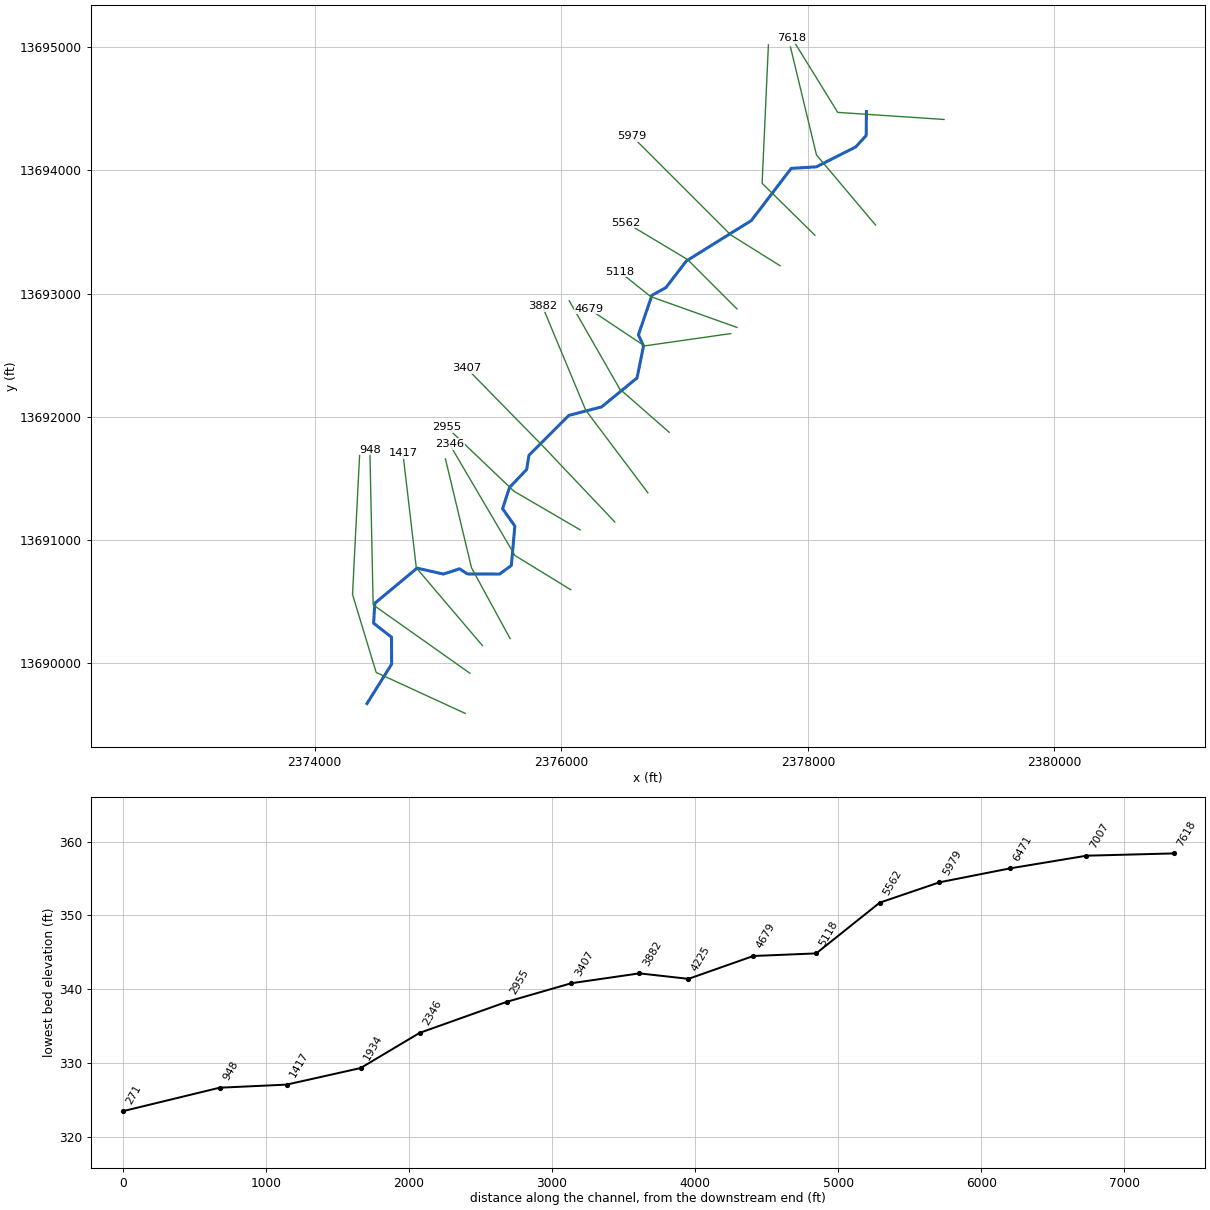
--- Stream0565.prj (project) ---

Proj Title=Stream0565 Base Level Engineering
Current Plan=p01
Default Exp/Contr=0.3,0.1
English Units
Geom File=g01
Flow File=f01
Plan File=p01
BEGIN DESCRIPTION:
Stream0565
END DESCRIPTION:

--- Stream0565.p01 (plan) ---

Plan Title=Multiple Run
Short Identifier=Multiple
Geom File=g01
Flow File=f01
Subcritical Flow
K Sum by GR= 0
Std Step Tol= 0.01
Critical Tol= 0.01
Num of Std Step Trials= 20
Max Error Tol= 0.3
Flow Tol Ratio= 0.001
Split Flow NTrial= 30
Split Flow Tol= 0.02
Split Flow Ratio= 0.02
Log Output Level= 0
Friction Slope Method= 1
Unsteady Friction Slope Method= 2
Unsteady Bridges Friction Slope Method= 1
Parabolic Critical Depth
Global Vel Dist=  1 , 1 , 1
Global Log Level= 0
CheckData=True
Encroach Param= -1, 0, 0, 0
BEGIN DESCRIPTION:
Multiple Run
END DESCRIPTION:

--- Stream0565.f01 (steady flow) ---

Flow Title=Multiple
Number of Profiles=7
Profile Names=10-year,25-year,50-year,1pct_min,100-year,1pct_plu,500-year
River Rch & RM= Stream0565,Reach-1,7618
     733    1193    1611    1053    2102    4194    3546
River Rch & RM= Stream0565,Reach-1,5562
     975    1610    2195    1447    2887    5759    4951
Boundary for River Rch & Prof#=Stream0565,Reach-1,1
Up Type=0
Dn Type=3
Dn Slope=0.005
Boundary for River Rch & Prof#=Stream0565,Reach-1,2
Up Type=0
Dn Type=3
Dn Slope=0.005
Boundary for River Rch & Prof#=Stream0565,Reach-1,3
Up Type=0
Dn Type=3
Dn Slope=0.005
Boundary for River Rch & Prof#=Stream0565,Reach-1,4
Up Type=0
Dn Type=3
Dn Slope=0.005
Boundary for River Rch & Prof#=Stream0565,Reach-1,5
Up Type=0
Dn Type=3
Dn Slope=0.005
Boundary for River Rch & Prof#=Stream0565,Reach-1,6
Up Type=0
Dn Type=3
Dn Slope=0.005
Boundary for River Rch & Prof#=Stream0565,Reach-1,7
Up Type=0
Dn Type=3
Dn Slope=0.005

--- Stream0565.g01 (geometry) ---

Geom Title=Existing Conditions

River Reach=Stream0565,Reach-1
Reach XY= 30
      2378475.00     13694475.00      2378472.96     13694280.84
      2378388.24     13694188.62      2378069.06     13694027.26
      2377864.88     13694014.66      2377541.67     13693591.65
      2377015.32     13693264.22      2376848.83     13693047.86
      2376735.39     13692985.10      2376625.81     13692664.29
      2376667.41     13692575.01      2376614.53     13692315.18
      2376327.43     13692080.52      2376061.70     13692011.60
      2375738.40     13691688.30      2375719.48     13691572.57
      2375580.83     13691427.30      2375524.33     13691254.92
      2375623.94     13691114.56      2375595.53     13690794.71
      2375500.13     13690724.70      2375240.16     13690725.66
      2375175.00     13690767.44      2375045.10     13690724.91
      2374830.86     13690772.95      2374488.37     13690488.32
      2374478.52     13690326.46      2374623.38     13690213.17
      2374625.04     13689994.98      2374425.00     13689675.00

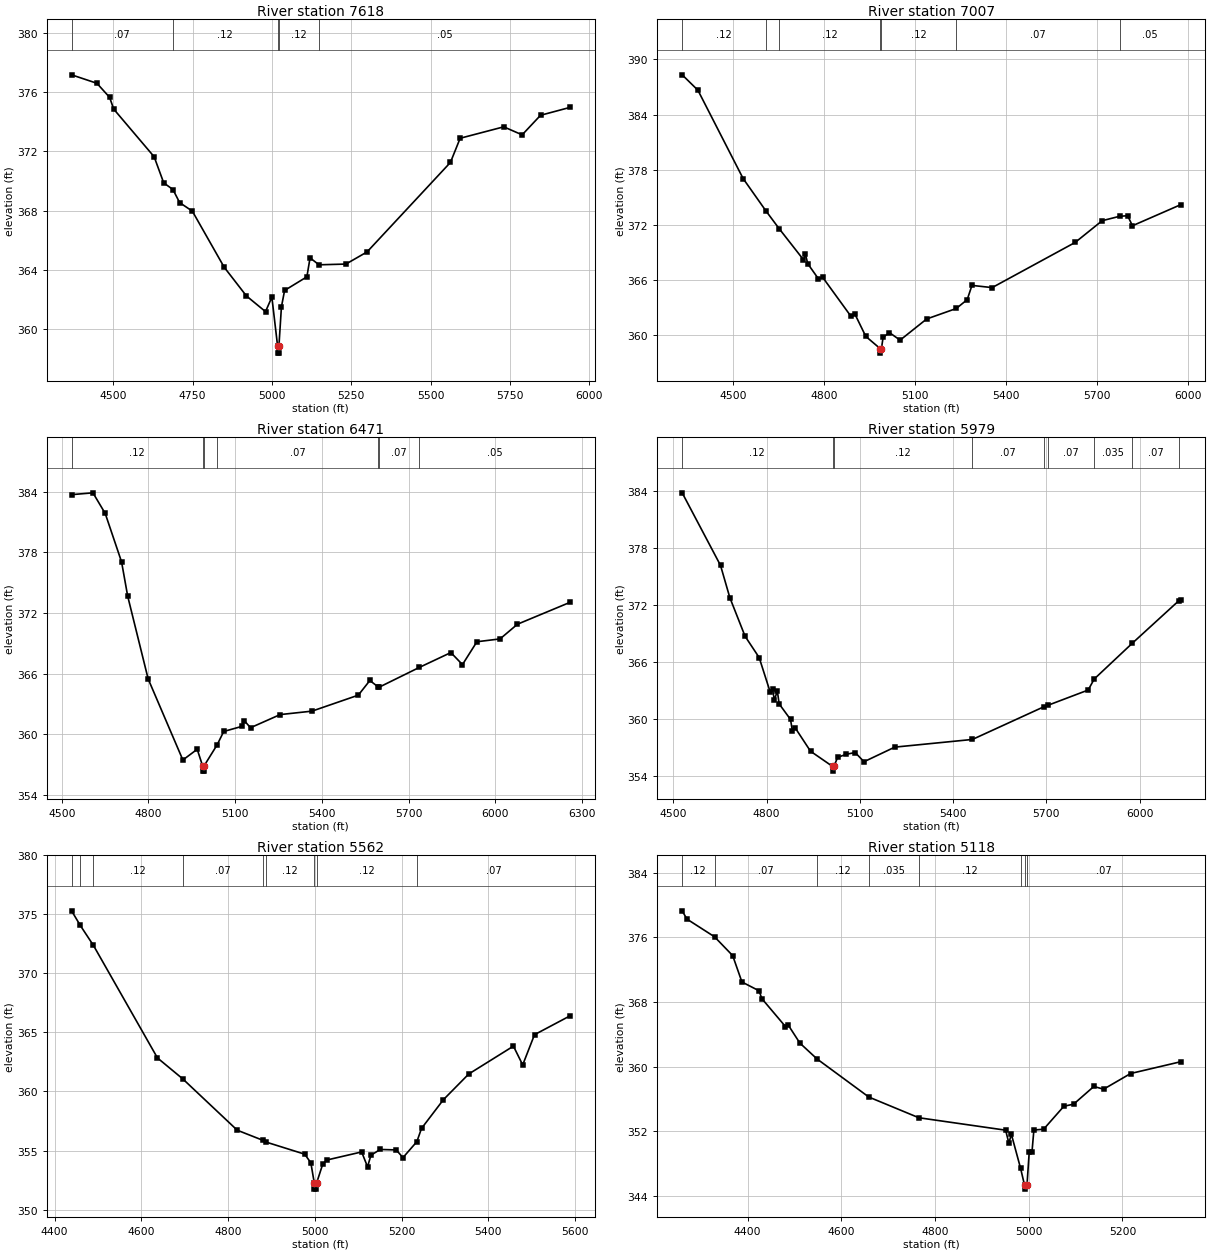
Type RM Length L Ch R = 1,7618,611,611,611
BEGIN DESCRIPTION:
Stream0565 15.0
END DESCRIPTION:
XS GIS Cut Line= 3
      2379104.52     13694411.33      2378242.25     13694468.81
      2377871.78     13695069.24
#Sta/Elev= 30
  4369.1  377.17  4448.8  376.60  4488.9  375.65  4501.7  374.86  4629.2  371.64
  4659.3  369.88  4688.4  369.43  4709.4  368.55  4749.5  367.97  4849.7  364.19
  4919.8  362.25  4980.0  361.19  5000.0  362.17  5017.9  358.89  5018.2  358.39
  5022.0  358.39  5022.3  358.89  5030.1  361.51  5040.1  362.62  5110.3  363.54
  5120.3  364.82  5148.4  364.35  5233.3  364.40  5299.9  365.22  5562.5  371.26
  5593.1  372.89  5730.4  373.66  5788.4  373.12  5846.3  374.44  5938.8  374.97
#Mann=5,-1,0
  4369.1    0.07       0  4688.4    0.12       0  5017.9    0.05       0
  5022.3    0.12       0  5148.4    0.05       0
Bank Sta=5017.9,5022.3
Exp/Cntr=0.3,0.1

Type RM Length L Ch R = 1,7007,536,536,536
BEGIN DESCRIPTION:
Stream0565 14.0
END DESCRIPTION:
XS GIS Cut Line= 3
      2378548.83     13693555.42      2378069.79     13694123.89
      2377859.00     13694998.97
#Sta/Elev= 30
  4331.9  388.32  4383.7  386.65  4532.9  377.05  4608.4  373.52  4651.6  371.61
  4731.9  368.23  4738.4  368.80  4746.2  367.79  4781.3  366.15  4795.6  366.30
  4887.9  362.11  4902.2  362.28  4937.4  359.90  4984.6  358.58  4984.9  358.08
  4989.1  358.58  4994.6  359.80  5015.4  360.31  5050.6  359.49  5138.2  361.79
  5235.9  362.93  5271.9  363.89  5287.6  365.44  5354.2  365.20  5628.1  370.11
  5717.1  372.47  5774.7  372.95  5801.0  373.01  5817.0  371.92  5975.4  374.20
#Mann=7,-1,0
  4331.9    0.12       0  4608.4    0.07       0  4651.6    0.12       0
  4984.6    0.05       0  4989.1    0.12       0  5235.9    0.07       0
  5774.7    0.05       0
Bank Sta=4984.6,4989.1
Exp/Cntr=0.3,0.1

Type RM Length L Ch R = 1,6471,492,492,492
BEGIN DESCRIPTION:
Stream0565 13.0
END DESCRIPTION:
XS GIS Cut Line= 3
      2378057.01     13693472.37      2377629.05     13693893.94
      2377680.07     13695016.45
#Sta/Elev= 30
  4533.9  383.69  4607.8  383.87  4650.3  381.83  4706.9  377.04  4728.1  373.65
  4798.8  365.48  4919.0  357.46  4968.6  358.52  4987.5  356.86  4987.8  356.36
  4991.7  356.36  4992.0  356.86  5037.8  358.97  5060.4  360.28  5124.1  360.79
  5131.2  361.36  5153.1  360.65  5255.8  361.95  5365.9  362.29  5526.1  363.87
  5566.1  365.32  5595.7  364.66  5597.7  364.65  5737.1  366.61  5846.4  368.08
  5886.5  366.89  5936.5  369.15  6016.6  369.43  6076.7  370.88  6258.3  373.04
#Mann=7,-1,0
  4533.9    0.12       0  4987.5    0.05       0  4992.0    0.12       0
  5037.8    0.07       0  5595.7    0.05       0  5597.7    0.07       0
  5737.1    0.05       0
Bank Sta=4987.5,4992
Exp/Cntr=0.3,0.1

Type RM Length L Ch R = 1,5979,417,417,417
BEGIN DESCRIPTION:
Stream0565 12.0
END DESCRIPTION:
XS GIS Cut Line= 3
      2377775.03     13693224.98      2377375.00     13693475.00
      2376575.00     13694275.00
#Sta/Elev= 30
  4528.5  383.82  4651.8  376.17  4681.8  372.77  4730.8  368.70  4776.2  366.45
  4811.6  362.82  4819.2  363.13  4825.1  361.95  4834.5  362.96  4840.4  361.57
  4877.0  359.93  4882.9  358.75  4892.3  359.03  4941.3  356.58  5012.1  354.98
  5012.4  354.48  5016.7  354.98  5028.5  355.93  5056.8  356.26  5085.1  356.44
  5113.4  355.47  5212.4  357.01  5462.2  357.82  5691.0  361.25  5705.1  361.42
  5834.6  363.03  5854.0  364.19  5975.8  367.94  6126.1  372.44  6131.6  372.53
#Mann=9,-1,0
  4528.5    0.12       0  5012.1    0.05       0  5016.7    0.12       0
  5462.2    0.07       0  5691.0   0.035       0  5705.1    0.07       0
  5854.0   0.035       0  5975.8    0.07       0  6126.1    0.05       0
Bank Sta=5012.1,5016.7
Exp/Cntr=0.3,0.1

Type RM Length L Ch R = 1,5562,444,444,444
BEGIN DESCRIPTION:
Stream0565 11.0
END DESCRIPTION:
XS GIS Cut Line= 3
      2377425.02     13692874.98      2377025.00     13693275.00
      2376525.00     13693575.00
#Sta/Elev= 30
  4439.1  375.30  4459.2  374.06  4489.5  372.37  4637.1  362.84  4695.3  361.07
  4821.0  356.72  4879.8  355.87  4887.9  355.71  4976.5  354.69  4990.7  353.96
  4998.7  352.23  4999.1  351.73  5003.4  351.73  5003.8  352.23  5018.4  353.88
  5028.1  354.20  5107.8  354.88  5121.4  353.62  5129.2  354.60  5150.6  355.09
  5187.5  355.05  5203.1  354.40  5235.1  355.75  5245.8  356.87  5296.4  359.31
  5354.7  361.48  5457.7  363.84  5479.1  362.25  5506.3  364.81  5587.9  366.40
#Mann=9,-1,0
  4439.1    0.12       0  4459.2    0.07       0  4489.5    0.12       0
  4695.3    0.07       0  4879.8   0.035       0  4887.9    0.12       0
  4998.7    0.05       0  5003.8    0.12       0  5235.1    0.07       0
Bank Sta=4998.7,5003.8
Exp/Cntr=0.3,0.1

Type RM Length L Ch R = 1,5118,439,439,439
BEGIN DESCRIPTION:
Stream0565 10.0
END DESCRIPTION:
XS GIS Cut Line= 3
      2377425.05     13692724.98      2376725.00     13692975.00
      2376475.01     13693174.99
#Sta/Elev= 30
  4260.4  379.29  4270.5  378.27  4329.4  376.08  4368.2  373.75  4387.9  370.49
  4424.5  369.40  4430.3  368.44  4480.8  364.98  4486.1  365.22  4511.6  362.93
  4548.2  360.97  4658.7  356.26  4765.4  353.70  4950.7  352.16  4957.6  350.56
  4962.9  351.66  4982.6  347.45  4991.0  345.37  4991.5  344.87  4996.3  345.37
  5001.1  349.52  5007.0  349.52  5011.0  352.18  5031.8  352.28  5075.0  355.12
  5095.8  355.38  5139.0  357.57  5159.8  357.23  5217.5  359.17  5323.9  360.62
#Mann=8,-1,0
  4260.4    0.12       0  4329.4    0.07       0  4548.2    0.12       0
  4658.7   0.035       0  4765.4    0.12       0  4982.6    0.07       0
  4991.0    0.05       0  4996.3    0.07       0
Bank Sta=4991,4996.3
Exp/Cntr=0.3,0.1

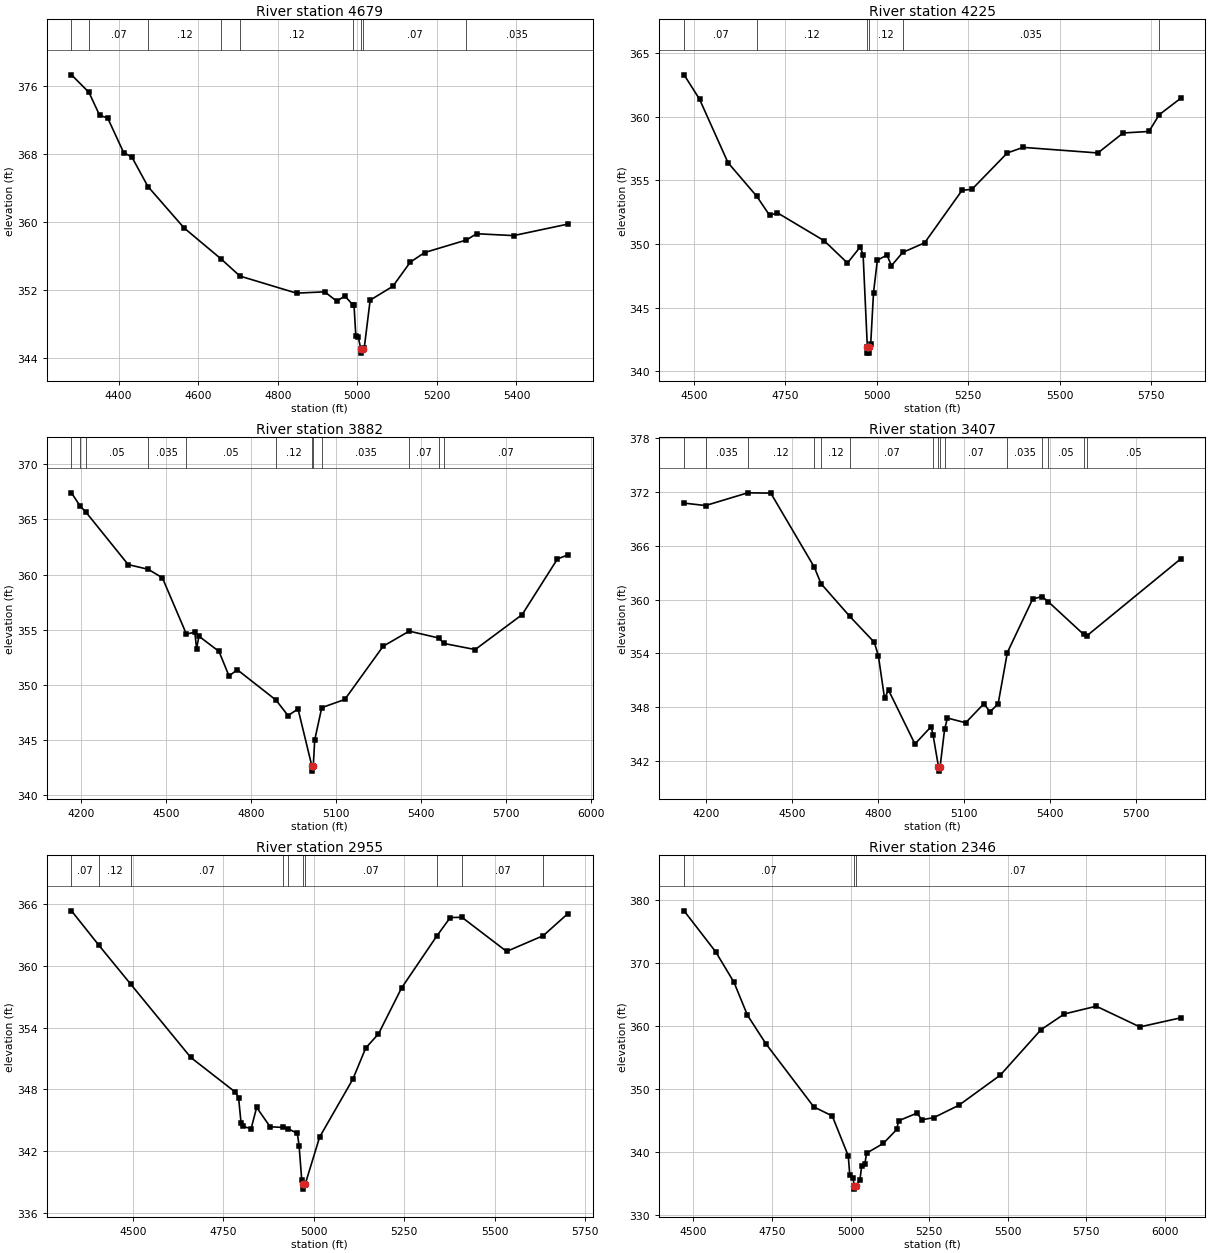
Type RM Length L Ch R = 1,4679,454,454,454
BEGIN DESCRIPTION:
Stream0565 9.0
END DESCRIPTION:
XS GIS Cut Line= 3
      2377374.97     13692675.00      2376675.00     13692575.00
      2376225.00     13692875.00
#Sta/Elev= 30
  4281.7  377.34  4325.6  375.27  4352.4  372.56  4372.6  372.25  4413.0  368.15
  4433.2  367.66  4473.8  364.17  4564.5  359.29  4657.8  355.62  4704.9  353.61
  4847.4  351.59  4918.1  351.75  4948.4  350.64  4968.6  351.26  4989.7  350.17
  4991.8  350.17  4996.3  346.56  5002.3  346.47  5008.7  345.02  5009.1  344.52
  5014.0  345.02  5017.3  345.07  5032.3  350.77  5089.4  352.40  5133.0  355.24
  5169.1  356.38  5274.2  357.86  5299.8  358.60  5392.9  358.38  5529.6  359.74
#Mann=9,-1,0
  4281.7    0.12       0  4325.6    0.07       0  4473.8    0.12       0
  4657.8   0.035       0  4704.9    0.12       0  4989.7    0.07       0
  5008.7    0.05       0  5014.0    0.07       0  5274.2   0.035       0
Bank Sta=5008.7,5014
Exp/Cntr=0.3,0.1

Type RM Length L Ch R = 1,4225,343,343,343
BEGIN DESCRIPTION:
Stream0565 8.0
END DESCRIPTION:
XS GIS Cut Line= 3
      2376874.99     13691875.01      2376475.00     13692225.00
      2376064.73     13692941.11
#Sta/Elev= 30
  4473.5  363.30  4515.7  361.39  4593.5  356.40  4672.3  353.75  4707.4  352.25
  4728.3  352.46  4856.5  350.26  4920.0  348.51  4955.2  349.79  4962.8  349.12
  4974.3  341.93  4974.7  341.43  4979.3  341.43  4979.7  341.93  4983.6  342.18
  4991.2  346.19  5001.7  348.73  5028.0  349.14  5040.2  348.30  5070.8  349.34
  5130.9  350.10  5233.0  354.22  5260.4  354.31  5356.8  357.16  5399.9  357.60
  5604.3  357.16  5673.3  358.73  5743.8  358.85  5772.1  360.17  5830.3  361.45
#Mann=6,-1,0
  4473.5    0.07       0  4672.3    0.12       0  4974.3    0.05       0
  4979.7    0.12       0  5070.8   0.035       0  5772.1    0.07       0
Bank Sta=4974.3,4979.7
Exp/Cntr=0.3,0.1

Type RM Length L Ch R = 1,3882,475,475,475
BEGIN DESCRIPTION:
Stream0565 7.0
END DESCRIPTION:
XS GIS Cut Line= 3
      2376702.84     13691383.66      2376198.24     13692054.33
      2375846.93     13692897.47
#Sta/Elev= 30
  4165.1  367.42  4194.9  366.24  4215.7  365.68  4365.1  360.91  4436.1  360.48
  4485.9  359.71  4570.6  354.61  4600.4  354.77  4606.7  353.28  4615.0  354.41
  4685.8  353.03  4721.2  350.80  4750.3  351.37  4887.2  348.61  4929.4  347.21
  4964.8  347.81  5013.2  342.67  5013.7  342.17  5018.7  342.67  5023.6  344.99
  5048.5  347.93  5129.8  348.67  5265.2  353.50  5357.2  354.87  5463.0  354.24
  5478.3  353.76  5590.1  353.20  5755.9  356.37  5880.5  361.42  5917.8  361.79
#Mann=12,-1,0
  4165.1    0.05       0  4194.9    0.07       0  4215.7    0.05       0
  4436.1   0.035       0  4570.6    0.05       0  4887.2    0.12       0
  5013.2    0.05       0  5018.7    0.12       0  5048.5   0.035       0
  5357.2    0.07       0  5463.0   0.035       0  5478.3    0.07       0
Bank Sta=5013.2,5018.7
Exp/Cntr=0.3,0.1

Type RM Length L Ch R = 1,3407,452,452,452
BEGIN DESCRIPTION:
Stream0565 6.0
END DESCRIPTION:
XS GIS Cut Line= 3
      2376434.56     13691147.32      2375853.32     13691760.50
      2375233.72     13692392.87
#Sta/Elev= 30
  4124.8  370.77  4199.8  370.50  4346.5  371.92  4426.9  371.89  4578.4  363.63
  4602.2  361.77  4702.6  358.11  4787.7  355.23  4801.9  353.72  4823.3  349.00
  4837.4  349.88  4929.3  343.87  4985.8  345.81  4992.5  344.87  5011.3  341.34
  5011.7  340.84  5017.0  341.34  5032.7  345.51  5042.4  346.77  5106.0  346.24
  5169.7  348.37  5190.9  347.46  5219.2  348.35  5251.3  354.08  5339.5  360.05
  5372.3  360.34  5394.6  359.74  5517.2  356.11  5528.7  355.96  5855.0  364.53
#Mann=15,-1,0
  4124.8    0.05       0  4199.8   0.035       0  4346.5    0.12       0
  4578.4    0.07       0  4602.2    0.12       0  4702.6    0.07       0
  4992.5    0.12       0  5011.3    0.05       0  5017.0    0.12       0
  5032.7    0.07       0  5251.3   0.035       0  5372.3    0.07       0
  5394.6    0.05       0  5517.2    0.07       0  5528.7    0.05       0
Bank Sta=5011.3,5017
Exp/Cntr=0.3,0.1

Type RM Length L Ch R = 1,2955,609,609,609
BEGIN DESCRIPTION:
Stream0565 5.0
END DESCRIPTION:
XS GIS Cut Line= 3
      2376153.53     13691083.42      2375616.98     13691396.41
      2375074.01     13691913.83
#Sta/Elev= 30
  4330.8  365.33  4406.6  361.98  4495.1  358.18  4660.2  351.10  4783.4  347.73
  4792.2  347.20  4799.1  344.74  4804.9  344.40  4826.9  344.19  4842.1  346.25
  4879.4  344.37  4914.3  344.31  4929.2  344.18  4954.6  343.73  4959.4  342.51
  4966.6  339.22  4970.7  338.82  4971.1  338.32  4976.4  338.82  5016.0  343.37
  5107.8  348.99  5143.4  352.02  5178.6  353.39  5242.5  357.85  5339.5  362.88
  5376.8  364.68  5409.1  364.70  5532.5  361.39  5633.6  362.92  5702.0  365.07
#Mann=10,-1,0
  4330.8    0.07       0  4406.6    0.12       0  4495.1    0.07       0
  4914.3   0.035       0  4929.2    0.07       0  4970.7    0.05       0
  4976.4    0.07       0  5339.5    0.05       0  5409.1    0.07       0
  5633.6    0.05       0
Bank Sta=4970.7,4976.4
Exp/Cntr=0.3,0.1

Type RM Length L Ch R = 1,2346,412,412,412
BEGIN DESCRIPTION:
Stream0565 4.0
END DESCRIPTION:
XS GIS Cut Line= 3
      2376076.86     13690597.98      2375625.00     13690875.00
      2375093.21     13691779.65
#Sta/Elev= 30
  4470.5  378.35  4571.2  371.83  4629.2  367.00  4672.1  361.76  4730.7  357.23
  4883.2  347.19  4941.9  345.75  4992.8  339.41  4997.6  336.36  5008.4  335.94
  5011.3  334.62  5011.8  334.12  5017.1  334.62  5029.8  335.53  5035.6  337.85
  5045.5  338.13  5051.3  339.84  5104.1  341.38  5147.0  343.60  5152.8  344.98
  5211.4  346.20  5227.1  345.15  5264.2  345.47  5344.3  347.44  5476.1  352.22
  5605.9  359.46  5680.2  361.96  5781.7  363.19  5920.4  359.90  6049.9  361.34
#Mann=3,-1,0
  4470.5    0.07       0  5011.3    0.05       0  5017.1    0.07       0
Bank Sta=5011.3,5017.1
Exp/Cntr=0.3,0.1

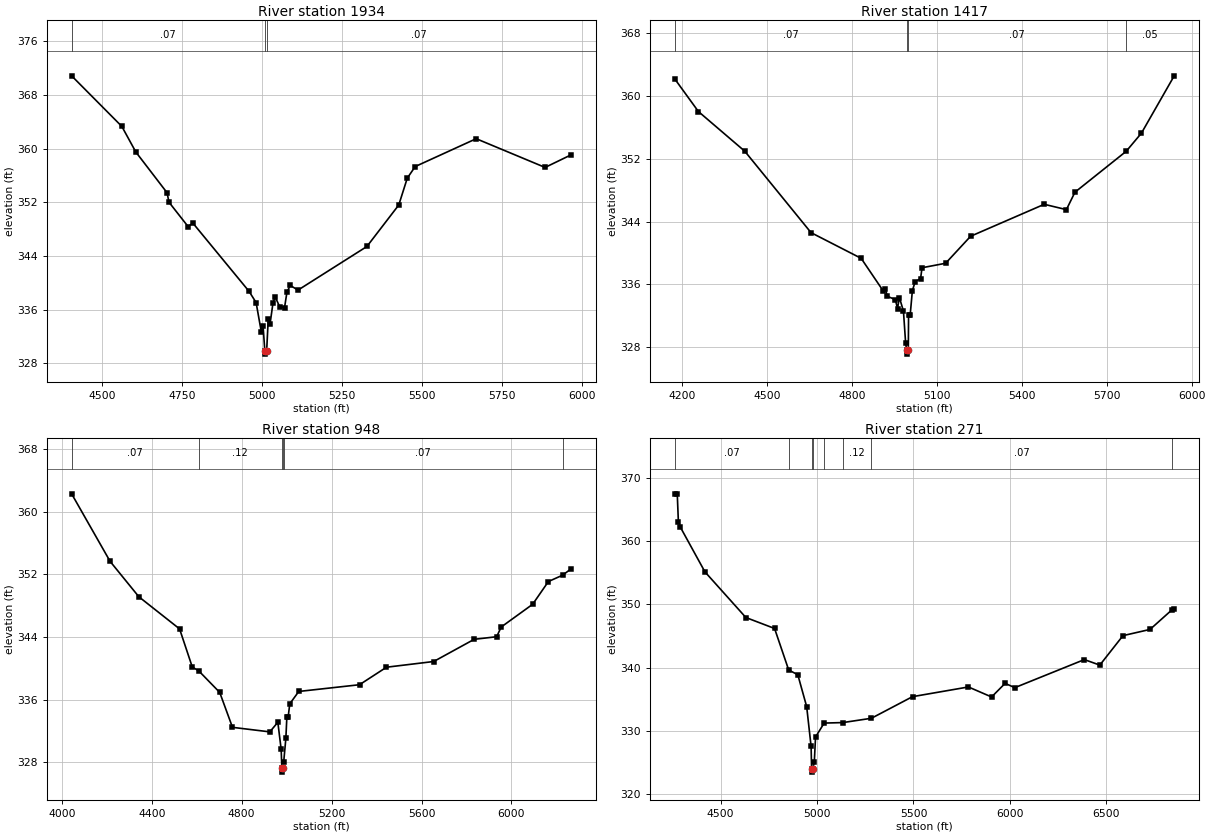
Type RM Length L Ch R = 1,1934,517,517,517
BEGIN DESCRIPTION:
Stream0565 3.0
END DESCRIPTION:
XS GIS Cut Line= 3
      2375585.02     13690201.97      2375272.05     13690776.82
      2375061.25     13691658.34
#Sta/Elev= 30
  4404.7  370.84  4561.7  363.30  4605.4  359.49  4703.2  353.41  4708.9  352.02
  4768.8  348.38  4783.9  348.89  4959.7  338.71  4981.5  337.05  4997.7  332.70
  5003.3  333.54  5008.7  329.87  5009.2  329.37  5014.5  329.87  5019.5  334.66
  5025.2  333.91  5034.4  337.05  5041.3  337.89  5055.3  336.41  5070.4  336.31
  5077.9  338.60  5088.2  339.61  5112.5  338.91  5327.9  345.41  5427.5  351.59
  5454.1  355.59  5478.9  357.32  5669.6  361.47  5885.0  357.19  5965.6  359.05
#Mann=3,-1,0
  4404.7    0.07       0  5008.7    0.05       0  5014.5    0.07       0
Bank Sta=5008.7,5014.5
Exp/Cntr=0.3,0.1

Type RM Length L Ch R = 1,1417,469,469,469
BEGIN DESCRIPTION:
Stream0565 2.0
END DESCRIPTION:
XS GIS Cut Line= 3
      2375361.49     13690144.44      2374825.00     13690775.00
      2374716.33     13691703.06
#Sta/Elev= 30
  4176.2  362.14  4259.0  358.02  4422.6  352.97  4656.5  342.60  4833.4  339.33
  4912.2  335.13  4919.0  335.43  4925.6  334.50  4954.1  334.07  4961.8  332.94
  4968.4  334.34  4982.7  332.61  4990.4  328.54  4994.1  327.63  4994.5  327.13
  4999.9  327.63  5000.8  332.17  5006.6  332.17  5014.2  335.21  5024.2  336.37
  5043.2  336.75  5048.3  338.13  5131.5  338.70  5219.8  342.14  5479.7  346.21
  5557.9  345.53  5588.1  347.75  5769.0  352.96  5822.8  355.27  5938.5  362.57
#Mann=4,-1,0
  4176.2    0.07       0  4994.1    0.05       0  4999.9    0.07       0
  5769.0    0.05       0
Bank Sta=4994.1,4999.9
Exp/Cntr=0.3,0.1

Type RM Length L Ch R = 1,948,677,677,677
BEGIN DESCRIPTION:
Stream0565 1.0
END DESCRIPTION:
XS GIS Cut Line= 3
      2375259.28     13689920.89      2374475.00     13690475.00
      2374448.06     13691734.94
#Sta/Elev= 30
  4043.7  362.31  4214.8  353.67  4342.8  349.14  4523.9  345.03  4580.5  340.14
  4608.2  339.69  4702.3  336.91  4759.1  332.44  4925.2  331.86  4960.9  333.09
  4975.7  329.61  4978.8  327.21  4979.3  326.71  4984.7  327.21  4986.9  327.99
  4996.6  331.05  5000.9  333.71  5006.5  333.71  5014.0  335.45  5054.0  337.03
  5324.1  337.89  5444.1  340.13  5654.1  340.86  5834.2  343.70  5934.2  344.03
  5954.2  345.27  6094.2  348.18  6164.2  351.09  6227.2  351.90  6264.2  352.69
#Mann=6,-1,0
  4043.7    0.07       0  4608.2    0.12       0  4978.8    0.05       0
  4984.7    0.12       0  4986.9    0.07       0  6227.2    0.05       0
Bank Sta=4978.8,4984.7
Exp/Cntr=0.3,0.1

Type RM Length L Ch R = 1,271,0,0,0
BEGIN DESCRIPTION:
XS7085
END DESCRIPTION:
XS GIS Cut Line= 4
      2375220.98     13689595.11      2374499.16     13689927.28
      2374307.53     13690559.65      2374365.02     13691690.14
#Sta/Elev= 30
  4264.0  367.45  4275.9  367.41  4281.6  363.07  4292.6  362.15  4419.2  355.14
  4631.4  347.93  4780.2  346.20  4853.3  339.65  4900.6  338.90  4946.5  333.87
  4969.5  327.58  4972.1  324.03  4972.6  323.53  4978.0  324.03  4986.1  325.14
  4992.5  329.07  5037.1  331.27  5134.0  331.35  5282.1  332.03  5495.1  335.44
  5784.8  336.97  5904.9  335.39  5975.0  337.54  6025.1  336.86  6385.6  341.29
  6465.7  340.42  6585.8  345.07  6726.0  346.05  6837.6  349.09  6851.3  349.23
#Mann=8,-1,0
  4264.0    0.07       0  4853.3    0.12       0  4972.1    0.05       0
  4978.0    0.12       0  5037.1     0.1       0  5134.0    0.12       0
  5282.1    0.07       0  6837.6    0.05       0
Bank Sta=4972.1,4978
Exp/Cntr=0.3,0.1

Chan Stop Cuts=-1