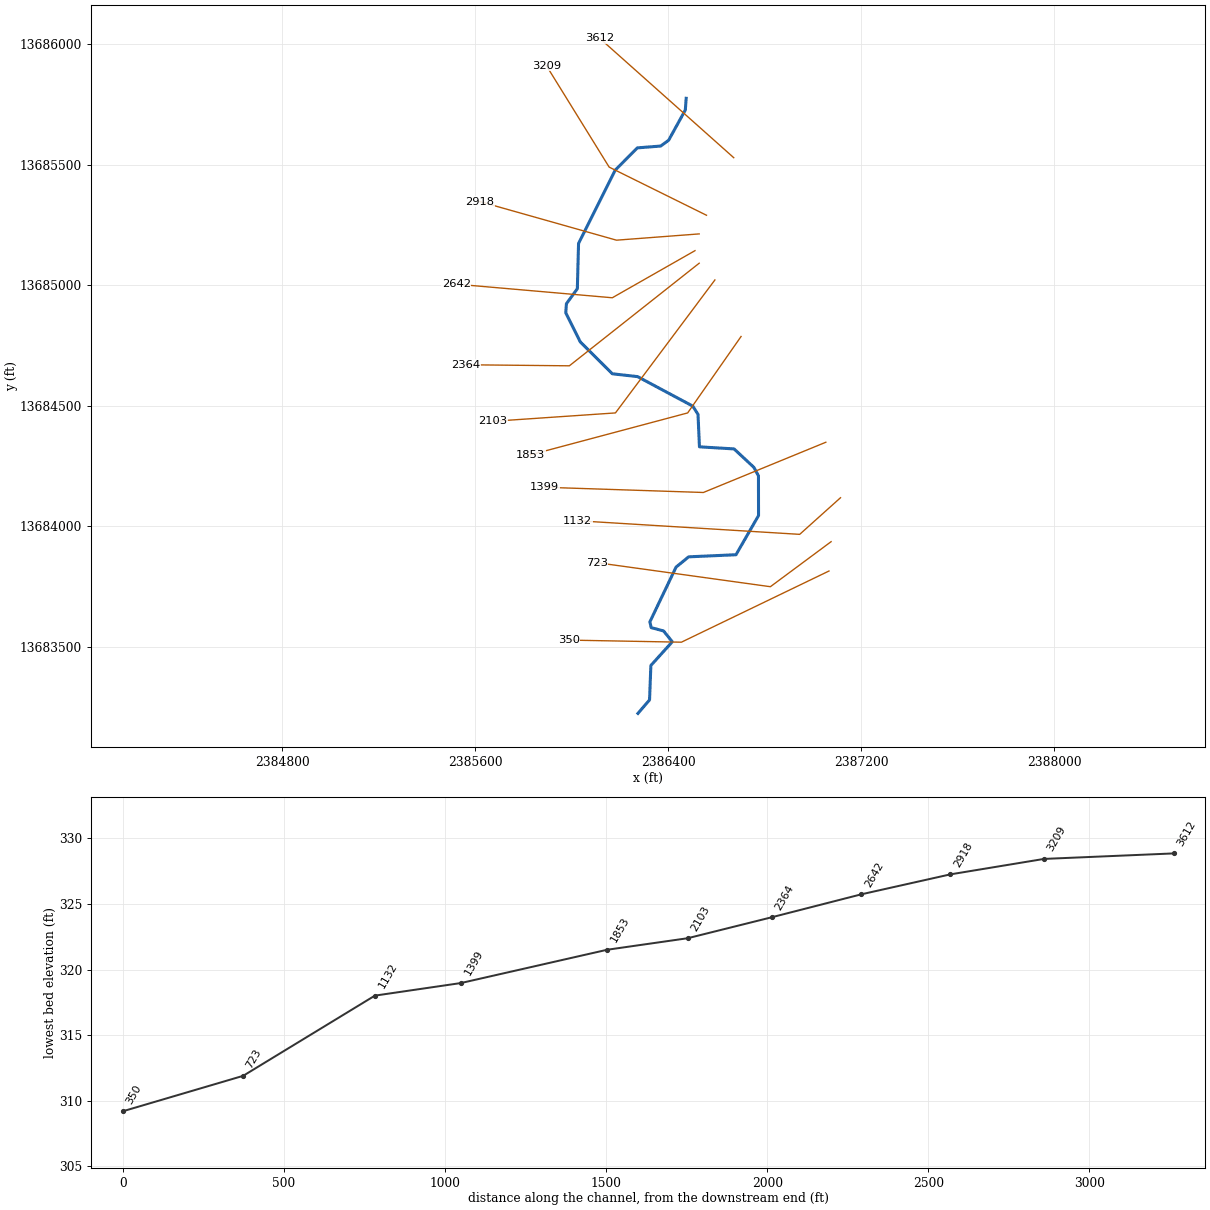
--- Stream0568.prj (project) ---

Proj Title=Stream0568 Base Level Engineering
Current Plan=p01
Default Exp/Contr=0.3,0.1
English Units
Geom File=g01
Flow File=f01
Plan File=p01
BEGIN DESCRIPTION:
Stream0568
END DESCRIPTION:

--- Stream0568.p01 (plan) ---

Plan Title=Multiple Run
Short Identifier=Multiple
Geom File=g01
Flow File=f01
Subcritical Flow
K Sum by GR= 0
Std Step Tol= 0.01
Critical Tol= 0.01
Num of Std Step Trials= 20
Max Error Tol= 0.3
Flow Tol Ratio= 0.001
Split Flow NTrial= 30
Split Flow Tol= 0.02
Split Flow Ratio= 0.02
Log Output Level= 0
Friction Slope Method= 1
Unsteady Friction Slope Method= 2
Unsteady Bridges Friction Slope Method= 1
Parabolic Critical Depth
Global Vel Dist=  1 , 1 , 1
Global Log Level= 0
CheckData=True
Encroach Param= -1, 0, 0, 0
BEGIN DESCRIPTION:
Multiple Run
END DESCRIPTION:

--- Stream0568.f01 (steady flow) ---

Flow Title=Multiple
Number of Profiles=7
Profile Names=10-year,25-year,50-year,1pct_min,100-year,1pct_plu,500-year
River Rch & RM= Stream0568,Reach-1,3612
     594     955    1278     829    1654    3301    2745
River Rch & RM= Stream0568,Reach-1,2364
     623    1003    1345     873    1742    3476    2896
Boundary for River Rch & Prof#=Stream0568,Reach-1,1
Up Type=0
Dn Type=3
Dn Slope=0.005
Boundary for River Rch & Prof#=Stream0568,Reach-1,2
Up Type=0
Dn Type=3
Dn Slope=0.005
Boundary for River Rch & Prof#=Stream0568,Reach-1,3
Up Type=0
Dn Type=3
Dn Slope=0.005
Boundary for River Rch & Prof#=Stream0568,Reach-1,4
Up Type=0
Dn Type=3
Dn Slope=0.005
Boundary for River Rch & Prof#=Stream0568,Reach-1,5
Up Type=0
Dn Type=3
Dn Slope=0.005
Boundary for River Rch & Prof#=Stream0568,Reach-1,6
Up Type=0
Dn Type=3
Dn Slope=0.005
Boundary for River Rch & Prof#=Stream0568,Reach-1,7
Up Type=0
Dn Type=3
Dn Slope=0.005

--- Stream0568.g01 (geometry) ---

Geom Title=Existing Conditions

River Reach=Stream0568,Reach-1
Reach XY= 30
      2386475.00     13685775.00      2386471.40     13685726.49
      2386402.20     13685601.04      2386369.29     13685577.08
      2386272.56     13685569.48      2386180.83     13685477.31
      2386028.75     13685173.45      2386023.76     13684985.50
      2385978.37     13684923.26      2385975.75     13684885.68
      2386035.76     13684765.32      2386168.83     13684632.86
      2386273.41     13684621.17      2386502.30     13684498.90
      2386524.00     13684464.70      2386530.01     13684330.01
      2386673.54     13684321.46      2386755.41     13684245.21
      2386774.62     13684209.85      2386774.94     13684045.03
      2386681.48     13683882.69      2386485.28     13683874.01
      2386433.00     13683831.39      2386324.54     13683604.54
      2386329.83     13683580.61      2386381.31     13683566.72
      2386417.45     13683521.85      2386328.56     13683423.53
      2386323.09     13683280.79      2386275.00     13683225.00

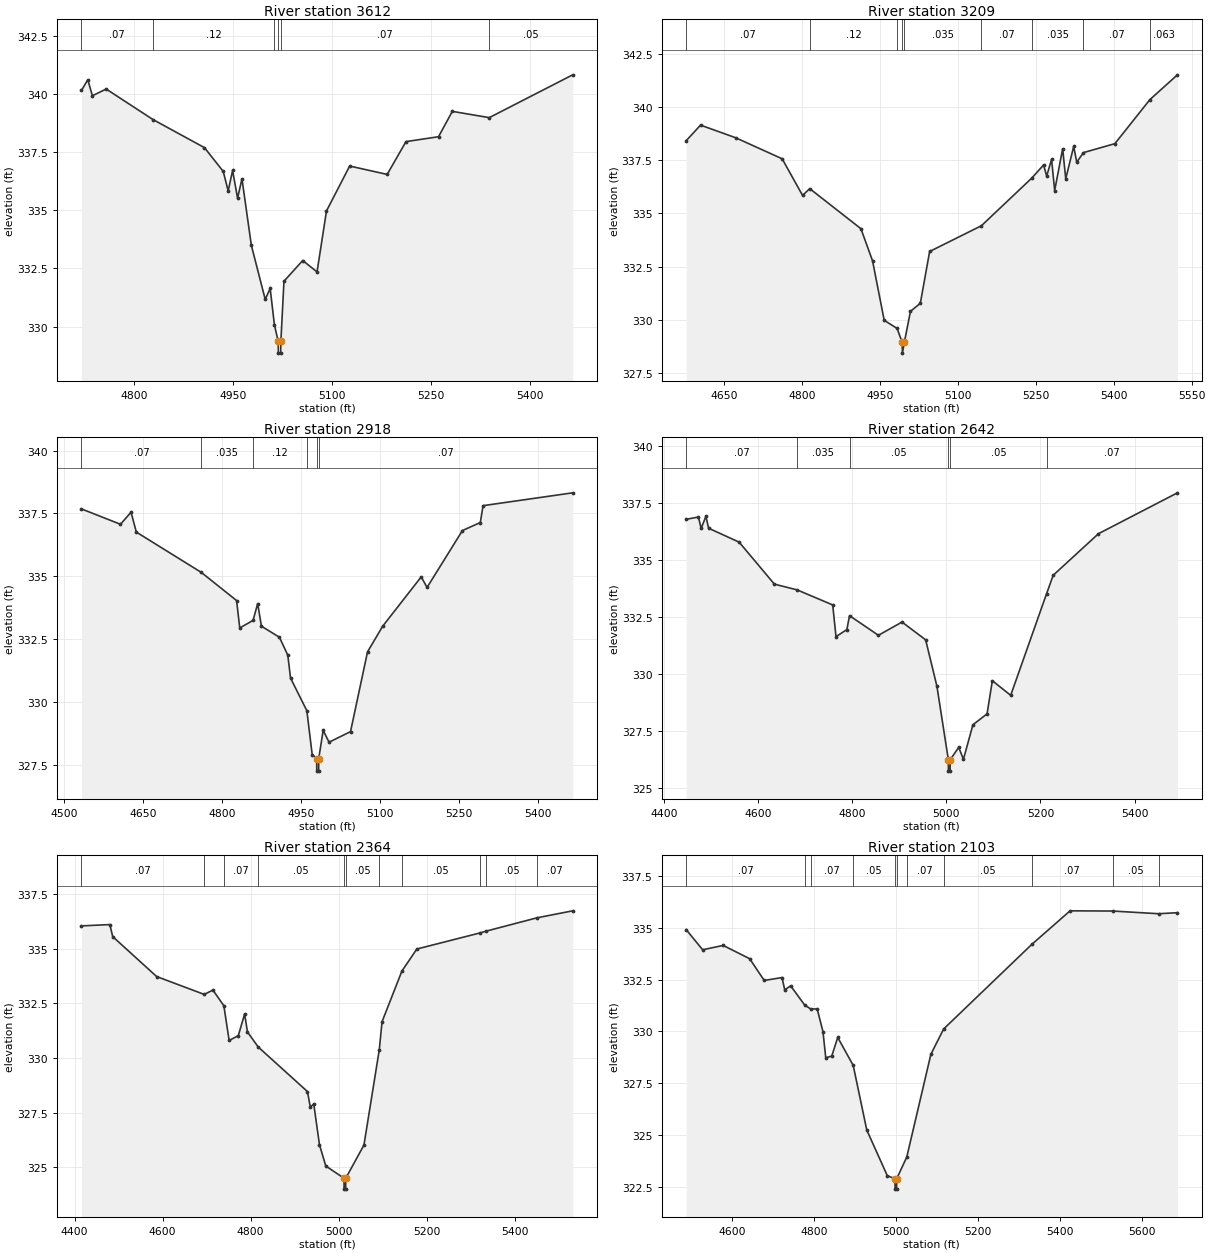
Type RM Length L Ch R = 1,3612,403,403,403
BEGIN DESCRIPTION:
XS7098
END DESCRIPTION:
XS GIS Cut Line= 2
      2386672.14     13685528.81      2386116.55     13686023.64
#Sta/Elev= 30
  4720.5  340.15  4730.1  340.61  4737.0  339.92  4757.9  340.21  4828.7  338.90
  4906.8  337.69  4935.2  336.67  4942.7  335.83  4949.4  336.71  4956.9  335.52
  4963.6  336.35  4977.8  333.49  4998.8  331.17  5006.3  331.64  5012.7  330.08
  5018.5  329.36  5018.7  328.86  5022.2  328.86  5022.5  329.36  5027.2  331.95
  5055.6  332.84  5077.3  332.35  5091.6  334.97  5126.7  336.90  5183.5  336.54
  5212.0  337.95  5261.3  338.16  5282.2  339.25  5338.1  338.98  5464.5  340.82
#Mann=6,-1,0
  4720.5    0.07       0  4828.7    0.12       0  5012.7    0.07       0
  5018.5    0.05       0  5022.5    0.07       0  5338.1    0.05       0
Bank Sta=5018.5,5022.5
Exp/Cntr=0.3,0.1

Type RM Length L Ch R = 1,3209,291,291,291
BEGIN DESCRIPTION:
XS7097
END DESCRIPTION:
XS GIS Cut Line= 3
      2386559.26     13685290.12      2386155.64     13685489.76
      2385895.45     13685910.40
#Sta/Elev= 30
  4577.8  338.41  4605.3  339.14  4672.6  338.55  4762.3  337.56  4801.6  335.84
  4815.3  336.16  4913.8  334.28  4936.2  332.77  4958.6  329.98  4983.4  329.60
  4993.3  328.94  4993.6  328.44  4997.3  328.94  5009.1  330.40  5028.1  330.78
  5046.0  333.21  5145.7  334.42  5242.3  336.65  5265.2  337.27  5271.1  336.75
  5280.6  337.53  5286.5  336.07  5301.9  338.03  5307.8  336.62  5323.1  338.14
  5329.0  337.40  5341.9  337.85  5402.3  338.27  5469.8  340.34  5522.7  341.50
#Mann=9,-1,0
  4577.8    0.07       0  4815.3    0.12       0  4983.4   0.035       0
  4993.3   0.035       0  4997.3   0.035       0  5145.7    0.07       0
  5242.3   0.035       0  5341.9    0.07       0  5469.8   0.063       0
Bank Sta=4993.3,4997.3
Exp/Cntr=0.3,0.1

Type RM Length L Ch R = 1,2918,276,276,276
BEGIN DESCRIPTION:
XS7096
END DESCRIPTION:
XS GIS Cut Line= 3
      2386528.88     13685212.85      2386186.02     13685186.81
      2385618.76     13685347.02
#Sta/Elev= 30
  4532.8  337.68  4606.9  337.07  4627.0  337.55  4637.0  336.76  4760.3  335.16
  4827.5  334.04  4833.5  332.95  4858.8  333.25  4867.6  333.92  4874.7  333.02
  4908.9  332.58  4924.8  331.87  4930.0  330.96  4961.0  329.66  4971.2  327.91
  4979.6  327.76  4979.9  327.26  4983.4  327.26  4983.6  327.76  4992.0  328.88
  5003.2  328.41  5044.0  328.83  5076.3  332.00  5105.1  333.02  5178.3  334.98
  5189.4  334.56  5256.6  336.82  5290.6  337.14  5295.8  337.81  5466.1  338.32
#Mann=6,-1,0
  4532.8    0.07       0  4760.3   0.035       0  4858.8    0.12       0
  4961.0    0.07       0  4979.6    0.05       0  4983.6    0.07       0
Bank Sta=4979.6,4983.6
Exp/Cntr=0.3,0.1

Type RM Length L Ch R = 1,2642,278,278,278
BEGIN DESCRIPTION:
XS7095
END DESCRIPTION:
XS GIS Cut Line= 3
      2386511.52     13685143.39      2386168.66     13684948.09
      2385522.00     13685004.51
#Sta/Elev= 30
  4447.3  336.77  4473.2  336.87  4479.0  336.37  4489.1  336.90  4494.8  336.38
  4559.7  335.77  4634.6  333.93  4682.7  333.68  4758.5  333.02  4765.5  331.63
  4788.6  331.94  4794.2  332.55  4855.6  331.69  4905.8  332.27  4956.0  331.49
  4980.0  329.45  5004.2  326.24  5004.4  325.74  5007.9  325.74  5008.2  326.24
  5026.2  326.78  5036.3  326.26  5056.4  327.77  5086.5  328.25  5097.7  329.70
  5136.7  329.06  5212.9  333.51  5227.0  334.32  5323.2  336.14  5491.0  337.93
#Mann=6,-1,0
  4447.3    0.07       0  4682.7   0.035       0  4794.2    0.05       0
  5004.2    0.05       0  5008.2    0.05       0  5212.9    0.07       0
Bank Sta=5004.2,5008.2
Exp/Cntr=0.3,0.1

Type RM Length L Ch R = 1,2364,261,261,261
BEGIN DESCRIPTION:
XS7094
END DESCRIPTION:
XS GIS Cut Line= 3
      2386528.90     13685091.32      2385990.71     13684665.97
      2385561.02     13684670.31
#Sta/Elev= 30
  4415.8  336.05  4480.3  336.11  4486.7  335.56  4586.5  333.73  4694.7  332.91
  4714.3  333.11  4739.2  332.39  4751.2  330.80  4772.0  331.02  4786.4  332.02
  4792.8  331.19  4817.3  330.50  4929.1  328.46  4935.5  327.75  4943.4  327.89
  4956.3  326.03  4970.7  325.05  5012.1  324.49  5012.3  323.99  5015.8  323.99
  5016.1  324.49  5057.4  326.01  5092.2  330.37  5098.5  331.66  5143.6  333.98
  5177.5  334.99  5321.5  335.73  5335.1  335.81  5450.4  336.42  5531.5  336.74
#Mann=11,-1,0
  4415.8    0.07       0  4694.7   0.035       0  4739.2    0.07       0
  4817.3    0.05       0  5012.1    0.05       0  5016.1    0.05       0
  5092.2    0.07       0  5143.6    0.05       0  5321.5    0.07       0
  5335.1    0.05       0  5450.4    0.07       0
Bank Sta=5012.1,5016.1
Exp/Cntr=0.3,0.1

Type RM Length L Ch R = 1,2103,250,250,250
BEGIN DESCRIPTION:
XS7092
END DESCRIPTION:
XS GIS Cut Line= 3
      2386594.03     13685021.90      2386181.68     13684470.66
      2385673.87     13684435.94
#Sta/Elev= 30
  4488.0  334.91  4528.0  333.94  4578.0  334.15  4642.6  333.51  4678.0  332.46
  4721.4  332.60  4728.1  332.01  4742.6  332.20  4776.8  331.27  4791.0  331.09
  4807.3  331.08  4821.3  329.99  4828.1  328.73  4842.7  328.81  4857.3  329.71
  4895.0  328.36  4928.1  325.24  4978.1  323.04  4997.0  322.89  4997.2  322.39
  5000.7  322.39  5001.0  322.89  5025.6  323.94  5084.4  328.90  5115.5  330.12
  5330.3  334.20  5423.7  335.82  5527.3  335.81  5639.5  335.68  5685.4  335.73
#Mann=11,-1,0
  4488.0    0.07       0  4776.8   0.035       0  4791.0    0.07       0
  4895.0    0.05       0  4997.0    0.05       0  5001.0    0.05       0
  5025.6    0.07       0  5115.5    0.05       0  5330.3    0.07       0
  5527.3    0.05       0  5639.5    0.07       0
Bank Sta=4997,5001
Exp/Cntr=0.3,0.1

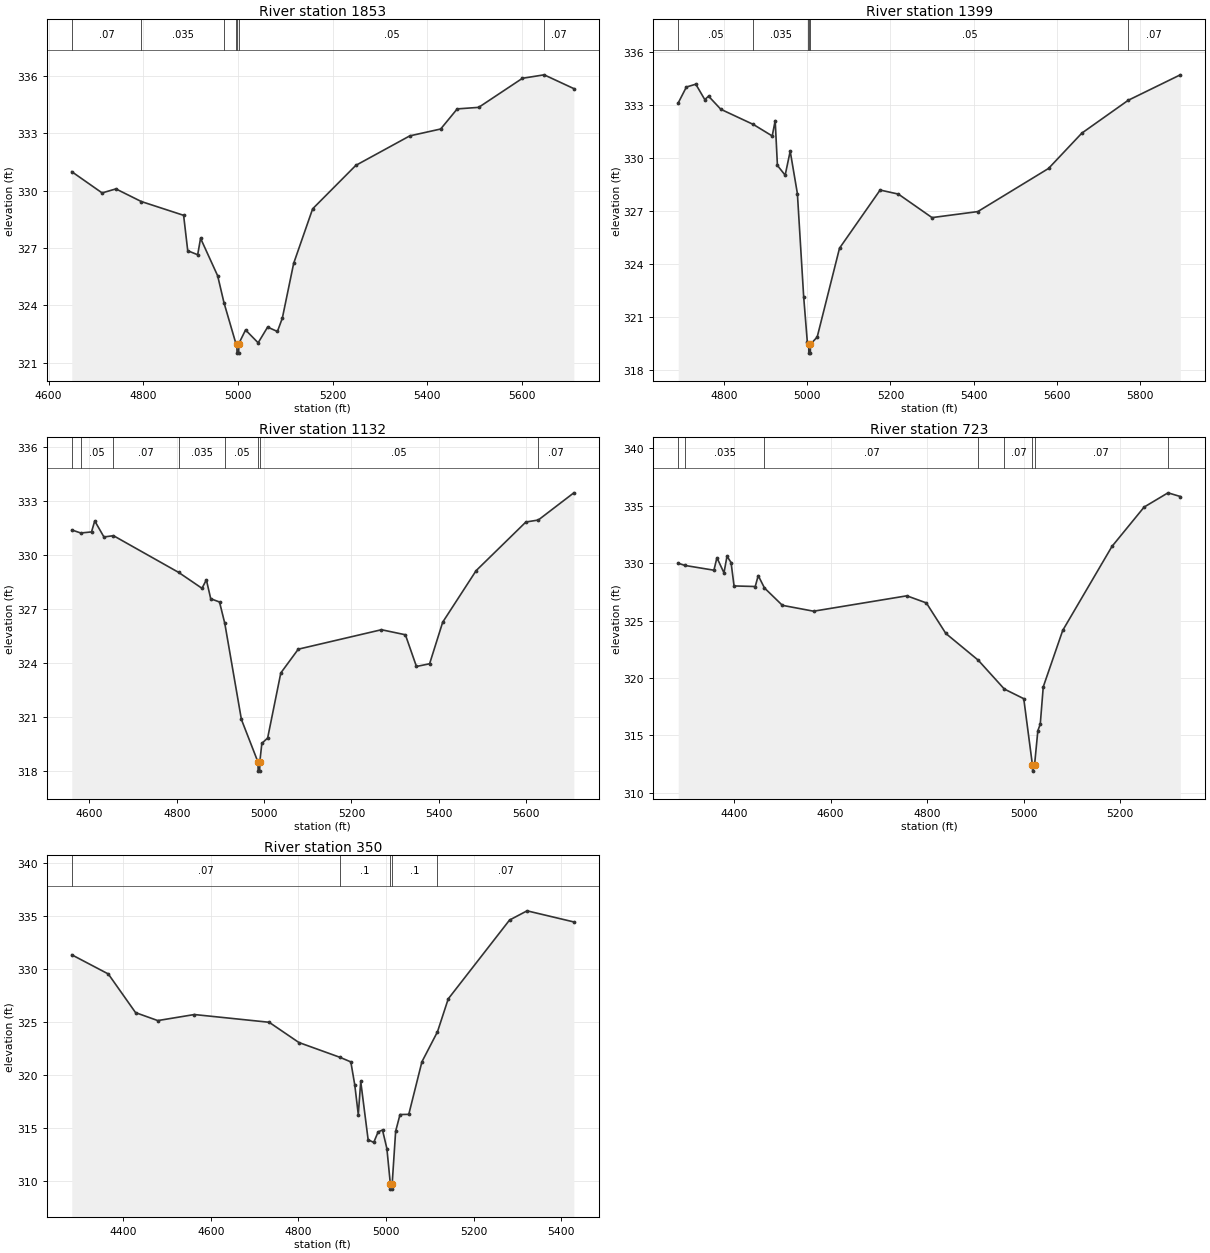
Type RM Length L Ch R = 1,1853,454,454,454
BEGIN DESCRIPTION:
XS7091
END DESCRIPTION:
XS GIS Cut Line= 3
      2386702.54     13684787.53      2386481.16     13684470.66
      2385830.15     13684297.06
#Sta/Elev= 30
  4648.9  330.99  4713.0  329.88  4742.1  330.09  4795.8  329.43  4885.1  328.71
  4893.8  326.86  4914.8  326.65  4920.9  327.51  4957.0  325.55  4970.4  324.14
  4995.4  322.02  4997.7  322.01  4997.9  321.51  5001.4  321.51  5001.7  322.01
  5015.9  322.72  5042.5  322.05  5062.5  322.87  5083.2  322.64  5093.6  323.34
  5117.5  326.20  5157.6  329.05  5248.8  331.32  5362.7  332.86  5428.0  333.22
  5462.9  334.27  5508.2  334.35  5600.7  335.87  5646.5  336.05  5709.2  335.33
#Mann=7,-1,0
  4648.9    0.07       0  4795.8   0.035       0  4970.4    0.12       0
  4995.4    0.05       0  4997.7    0.05       0  5001.7    0.05       0
  5646.5    0.07       0
Bank Sta=4997.7,5001.7
Exp/Cntr=0.3,0.1

Type RM Length L Ch R = 1,1399,267,267,267
BEGIN DESCRIPTION:
XS7090
END DESCRIPTION:
XS GIS Cut Line= 3
      2387054.06     13684349.12      2386546.27     13684140.80
      2385888.29     13684162.44
#Sta/Elev= 30
  4689.8  333.13  4709.4  334.03  4732.0  334.19  4753.6  333.32  4762.8  333.51
  4792.2  332.77  4870.5  331.91  4915.8  331.26  4922.9  332.13  4928.3  329.59
  4946.9  329.04  4959.0  330.40  4976.3  328.00  4991.4  322.16  5000.2  319.59
  5002.0  319.53  5003.6  319.47  5003.8  318.97  5007.4  318.97  5007.7  319.47
  5023.9  319.88  5077.6  324.91  5175.2  328.20  5219.1  327.97  5300.0  326.64
  5410.0  326.98  5580.1  329.42  5660.2  331.42  5771.8  333.28  5897.0  334.72
#Mann=6,-1,0
  4689.8    0.05       0  4870.5   0.035       0  5002.0    0.05       0
  5003.6   0.035       0  5007.7    0.05       0  5771.8    0.07       0
Bank Sta=5003.6,5007.7
Exp/Cntr=0.3,0.1

Type RM Length L Ch R = 1,1132,409,409,409
BEGIN DESCRIPTION:
XS7089
END DESCRIPTION:
XS GIS Cut Line= 3
      2387114.82     13684119.07      2386945.57     13683967.19
      2386025.41     13684023.61
#Sta/Elev= 30
  4559.7  331.40  4580.3  331.23  4604.9  331.29  4612.3  331.90  4633.3  331.01
  4655.2  331.08  4804.5  329.04  4857.8  328.16  4867.8  328.63  4877.8  327.58
  4897.9  327.40  4910.0  326.21  4948.0  320.88  4986.0  318.51  4986.3  318.01
  4989.9  318.01  4990.1  318.51  4994.8  319.55  5008.1  319.85  5038.2  323.46
  5078.2  324.78  5268.6  325.86  5323.4  325.58  5348.7  323.82  5378.8  323.97
  5408.8  326.28  5485.3  329.14  5599.2  331.84  5627.6  331.95  5709.0  333.46
#Mann=8,-1,0
  4559.7    0.07       0  4580.3    0.05       0  4655.2    0.07       0
  4804.5   0.035       0  4910.0    0.05       0  4986.0    0.05       0
  4990.1    0.05       0  5627.6    0.07       0
Bank Sta=4986,4990.1
Exp/Cntr=0.3,0.1

Type RM Length L Ch R = 1,723,373,373,373
BEGIN DESCRIPTION:
XS7088
END DESCRIPTION:
XS GIS Cut Line= 3
      2387075.77     13683936.80      2386824.05     13683750.17
      2386103.59     13683850.00
#Sta/Elev= 30
  4284.1  330.00  4297.4  329.81  4358.1  329.39  4364.3  330.48  4378.9  329.16
  4385.2  330.61  4393.6  330.06  4399.8  328.02  4443.7  327.97  4449.9  328.92
  4462.9  327.84  4500.0  326.33  4564.7  325.82  4758.0  327.16  4798.4  326.54
  4838.8  323.88  4906.0  321.55  4960.0  319.04  5000.3  318.20  5018.4  312.39
  5018.7  311.89  5022.6  312.39  5029.5  315.41  5034.5  315.98  5040.7  319.23
  5081.1  324.15  5183.1  331.46  5249.8  334.89  5299.3  336.13  5324.8  335.81
#Mann=8,-1,0
  4284.1    0.07       0  4297.4   0.035       0  4462.9    0.07       0
  4906.0     0.1       0  4960.0    0.07       0  5018.4    0.05       0
  5022.6    0.07       0  5299.3    0.05       0
Bank Sta=5018.4,5022.6
Exp/Cntr=0.3,0.1

Type RM Length L Ch R = 1,350,0,0,0
BEGIN DESCRIPTION:
XS7087
END DESCRIPTION:
XS GIS Cut Line= 3
      2387067.08     13683815.27      2386455.12     13683520.14
      2385988.21     13683528.79
#Sta/Elev= 30
  4282.5  331.31  4365.9  329.50  4428.2  325.85  4478.9  325.10  4562.4  325.67
  4733.2  324.94  4801.1  323.03  4895.0  321.63  4919.7  321.20  4928.7  319.02
  4936.7  316.23  4942.3  319.35  4959.2  313.85  4972.0  313.60  4982.0  314.59
  4992.0  314.77  5002.0  313.02  5009.9  309.69  5010.2  309.19  5013.8  309.19
  5014.1  309.69  5022.0  314.65  5032.0  316.23  5052.0  316.25  5082.0  321.21
  5117.5  324.04  5142.1  327.15  5282.1  334.59  5322.1  335.46  5428.9  334.41
#Mann=5,-1,0
  4282.5    0.07       0  4895.0     0.1       0  5009.9    0.05       0
  5014.1     0.1       0  5117.5    0.07       0
Bank Sta=5009.9,5014.1
Exp/Cntr=0.3,0.1

Chan Stop Cuts=-1