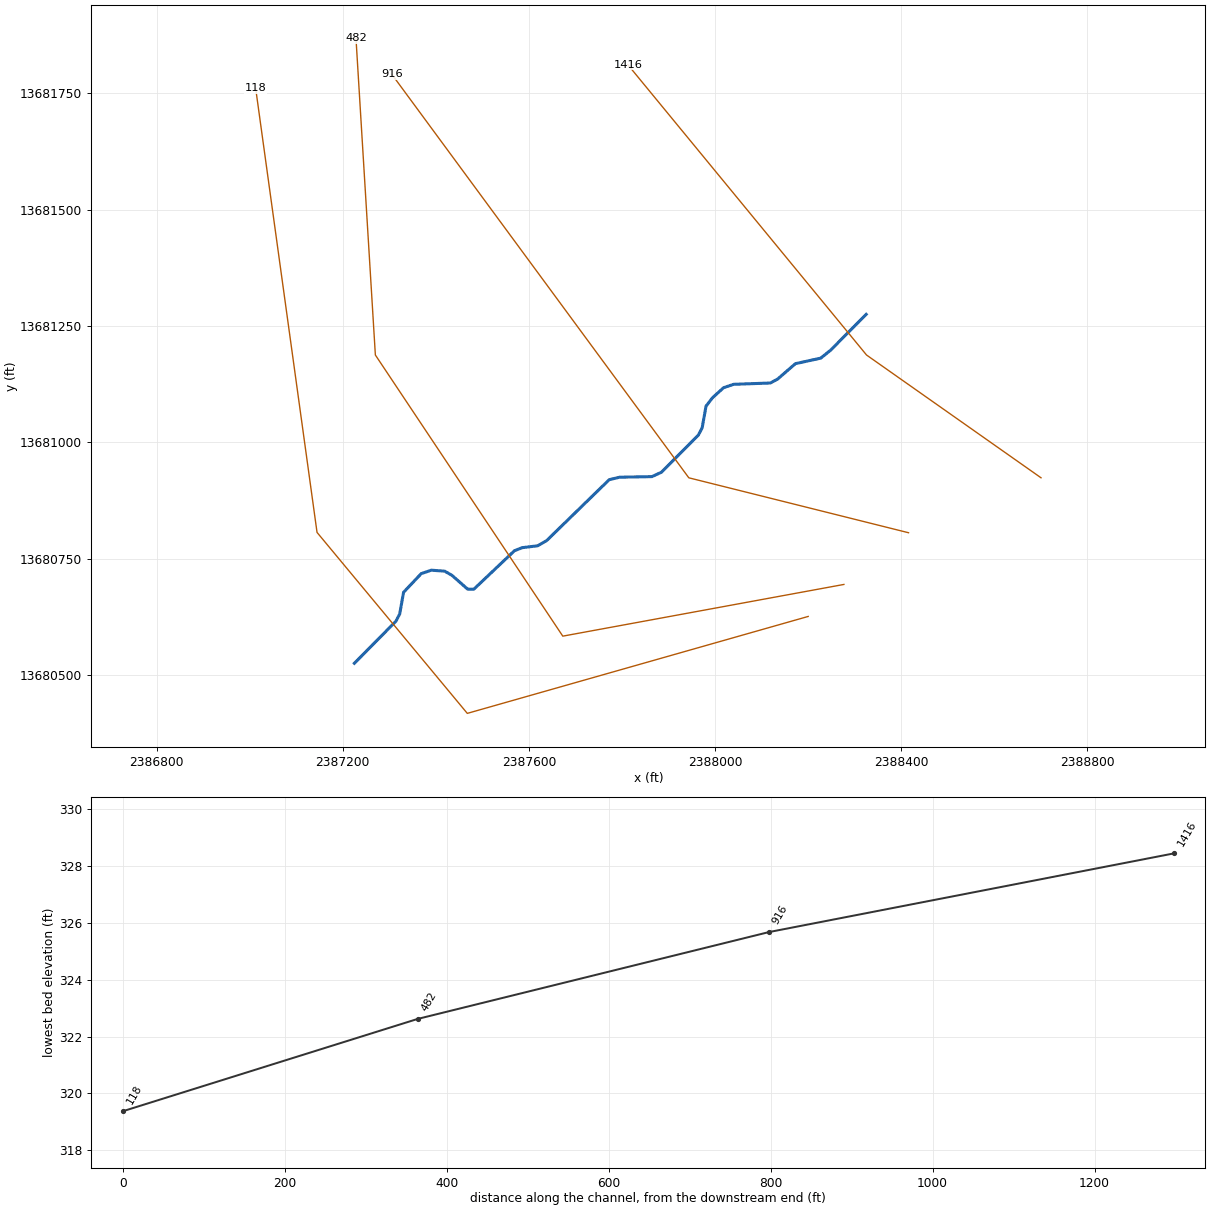
--- Stream0570.prj (project) ---

Proj Title=Stream0570 Base Level Engineering
Current Plan=p01
Default Exp/Contr=0.3,0.1
English Units
Geom File=g01
Flow File=f01
Plan File=p01
BEGIN DESCRIPTION:
Stream0570
END DESCRIPTION:

--- Stream0570.p01 (plan) ---

Plan Title=Multiple Run
Short Identifier=Multiple
Geom File=g01
Flow File=f01
Subcritical Flow
K Sum by GR= 0
Std Step Tol= 0.01
Critical Tol= 0.01
Num of Std Step Trials= 20
Max Error Tol= 0.3
Flow Tol Ratio= 0.001
Split Flow NTrial= 30
Split Flow Tol= 0.02
Split Flow Ratio= 0.02
Log Output Level= 0
Friction Slope Method= 1
Unsteady Friction Slope Method= 2
Unsteady Bridges Friction Slope Method= 1
Parabolic Critical Depth
Global Vel Dist=  1 , 1 , 1
Global Log Level= 0
CheckData=True
Encroach Param= -1, 0, 0, 0
BEGIN DESCRIPTION:
Multiple Run
END DESCRIPTION:

--- Stream0570.f01 (steady flow) ---

Flow Title=Multiple
Number of Profiles=7
Profile Names=10-year,25-year,50-year,1pct_min,100-year,1pct_plu,500-year
River Rch & RM= Stream0570,Reach-1,1416
     373     585     770     493     984    1963    1586
Boundary for River Rch & Prof#=Stream0570,Reach-1,1
Up Type=0
Dn Type=3
Dn Slope=0.005
Boundary for River Rch & Prof#=Stream0570,Reach-1,2
Up Type=0
Dn Type=3
Dn Slope=0.005
Boundary for River Rch & Prof#=Stream0570,Reach-1,3
Up Type=0
Dn Type=3
Dn Slope=0.005
Boundary for River Rch & Prof#=Stream0570,Reach-1,4
Up Type=0
Dn Type=3
Dn Slope=0.005
Boundary for River Rch & Prof#=Stream0570,Reach-1,5
Up Type=0
Dn Type=3
Dn Slope=0.005
Boundary for River Rch & Prof#=Stream0570,Reach-1,6
Up Type=0
Dn Type=3
Dn Slope=0.005
Boundary for River Rch & Prof#=Stream0570,Reach-1,7
Up Type=0
Dn Type=3
Dn Slope=0.005

--- Stream0570.g01 (geometry) ---

Geom Title=Existing Conditions

River Reach=Stream0570,Reach-1
Reach XY= 30
      2388325.00     13681275.00      2388248.51     13681197.92
      2388227.32     13681180.79      2388172.83     13681168.87
      2388134.65     13681135.84      2388119.03     13681127.33
      2388040.09     13681124.53      2388018.55     13681117.26
      2387994.59     13681095.57      2387980.74     13681077.57
      2387972.45     13681031.08      2387964.22     13681015.32
      2387884.81     13680935.51      2387864.52     13680926.16
      2387795.06     13680924.87      2387772.57     13680919.48
      2387638.21     13680788.63      2387618.95     13680777.53
      2387585.64     13680773.44      2387568.95     13680766.80
      2387481.72     13680684.17      2387468.45     13680684.34
      2387434.66     13680714.08      2387418.91     13680723.03
      2387390.24     13680725.04      2387368.67     13680717.62
      2387330.74     13680677.62      2387322.46     13680631.09
      2387314.28     13680615.32      2387225.00     13680525.00

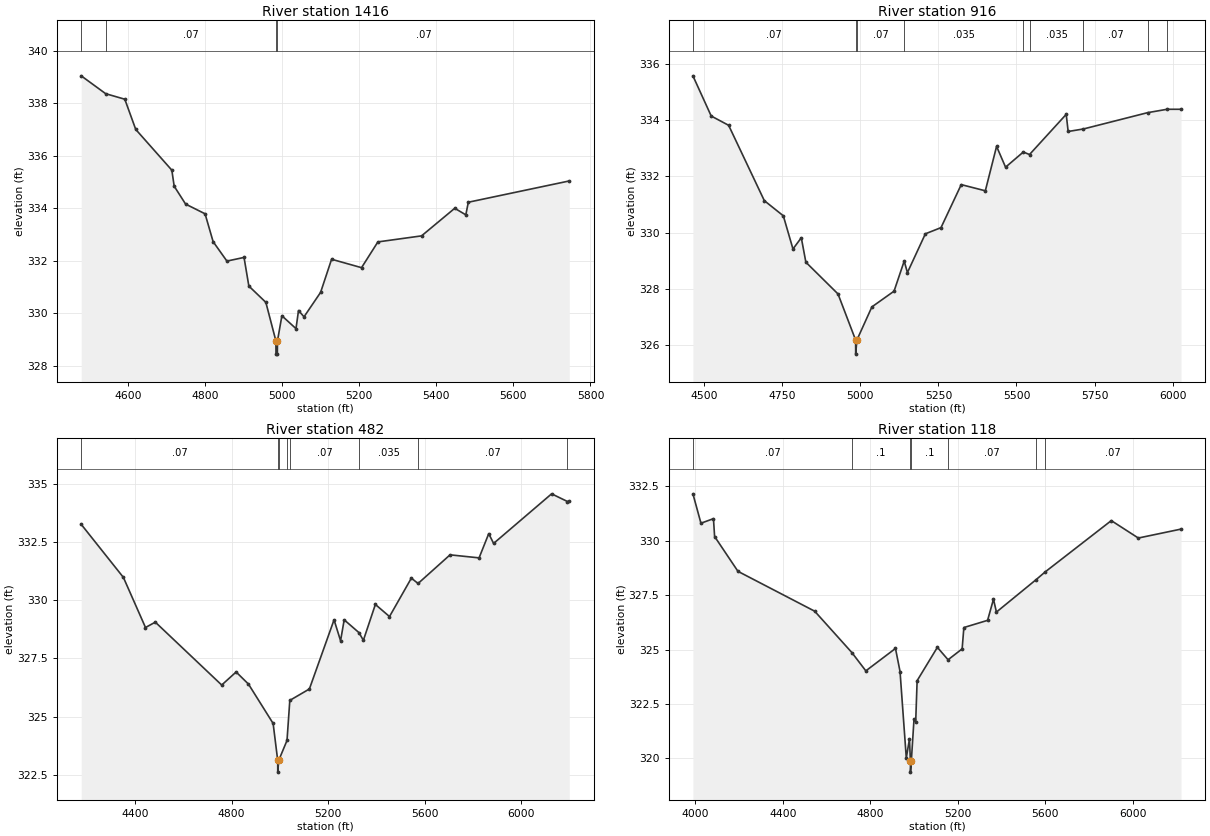
Type RM Length L Ch R = 1,1416,500,500,500
BEGIN DESCRIPTION:
XS7105
END DESCRIPTION:
XS GIS Cut Line= 3
      2388700.69     13680923.62      2388325.69     13681187.50
      2387812.81     13681811.28
#Sta/Elev= 30
  4479.0  339.04  4542.5  338.36  4592.1  338.15  4620.5  337.00  4714.1  335.45
  4720.2  334.84  4749.8  334.16  4800.3  333.79  4821.2  332.73  4857.0  331.99
  4901.4  332.13  4913.9  331.04  4958.0  330.42  4984.1  328.95  4984.3  328.45
  4987.8  328.45  4988.1  328.95  4999.6  329.91  5036.2  329.42  5042.7  330.11
  5057.0  329.87  5100.0  330.80  5128.5  332.06  5206.2  331.74  5248.6  332.72
  5361.9  332.95  5448.0  334.00  5476.7  333.75  5483.2  334.23  5745.1  335.04
#Mann=4,-1,0
  4479.0   0.035       0  4542.5    0.07       0  4984.1    0.05       0
  4988.1    0.07       0
Bank Sta=4984.1,4988.1
Exp/Cntr=0.3,0.1

Type RM Length L Ch R = 1,916,434,434,434
BEGIN DESCRIPTION:
XS7104
END DESCRIPTION:
XS GIS Cut Line= 3
      2388415.97     13680805.56      2387943.75     13680923.61
      2387305.50     13681790.80
#Sta/Elev= 30
  4463.6  335.58  4522.2  334.15  4578.0  333.82  4692.3  331.14  4753.2  330.60
  4784.1  329.42  4810.8  329.82  4825.4  328.95  4928.4  327.82  4984.8  326.18
  4985.0  325.68  4988.8  326.18  5036.9  327.36  5107.9  327.92  5140.4  328.99
  5150.7  328.58  5208.2  329.96  5258.3  330.18  5323.1  331.71  5400.3  331.49
  5436.3  333.07  5465.1  332.33  5522.0  332.87  5541.8  332.78  5659.4  334.21
  5665.6  333.60  5714.7  333.69  5920.2  334.27  5982.5  334.39  6027.1  334.39
#Mann=9,-1,0
  4463.6    0.07       0  4984.8    0.05       0  4988.8    0.07       0
  5140.4   0.035       0  5522.0    0.07       0  5541.8   0.035       0
  5714.7    0.07       0  5920.2    0.05       0  5982.5    0.07       0
Bank Sta=4984.8,4988.8
Exp/Cntr=0.3,0.1

Type RM Length L Ch R = 1,482,364,364,364
BEGIN DESCRIPTION:
XS7103
END DESCRIPTION:
XS GIS Cut Line= 4
      2388277.05     13680694.44      2387672.92     13680583.33
      2387270.14     13681187.50      2387228.47     13681868.05
#Sta/Elev= 30
  4176.9  333.26  4351.8  330.98  4443.3  328.83  4484.0  329.06  4759.0  326.36
  4818.8  326.92  4869.9  326.40  4972.1  324.71  4991.1  323.12  4991.3  322.62
  4995.1  323.12  5029.6  323.98  5041.2  325.70  5122.3  326.19  5224.5  329.16
  5251.5  328.26  5266.5  329.16  5327.7  328.61  5346.0  328.28  5395.7  329.82
  5454.2  329.30  5544.8  330.95  5572.6  330.72  5705.1  331.95  5825.4  331.82
  5865.4  332.86  5885.5  332.44  6125.9  334.57  6191.5  334.24  6199.1  334.25
#Mann=8,-1,0
  4176.9    0.07       0  4991.1    0.05       0  4995.1    0.07       0
  5029.6     0.1       0  5041.2    0.07       0  5327.7   0.035       0
  5572.6    0.07       0  6191.5    0.05       0
Bank Sta=4991.1,4995.1
Exp/Cntr=0.3,0.1

Type RM Length L Ch R = 1,118,0,0,0
BEGIN DESCRIPTION:
XS7103x
END DESCRIPTION:
XS GIS Cut Line= 4
      2388200.31     13680625.68      2387467.71     13680417.36
      2387144.79     13680806.25      2387012.92     13681760.55
#Sta/Elev= 30
  3989.6  332.15  4026.3  330.80  4083.5  331.01  4088.7  330.19  4195.5  328.59
  4546.1  326.76  4716.0  324.86  4779.8  324.02  4915.3  325.05  4936.1  323.99
  4964.7  320.02  4979.1  320.89  4983.6  319.87  4983.8  319.37  4987.6  319.87
  4999.9  321.79  5007.7  321.69  5014.2  323.57  5106.7  325.10  5155.6  324.53
  5219.9  325.03  5227.8  326.01  5336.2  326.34  5363.1  327.31  5376.6  326.72
  5558.0  328.21  5600.1  328.57  5901.5  330.92  6025.0  330.12  6220.1  330.53
#Mann=7,-1,0
  3989.6    0.07       0  4716.0     0.1       0  4983.6    0.05       0
  4987.6     0.1       0  5155.6    0.07       0  5558.0   0.035       0
  5600.1    0.07       0
Bank Sta=4983.6,4987.6
Exp/Cntr=0.3,0.1

Chan Stop Cuts=-1