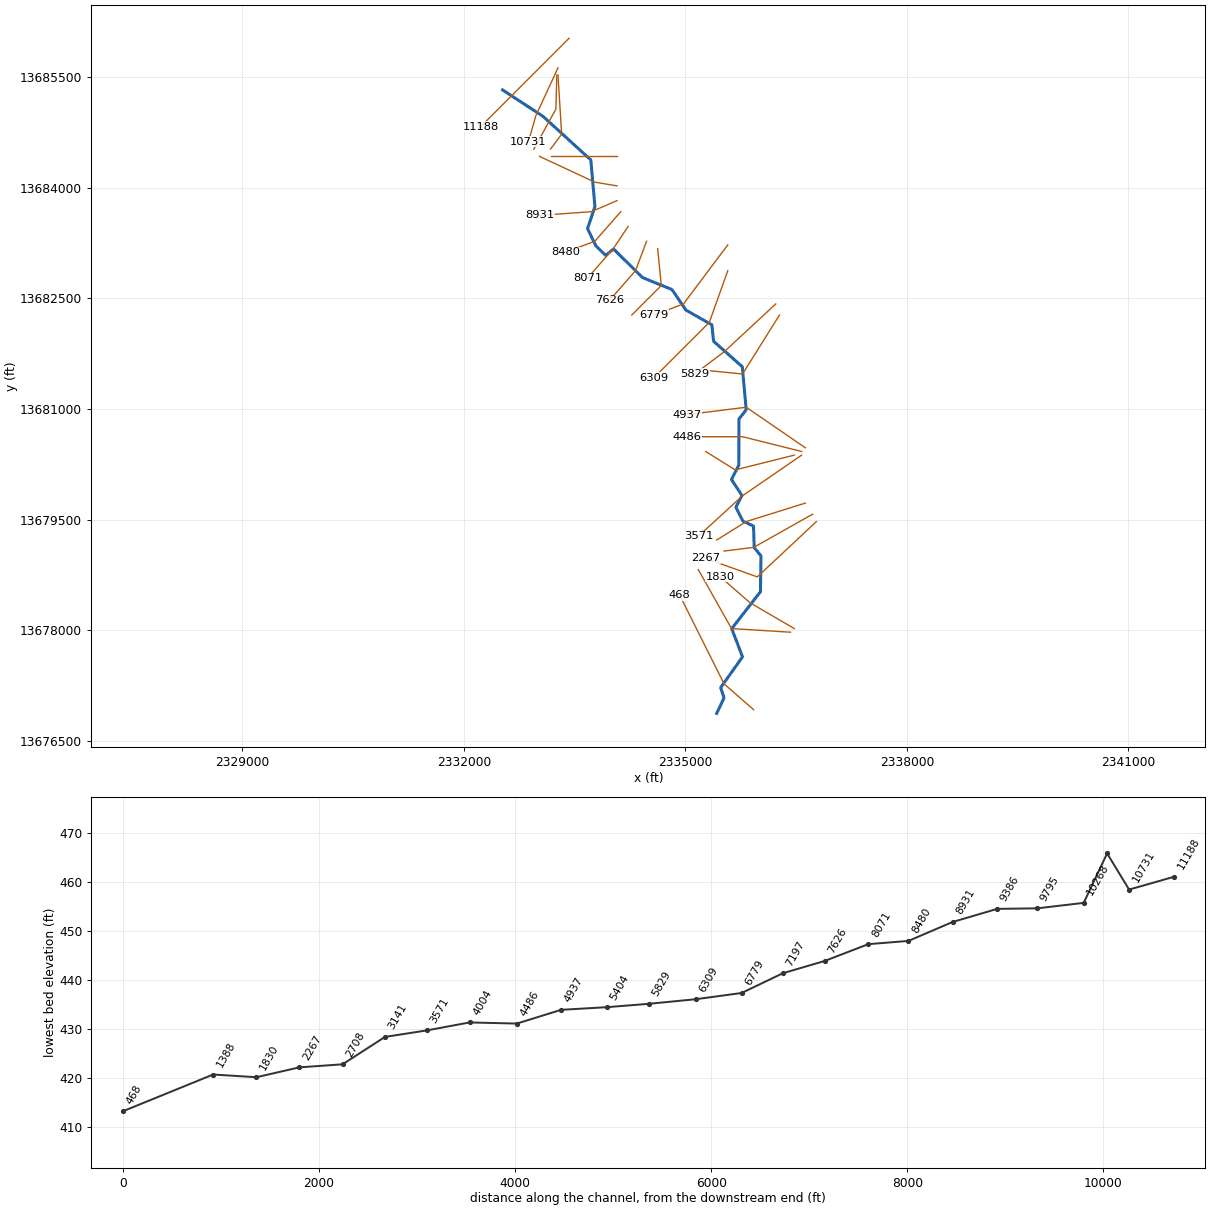
--- Stream0577.prj (project) ---

Proj Title=Stream0577 Base Level Engineering
Current Plan=p01
Default Exp/Contr=0.3,0.1
English Units
Geom File=g01
Flow File=f01
Plan File=p01
BEGIN DESCRIPTION:
Stream0577
END DESCRIPTION:

--- Stream0577.p01 (plan) ---

Plan Title=Multiple Run
Short Identifier=Multiple
Geom File=g01
Flow File=f01
Subcritical Flow
K Sum by GR= 0
Std Step Tol= 0.01
Critical Tol= 0.01
Num of Std Step Trials= 20
Max Error Tol= 0.3
Flow Tol Ratio= 0.001
Split Flow NTrial= 30
Split Flow Tol= 0.02
Split Flow Ratio= 0.02
Log Output Level= 0
Friction Slope Method= 1
Unsteady Friction Slope Method= 2
Unsteady Bridges Friction Slope Method= 1
Parabolic Critical Depth
Global Vel Dist=  1 , 1 , 1
Global Log Level= 0
CheckData=True
Encroach Param= -1, 0, 0, 0
BEGIN DESCRIPTION:
Multiple Run
END DESCRIPTION:

--- Stream0577.f01 (steady flow) ---

Flow Title=Multiple
Number of Profiles=7
Profile Names=10-year,25-year,50-year,1pct_min,100-year,1pct_plu,500-year
River Rch & RM= Stream0577,Reach-1,11188
     692    1132    1533    1005    2006    4003    3407
River Rch & RM= Stream0577,Reach-1,9795
     970    1608    2198    1452    2897    5781    4995
River Rch & RM= Stream0577,Reach-1,5404
    1178    1965    2697    1787    3566    7114    6186
Boundary for River Rch & Prof#=Stream0577,Reach-1,1
Up Type=0
Dn Type=3
Dn Slope=0.005
Boundary for River Rch & Prof#=Stream0577,Reach-1,2
Up Type=0
Dn Type=3
Dn Slope=0.005
Boundary for River Rch & Prof#=Stream0577,Reach-1,3
Up Type=0
Dn Type=3
Dn Slope=0.005
Boundary for River Rch & Prof#=Stream0577,Reach-1,4
Up Type=0
Dn Type=3
Dn Slope=0.005
Boundary for River Rch & Prof#=Stream0577,Reach-1,5
Up Type=0
Dn Type=3
Dn Slope=0.005
Boundary for River Rch & Prof#=Stream0577,Reach-1,6
Up Type=0
Dn Type=3
Dn Slope=0.005
Boundary for River Rch & Prof#=Stream0577,Reach-1,7
Up Type=0
Dn Type=3
Dn Slope=0.005

--- Stream0577.g01 (geometry) ---

Geom Title=Existing Conditions

River Reach=Stream0577,Reach-1
Reach XY= 30
      2332525.00     13685325.00      2333069.53     13684969.74
      2333719.48     13684377.43      2333775.39     13683745.13
      2333675.06     13683445.03      2333788.62     13683211.78
      2333921.84     13683082.54      2334027.20     13683170.17
      2334418.81     13682782.82      2334819.53     13682619.74
      2335007.95     13682341.50      2335358.76     13682142.22
      2335382.81     13681918.81      2335771.46     13681573.53
      2335824.61     13680990.16      2335726.05     13680864.56
      2335724.61     13680240.16      2335624.89     13680045.10
      2335767.22     13679828.40      2335684.39     13679668.39
      2335780.58     13679480.58      2335923.38     13679413.19
      2335933.01     13679121.67      2336024.61     13679009.84
      2336017.68     13678524.90      2335628.53     13678023.53
      2335774.48     13677640.89      2335478.14     13677223.36
      2335524.25     13677085.69      2335425.00     13676875.00

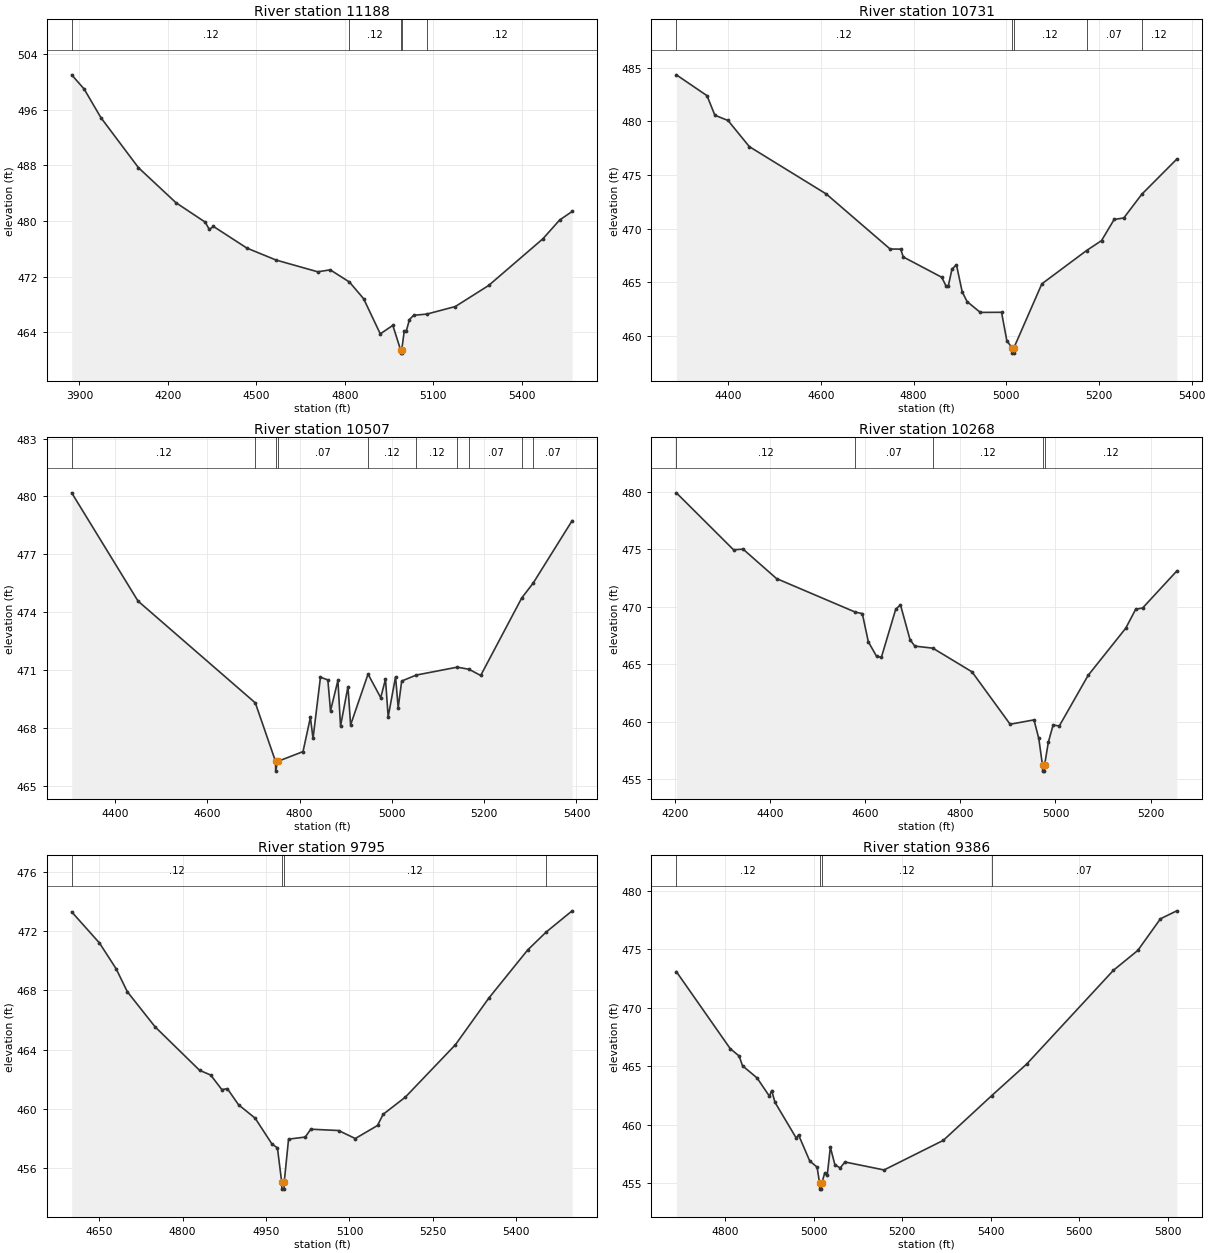
Type RM Length L Ch R = 1,11188,457,457,457
BEGIN DESCRIPTION:
Stream0577 24.0
END DESCRIPTION:
XS GIS Cut Line= 3
      2333425.01     13686025.01      2332625.00     13685225.00
      2332224.98     13684824.98
#Sta/Elev= 30
  3873.7  501.02  3916.1  498.97  3972.7  494.87  4100.0  487.68  4227.3  482.64
  4326.3  479.85  4340.4  478.80  4354.5  479.23  4467.7  476.12  4566.7  474.40
  4708.1  472.71  4750.5  472.99  4815.6  471.24  4863.7  468.84  4920.2  463.79
  4962.7  465.01  4988.8  461.52  4989.1  461.02  4992.8  461.02  4993.0  461.52
  5001.6  464.23  5008.6  464.23  5019.2  465.85  5033.4  466.46  5078.0  466.63
  5174.8  467.72  5287.9  470.75  5471.8  477.46  5528.3  480.15  5570.8  481.38
#Mann=5,-1,0
  3873.7    0.12       0  4815.6    0.12       0  4988.8    0.05       0
  4993.0    0.12       0  5078.0    0.12       0
Bank Sta=4988.8,4993
Exp/Cntr=0.3,0.1

Type RM Length L Ch R = 1,10731,224,224,224
BEGIN DESCRIPTION:
Stream0577 23.0
END DESCRIPTION:
XS GIS Cut Line= 3
      2333275.00     13685625.00      2332975.00     13684975.00
      2332875.00     13684624.99
#Sta/Elev= 30
  4288.1  484.32  4354.2  482.38  4371.2  480.56  4399.6  480.07  4445.5  477.64
  4611.6  473.23  4749.3  468.11  4772.2  468.10  4777.7  467.37  4860.8  465.48
  4869.5  464.71  4875.0  464.68  4882.8  466.24  4892.5  466.64  4904.9  464.12
  4915.4  463.22  4943.9  462.21  4989.8  462.22  5001.2  459.58  5012.2  458.92
  5012.5  458.42  5016.2  458.42  5016.5  458.92  5076.8  464.87  5173.3  467.97
  5205.5  468.89  5232.8  470.86  5253.6  471.00  5292.3  473.20  5368.0  476.48
#Mann=5,-1,0
  4288.1    0.12       0  5012.2    0.05       0  5016.5    0.12       0
  5173.3    0.07       0  5292.3    0.12       0
Bank Sta=5012.2,5016.5
Exp/Cntr=0.3,0.1

Type RM Length L Ch R = 1,10507,239,239,239
BEGIN DESCRIPTION:
Stream0577 23.0a
END DESCRIPTION:
XS GIS Cut Line= 3
      2333259.46     13685528.65      2333246.44     13685064.24
      2332946.96     13684521.70
#Sta/Elev= 30
  4306.3  480.19  4450.0  474.59  4704.2  469.32  4748.0  466.29  4748.3  465.79
  4752.3  466.29  4807.5  466.80  4823.5  468.57  4829.2  467.48  4845.3  470.65
  4861.3  470.51  4867.1  468.91  4883.1  470.48  4888.8  468.12  4904.9  470.16
  4910.6  468.18  4948.4  470.81  4975.9  469.59  4986.2  470.55  4992.0  468.60
  5008.0  470.67  5013.7  469.07  5021.3  470.45  5052.7  470.76  5141.8  471.17
  5167.1  471.06  5192.5  470.74  5281.4  474.75  5306.2  475.52  5390.6  478.75
#Mann=10,-1,0
  4306.3    0.12       0  4704.2    0.07       0  4748.0    0.05       0
  4752.3    0.07       0  4948.4    0.12       0  5052.7    0.12       0
  5141.8    0.12       0  5167.1    0.07       0  5281.4    0.12       0
  5306.2    0.07       0
Bank Sta=4748,4752.3
Exp/Cntr=0.3,0.1

Type RM Length L Ch R = 1,10268,473,473,473
BEGIN DESCRIPTION:
Stream0577 22.0
END DESCRIPTION:
XS GIS Cut Line= 3
      2333275.00     13685524.97      2333325.00     13684725.00
      2333175.02     13684525.03
#Sta/Elev= 30
  4203.4  479.93  4323.6  474.97  4343.6  475.03  4413.8  472.47  4579.3  469.55
  4594.1  469.42  4606.7  466.97  4624.2  465.69  4634.2  465.62  4664.3  469.80
  4674.3  470.18  4694.3  467.16  4704.3  466.59  4742.4  466.41  4824.6  464.35
  4904.7  459.79  4954.8  460.17  4964.9  458.55  4972.7  456.21  4973.0  455.71
  4976.7  455.71  4977.0  456.21  4984.9  458.22  4994.9  459.71  5008.1  459.65
  5068.5  464.04  5147.6  468.15  5168.5  469.80  5183.1  469.91  5254.9  473.13
#Mann=5,-1,0
  4203.4    0.12       0  4579.3    0.07       0  4742.4    0.12       0
  4972.7    0.05       0  4977.0    0.12       0
Bank Sta=4972.7,4977
Exp/Cntr=0.3,0.1

Type RM Length L Ch R = 1,9795,409,409,409
BEGIN DESCRIPTION:
Stream0577 21.0
END DESCRIPTION:
XS GIS Cut Line= 3
      2334074.97     13684425.00      2333675.00     13684425.00
      2333174.97     13684425.00
#Sta/Elev= 30
  4600.4  473.29  4650.4  471.19  4680.4  469.45  4700.4  467.91  4750.4  465.54
  4830.4  462.61  4850.4  462.29  4870.4  461.31  4880.4  461.37  4900.4  460.29
  4930.4  459.38  4960.4  457.65  4970.4  457.38  4978.0  455.10  4978.4  454.60
  4982.4  454.60  4982.7  455.10  4990.4  457.97  5020.4  458.11  5030.4  458.64
  5080.4  458.55  5110.4  458.01  5150.4  458.89  5160.4  459.64  5200.4  460.80
  5290.4  464.33  5350.4  467.47  5420.4  470.72  5453.7  471.93  5500.4  473.36
#Mann=4,-1,0
  4600.4    0.12       0  4978.0    0.05       0  4982.7    0.12       0
  5453.7    0.07       0
Bank Sta=4978,4982.7
Exp/Cntr=0.3,0.1

Type RM Length L Ch R = 1,9386,455,455,455
BEGIN DESCRIPTION:
Stream0577 20.0
END DESCRIPTION:
XS GIS Cut Line= 3
      2334075.02     13684025.00      2333775.00     13684075.00
      2333025.00     13684425.00
#Sta/Elev= 30
  4688.9  473.09  4810.6  466.51  4830.9  465.87  4838.5  465.04  4871.4  464.00
  4899.3  462.44  4904.4  462.92  4912.0  461.91  4960.1  458.85  4965.2  459.13
  4990.5  456.90  5007.2  456.37  5012.8  454.99  5013.1  454.49  5017.1  454.49
  5017.5  454.99  5024.6  455.88  5030.1  455.68  5037.2  458.07  5047.4  456.58
  5059.3  456.30  5070.3  456.81  5158.6  456.13  5292.6  458.66  5402.2  462.49
  5481.0  465.18  5677.2  473.20  5732.4  474.90  5783.7  477.61  5820.7  478.29
#Mann=4,-1,0
  4688.9    0.12       0  5012.8    0.05       0  5017.5    0.12       0
  5402.2    0.07       0
Bank Sta=5012.8,5017.5
Exp/Cntr=0.3,0.1

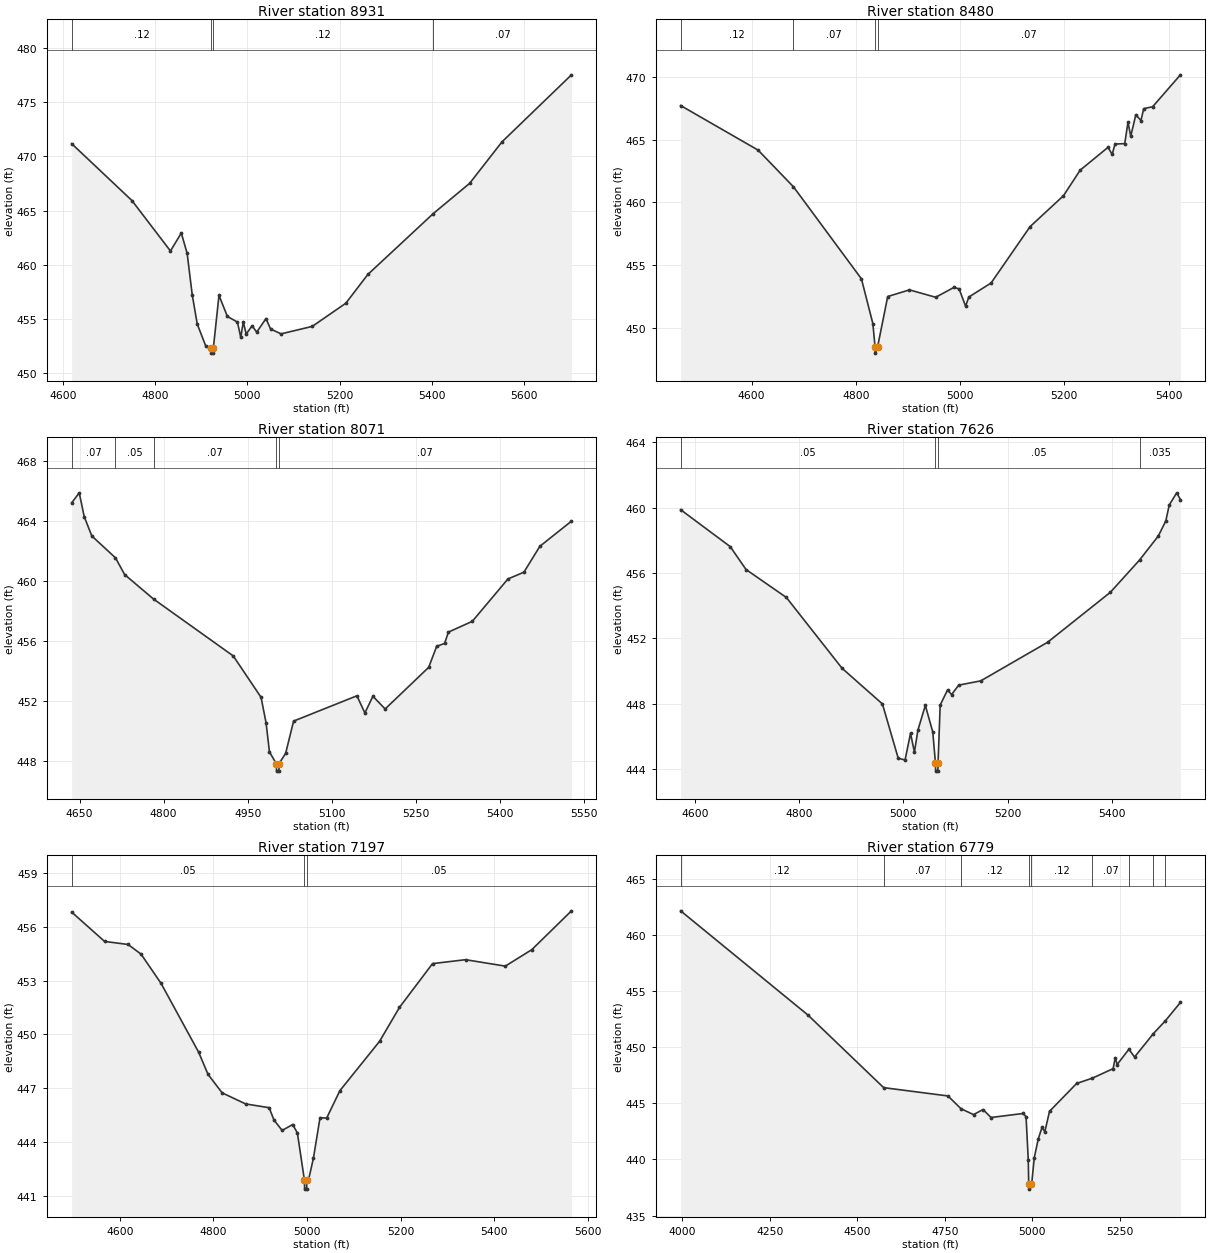
Type RM Length L Ch R = 1,8931,451,451,451
BEGIN DESCRIPTION:
Stream0577 19.0
END DESCRIPTION:
XS GIS Cut Line= 3
      2334075.00     13683825.00      2333725.00     13683675.00
      2333024.97     13683625.00
#Sta/Elev= 30
  4619.3  471.18  4749.9  465.92  4833.3  461.26  4856.8  462.92  4869.5  461.03
  4880.4  457.23  4891.3  454.51  4909.4  452.52  4921.6  452.32  4921.9  451.82
  4925.9  451.82  4926.3  452.32  4938.4  457.16  4956.6  455.21  4978.3  454.69
  4985.6  453.28  4991.0  454.70  4997.4  453.58  5010.1  454.35  5020.1  453.76
  5040.2  455.01  5050.2  454.05  5072.8  453.60  5140.4  454.29  5213.1  456.43
  5260.8  459.09  5402.6  464.72  5481.3  467.51  5551.5  471.35  5701.9  477.54
#Mann=4,-1,0
  4619.3    0.12       0  4921.6    0.05       0  4926.3    0.12       0
  5402.6    0.07       0
Bank Sta=4921.6,4926.3
Exp/Cntr=0.3,0.1

Type RM Length L Ch R = 1,8480,409,409,409
BEGIN DESCRIPTION:
Stream0577 18.0
END DESCRIPTION:
XS GIS Cut Line= 3
      2334125.03     13683675.03      2333775.00     13683275.00
      2333374.96     13683124.98
#Sta/Elev= 30
  4463.9  467.73  4612.5  464.17  4680.4  461.24  4810.8  453.89  4832.7  450.32
  4836.9  448.46  4837.2  447.96  4841.8  448.46  4861.2  452.48  4902.9  453.01
  4953.2  452.42  4988.3  453.21  4998.1  453.09  5010.6  451.71  5016.8  452.44
  5059.5  453.56  5134.3  458.06  5198.4  460.53  5230.4  462.57  5283.8  464.39
  5291.8  463.83  5297.2  464.65  5315.9  464.69  5322.1  466.40  5327.4  465.28
  5337.2  467.00  5347.0  466.53  5352.3  467.48  5369.3  467.63  5422.7  470.18
#Mann=4,-1,0
  4463.9    0.12       0  4680.4    0.07       0  4836.9    0.05       0
  4841.8    0.07       0
Bank Sta=4836.9,4841.8
Exp/Cntr=0.3,0.1

Type RM Length L Ch R = 1,8071,445,445,445
BEGIN DESCRIPTION:
Stream0577 17.0
END DESCRIPTION:
XS GIS Cut Line= 3
      2334224.99     13683474.99      2334025.00     13683175.00
      2333675.03     13682775.04
#Sta/Elev= 30
  4635.9  465.21  4649.4  465.88  4658.4  464.28  4671.9  463.00  4714.1  461.54
  4730.5  460.42  4782.0  458.79  4924.3  454.99  4973.9  452.23  4982.9  450.52
  4988.9  448.58  5001.1  447.80  5001.5  447.30  5005.7  447.30  5006.0  447.80
  5017.8  448.49  5032.0  450.64  5145.0  452.33  5159.2  451.18  5173.5  452.30
  5195.3  451.45  5273.1  454.23  5287.3  455.63  5301.6  455.83  5308.2  456.58
  5350.9  457.30  5414.5  460.13  5443.0  460.58  5471.5  462.31  5527.9  463.99
#Mann=5,-1,0
  4635.9    0.07       0  4714.1    0.05       0  4782.0    0.07       0
  5001.1    0.05       0  5006.0    0.07       0
Bank Sta=5001.1,5006
Exp/Cntr=0.3,0.1

Type RM Length L Ch R = 1,7626,429,429,429
BEGIN DESCRIPTION:
Stream0577 16.0
END DESCRIPTION:
XS GIS Cut Line= 3
      2334475.00     13683274.99      2334325.00     13682875.00
      2333975.00     13682475.00
#Sta/Elev= 30
  4572.8  459.87  4668.0  457.61  4698.3  456.21  4775.7  454.50  4882.5  450.17
  4959.9  447.99  4990.2  444.67  5003.3  444.56  5013.8  446.19  5021.3  445.04
  5028.0  446.39  5042.2  447.90  5056.5  446.27  5061.6  444.38  5062.0  443.88
  5066.2  443.88  5066.6  444.38  5070.7  447.92  5084.9  448.85  5092.5  448.56
  5106.3  449.14  5148.5  449.40  5276.7  451.76  5397.2  454.82  5453.1  456.79
  5489.3  458.27  5503.5  459.19  5510.1  460.16  5524.4  460.90  5531.5  460.49
#Mann=4,-1,0
  4572.8    0.05       0  5061.6    0.05       0  5066.6    0.05       0
  5453.1   0.035       0
Bank Sta=5061.6,5066.6
Exp/Cntr=0.3,0.1

Type RM Length L Ch R = 1,7197,418,418,418
BEGIN DESCRIPTION:
Stream0577 15.0
END DESCRIPTION:
XS GIS Cut Line= 3
      2334625.00     13683175.04      2334675.00     13682675.00
      2334275.02     13682275.02
#Sta/Elev= 30
  4497.2  456.84  4567.6  455.20  4617.8  455.03  4645.5  454.49  4688.2  452.86
  4768.6  449.01  4788.7  447.77  4818.8  446.74  4869.1  446.12  4919.3  445.91
  4929.4  445.23  4947.0  444.64  4969.6  444.97  4979.6  444.50  4994.7  441.86
  4995.1  441.36  4999.4  441.36  4999.7  441.86  5003.3  441.86  5013.9  443.09
  5028.0  445.35  5042.2  445.33  5070.4  446.86  5155.3  449.62  5197.7  451.51
  5268.4  453.96  5339.1  454.18  5424.0  453.82  5480.6  454.74  5565.4  456.91
#Mann=3,-1,0
  4497.2    0.05       0  4994.7    0.05       0  4999.7    0.05       0
Bank Sta=4994.7,4999.7
Exp/Cntr=0.3,0.1

Type RM Length L Ch R = 1,6779,470,470,470
BEGIN DESCRIPTION:
Stream0577 14.0
END DESCRIPTION:
XS GIS Cut Line= 3
      2335574.98     13683224.97      2334975.00     13682425.00
      2334574.97     13682274.99
#Sta/Elev= 30
  3995.7  462.14  4359.2  452.86  4575.5  446.39  4759.2  445.65  4796.4  444.51
  4832.1  443.99  4859.2  444.44  4882.1  443.73  4973.8  444.09  4982.1  443.80
  4988.4  439.98  4989.7  437.85  4990.2  437.35  4995.4  437.85  4998.3  437.85
  5005.5  440.14  5017.0  441.82  5027.7  442.85  5035.7  442.46  5049.1  444.28
  5126.5  446.76  5171.8  447.24  5230.6  448.08  5236.9  449.04  5242.2  448.45
  5275.8  449.81  5292.0  449.12  5345.9  451.21  5379.8  452.34  5422.9  453.98
#Mann=9,-1,0
  3995.7    0.12       0  4575.5    0.07       0  4796.4    0.12       0
  4989.7    0.05       0  4995.4    0.12       0  5171.8    0.07       0
  5275.8    0.05       0  5345.9    0.07       0  5379.8    0.05       0
Bank Sta=4989.7,4995.4
Exp/Cntr=0.3,0.1

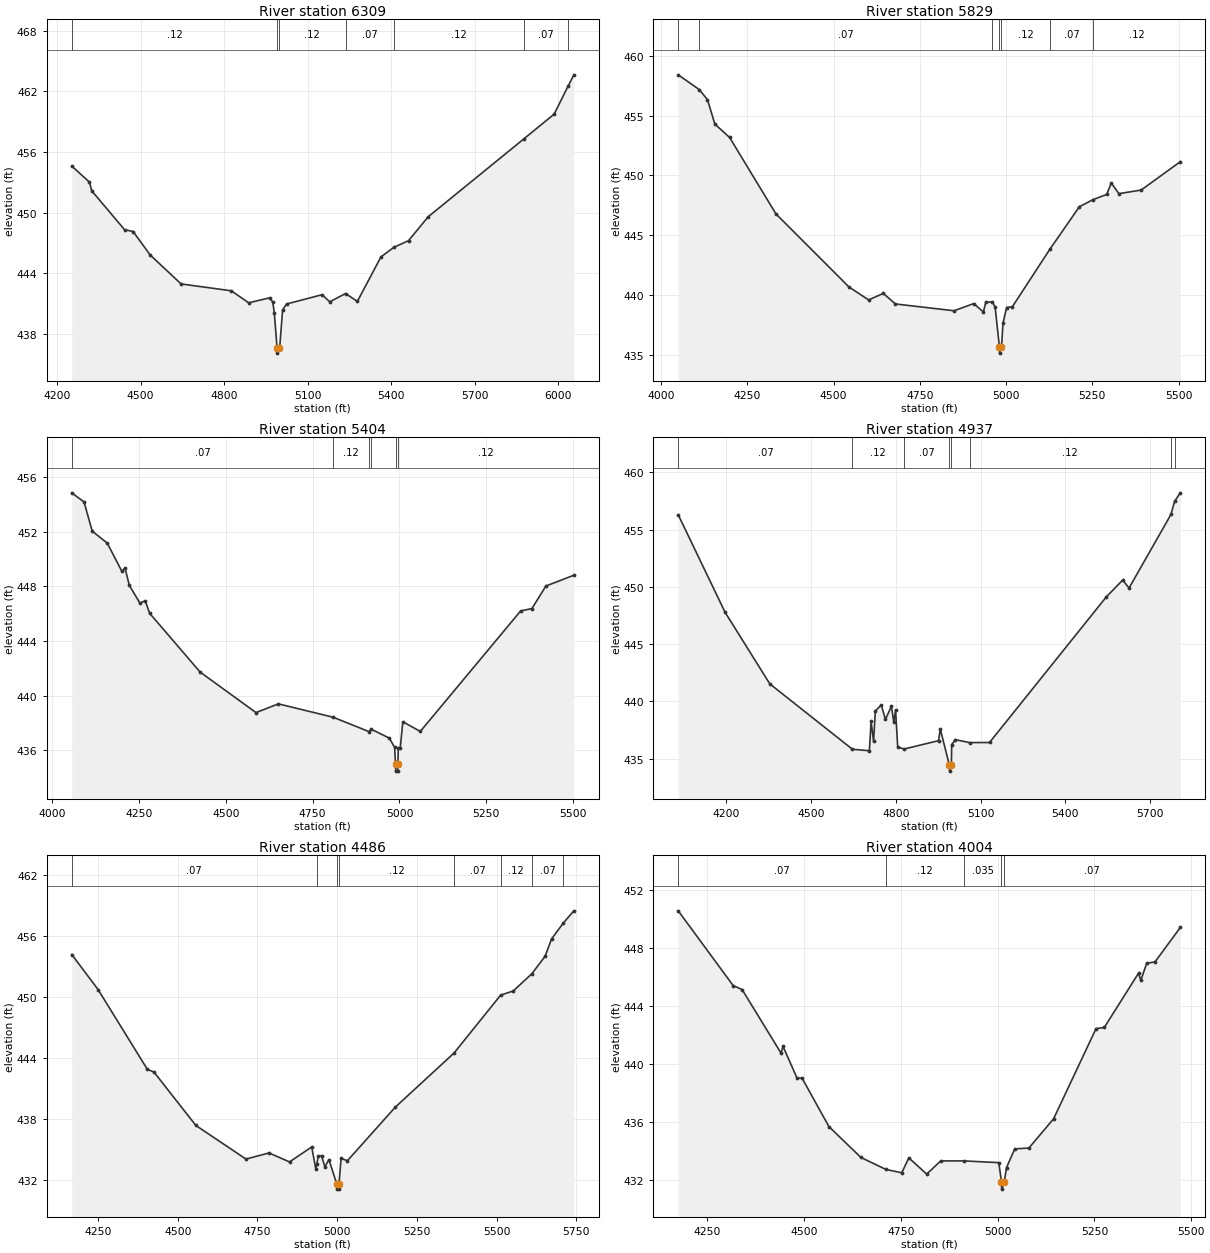
Type RM Length L Ch R = 1,6309,480,480,480
BEGIN DESCRIPTION:
Stream0577 13.0
END DESCRIPTION:
XS GIS Cut Line= 3
      2335575.00     13682875.01      2335325.00     13682175.00
      2334574.98     13681424.98
#Sta/Elev= 30
  4252.5  454.60  4316.2  453.00  4324.2  452.15  4442.1  448.30  4472.9  448.12
  4534.4  445.79  4645.4  442.93  4825.9  442.25  4888.0  441.06  4964.0  441.56
  4974.6  441.14  4980.4  440.04  4990.2  436.58  4990.7  436.08  4996.1  436.58
  4999.4  436.58  5010.0  440.34  5024.1  440.94  5151.4  441.86  5179.7  441.16
  5236.2  441.98  5278.7  441.20  5363.5  445.61  5410.8  446.57  5462.5  447.21
  5533.2  449.58  5876.4  457.28  5985.8  459.74  6035.8  462.51  6056.5  463.63
#Mann=7,-1,0
  4252.5    0.12       0  4990.2    0.05       0  4996.1    0.12       0
  5236.2    0.07       0  5410.8    0.12       0  5876.4    0.07       0
  6035.8    0.12       0
Bank Sta=4990.2,4996.1
Exp/Cntr=0.3,0.1

Type RM Length L Ch R = 1,5829,425,425,425
BEGIN DESCRIPTION:
Stream0577 12.0
END DESCRIPTION:
XS GIS Cut Line= 3
      2336224.97     13682424.97      2335525.00     13681775.00
      2335125.00     13681475.00
#Sta/Elev= 30
  4049.7  458.40  4110.5  457.17  4134.4  456.33  4155.9  454.28  4198.5  453.17
  4332.8  446.78  4544.9  440.66  4601.5  439.59  4644.1  440.13  4679.2  439.25
  4849.3  438.68  4906.0  439.28  4934.3  438.58  4941.1  439.41  4960.3  439.41
  4968.2  438.98  4980.7  435.64  4981.1  435.14  4986.6  435.64  4991.0  437.65
  5001.5  438.95  5018.4  439.03  5127.0  443.83  5212.2  447.37  5251.0  447.96
  5291.4  448.40  5304.9  449.36  5326.8  448.47  5391.4  448.77  5504.9  451.14
#Mann=7,-1,0
  4049.7    0.12       0  4110.5    0.07       0  4960.3    0.12       0
  4980.7    0.05       0  4986.6    0.12       0  5127.0    0.07       0
  5251.0    0.12       0
Bank Sta=4980.7,4986.6
Exp/Cntr=0.3,0.1

Type RM Length L Ch R = 1,5404,467,467,467
BEGIN DESCRIPTION:
Stream0577 11.0
END DESCRIPTION:
XS GIS Cut Line= 3
      2336274.99     13682274.98      2335775.00     13681475.00
      2335274.97     13681525.00
#Sta/Elev= 30
  4056.3  454.86  4091.7  454.19  4115.2  452.05  4158.3  451.18  4200.7  449.10
  4209.6  449.36  4222.0  448.08  4252.6  446.77  4267.9  446.95  4280.3  446.04
  4426.0  441.72  4586.9  438.75  4651.2  439.39  4809.2  438.41  4912.9  437.35
  4918.0  437.54  4970.8  436.88  4986.1  436.20  4988.6  434.96  4989.1  434.46
  4995.0  434.46  4995.5  434.96  4996.7  436.15  5002.2  436.15  5009.7  438.08
  5060.0  437.37  5348.9  446.20  5381.6  446.38  5421.8  448.03  5502.2  448.82
#Mann=6,-1,0
  4056.3    0.07       0  4809.2    0.12       0  4912.9    0.07       0
  4918.0    0.12       0  4988.6    0.05       0  4995.5    0.12       0
Bank Sta=4988.6,4995.5
Exp/Cntr=0.3,0.1

Type RM Length L Ch R = 1,4937,451,451,451
BEGIN DESCRIPTION:
Stream0577 10.0
END DESCRIPTION:
XS GIS Cut Line= 3
      2336624.99     13680475.00      2335825.00     13681025.00
      2335025.04     13680925.01
#Sta/Elev= 30
  4029.7  456.30  4195.5  447.79  4353.8  441.54  4646.1  435.83  4706.2  435.70
  4712.3  438.26  4721.1  436.51  4727.2  439.16  4748.2  439.70  4763.1  438.43
  4784.0  439.57  4792.8  438.20  4798.9  439.28  4806.4  436.03  4829.1  435.85
  4951.1  436.58  4957.2  437.59  4989.6  434.42  4990.1  433.92  4996.5  434.42
  4997.5  436.24  5010.6  436.67  5061.1  436.41  5131.5  436.42  5544.7  449.13
  5602.7  450.60  5625.3  449.91  5773.6  456.33  5786.3  457.47  5806.7  458.22
#Mann=8,-1,0
  4029.7    0.07       0  4646.1    0.12       0  4829.1    0.07       0
  4989.6    0.05       0  4996.5    0.07       0  5061.1    0.12       0
  5773.6    0.07       0  5786.3    0.12       0
Bank Sta=4989.6,4996.5
Exp/Cntr=0.3,0.1

Type RM Length L Ch R = 1,4486,482,482,482
BEGIN DESCRIPTION:
Stream0577 9.0
END DESCRIPTION:
XS GIS Cut Line= 3
      2336575.02     13680425.00      2335775.00     13680625.00
      2335025.04     13680625.00
#Sta/Elev= 30
  4167.8  454.22  4250.3  450.77  4404.9  442.91  4425.5  442.65  4556.9  437.39
  4714.1  434.08  4786.3  434.68  4850.7  433.80  4920.3  435.27  4933.2  433.09
  4936.2  433.58  4940.9  434.34  4951.2  434.41  4961.5  433.33  4974.4  434.02
  4998.9  431.62  4999.4  431.12  5005.4  431.12  5005.9  431.62  5012.4  434.14
  5032.4  433.92  5182.4  439.19  5366.7  444.52  5512.8  450.22  5552.4  450.63
  5611.2  452.34  5652.4  454.05  5672.4  455.75  5709.6  457.33  5742.4  458.52
#Mann=8,-1,0
  4167.8    0.07       0  4936.2    0.12       0  4998.9    0.05       0
  5005.9    0.12       0  5366.7    0.07       0  5512.8    0.12       0
  5611.2    0.07       0  5709.6    0.12       0
Bank Sta=4998.9,5005.9
Exp/Cntr=0.3,0.1

Type RM Length L Ch R = 1,4004,433,433,433
BEGIN DESCRIPTION:
Stream0577 8.0
END DESCRIPTION:
XS GIS Cut Line= 3
      2336474.99     13680375.00      2335675.00     13680175.00
      2335275.01     13680425.00
#Sta/Elev= 30
  4175.4  450.58  4317.1  445.42  4340.3  445.14  4440.8  440.75  4446.0  441.21
  4482.0  439.03  4494.9  439.03  4564.5  435.67  4647.0  433.54  4711.6  432.71
  4752.6  432.48  4770.7  433.51  4817.0  432.39  4853.1  433.30  4913.1  433.30
  5003.0  433.18  5010.0  431.85  5010.5  431.35  5017.2  431.85  5023.0  432.84
  5044.2  434.13  5080.8  434.19  5144.5  436.21  5254.1  442.44  5275.4  442.52
  5363.8  446.27  5369.7  445.78  5385.0  446.96  5406.3  447.05  5471.7  449.43
#Mann=5,-1,0
  4175.4    0.07       0  4711.6    0.12       0  4913.1   0.035       0
  5010.0   0.035       0  5017.2    0.07       0
Bank Sta=5010,5017.2
Exp/Cntr=0.3,0.1

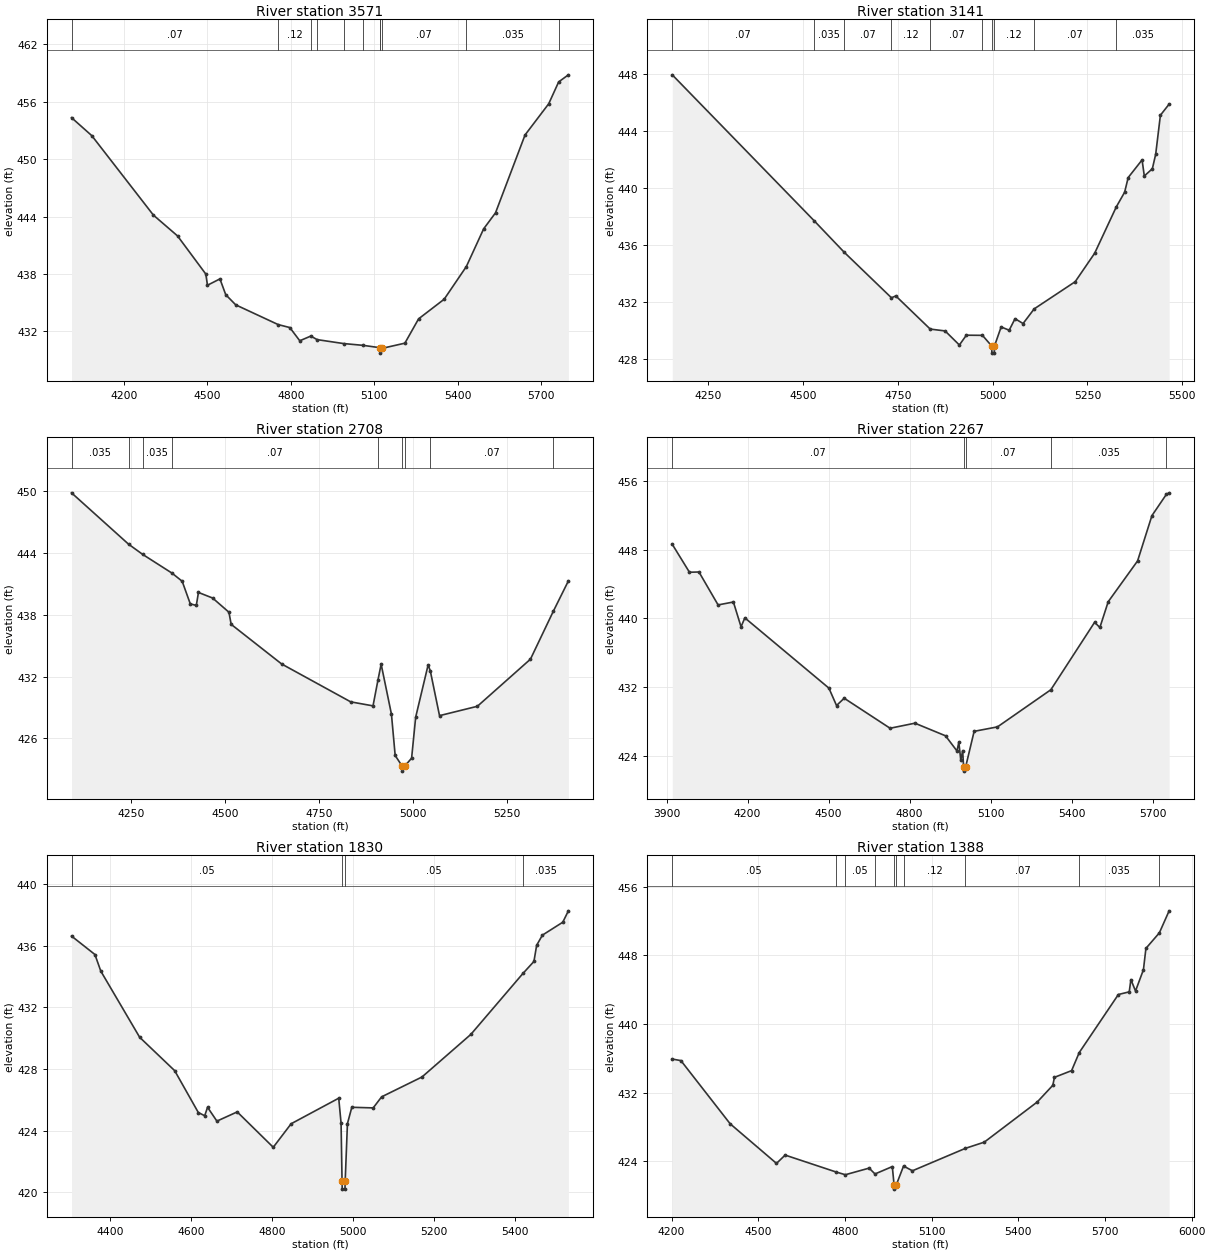
Type RM Length L Ch R = 1,3571,430,430,430
BEGIN DESCRIPTION:
Stream0577 7.0
END DESCRIPTION:
XS GIS Cut Line= 3
      2336574.96     13680374.97      2335775.00     13679825.00
      2335175.01     13679275.01
#Sta/Elev= 30
  4012.4  454.33  4085.2  452.45  4306.6  444.15  4393.2  441.98  4494.7  438.00
  4500.8  436.83  4545.5  437.49  4566.4  435.84  4602.3  434.78  4754.7  432.72
  4796.5  432.41  4832.3  431.03  4871.8  431.52  4894.7  431.15  4989.5  430.74
  5060.4  430.55  5119.5  430.31  5121.1  430.24  5121.6  429.74  5128.3  430.24
  5209.8  430.78  5259.1  433.32  5351.0  435.37  5430.6  438.78  5492.8  442.72
  5535.4  444.39  5641.4  452.52  5726.5  455.78  5762.2  458.06  5797.1  458.80
#Mann=11,-1,0
  4012.4    0.07       0  4754.7    0.12       0  4871.8   0.035       0
  4894.7    0.12       0  4989.5    0.07       0  5060.4    0.12       0
  5119.5    0.07       0  5121.1    0.05       0  5128.3    0.07       0
  5430.6   0.035       0  5762.2    0.07       0
Bank Sta=5121.1,5128.3
Exp/Cntr=0.3,0.1

Type RM Length L Ch R = 1,3141,433,433,433
BEGIN DESCRIPTION:
Stream0577 6.0
END DESCRIPTION:
XS GIS Cut Line= 3
      2336624.97     13679724.99      2335825.00     13679475.00
      2335425.02     13679225.01
#Sta/Elev= 30
  4155.7  447.96  4529.2  437.72  4609.0  435.49  4733.5  432.29  4745.0  432.42
  4835.7  430.09  4874.9  429.96  4912.6  428.97  4931.0  429.66  4973.4  429.65
  4997.8  428.90  4998.3  428.40  5004.6  428.40  5005.1  428.90  5022.7  430.24
  5043.9  430.01  5059.3  430.82  5080.5  430.48  5109.8  431.51  5217.9  433.42
  5269.2  435.42  5326.3  438.68  5348.2  439.71  5357.6  440.74  5394.2  441.98
  5400.1  440.85  5421.3  441.36  5430.1  442.38  5442.5  445.12  5465.5  445.90
#Mann=10,-1,0
  4155.7    0.07       0  4529.2   0.035       0  4609.0    0.07       0
  4733.5    0.12       0  4835.7    0.07       0  4973.4    0.12       0
  4997.8    0.05       0  5005.1    0.12       0  5109.8    0.07       0
  5326.3   0.035       0
Bank Sta=4997.8,5005.1
Exp/Cntr=0.3,0.1

Type RM Length L Ch R = 1,2708,441,441,441
BEGIN DESCRIPTION:
Stream0577 5.0
END DESCRIPTION:
XS GIS Cut Line= 3
      2336725.01     13679575.00      2335925.00     13679125.00
      2335525.00     13679075.00
#Sta/Elev= 30
  4092.3  449.86  4244.0  444.87  4281.8  443.87  4359.4  442.06  4386.5  441.27
  4408.1  439.07  4424.1  438.92  4429.8  440.18  4467.4  439.64  4510.8  438.26
  4516.8  437.08  4651.0  433.23  4834.6  429.55  4893.9  429.16  4907.1  431.68
  4915.5  433.21  4942.9  428.35  4952.8  424.34  4971.1  423.32  4971.6  422.82
  4978.5  423.32  4996.5  424.08  5007.3  428.06  5040.4  433.14  5046.2  432.56
  5070.7  428.21  5171.4  429.12  5312.5  433.70  5373.1  438.34  5413.3  441.30
#Mann=9,-1,0
  4092.3   0.035       0  4244.0    0.07       0  4281.8   0.035       0
  4359.4    0.07       0  4907.1    0.12       0  4971.1    0.05       0
  4978.5    0.12       0  5046.2    0.07       0  5373.1   0.035       0
Bank Sta=4971.1,4978.5
Exp/Cntr=0.3,0.1

Type RM Length L Ch R = 1,2267,437,437,437
BEGIN DESCRIPTION:
Stream0577 4.0
END DESCRIPTION:
XS GIS Cut Line= 3
      2336774.97     13679474.97      2335975.00     13678725.00
      2335275.04     13678974.98
#Sta/Elev= 30
  3921.2  448.65  3984.9  445.39  4020.1  445.42  4090.9  441.58  4147.6  441.92
  4175.9  439.03  4190.0  440.07  4501.2  431.88  4529.5  429.85  4557.9  430.70
  4727.8  427.20  4819.7  427.79  4933.0  426.32  4975.5  424.55  4982.3  425.57
  4989.6  423.47  4996.5  424.59  5000.0  422.70  5000.5  422.20  5007.6  422.70
  5039.0  426.84  5125.5  427.36  5323.1  431.69  5485.0  439.55  5504.6  438.95
  5535.4  441.95  5644.2  446.71  5697.3  451.99  5751.0  454.48  5761.0  454.65
#Mann=5,-1,0
  3921.2    0.07       0  5000.0    0.05       0  5007.6    0.07       0
  5323.1   0.035       0  5751.0    0.07       0
Bank Sta=5000,5007.6
Exp/Cntr=0.3,0.1

Type RM Length L Ch R = 1,1830,442,442,442
BEGIN DESCRIPTION:
Stream0577 3.0
END DESCRIPTION:
XS GIS Cut Line= 3
      2336474.96     13678025.02      2335875.00     13678375.00
      2335474.99     13678725.01
#Sta/Elev= 30
  4305.2  436.64  4363.0  435.44  4377.5  434.36  4473.4  430.06  4559.8  427.89
  4618.1  425.17  4633.9  424.96  4640.9  425.51  4664.0  424.61  4714.1  425.21
  4803.0  422.91  4847.2  424.44  4964.6  426.10  4970.4  424.47  4972.8  420.69
  4973.3  420.19  4980.0  420.19  4980.5  420.69  4986.1  424.45  4996.9  425.51
  5049.6  425.47  5070.5  426.19  5170.1  427.48  5290.7  430.25  5419.2  434.21
  5446.3  434.99  5453.0  436.04  5467.2  436.70  5517.5  437.54  5531.3  438.28
#Mann=4,-1,0
  4305.2    0.05       0  4972.8    0.05       0  4980.5    0.05       0
  5419.2   0.035       0
Bank Sta=4972.8,4980.5
Exp/Cntr=0.3,0.1

Type RM Length L Ch R = 1,1388,920,920,920
BEGIN DESCRIPTION:
Stream0577 2.0
END DESCRIPTION:
XS GIS Cut Line= 3
      2336424.97     13677975.00      2335625.00     13678025.00
      2335175.00     13678824.99
#Sta/Elev= 30
  4202.6  435.91  4232.6  435.73  4403.0  428.36  4563.3  423.74  4593.3  424.71
  4770.3  422.73  4801.6  422.42  4883.9  423.19  4904.2  422.51  4964.1  423.37
  4970.2  421.24  4970.7  420.74  4977.9  421.24  5003.0  423.43  5033.8  422.88
  5217.3  425.50  5282.4  426.22  5465.9  430.91  5519.5  432.85  5525.2  433.78
  5584.5  434.56  5611.0  436.67  5746.4  443.44  5784.0  443.75  5789.7  445.18
  5805.7  443.85  5833.1  446.33  5841.7  448.82  5888.2  450.63  5922.0  453.20
#Mann=10,-1,0
  4202.6    0.05       0  4770.3    0.07       0  4801.6    0.05       0
  4904.2    0.07       0  4970.2    0.05       0  4977.9    0.07       0
  5003.0    0.12       0  5217.3    0.07       0  5611.0   0.035       0
  5888.2    0.07       0
Bank Sta=4970.2,4977.9
Exp/Cntr=0.3,0.1

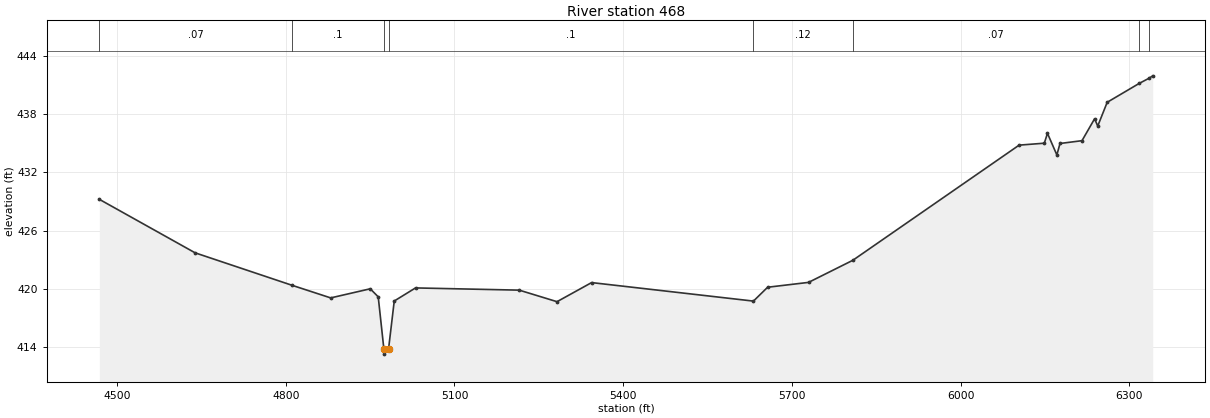
Type RM Length L Ch R = 1,468,0,0,0
BEGIN DESCRIPTION:
Stream0577 1.0
END DESCRIPTION:
XS GIS Cut Line= 3
      2335924.98     13676925.01      2335525.00     13677275.00
      2334925.01     13678474.98
#Sta/Elev= 30
  4468.5  429.23  4638.8  423.71  4810.7  420.37  4879.9  419.06  4950.2  420.00
  4964.4  419.17  4974.5  413.76  4975.0  413.26  4982.7  413.76  4992.9  418.74
  5030.7  420.09  5215.2  419.86  5282.3  418.67  5343.8  420.64  5631.6  418.73
  5656.8  420.16  5729.5  420.66  5808.3  422.94  6104.0  434.82  6148.8  435.02
  6154.4  436.04  6171.1  433.81  6176.7  434.99  6215.8  435.28  6238.2  437.54
  6243.8  436.79  6260.6  439.24  6317.3  441.18  6335.3  441.73  6341.6  441.97
#Mann=8,-1,0
  4468.5    0.07       0  4810.7     0.1       0  4974.5    0.05       0
  4982.7     0.1       0  5631.6    0.12       0  5808.3    0.07       0
  6317.3   0.035       0  6335.3    0.07       0
Bank Sta=4974.5,4982.7
Exp/Cntr=0.3,0.1

Chan Stop Cuts=-1