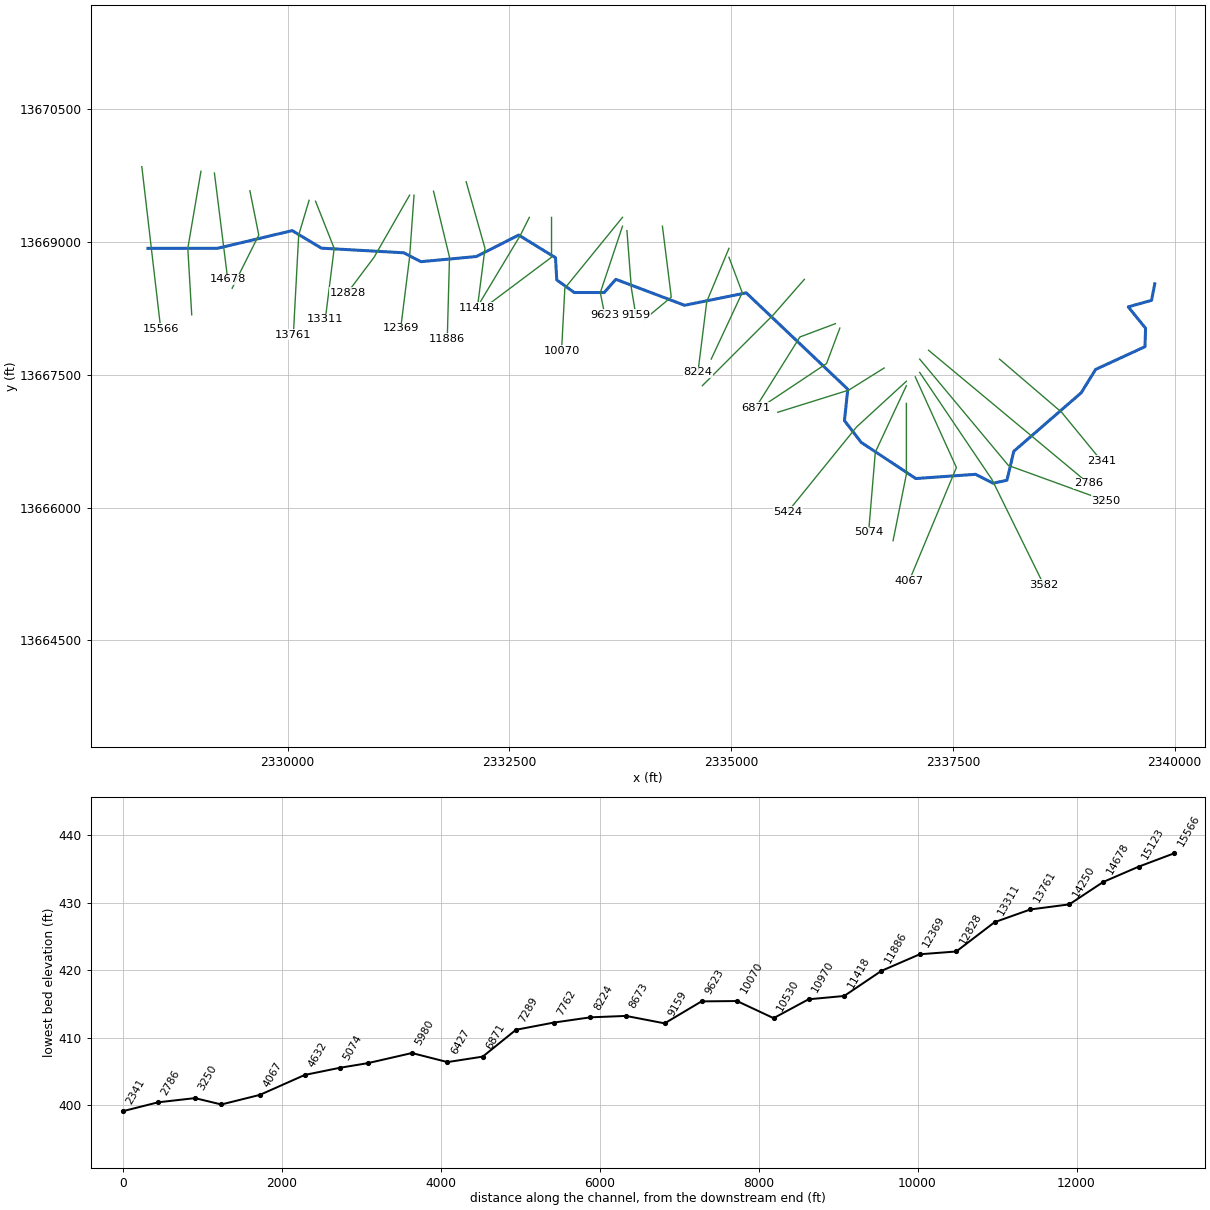
--- Stream0578.prj (project) ---

Proj Title=Stream0578 Base Level Engineering
Current Plan=p01
Default Exp/Contr=0.3,0.1
English Units
Geom File=g01
Flow File=f01
Plan File=p01
Y Axis Title=Elevation
X Axis Title(PF)=Main Channel Distance
X Axis Title(XS)=Station
BEGIN DESCRIPTION:
Stream0578
END DESCRIPTION:
DSS Export Rating Curves= 0
DSS Export Rating Curve Sorted= 0
DSS Export Volume Flow Curves= 0
DXF OffsetX= 0
DXF OffsetY= 0
DXF ScaleX= 1
DXF ScaleY= 10

--- Stream0578.p01 (plan) ---

Plan Title=Multiple Run
Short Identifier=Multiple
Geom File=g01
Flow File=f01
Subcritical Flow
K Sum by GR= 0
Std Step Tol= 0.01
Critical Tol= 0.01
Num of Std Step Trials= 20
Max Error Tol= 0.3
Flow Tol Ratio= 0.001
Split Flow NTrial= 30
Split Flow Tol= 0.02
Split Flow Ratio= 0.02
Log Output Level= 0
Friction Slope Method= 1
Unsteady Friction Slope Method= 2
Unsteady Bridges Friction Slope Method= 1
Parabolic Critical Depth
Global Vel Dist=  1 , 1 , 1
Global Log Level= 0
CheckData=True
Encroach Param= -1, 0, 0, 0
BEGIN DESCRIPTION:
Multiple Run
END DESCRIPTION:

--- Stream0578.f01 (steady flow) ---

Flow Title=Multiple
Number of Profiles=7
Profile Names=10-year,25-year,50-year,1pct_min,100-year,1pct_plu,500-year
River Rch & RM= Stream0578,Reach-1,15566
     892    1488    2044    1358    2709    5406    4725
River Rch & RM= Stream0578,Reach-1,11418
    1352    2284    3162    2115    4219    8418    7454
River Rch & RM= Stream0578,Reach-1,8224
    1426    2412    3341    2233    4455    8890    7870
River Rch & RM= Stream0578,Reach-1,5074
    1740    2939    4067    2713    5414   10802    9523
Boundary for River Rch & Prof#=Stream0578,Reach-1,1
Up Type=0
Dn Type=3
Dn Slope=0.005
Boundary for River Rch & Prof#=Stream0578,Reach-1,2
Up Type=0
Dn Type=3
Dn Slope=0.005
Boundary for River Rch & Prof#=Stream0578,Reach-1,3
Up Type=0
Dn Type=3
Dn Slope=0.005
Boundary for River Rch & Prof#=Stream0578,Reach-1,4
Up Type=0
Dn Type=3
Dn Slope=0.005
Boundary for River Rch & Prof#=Stream0578,Reach-1,5
Up Type=0
Dn Type=3
Dn Slope=0.005
Boundary for River Rch & Prof#=Stream0578,Reach-1,6
Up Type=0
Dn Type=3
Dn Slope=0.005
Boundary for River Rch & Prof#=Stream0578,Reach-1,7
Up Type=0
Dn Type=3
Dn Slope=0.005

--- Stream0578.g01 (geometry) ---

Geom Title=Existing Conditions
Program Version=4.10

River Reach=Stream0578      ,Reach-1
Reach XY= 30
        2328425.       13668925.      2329211.02     13668925.56
      2330052.34     13669125.22      2330380.93     13668927.24
      2331309.61     13668874.92      2331502.19     13668774.61
      2332128.42      13668832.8      2332604.91     13669075.11
      2333019.75     13668819.56      2333034.14     13668568.25
      2333231.11      13668426.8      2333569.15     13668426.54
      2333699.88     13668575.54      2334474.99     13668282.53
      2335169.74     13668422.92      2336314.72     13667335.16
      2336276.84     13666981.12      2336465.32     13666735.78
      2337080.93     13666327.24      2337754.97     13666374.94
      2337952.16     13666274.68      2338108.76     13666307.77
      2338185.75     13666634.71      2338945.39     13667294.84
      2339108.21     13667558.56      2339664.53     13667815.18
      2339671.47     13668023.55      2339475.86     13668264.68
      2339738.74     13668338.19        2339775.       13668525.

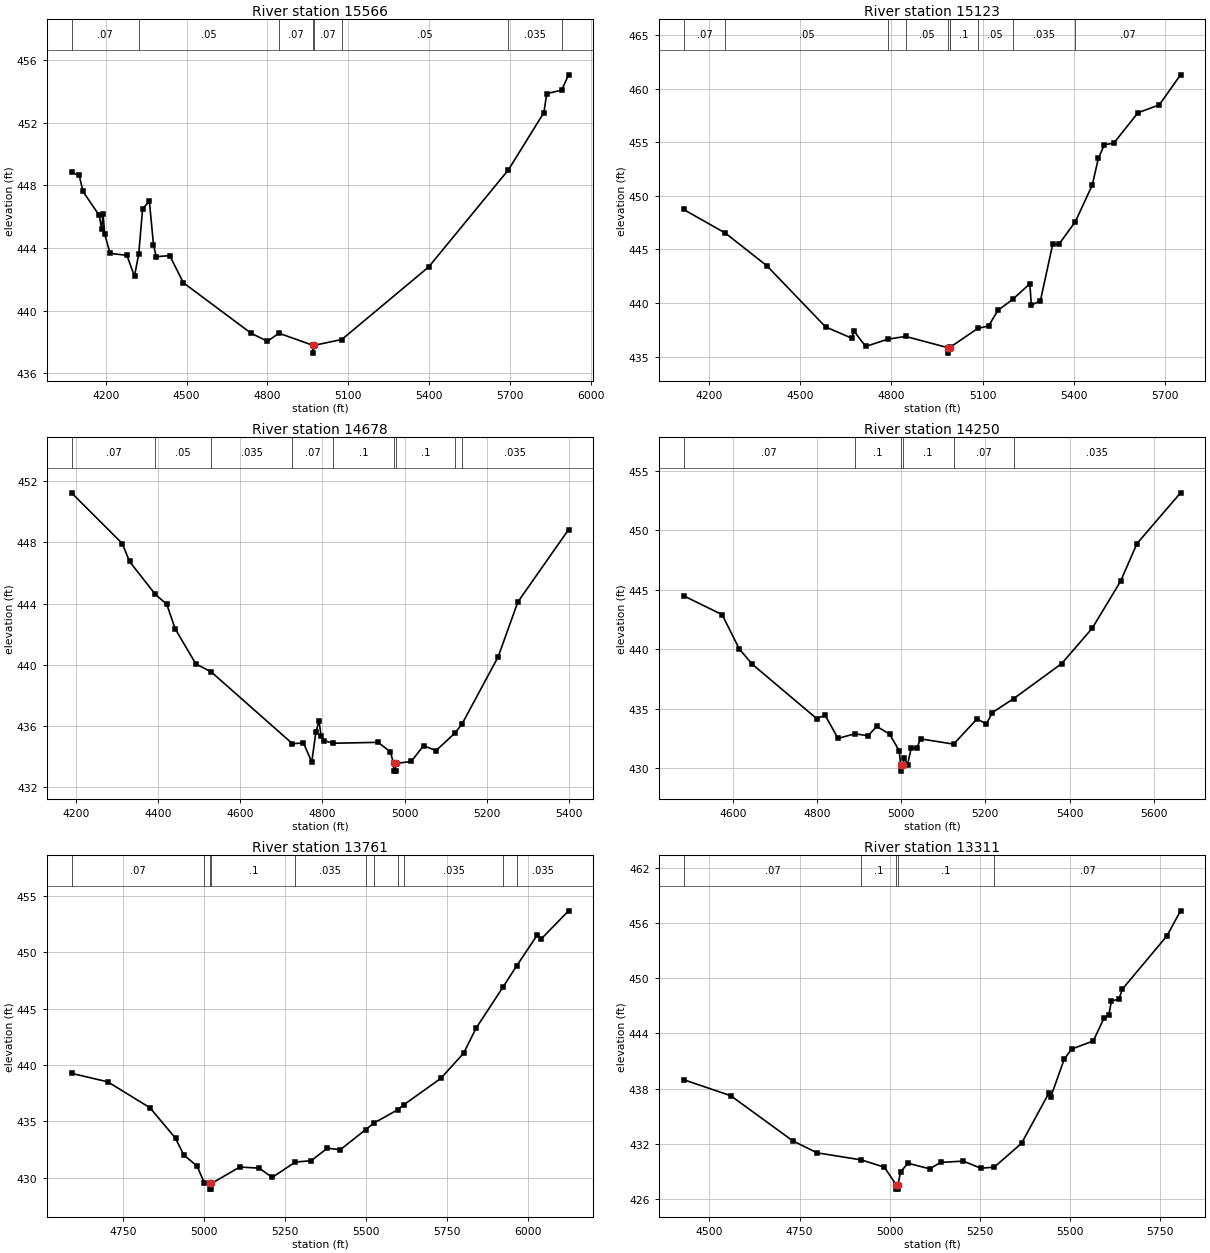
Type RM Length L Ch R = 1 ,15566   ,443,443,443
BEGIN DESCRIPTION:
XS7133
END DESCRIPTION:
XS GIS Cut Line= 2
      2328356.58     13669847.21      2328570.07      13668014.4
#Sta/Elev= 30
  4072.6  448.83  4101.1  448.64  4115.1  447.61  4175.5  446.08  4184.5  445.21
  4189.6   446.2  4195.6  444.89  4215.8  443.65  4278.1  443.53  4306.4  442.19
  4322.2  443.64  4336.6   446.5  4361.6  446.98  4376.9  444.21  4386.9  443.44
  4437.3  443.51  4487.6  441.78  4739.3  438.55  4799.7  438.04  4842.9  438.55
  4968.6  437.78    4969  437.28  4973.8  437.78  5075.9  438.15  5398.7  442.79
  5694.5  448.99  5826.2  452.65  5836.7  453.86  5892.1  454.08  5917.8  455.06
#Mann= 8 ,-1 , 0
  4072.6     .07       0  4322.2     .05       0  4842.9     .07       0
  4968.6     .05       0  4973.8     .07       0  5075.9     .05       0
  5694.5    .035       0  5892.1     .07       0
Bank Sta=4968.6,4973.8
XS Rating Curve= 0 ,0
Exp/Cntr=0.3,0.1

Type RM Length L Ch R = 1 ,15123   ,445,445,445
BEGIN DESCRIPTION:
Stream0578 32.0
END DESCRIPTION:
XS GIS Cut Line= 3
      2329023.24     13669795.13        2328875.       13668925.
      2328919.08     13668175.36
#Sta/Elev= 30
  4117.3  448.73  4254.9  446.52  4391.3  443.47  4584.1  437.77  4671.4   436.7
  4676.5  437.42  4715.9  435.94  4788.6  436.62  4847.3  436.88  4987.2  435.82
  4987.6  435.32  4992.4  435.82  4993.8  435.87    5084  437.62  5120.2  437.86
  5150.2   439.3  5198.8  440.33  5255.5  441.79  5260.5  439.78  5290.5  440.23
  5330.5  445.46  5350.6  445.46    5405  447.58  5460.8  451.01  5480.8  453.51
  5500.8  454.78  5530.9   454.9    5611  457.75  5681.1  458.49  5750.9  461.29
#Mann= 10 ,-1 , 0
  4117.3     .07       0  4254.9     .05       0  4788.6      .1       0
  4847.3     .05       0  4987.2     .05       0  4992.4     .05       0
  4993.8      .1       0    5084     .05       0  5198.8    .035       0
    5405     .07       0
Bank Sta=4987.2,4992.4
XS Rating Curve= 0 ,0
Exp/Cntr=0.3,0.1

Type RM Length L Ch R = 1 ,14678   ,428,428,428
BEGIN DESCRIPTION:
Stream0578 31.0
END DESCRIPTION:
XS GIS Cut Line= 3
        2329175.     13669775.03        2329275.       13668975.
        2329325.     13668574.97
#Sta/Elev= 30
  4189.4  451.23  4312.9  447.92  4330.5  446.75    4393  444.61  4421.2  443.95
  4441.4  442.36  4491.8  440.06  4529.2  439.54    4727  434.85  4753.8   434.9
  4773.9  433.65    4784  435.62  4791.6  436.32  4796.6  435.37  4804.2  435.05
  4825.9  434.88  4935.2  434.94  4965.4  434.32  4972.9  433.56  4973.3  433.06
  4977.7  433.06  4978.1  433.56  5015.8  433.69    5046  434.72  5076.3   434.4
  5122.5  435.55  5139.6  436.14  5227.4  440.52  5275.3   444.1  5398.8  448.83
#Mann= 9 ,-1 , 0
  4189.4     .07       0    4393     .05       0  4529.2    .035       0
    4727     .07       0  4825.9      .1       0  4972.9     .05       0
  4978.1      .1       0  5122.5     .07       0  5139.6    .035       0
Bank Sta=4972.9,4978.1
XS Rating Curve= 0 ,0
Exp/Cntr=0.3,0.1

Type RM Length L Ch R = 1 ,14250   ,489,489,489
BEGIN DESCRIPTION:
Stream0578 30.0
END DESCRIPTION:
XS GIS Cut Line= 3
        2329575.       13669575.        2329675.       13669075.
      2329375.01     13668475.02
#Sta/Elev= 30
  4483.1  444.48  4574.9  442.89  4615.7     440  4646.3  438.73  4799.2  434.16
  4819.6  434.43  4850.2  432.49  4890.5  432.88  4921.6  432.71    4942   433.5
  4972.6  432.85  4995.8  431.43  4998.7  430.24  4999.1  429.74  5004.1  430.24
    5007  430.86  5015.4  430.28  5023.7  431.65  5037.7  431.69  5046.1  432.45
  5124.8  432.01  5180.3  434.13  5202.6   433.7  5216.6  434.66  5267.6  435.84
  5381.5  438.78  5454.2  441.76  5521.3   445.7  5560.4  448.87  5663.8  453.13
#Mann= 6 ,-1 , 0
  4483.1     .07       0  4890.5      .1       0  4998.7     .05       0
  5004.1      .1       0  5124.8     .07       0  5267.6    .035       0
Bank Sta=4998.7,5004.1
XS Rating Curve= 0 ,0
Exp/Cntr=0.3,0.1

Type RM Length L Ch R = 1 ,13761   ,450,450,450
BEGIN DESCRIPTION:
Stream0578 29.0
END DESCRIPTION:
XS GIS Cut Line= 3
        2330242.     13669467.07        2330125.       13669075.
      2330064.91     13667951.46
#Sta/Elev= 30
  4590.9  439.26  4702.7  438.51  4833.1  436.21    4912   433.5  4937.4  432.02
  4978.3  431.04  5000.6  429.57  5017.3  429.49  5017.8  428.99  5022.4  428.99
  5022.8  429.49  5110.2  430.95  5170.3  430.85  5210.4  430.03  5281.5  431.39
  5330.5  431.51  5380.6  432.62  5420.7  432.49  5498.4  434.26  5524.3  434.85
  5597.2  436.02  5616.9  436.48  5731.1  438.82  5801.2  441.05  5839.5  443.26
  5923.6  446.95  5964.6  448.78  6028.2  451.52  6041.5  451.21  6125.2  453.68
#Mann= 11 ,-1 , 0
  4590.9     .07       0  5000.6      .1       0  5017.3     .05       0
  5022.8      .1       0  5281.5    .035       0  5498.4     .07       0
  5524.3    .035       0  5597.2     .07       0  5616.9    .035       0
  5923.6     .07       0  5964.6    .035       0
Bank Sta=5017.3,5022.8
XS Rating Curve= 0 ,0
Exp/Cntr=0.3,0.1

Type RM Length L Ch R = 1 ,13311   ,483,483,483
BEGIN DESCRIPTION:
Stream0578 28.0
END DESCRIPTION:
XS GIS Cut Line= 3
       2330314.9     13669456.67        2330525.       13668925.
        2330425.     13668125.01
#Sta/Elev= 30
  4428.3  438.99  4559.1  437.25  4731.2  432.35  4798.5  431.05  4921.5  430.28
  4985.1  429.49  5017.3  427.61  5017.8  427.11  5022.5  427.11  5022.9  427.61
  5030.2  428.99  5050.4  429.92  5110.8  429.31  5141.1  430.01  5204.1  430.15
  5251.9  429.38  5289.6  429.49  5365.3  432.08  5440.9  437.51  5445.9  437.06
  5483.7  441.21  5503.9   442.3  5564.3  443.19  5594.6  445.73  5607.2  445.98
  5614.7  447.56  5634.9  447.69    5645  448.82  5768.4  454.59  5806.2  457.31
#Mann= 5 ,-1 , 0
  4428.3     .07       0  4921.5      .1       0  5017.3     .05       0
  5022.9      .1       0  5289.6     .07       0
Bank Sta=5017.3,5022.9
XS Rating Curve= 0 ,0
Exp/Cntr=0.3,0.1

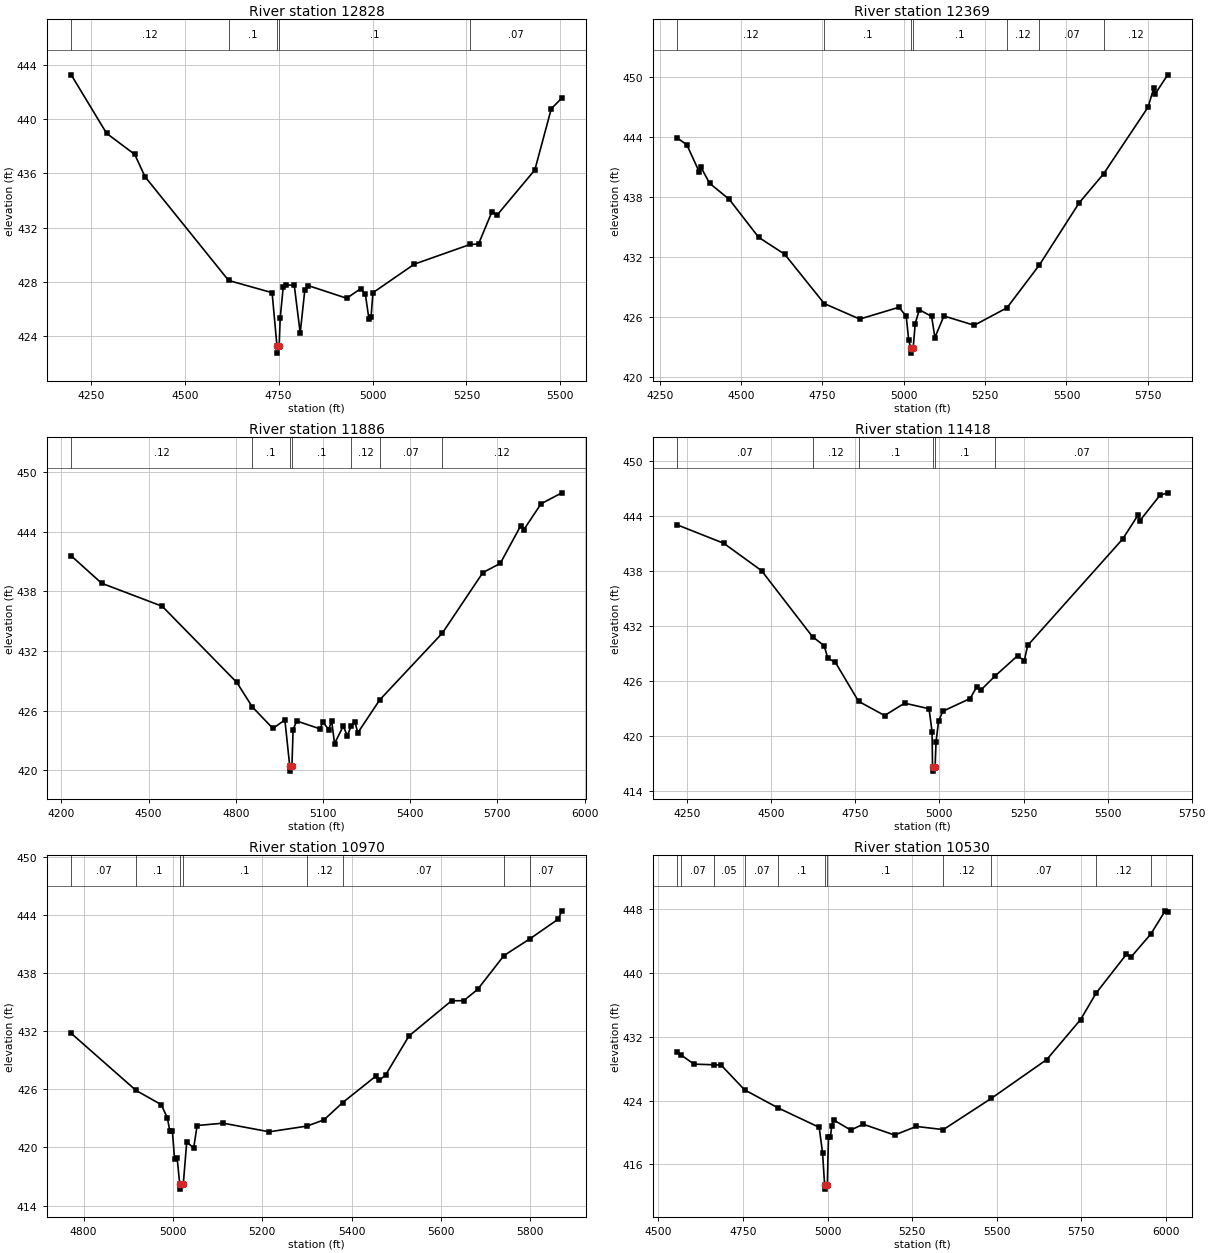
Type RM Length L Ch R = 1 ,12828   ,459,459,459
BEGIN DESCRIPTION:
Stream0578 27.0
END DESCRIPTION:
XS GIS Cut Line= 3
      2331375.01     13669525.02        2330975.       13668825.
      2330675.03     13668425.04
#Sta/Elev= 30
  4197.6  443.26  4291.9  438.95  4366.8   437.4  4394.1  435.76  4616.7  428.12
  4732.5  427.22  4745.5  423.27    4746  422.77  4751.2  423.27  4754.1  425.37
    4762  427.61  4769.9  427.79  4791.5  427.76  4807.3  424.25  4819.6  427.43
  4828.9  427.74  4931.1  426.81  4968.6  427.52  4980.8   427.1  4990.2   425.3
  4995.9  425.42    5001  427.22  5111.1  429.32  5259.4  430.77    5282   430.8
  5317.4  433.15    5332  432.95    5432  436.26  5475.7  440.76  5503.8  441.55
#Mann= 5 ,-1 , 0
  4197.6     .12       0  4616.7      .1       0  4745.5     .05       0
  4751.2      .1       0  5259.4     .07       0
Bank Sta=4745.5,4751.2
XS Rating Curve= 0 ,0
Exp/Cntr=0.3,0.1

Type RM Length L Ch R = 1 ,12369   ,483,483,483
BEGIN DESCRIPTION:
Stream0578 26.0
END DESCRIPTION:
XS GIS Cut Line= 3
        2331425.     13669525.02        2331375.       13668825.
        2331275.     13668025.03
#Sta/Elev= 30
  4303.1  443.93  4333.2  443.22  4370.8  440.54  4375.8  441.01  4403.4  439.36
  4463.5  437.76  4553.8  433.96    4634  432.26  4755.6  427.32  4864.6  425.77
  4984.9  426.95  5007.4  426.07    5015  423.67  5021.4  422.86  5021.9  422.36
  5028.8  422.86  5035.1  425.32  5047.7  426.71  5085.5  426.03  5095.6  423.92
  5123.3  426.08  5216.5  425.15  5317.2   426.9  5416.8  431.19    5539  437.41
    5614  440.31  5750.7  446.99  5768.3  448.89  5773.3  448.35  5811.1  450.23
#Mann= 7 ,-1 , 0
  4303.1     .12       0  4755.6      .1       0  5021.4     .05       0
  5028.8      .1       0  5317.2     .12       0  5416.8     .07       0
    5614     .12       0
Bank Sta=5021.4,5028.8
XS Rating Curve= 0 ,0
Exp/Cntr=0.3,0.1

Type RM Length L Ch R = 1 ,11886   ,468,468,468
BEGIN DESCRIPTION:
Stream0578 25.0
END DESCRIPTION:
XS GIS Cut Line= 3
      2331644.82     13669569.44        2331825.       13668825.
      2331799.79     13667903.38
#Sta/Elev= 30
  4233.7  441.59  4338.4  438.83  4546.9  436.51  4803.7  428.83  4856.5  426.38
  4927.6   424.2  4968.8  425.06  4985.6   420.4  4986.1   419.9  4993.1   420.4
  4997.1  424.08  5009.6  424.95  5089.7  424.16  5099.7  424.85  5119.7  424.08
  5129.7  424.99  5139.7  422.68  5169.7  424.44  5183.6  423.45  5196.9  424.45
  5209.7  424.87  5219.7  423.76  5295.5  427.09  5510.7  433.81  5649.9   439.9
  5709.9  440.83  5779.9  444.61  5789.9  444.18    5850  446.83  5921.6  447.94
#Mann= 7 ,-1 , 0
  4233.7     .12       0  4856.5      .1       0  4985.6     .05       0
  4993.1      .1       0  5196.9     .12       0  5295.5     .07       0
  5510.7     .12       0
Bank Sta=4985.6,4993.1
XS Rating Curve= 0 ,0
Exp/Cntr=0.3,0.1

Type RM Length L Ch R = 1 ,11418   ,448,448,448
BEGIN DESCRIPTION:
Stream0578 24.0
END DESCRIPTION:
XS GIS Cut Line= 3
      2332012.89     13669676.03        2332225.       13668925.
      2332138.81      13668252.1
#Sta/Elev= 30
  4219.9  443.08  4358.8  441.06  4471.2  438.07  4622.6  430.86  4657.4  429.88
  4667.8  428.53  4690.7  428.06  4759.5  423.81    4837  422.26  4896.4  423.61
  4969.1     423  4978.1  420.49  4979.5  416.69    4980  416.19  4987.2  416.69
  4989.9  419.39  4997.7   421.7  5010.4  422.73    5091  424.11  5111.2   425.4
  5122.3  425.01  5165.6  426.58  5232.2  428.78  5252.3  428.25  5262.4  429.91
  5544.7  441.52  5590.4  444.13  5595.4   443.5  5655.6   446.3  5678.7  446.57
#Mann= 6 ,-1 , 0
  4219.9     .07       0  4622.6     .12       0  4759.5      .1       0
  4979.5     .05       0  4987.2      .1       0  5165.6     .07       0
Bank Sta=4979.5,4987.2
XS Rating Curve= 0 ,0
Exp/Cntr=0.3,0.1

Type RM Length L Ch R = 1 ,10970   ,440,440,440
BEGIN DESCRIPTION:
Stream0578 23.0
END DESCRIPTION:
XS GIS Cut Line= 3
      2332725.01     13669275.02        2332625.       13669075.
      2332174.98     13668324.97
#Sta/Elev= 30
  4772.3  431.79  4917.2   425.9  4973.6  424.43  4987.5  423.08  4993.1  421.69
  4998.8  421.69  5003.7  418.81  5009.5   418.9  5015.3   416.2  5015.8   415.7
  5023.2   416.2  5030.9  420.56  5046.5  419.95  5054.2  422.27  5112.5  422.51
  5215.6  421.62  5300.1  422.21    5338  422.85  5380.1  424.64  5454.6  427.38
  5462.4  426.95    5476  427.48  5528.5  431.52  5623.7  435.15  5650.9  435.16
    5682  436.32  5741.1  439.82  5799.5  441.56  5862.8  443.59  5870.6  444.44
#Mann= 8 ,-1 , 0
  4772.3     .07       0  4917.2      .1       0  5015.3     .05       0
  5023.2      .1       0  5300.1     .12       0  5380.1     .07       0
  5741.1     .12       0  5799.5     .07       0
Bank Sta=5015.3,5023.2
XS Rating Curve= 0 ,0
Exp/Cntr=0.3,0.1

Type RM Length L Ch R = 1 ,10530   ,460,460,460
BEGIN DESCRIPTION:
Stream0578 22.0
END DESCRIPTION:
XS GIS Cut Line= 3
        2332975.     13669275.01        2332975.       13668825.
        2332175.       13668225.
#Sta/Elev= 30
  4555.4  430.06  4567.2  429.73  4605.4  428.58  4664.4   428.5  4685.4  428.47
  4754.8  425.36  4854.5  423.08  4975.4  420.66  4985.4  417.44  4991.5  413.41
    4992  412.91  4999.4  413.41  5002.9  419.44  5008.5  419.44  5012.7  420.86
  5018.9  421.56  5068.9  420.31  5105.4  421.05  5198.1  419.69  5262.7  420.77
  5342.2  420.37  5484.2  424.29  5648.1  429.16  5748.1  434.17  5793.5  437.46
  5883.5  442.36  5898.1  442.06  5955.6  444.89  5998.1   447.8  6005.4  447.65
#Mann= 11 ,-1 , 0
  4555.4     .05       0  4567.2     .07       0  4664.4     .05       0
  4754.8     .07       0  4854.5      .1       0  4991.5     .05       0
  4999.4      .1       0  5342.2     .12       0  5484.2     .07       0
  5793.5     .12       0  5955.6     .07       0
Bank Sta=4991.5,4999.4
XS Rating Curve= 0 ,0
Exp/Cntr=0.3,0.1

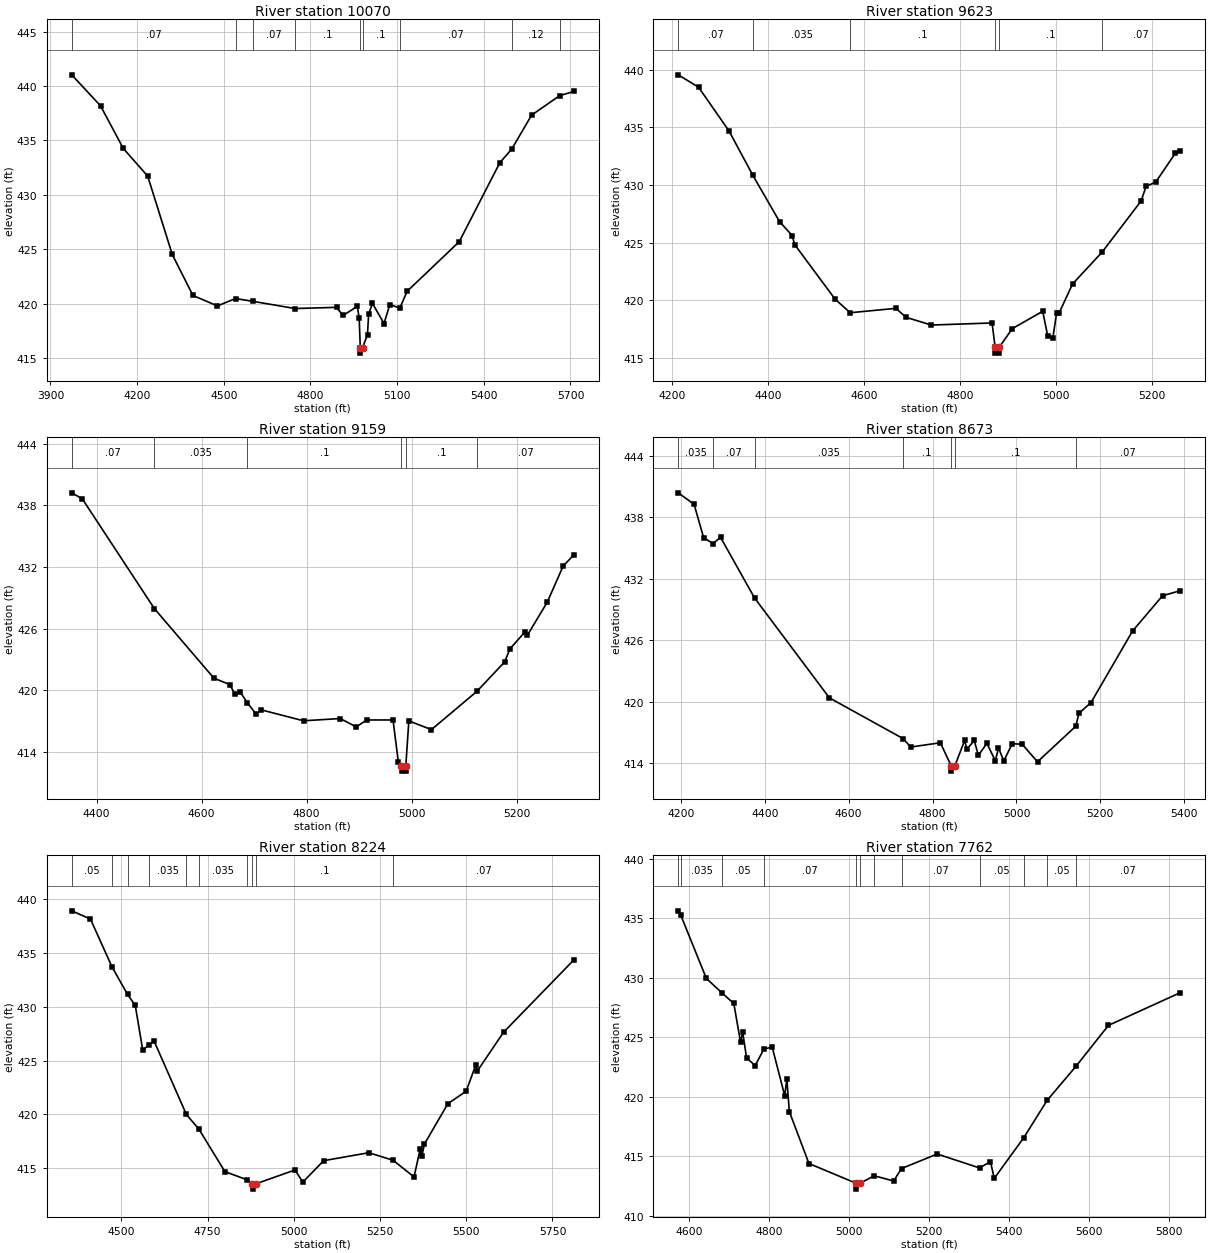
Type RM Length L Ch R = 1 ,10070   ,447,447,447
BEGIN DESCRIPTION:
Stream0578 21.0
END DESCRIPTION:
XS GIS Cut Line= 3
      2333774.98     13669274.97        2333125.       13668475.
      2333088.13      13667768.9
#Sta/Elev= 30
  3973.8  441.03  4073.6  438.17  4151.9  434.27  4236.7  431.71  4321.6  424.51
  4393.3  420.74    4478  419.78  4540.7  420.46  4601.2   420.2  4746.7  419.54
  4890.3  419.65  4912.6   418.9  4962.2  419.74  4968.6  418.66  4972.5  415.94
    4973  415.44  4980.5  415.94  4997.4  417.15  5001.3  419.04  5014.6  420.01
  5054.6  418.16  5074.6  419.91  5109.2  419.58  5134.7  421.13    5315  425.69
  5455.2  432.94  5496.8  434.21  5565.3  437.32    5662  439.11  5711.6   439.5
#Mann= 9 ,-1 , 0
  3973.8     .07       0  4540.7      .1       0  4601.2     .07       0
  4746.7      .1       0  4972.5     .05       0  4980.5      .1       0
  5109.2     .07       0  5496.8     .12       0    5662     .07       0
Bank Sta=4972.5,4980.5
XS Rating Curve= 0 ,0
Exp/Cntr=0.3,0.1

Type RM Length L Ch R = 1 ,9623    ,464,464,464
BEGIN DESCRIPTION:
Stream0578 20.0
END DESCRIPTION:
XS GIS Cut Line= 3
      2333775.02     13669175.05        2333525.       13668425.
      2333575.01     13668174.97
#Sta/Elev= 30
  4213.2  439.57  4255.4   438.5  4318.7  434.71  4368.6  430.84  4424.1  426.82
  4450.4  425.61  4455.7  424.82    4540  420.07  4571.4   418.9  4666.5  419.28
  4687.6   418.5  4740.3  417.83  4866.8  418.01  4873.2  415.89  4873.7  415.39
    4881  415.39  4881.5  415.89  4908.9  417.52  4972.2  419.02  4982.7  416.88
  4993.3   416.7  5001.2  418.88  5006.4  418.88  5034.4   421.4  5095.8  424.16
  5177.2  428.61  5187.4  429.87  5207.8  430.26  5248.6  432.77  5258.8  432.95
#Mann= 6 ,-1 , 0
  4213.2     .07       0  4368.6    .035       0  4571.4      .1       0
  4873.2     .05       0  4881.5      .1       0  5095.8     .07       0
Bank Sta=4873.2,4881.5
XS Rating Curve= 0 ,0
Exp/Cntr=0.3,0.1

Type RM Length L Ch R = 1 ,9159    ,486,486,486
BEGIN DESCRIPTION:
Stream0578 19.0
END DESCRIPTION:
XS GIS Cut Line= 3
        2333825.     13669125.01        2333875.       13668475.
      2333925.01     13668174.96
#Sta/Elev= 30
  4352.8  439.23  4372.9  438.64  4510.1  427.96  4623.6  421.18  4653.7  420.57
  4663.7  419.61  4673.8  419.82  4687.3  418.78  4703.8  417.69  4713.9   418.1
  4794.1  417.04  4864.3  417.26  4894.4  416.44  4914.5  417.12  4964.6  417.12
  4974.6  413.05  4980.4  412.64  4980.9  412.14  4988.4  412.14  4988.9  412.64
  4994.7  417.03  5037.7  416.18  5124.2   419.9  5177.1  422.77  5187.2  424.04
  5215.1  425.65  5220.2  425.35  5258.2  428.58  5288.6  432.11  5308.9  433.19
#Mann= 6 ,-1 , 0
  4352.8     .07       0  4510.1    .035       0  4687.3      .1       0
  4980.4     .05       0  4988.9      .1       0  5124.2     .07       0
Bank Sta=4980.4,4988.9
XS Rating Curve= 0 ,0
Exp/Cntr=0.3,0.1

Type RM Length L Ch R = 1 ,8673    ,449,449,449
BEGIN DESCRIPTION:
Stream0578 18.0
END DESCRIPTION:
XS GIS Cut Line= 3
        2334225.     13669175.02        2334325.       13668375.
      2334024.97     13668124.97
#Sta/Elev= 30
  4193.8   440.4  4231.6  439.28  4254.3  436.02  4276.8  435.45  4294.6  436.06
  4375.7  430.14  4554.1  420.39  4729.6  416.42  4748.1  415.59  4818.6  416.01
  4844.6  413.74  4845.1  413.24  4853.1  413.74  4876.6  416.25  4881.6  415.36
  4899.3  416.23  4909.3  414.78  4929.5  415.95  4949.7  414.25  4957.2   415.5
  4969.8  414.24    4990  415.92  5013.7  415.86  5050.2  414.15  5141.4  417.62
  5149.1  418.89  5177.7  419.93  5276.7  426.91  5348.3  430.36  5390.6  430.85
#Mann= 7 ,-1 , 0
  4193.8    .035       0  4276.8     .07       0  4375.7    .035       0
  4729.6      .1       0  4844.6     .05       0  4853.1      .1       0
  5141.4     .07       0
Bank Sta=4844.6,4853.1
XS Rating Curve= 0 ,0
Exp/Cntr=0.3,0.1

Type RM Length L Ch R = 1 ,8224    ,462,462,462
BEGIN DESCRIPTION:
Stream0578 17.0
END DESCRIPTION:
XS GIS Cut Line= 3
      2334975.01     13668925.02        2334725.       13668325.
      2334625.01     13667525.05
#Sta/Elev= 30
  4355.8  438.94    4410  438.17  4472.2  433.74  4517.5  431.16    4540  430.13
  4561.7  425.96  4580.2  426.48  4594.2  426.84  4688.2  419.98  4724.8   418.6
    4800  414.66  4864.1   413.9  4879.9  413.53  4880.4  413.03  4890.2  413.53
  5003.1  414.81    5026  413.68  5086.4  415.68  5217.5  416.42  5287.4  415.72
  5348.5  414.17  5366.1  416.73  5371.1  416.11  5378.7  417.23  5446.7  420.99
  5499.6  422.14  5527.3  424.57  5532.4  424.04    5608  427.63    5812  434.37
#Mann= 10 ,-1 , 0
  4355.8     .05       0  4472.2    .035       0  4517.5     .05       0
  4580.2    .035       0  4688.2     .07       0  4724.8    .035       0
  4864.1      .1       0  4879.9     .05       0  4890.2      .1       0
  5287.4     .07       0
Bank Sta=4879.9,4890.2
XS Rating Curve= 0 ,0
Exp/Cntr=0.3,0.1

Type RM Length L Ch R = 1 ,7762    ,473,473,473
BEGIN DESCRIPTION:
Stream0578 16.0
END DESCRIPTION:
XS GIS Cut Line= 3
      2334974.99     13668825.04        2335125.       13668425.
      2334774.99     13667674.99
#Sta/Elev= 30
  4573.3  435.62  4579.8  435.24  4643.6  429.94  4683.8  428.69  4712.2  427.84
  4729.1  424.59  4734.4  425.41  4744.2  423.26  4765.6  422.63  4787.9  424.04
  4808.3  424.16  4839.4  420.09  4844.8  421.48    4851  418.76    4900   414.4
  5017.5  412.75    5018  412.25  5027.8  412.75  5063.5  413.37  5111.7  412.93
  5131.4  413.98  5220.5   415.2  5326.3  414.03  5353.7  414.56  5363.1  413.15
  5436.5  416.55  5495.7  419.72  5567.3  422.56  5648.5     426  5828.2  428.75
#Mann= 12 ,-1 , 0
  4573.3     .05       0  4579.8    .035       0  4683.8     .05       0
  4787.9     .07       0  5017.5     .05       0  5027.8     .07       0
  5063.5      .1       0  5131.4     .07       0  5326.3     .05       0
  5436.5     .07       0  5495.7     .05       0  5567.3     .07       0
Bank Sta=5017.5,5027.8
XS Rating Curve= 0 ,0
Exp/Cntr=0.3,0.1

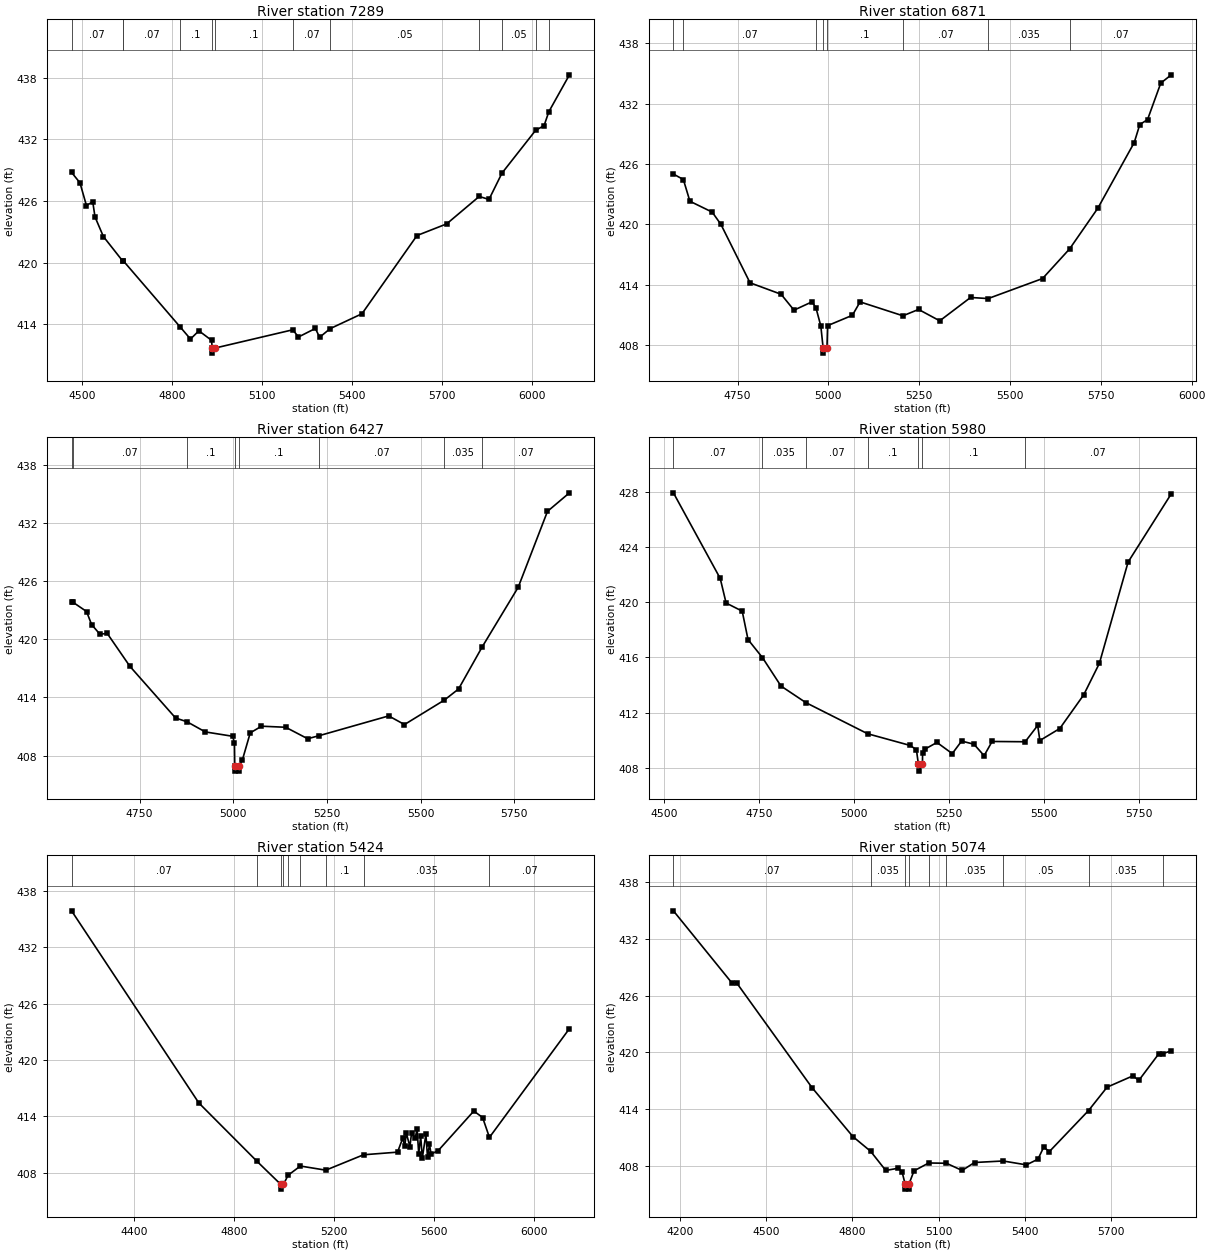
Type RM Length L Ch R = 1 ,7289    ,418,418,418
BEGIN DESCRIPTION:
Stream0578 15.0
END DESCRIPTION:
XS GIS Cut Line= 3
      2335824.98     13668574.98        2335475.       13668175.
      2334675.04     13667375.04
#Sta/Elev= 30
  4463.9  428.77  4491.9  427.76  4513.7  425.54  4534.6  425.92  4542.2  424.44
  4570.2  422.53  4634.6  420.15  4637.2  420.15  4826.2  413.75  4861.1  412.56
  4889.1  413.36  4931.3  412.44  4933.7  411.69  4934.2  411.19  4944.1  411.69
  5202.7  413.46  5221.7  412.76  5278.2  413.59  5292.4  412.73  5327.4  413.57
  5433.8  415.02  5617.6  422.63  5716.6  423.76  5825.4  426.43    5858  426.14
  5901.4   428.7    6014  432.87  6041.9  433.31  6057.9  434.67  6126.7  438.26
#Mann= 12 ,-1 , 0
  4463.9     .07       0  4634.6    .035       0  4637.2     .07       0
  4826.2      .1       0  4933.7     .05       0  4944.1      .1       0
  5202.7     .07       0  5327.4     .05       0  5825.4     .07       0
  5901.4     .05       0    6014     .07       0  6057.9     .05       0
Bank Sta=4933.7,4944.1
XS Rating Curve= 0 ,0
Exp/Cntr=0.3,0.1

Type RM Length L Ch R = 1 ,6871    ,444,444,444
BEGIN DESCRIPTION:
Stream0578 14.0
END DESCRIPTION:
XS GIS Cut Line= 3
      2336175.01       13668075.        2335775.       13667925.
        2335275.     13667125.01
#Sta/Elev= 30
  4573.3  425.01  4600.7  424.47  4618.7  422.31  4680.1  421.23  4704.1  420.01
  4784.2  414.21  4869.7  413.07  4905.3  411.49  4955.1  412.32  4965.8  411.71
  4979.1  409.92  4985.5  407.72    4986  407.22    4996  407.72  4997.8  409.95
    5066  410.98  5087.2  412.31  5205.2  410.93  5248.2  411.56  5306.5  410.43
  5391.4  412.75  5439.7  412.64  5589.5  414.63  5664.1  417.58  5741.7  421.62
  5841.9  428.14  5857.2  429.93  5878.5  430.42    5915  434.05  5943.9  434.87
#Mann= 8 ,-1 , 0
  4573.3    .035       0  4600.7     .07       0  4965.8      .1       0
  4985.5     .05       0    4996      .1       0  5205.2     .07       0
  5439.7    .035       0  5664.1     .07       0
Bank Sta=4985.5,4996
XS Rating Curve= 0 ,0
Exp/Cntr=0.3,0.1

Type RM Length L Ch R = 1 ,6427    ,447,447,447
BEGIN DESCRIPTION:
Stream0578 13.0
END DESCRIPTION:
XS GIS Cut Line= 3
        2336225.     13668024.99        2336075.       13667625.
      2335324.98     13667124.99
#Sta/Elev= 30
  4568.4  423.87  4572.3  423.81  4608.4  422.86  4621.8  421.52    4644  420.52
  4663.6   420.6  4724.1  417.21  4846.1  411.88  4876.4   411.5  4925.3  410.45
  4998.6     410  5003.1  409.27  5003.9  406.91  5004.4  406.41  5013.9  406.41
  5014.4  406.91  5024.1  407.54  5045.2  410.35  5075.2  411.04  5139.8  410.93
  5198.4  409.75  5228.8  410.06  5414.7   412.1  5456.8  411.21  5563.2  413.73
    5601  414.87  5664.3  419.22  5760.3  425.36  5838.4  433.18    5897  435.09
#Mann= 8 ,-1 , 0
  4568.4    .035       0  4572.3     .07       0  4876.4      .1       0
  5003.9     .05       0  5014.4      .1       0  5228.8     .07       0
  5563.2    .035       0  5664.3     .07       0
Bank Sta=5003.9,5014.4
XS Rating Curve= 0 ,0
Exp/Cntr=0.3,0.1

Type RM Length L Ch R = 1 ,5980    ,556,556,556
BEGIN DESCRIPTION:
Stream0578 12.0
END DESCRIPTION:
XS GIS Cut Line= 3
      2336724.99       13667575.        2336325.       13667325.
      2335525.04     13667075.01
#Sta/Elev= 30
  4524.7  427.93  4647.9  421.72  4663.3  419.94  4705.7  419.35    4721  417.29
    4759  415.98  4807.7  413.92    4873  412.72  5035.7  410.46  5147.8  409.61
    5164   409.3  5169.2  408.25  5169.7  407.75  5179.8  408.25  5180.3  409.03
  5185.5  409.33    5218  409.83  5258.3  409.02  5282.9  409.93  5315.4   409.7
  5342.1  408.87  5363.1   409.9  5450.1  409.88    5483  411.06  5488.8  409.97
  5541.2  410.84  5604.1  413.28  5645.4  415.57  5720.9  422.91  5834.5  427.86
#Mann= 7 ,-1 , 0
  4524.7     .07       0    4759    .035       0    4873     .07       0
  5035.7      .1       0  5169.2     .05       0  5179.8      .1       0
  5450.1     .07       0
Bank Sta=5169.2,5179.8
XS Rating Curve= 0 ,0
Exp/Cntr=0.3,0.1

Type RM Length L Ch R = 1 ,5424    ,350,350,350
BEGIN DESCRIPTION:
Stream0578 11.0
END DESCRIPTION:
XS GIS Cut Line= 3
      2336974.97     13667424.97      2336413.87     13666909.76
       2335638.9     13665952.75
#Sta/Elev= 30
    4150   435.9  4659.6  415.43  4892.1  409.22  4987.7  406.75  4988.2  406.25
  4998.3  406.75  5016.9  407.73    5066  408.71  5167.8  408.27  5318.8  409.91
    5455  410.19  5475.8  411.67  5483.8  410.82  5490.2  412.21  5504.6  410.77
    5511  412.22  5525.4  411.67  5533.4  412.65  5539.8  410.03  5547.7  411.88
  5554.2  409.57  5568.5   412.1    5575  409.66  5582.9  411.01  5589.4  409.98
  5618.1  410.36  5760.4  414.57  5795.6  413.88  5822.9  411.76  6143.2  423.35
#Mann= 9 ,-1 , 0
    4150     .07       0  4892.1    .035       0  4987.7    .035       0
  4998.3    .035       0  5016.9      .1       0    5066    .035       0
  5167.8      .1       0  5318.8    .035       0  5822.9     .07       0
Bank Sta=4987.7,4998.3
XS Rating Curve= 0 ,0
Exp/Cntr=0.3,0.1

Type RM Length L Ch R = 1 ,5074    ,442,442,442
BEGIN DESCRIPTION:
Stream0578 10.0
END DESCRIPTION:
XS GIS Cut Line= 3
      2336974.99     13667374.99        2336625.       13666625.
      2336549.29      13665722.3
#Sta/Elev= 30
  4176.7  434.94  4379.3  427.37  4396.6  427.35  4659.1  416.29  4801.8  411.11
  4863.1  409.57  4916.1  407.54  4960.2  407.78  4972.8   407.4  4983.8  406.07
  4984.3  405.57    4996  405.57  4996.5  406.07  5014.4   407.5  5065.7  408.33
  5127.3   408.3  5181.9  407.54  5225.1  408.38  5324.8  408.54  5405.7  408.13
  5445.9  408.73  5465.9  409.99    5486  409.54    5622  413.86  5686.7  416.33
    5777  417.53  5797.1  417.04  5867.4  419.88  5882.2  419.88  5910.2  420.17
#Mann= 9 ,-1 , 0
  4176.7     .07       0  4863.1    .035       0  4983.8    .035       0
  4996.5    .035       0  5065.7     .07       0  5127.3    .035       0
  5324.8     .05       0    5622    .035       0  5882.2     .05       0
Bank Sta=4983.8,4996.5
XS Rating Curve= 0 ,0
Exp/Cntr=0.3,0.1

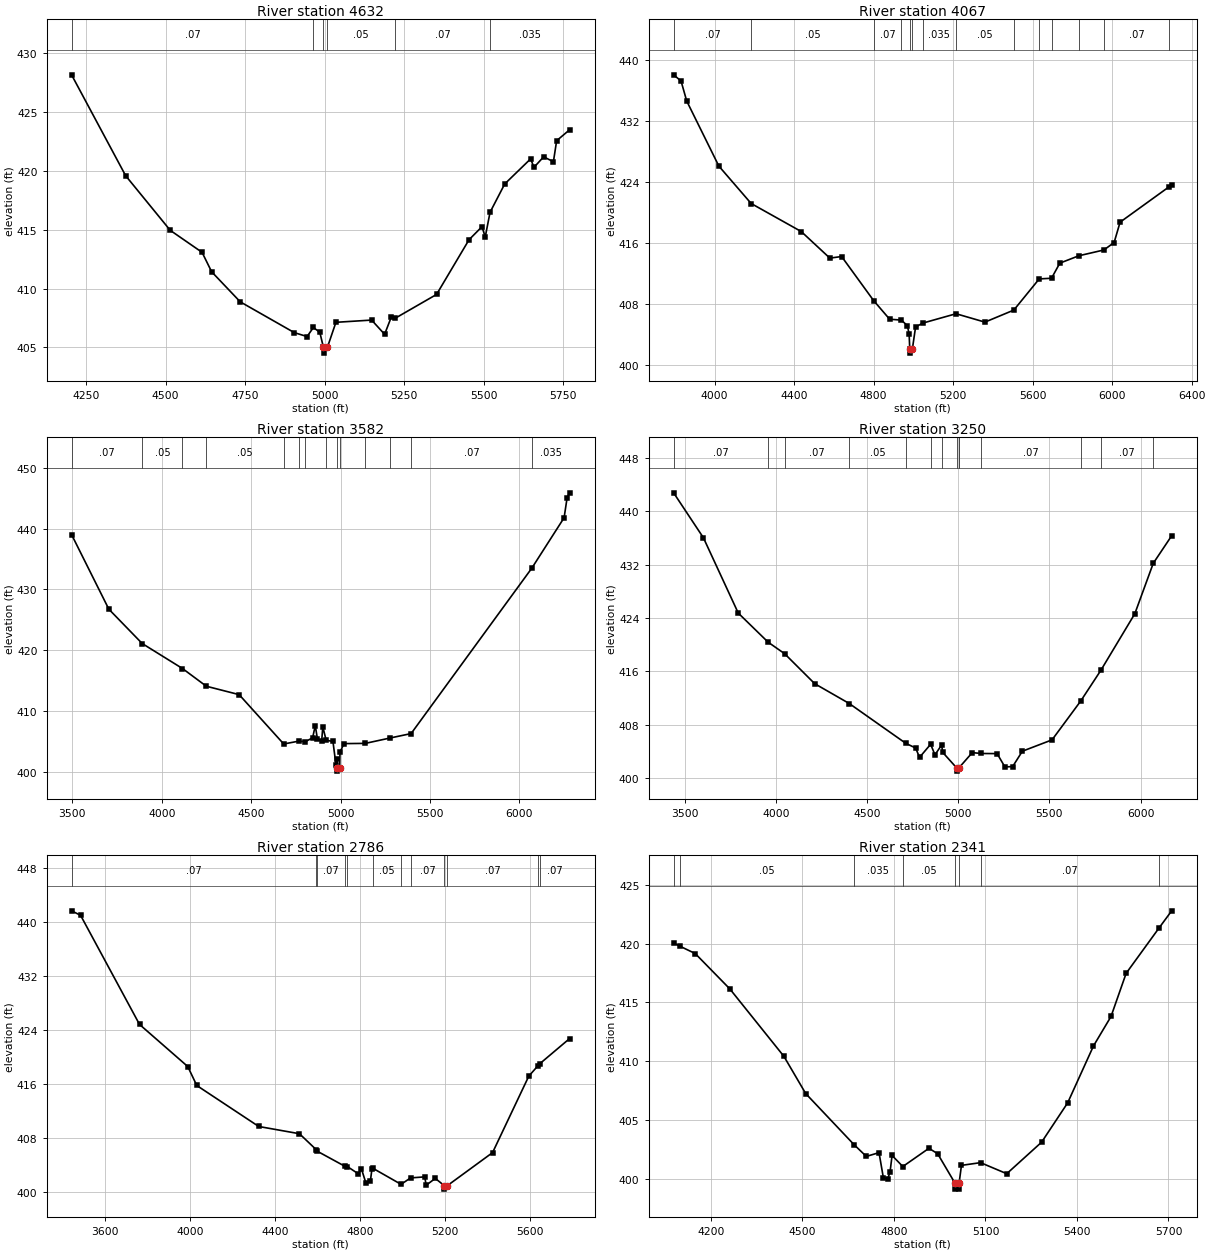
Type RM Length L Ch R = 1 ,4632    ,565,565,565
BEGIN DESCRIPTION:
Stream0578 9.0
END DESCRIPTION:
XS GIS Cut Line= 3
        2336975.     13667175.04        2336975.       13666375.
        2336825.       13665625.
#Sta/Elev= 30
  4204.7  428.17  4374.7  419.59  4514.7  414.95  4614.7  413.08  4644.7  411.43
  4734.7  408.87  4904.7  406.25  4944.7  405.92  4964.5  406.69  4984.7  406.28
  4995.9  405.01  4996.4  404.51  5008.6  405.01  5035.3  407.13  5147.5  407.32
  5188.3  406.11  5208.7  407.54  5220.6  407.46  5351.5   409.5  5453.5  414.15
  5494.2  415.26  5504.4  414.38  5519.5  416.48  5565.6  418.89  5647.2  421.03
  5657.4   420.3    5688   421.2  5718.6  420.78  5728.8  422.57  5769.6   423.5
#Mann= 6 ,-1 , 0
  4204.7     .07       0  4964.5     .05       0  4995.9     .05       0
  5008.6     .05       0  5220.6     .07       0  5519.5    .035       0
Bank Sta=4995.9,5008.6
XS Rating Curve= 0 ,0
Exp/Cntr=0.3,0.1

Type RM Length L Ch R = 1 ,4067    ,485,485,485
BEGIN DESCRIPTION:
Stream0578 8.0
END DESCRIPTION:
XS GIS Cut Line= 3
      2337075.02     13667474.96      2337538.87     13666451.42
       2337007.6     13665175.34
#Sta/Elev= 30
  3793.5  438.09  3830.8  437.28  3859.4  434.65  4021.1  426.11  4183.6   421.2
  4435.6  417.52  4579.6  414.03  4638.8  414.24  4799.7  408.46  4880.4  406.01
  4938.8   405.9  4969.6  405.17  4978.4  404.07  4981.7  402.06  4982.2  401.56
  4994.5  402.06  5010.9  404.99  5046.8   405.5  5214.5  406.73  5359.8  405.63
  5505.2  407.21  5632.9   411.3  5694.9  411.39  5736.6  413.37  5832.4  414.34
  5958.4   415.1  6009.9  416.08  6039.9  418.75  6286.8   423.4  6299.5  423.69
#Mann= 14 ,-1 , 0
  3793.5     .07       0  4183.6     .05       0  4799.7     .07       0
  4938.8     .12       0  4981.7     .05       0  4994.5     .12       0
  5046.8    .035       0  5214.5     .05       0  5505.2     .07       0
  5632.9     .05       0  5694.9    .035       0  5832.4    .063       0
  5958.4     .07       0  6286.8    .035       0
Bank Sta=4981.7,4994.5
XS Rating Curve= 0 ,0
Exp/Cntr=0.3,0.1

Type RM Length L Ch R = 1 ,3582    ,332,332,332
BEGIN DESCRIPTION:
Stream0578 7.0
END DESCRIPTION:
XS GIS Cut Line= 3
      2337124.98     13667525.03      2337939.91     13666316.01
        2338525.     13665124.99
#Sta/Elev= 30
  3495.8  439.01  3704.2  426.75  3890.6  421.11    4116     417  4249.3  414.09
  4432.8  412.71    4682   404.6  4764.9  405.06  4803.1  404.99  4843.6  405.61
  4858.5  407.62  4870.6  405.42  4894.5  405.12  4900.5  407.42  4919.5   405.2
  4957.3  405.03  4974.2  401.18  4979.8   402.1  4981.8  400.64  4982.3  400.14
    4995  400.64  4996.7  403.25  5019.1  404.66  5138.3   404.7  5276.4  405.58
  5394.4  406.31  6069.5   433.5  6249.9  441.78  6266.8  445.08  6280.8  445.87
#Mann= 14 ,-1 , 0
  3495.8     .07       0  3890.6     .05       0    4116     .07       0
  4249.3     .05       0    4682     .07       0  4764.9      .1       0
  4803.1    .035       0  4919.5      .1       0  4981.8     .05       0
    4995      .1       0  5138.3     .07       0  5276.4    .035       0
  5394.4     .07       0  6069.5    .035       0
Bank Sta=4981.8,4995
XS Rating Curve= 0 ,0
Exp/Cntr=0.3,0.1

Type RM Length L Ch R = 1 ,3250    ,464,464,464
BEGIN DESCRIPTION:
Stream0578 6.0
END DESCRIPTION:
XS GIS Cut Line= 3
      2337125.01     13667674.99        2338125.       13666475.
        2339225.       13666075.
#Sta/Elev= 30
  3438.6  442.73  3601.9  436.01  3793.3  424.73    3957  420.38  4047.7  418.65
  4212.4  414.17  4402.1   411.2  4712.4  405.24  4766.3  404.54  4787.8  403.14
  4848.6   405.1  4872.4  403.52  4908.6  404.98  4915.4  403.87  4990.8  401.58
  4991.3  401.08    5004  401.58  5005.5  401.62  5077.1  403.85  5126.8  403.72
  5213.4   403.7    5256  401.71  5298.6  401.76  5351.8  404.06  5514.7  405.76
    5672  411.57  5782.8  416.18  5968.9  424.64  6069.9  432.18  6171.1  436.31
#Mann= 14 ,-1 , 0
  3438.6     .07       0    3957     .05       0  4047.7     .07       0
  4402.1     .05       0  4712.4     .07       0  4848.6    .035       0
  4908.6     .07       0  4990.8     .05       0    5004     .07       0
  5005.5    .035       0  5126.8     .07       0    5672    .035       0
  5782.8     .07       0  6069.9     .05       0
Bank Sta=4990.8,5004
XS Rating Curve= 0 ,0
Exp/Cntr=0.3,0.1

Type RM Length L Ch R = 1 ,2786    ,445,445,445
BEGIN DESCRIPTION:
Stream0578 5.0
END DESCRIPTION:
XS GIS Cut Line= 3
      2337224.99     13667775.01        2338425.       13666775.
      2339025.01     13666274.99
#Sta/Elev= 30
  3442.8   441.6  3485.1  440.94  3762.4  424.81  3989.5  418.58  4031.8  415.78
  4323.4  409.72  4514.8  408.65  4594.2  406.28  4598.9  406.06  4730.2  403.81
  4740.5  403.79    4792  402.72  4806.3  403.47  4827.2  401.39  4848.7   401.7
  4855.8  403.43  4861.5  403.52  4992.8  401.17  5037.8  402.12  5104.4  402.27
  5110.9  401.03  5153.9  402.05  5196.7  400.96  5197.2  400.46    5210  400.96
  5423.4  405.86  5593.9  417.17  5636.4  418.68  5644.9  418.98  5785.9  422.72
#Mann= 12 ,-1 , 0
  3442.8     .07       0  4594.2     .05       0  4598.9     .07       0
  4730.2     .05       0  4740.5    .035       0  4861.5     .05       0
  4992.8    .035       0  5037.8     .07       0  5196.7    .035       0
    5210     .07       0  5636.4    .035       0  5644.9     .07       0
Bank Sta=5196.7,5210
XS Rating Curve= 0 ,0
Exp/Cntr=0.3,0.1

Type RM Length L Ch R = 1 ,2341    ,410,410,410
BEGIN DESCRIPTION:
Stream0578 4.0
END DESCRIPTION:
XS GIS Cut Line= 3
      2338025.02     13667674.98        2338725.       13667075.
      2339175.03     13666524.97
#Sta/Elev= 30
  4077.9  420.06    4098  419.79  4148.7  419.16  4262.3  416.15  4439.5  410.42
  4510.9  407.26  4668.9  402.93  4709.5  401.92  4751.2  402.24  4765.5  400.09
  4779.8  400.01  4787.4  400.62    4794     402  4829.2  401.06  4914.8  402.61
  4943.3  402.15  5000.3  399.64  5000.8  399.14  5013.1  399.14  5013.6  399.64
  5021.4  401.16    5084  401.39  5169.9  400.45  5284.1  403.13  5369.5  406.47
  5454.2  411.31  5511.6  413.81  5561.2  417.48  5669.8  421.36  5710.5  422.79
#Mann= 8 ,-1 , 0
  4077.9     .07       0    4098     .05       0  4668.9    .035       0
  4829.2     .05       0  5000.3     .05       0  5013.6     .05       0
    5084     .07       0  5669.8    .035       0
Bank Sta=5000.3,5013.6
XS Rating Curve= 0 ,0
Exp/Cntr=0.3,0.1