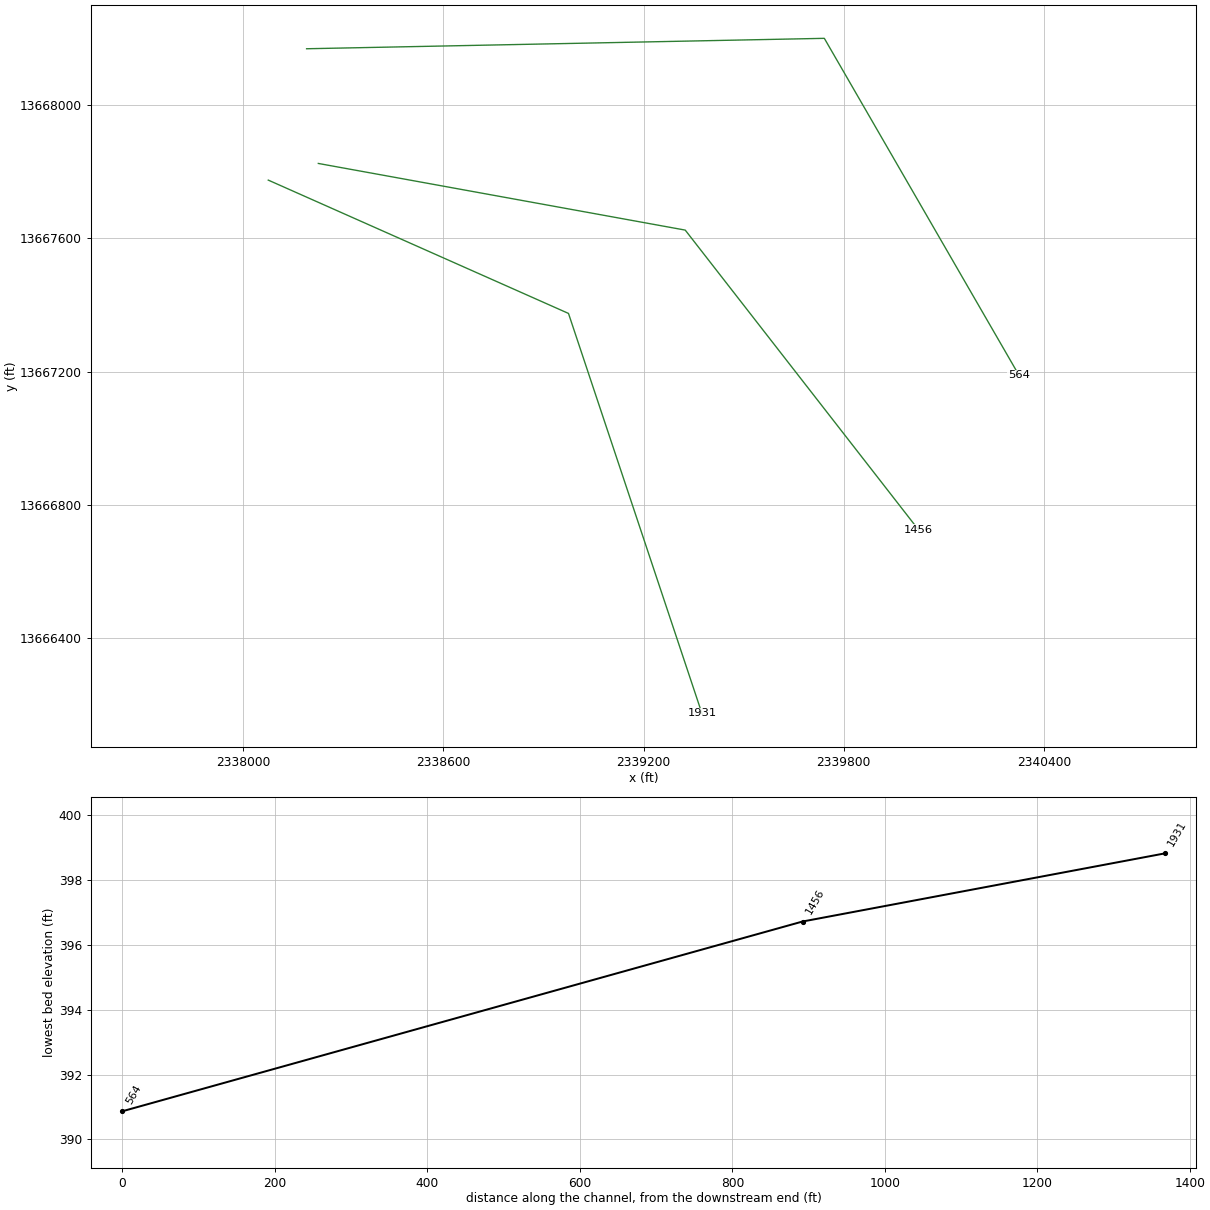
HEC-RAS study Stream0578.prj: Stream0578 Base Level Engineering

--- Stream0578.g01 (geometry) --- (continued)

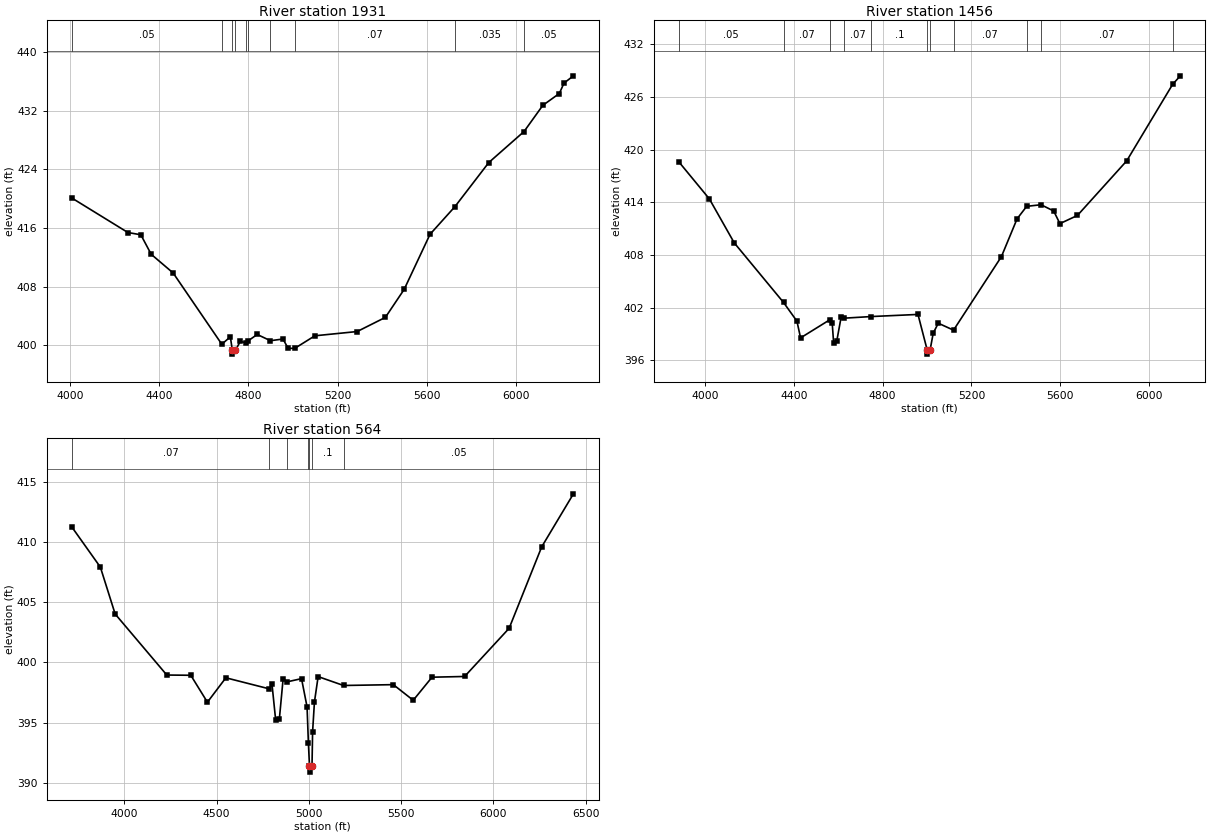
Type RM Length L Ch R = 1 ,1931    ,475,475,475
BEGIN DESCRIPTION:
Stream0578 3.0
END DESCRIPTION:
XS GIS Cut Line= 3
      2338075.02     13667774.99        2338975.       13667375.
      2339375.01     13666174.98
#Sta/Elev= 30
  4007.4  420.11  4259.1   415.4  4317.2  415.09  4363.7  412.43  4462.2  409.88
  4680.3  400.17  4718.7  401.18  4727.6  399.32  4728.1  398.82  4741.2  399.32
  4763.1  400.55  4789.4  400.36  4798.8  400.64  4839.1   401.5  4898.5  400.65
  4954.6  400.88  4977.9  399.61  5007.6  399.61  5097.7  401.32  5287.4   401.9
  5413.9  403.83  5498.2  407.65  5614.2  415.16  5725.6  418.92  5877.7  424.94
  6035.8  429.17  6120.1  432.74  6193.9  434.35    6215  435.77  6257.2  436.76
#Mann= 10 ,-1 , 0
  4007.4     .05       0  4680.3    .035       0  4727.6     .05       0
  4741.2    .035       0  4789.4     .05       0  4798.8     .07       0
  4898.5     .05       0  5007.6     .07       0  5725.6    .035       0
  6035.8     .05       0
Bank Sta=4727.6,4741.2
XS Rating Curve= 0 ,0
Exp/Cntr=0.3,0.1

Type RM Length L Ch R = 1 ,1456    ,892,892,892
BEGIN DESCRIPTION:
Stream0578 2.0
END DESCRIPTION:
XS GIS Cut Line= 3
      2338225.04     13667824.99        2339325.       13667625.
      2340025.02     13666724.98
#Sta/Elev= 30
    3882  418.64  4020.4  414.39  4132.2  409.39  4354.2   402.6  4414.3  400.48
  4430.8  398.57  4561.6  400.62  4573.1  400.28  4579.5  398.03  4593.4  398.17
  4613.8  400.99  4624.2  400.81  4749.6     401  4959.3  401.24  5000.4  397.22
  5000.9  396.72    5014  397.22    5028  399.12  5050.7  400.24  5119.3  399.45
  5334.8  407.82  5405.4  412.13  5448.6  413.55  5513.2  413.73  5570.1  413.02
  5598.1  411.58  5676.9  412.51  5898.6  418.72  6105.8  427.45  6140.2  428.41
#Mann= 11 ,-1 , 0
    3882     .05       0  4354.2     .07       0  4561.6    .035       0
  4624.2     .07       0  4749.6      .1       0  5000.4     .05       0
    5014      .1       0  5119.3     .07       0  5448.6    .035       0
  5513.2     .07       0  6105.8    .035       0
Bank Sta=5000.4,5014
XS Rating Curve= 0 ,0
Exp/Cntr=0.3,0.1

Type RM Length L Ch R = 1 ,564     ,0,0,0
BEGIN DESCRIPTION:
Stream0578 1.0
END DESCRIPTION:
XS GIS Cut Line= 3
      2338189.89     13668169.13        2339742.     13668200.38
      2340325.31     13667189.99
#Sta/Elev= 30
  3714.9  411.28    3870  407.93  3950.1  404.03  4230.1  398.95  4360.1  398.93
  4450.2  396.69  4550.2  398.72  4785.5   397.8  4800.2  398.19  4820.2  395.19
  4840.2   395.3  4860.2  398.58  4883.9  398.39  4960.3  398.65  4990.3   396.3
  4997.6  393.27  5003.5  391.37    5004  390.87  5017.1  391.37  5020.3  394.23
  5030.3  396.71  5050.3  398.82  5188.1  398.08  5457.9  398.15  5565.7  396.85
  5667.6  398.77  5844.2  398.83  6085.5  402.84  6262.1  409.62    6434  414.03
#Mann= 7 ,-1 , 0
  3714.9     .07       0  4785.5    .035       0  4883.9     .07       0
  4997.6      .1       0  5003.5     .05       0  5017.1      .1       0
  5188.1     .05       0
Bank Sta=5003.5,5017.1
XS Rating Curve= 0 ,0
Exp/Cntr=0.3,0.1

Chan Stop Cuts=-1
Use User Specified Reach Order=0
Composite Channel Slope=5