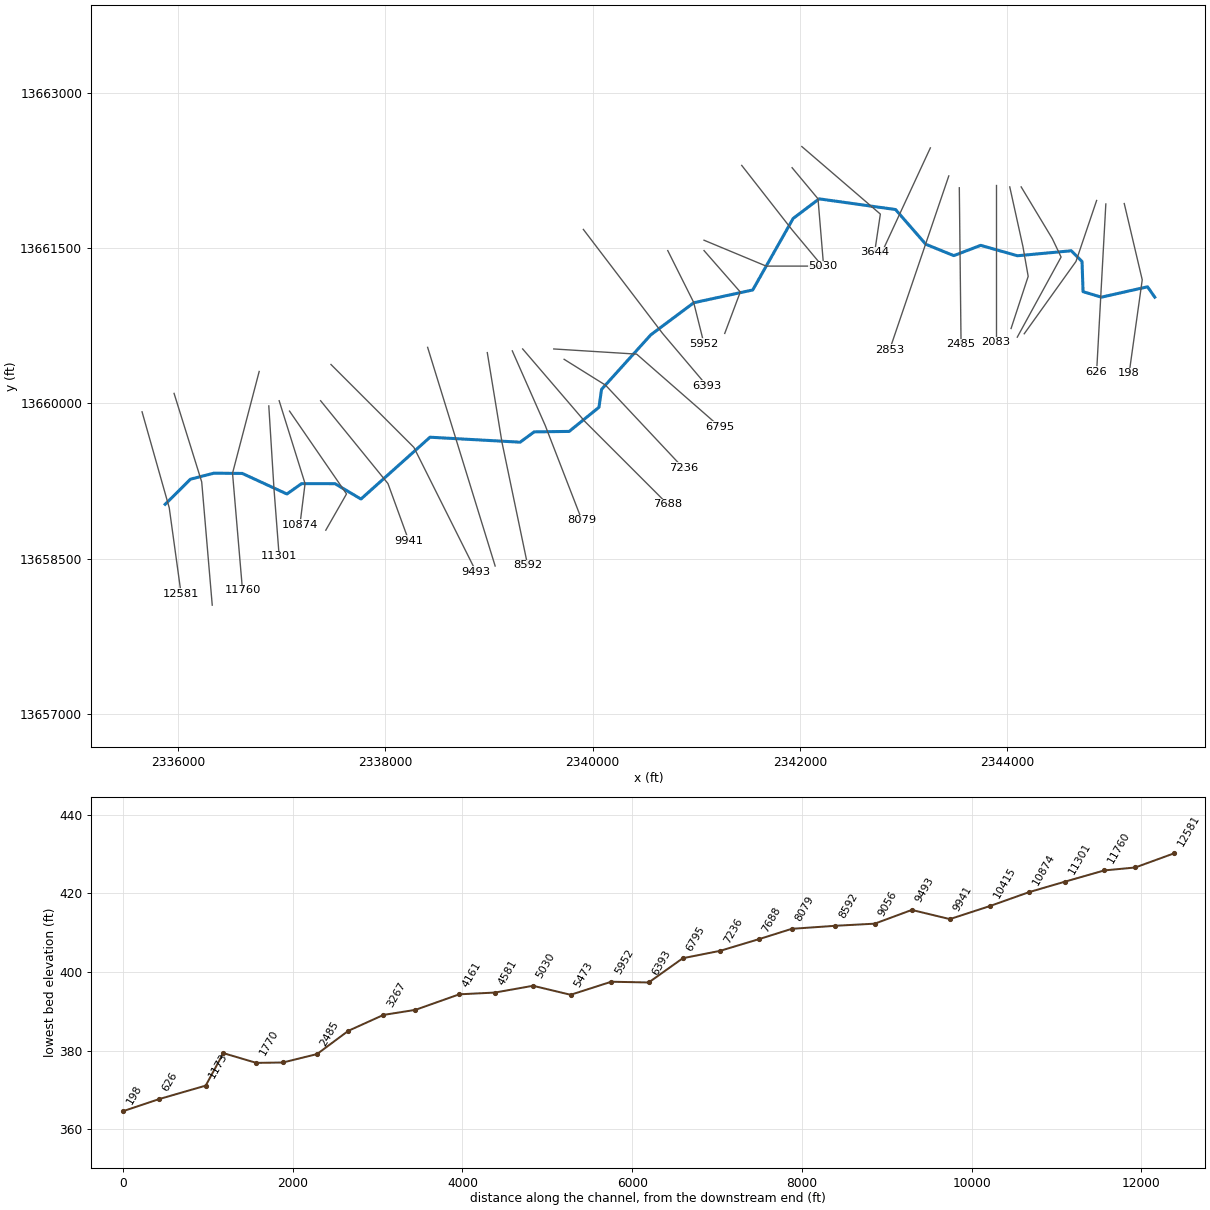
--- Stream0580.prj (project) ---

Proj Title=Stream0580 Base Level Engineering
Current Plan=p01
Default Exp/Contr=0.3,0.1
English Units
Geom File=g01
Flow File=f01
Plan File=p01
BEGIN DESCRIPTION:
Stream0580
END DESCRIPTION:

--- Stream0580.p01 (plan) ---

Plan Title=Multiple Run
Short Identifier=Multiple
Geom File=g01
Flow File=f01
Subcritical Flow
K Sum by GR= 0
Std Step Tol= 0.01
Critical Tol= 0.01
Num of Std Step Trials= 20
Max Error Tol= 0.3
Flow Tol Ratio= 0.001
Split Flow NTrial= 30
Split Flow Tol= 0.02
Split Flow Ratio= 0.02
Log Output Level= 0
Friction Slope Method= 1
Unsteady Friction Slope Method= 2
Unsteady Bridges Friction Slope Method= 1
Parabolic Critical Depth
Global Vel Dist=  1 , 1 , 1
Global Log Level= 0
CheckData=True
Encroach Param= -1, 0, 0, 0
BEGIN DESCRIPTION:
Multiple Run
END DESCRIPTION:

--- Stream0580.f01 (steady flow) ---

Flow Title=Multiple
Number of Profiles=7
Profile Names=10-year,25-year,50-year,1pct_min,100-year,1pct_plu,500-year
River Rch & RM= Stream0580,Reach-1,12581
     617    1004    1356     887    1769    3531    2987
River Rch & RM= Stream0580,Reach-1,10874
    1000    1665    2281    1512    3016    6019    5231
River Rch & RM= Stream0580,Reach-1,6393
    1236    2071    2851    1896    3782    7547    6607
Boundary for River Rch & Prof#=Stream0580,Reach-1,1
Up Type=0
Dn Type=3
Dn Slope=0.005
Boundary for River Rch & Prof#=Stream0580,Reach-1,2
Up Type=0
Dn Type=3
Dn Slope=0.005
Boundary for River Rch & Prof#=Stream0580,Reach-1,3
Up Type=0
Dn Type=3
Dn Slope=0.005
Boundary for River Rch & Prof#=Stream0580,Reach-1,4
Up Type=0
Dn Type=3
Dn Slope=0.005
Boundary for River Rch & Prof#=Stream0580,Reach-1,5
Up Type=0
Dn Type=3
Dn Slope=0.005
Boundary for River Rch & Prof#=Stream0580,Reach-1,6
Up Type=0
Dn Type=3
Dn Slope=0.005
Boundary for River Rch & Prof#=Stream0580,Reach-1,7
Up Type=0
Dn Type=3
Dn Slope=0.005

--- Stream0580.g01 (geometry) ---

Geom Title=Existing Conditions

River Reach=Stream0580,Reach-1
Reach XY= 30
      2335875.00     13659025.00      2336118.93     13659267.51
      2336345.13     13659325.38      2336619.11     13659323.04
      2337049.89     13659124.47      2337190.90     13659224.46
      2337514.56     13659223.96      2337764.31     13659075.74
      2338430.93     13659672.76      2339300.12     13659624.71
      2339435.63     13659724.39      2339773.44     13659728.76
      2340061.39     13659961.79      2340086.23     13660135.02
      2340561.35     13660661.43      2340976.50     13660971.39
      2341545.16     13661094.63      2341935.39     13661785.10
      2342185.62     13661974.40      2342923.42     13661871.18
      2343215.29     13661535.75      2343485.51     13661426.20
      2343745.13     13661525.39      2344099.88     13661424.88
      2344619.12     13661473.04      2344722.95     13661369.16
      2344732.95     13661078.00      2344909.66     13661024.96
      2345355.10     13661125.09      2345425.00     13661025.00

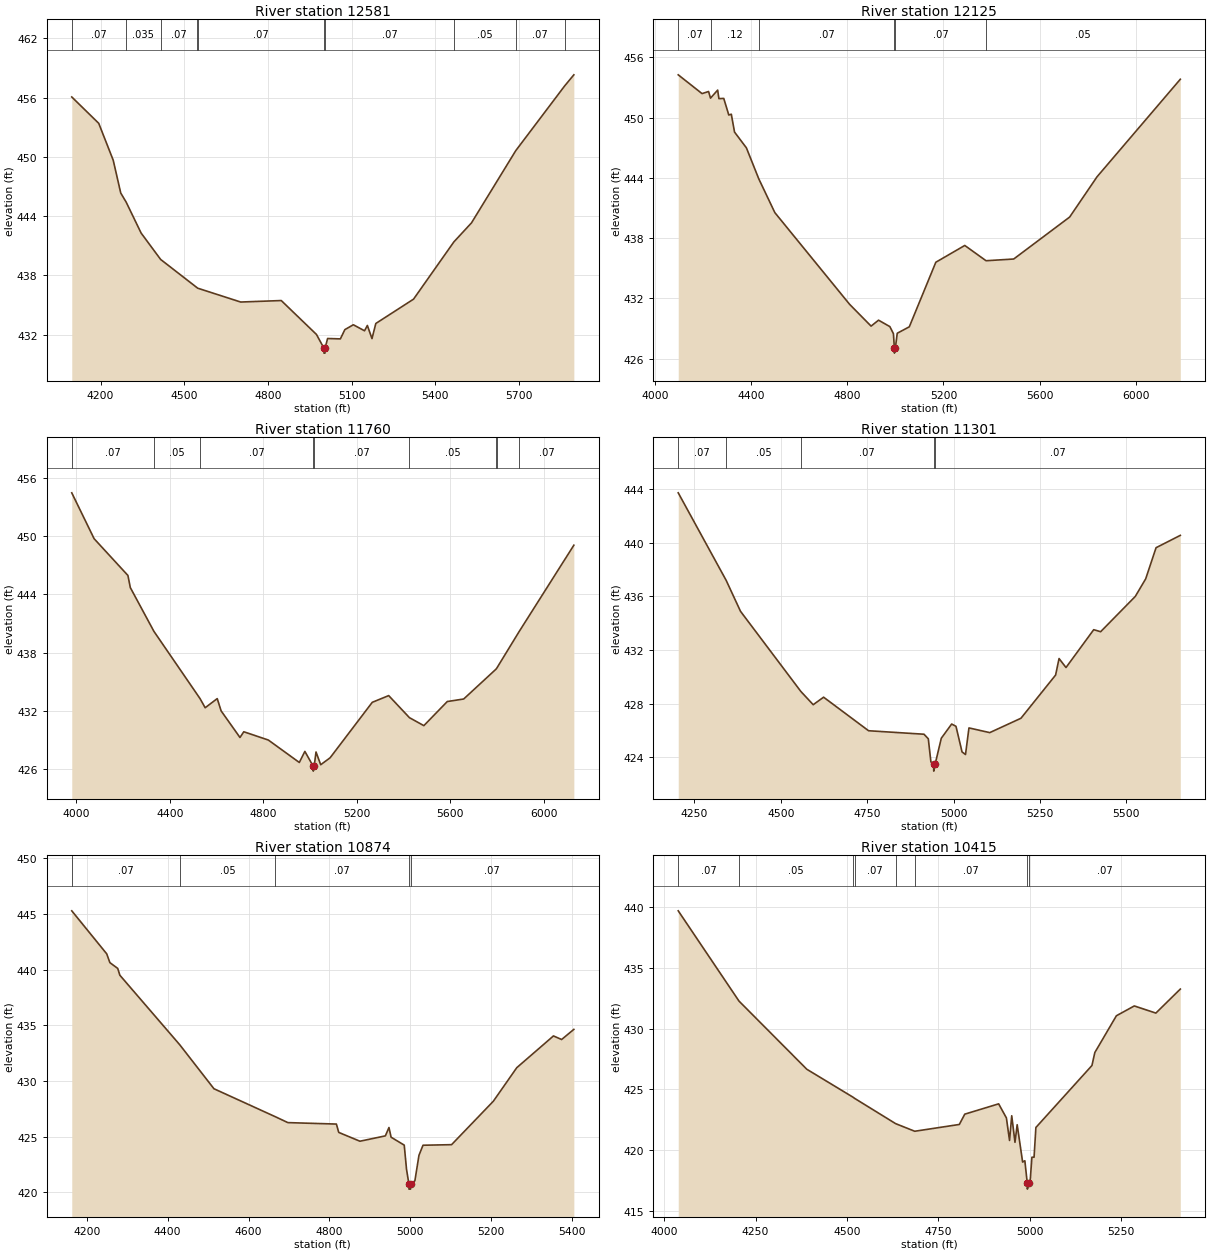
Type RM Length L Ch R = 1,12581,456,456,456
BEGIN DESCRIPTION:
XS7144
END DESCRIPTION:
XS GIS Cut Line= 3
      2335651.86     13659918.10      2335914.32     13658990.98
      2336028.62     13658161.27
#Sta/Elev= 30
  4096.5  456.06  4193.3  453.39  4245.2  449.66  4272.2  446.34  4291.8  445.41
  4345.3  442.29  4415.3  439.62  4546.5  436.75  4548.3  436.71  4702.5  435.31
  4848.0  435.46  4974.3  432.03  5001.1  430.64  5001.3  430.14  5004.8  430.14
  5005.1  430.64  5014.3  431.62  5060.0  431.58  5076.2  432.52  5106.6  433.01
  5146.8  432.40  5156.9  432.94  5173.5  431.61  5187.2  433.14  5322.5  435.60
  5467.1  441.39  5530.4  443.32  5689.3  450.63  5864.7  457.18  5897.6  458.30
#Mann=10,-1,0
  4096.5    0.07       0  4291.8   0.035       0  4415.3    0.07       0
  4546.5   0.035       0  4548.3    0.07       0  5001.1    0.05       0
  5005.1    0.07       0  5467.1    0.05       0  5689.3    0.07       0
  5864.7    0.05       0
Bank Sta=5001.1,5005.1
Exp/Cntr=0.3,0.1

Type RM Length L Ch R = 1,12125,365,365,365
BEGIN DESCRIPTION:
Stream0580 27.0
END DESCRIPTION:
XS GIS Cut Line= 3
      2335960.90     13660095.87      2336227.60     13659240.76
      2336329.19     13658051.22
#Sta/Elev= 30
  4096.3  454.27  4195.4  452.40  4222.6  452.61  4230.6  451.95  4260.4  452.75
  4265.6  451.90  4285.8  451.92  4306.7  450.27  4317.2  450.35  4330.6  448.57
  4380.0  447.00  4431.4  443.92  4498.4  440.55  4809.5  431.42  4898.9  429.25
  4930.0  429.84  4977.1  429.20  4992.0  428.49  4995.8  427.06  4996.1  426.56
  4999.9  427.06  5007.8  428.54  5058.0  429.18  5168.4  435.61  5288.9  437.28
  5377.4  435.76  5492.5  435.93  5725.4  440.11  5839.4  444.12  6185.9  453.83
#Mann=6,-1,0
  4096.3    0.07       0  4230.6    0.12       0  4431.4    0.07       0
  4995.8    0.05       0  4999.9    0.07       0  5377.4    0.05       0
Bank Sta=4995.8,4999.9
Exp/Cntr=0.3,0.1

Type RM Length L Ch R = 1,11760,459,459,459
BEGIN DESCRIPTION:
Stream0580 26.0
END DESCRIPTION:
XS GIS Cut Line= 3
      2336782.16     13660307.54      2336525.00     13659325.00
      2336621.30     13658195.13
#Sta/Elev= 30
  3980.0  454.44  4075.7  449.72  4220.4  445.94  4230.7  444.69  4331.7  440.19
  4529.5  433.26  4551.1  432.33  4602.8  433.27  4619.4  432.01  4700.2  429.27
  4716.5  429.86  4821.5  429.01  4954.3  426.70  4978.0  427.84  5013.7  426.31
  5013.9  425.81  5017.8  426.31  5025.7  427.78  5045.8  426.47  5086.0  427.18
  5266.6  432.89  5336.9  433.58  5425.7  431.31  5487.4  430.49  5587.8  432.97
  5658.0  433.23  5796.4  436.30  5800.1  436.42  5894.7  440.14  6129.6  449.05
#Mann=9,-1,0
  3980.0    0.07       0  4331.7    0.05       0  4529.5    0.07       0
  5013.7    0.05       0  5017.8    0.07       0  5425.7    0.05       0
  5796.4    0.07       0  5800.1    0.05       0  5894.7    0.07       0
Bank Sta=5013.7,5017.8
Exp/Cntr=0.3,0.1

Type RM Length L Ch R = 1,11301,427,427,427
BEGIN DESCRIPTION:
Stream0580 25.0
END DESCRIPTION:
XS GIS Cut Line= 3
      2336875.00     13659974.97      2336925.00     13659175.00
      2336975.00     13658525.05
#Sta/Elev= 30
  4203.1  443.72  4342.0  437.19  4383.4  434.89  4558.0  428.92  4593.8  427.93
  4623.9  428.49  4754.1  425.99  4914.5  425.73  4927.0  425.39  4934.5  423.67
  4942.4  423.48  4942.7  422.98  4946.6  423.48  4964.6  425.43  4994.6  426.49
  5007.1  426.32  5024.7  424.41  5034.7  424.22  5044.7  426.20  5104.9  425.85
  5195.2  426.92  5295.5  430.14  5305.5  431.37  5325.6  430.70  5405.8  433.52
  5425.9  433.37  5526.2  436.00  5556.3  437.31  5586.3  439.63  5656.5  440.55
#Mann=5,-1,0
  4203.1    0.07       0  4342.0    0.05       0  4558.0    0.07       0
  4942.4    0.05       0  4946.6    0.07       0
Bank Sta=4942.4,4946.6
Exp/Cntr=0.3,0.1

Type RM Length L Ch R = 1,10874,459,459,459
BEGIN DESCRIPTION:
Stream0580 24.0
END DESCRIPTION:
XS GIS Cut Line= 3
      2336975.01     13660024.96      2337225.00     13659225.00
      2337175.00     13658825.02
#Sta/Elev= 30
  4162.9  445.27  4249.3  441.41  4257.1  440.62  4276.5  440.10  4281.8  439.49
  4429.8  433.25  4514.4  429.30  4666.1  426.79  4697.2  426.26  4817.1  426.13
  4822.9  425.38  4875.3  424.59  4938.1  425.07  4947.1  425.82  4952.3  424.95
  4984.8  424.24  4990.5  422.06  4996.2  420.79  4996.5  420.29  5000.3  420.29
  5000.6  420.79  5011.1  421.03  5021.2  423.32  5031.2  424.23  5101.8  424.28
  5205.1  428.18  5263.0  431.19  5353.7  434.04  5373.9  433.72  5404.1  434.63
#Mann=5,-1,0
  4162.9    0.07       0  4429.8    0.05       0  4666.1    0.07       0
  4996.2    0.05       0  5000.6    0.07       0
Bank Sta=4996.2,5000.6
Exp/Cntr=0.3,0.1

Type RM Length L Ch R = 1,10415,474,474,474
BEGIN DESCRIPTION:
Stream0580 23.0
END DESCRIPTION:
XS GIS Cut Line= 3
      2337075.00     13659925.00      2337625.00     13659125.00
      2337425.02     13658775.03
#Sta/Elev= 30
  4038.5  439.71  4204.8  432.27  4390.4  426.65  4516.1  424.36  4521.8  424.24
  4633.3  422.17  4685.7  421.54  4807.7  422.10  4822.6  422.95  4915.3  423.80
  4936.5  422.64  4945.1  420.78  4951.1  422.82  4960.0  420.63  4966.0  422.08
  4980.9  419.00  4987.0  419.11  4993.6  417.27  4993.9  416.77  4998.0  417.27
  5001.9  417.58  5006.3  419.40  5012.2  419.40  5017.2  421.85  5170.6  426.96
  5178.5  428.03  5237.5  431.06  5286.5  431.87  5345.5  431.28  5412.4  433.26
#Mann=8,-1,0
  4038.5    0.07       0  4204.8    0.05       0  4516.1   0.035       0
  4521.8    0.07       0  4633.3   0.035       0  4685.7    0.07       0
  4993.6    0.05       0  4998.0    0.07       0
Bank Sta=4993.6,4998
Exp/Cntr=0.3,0.1

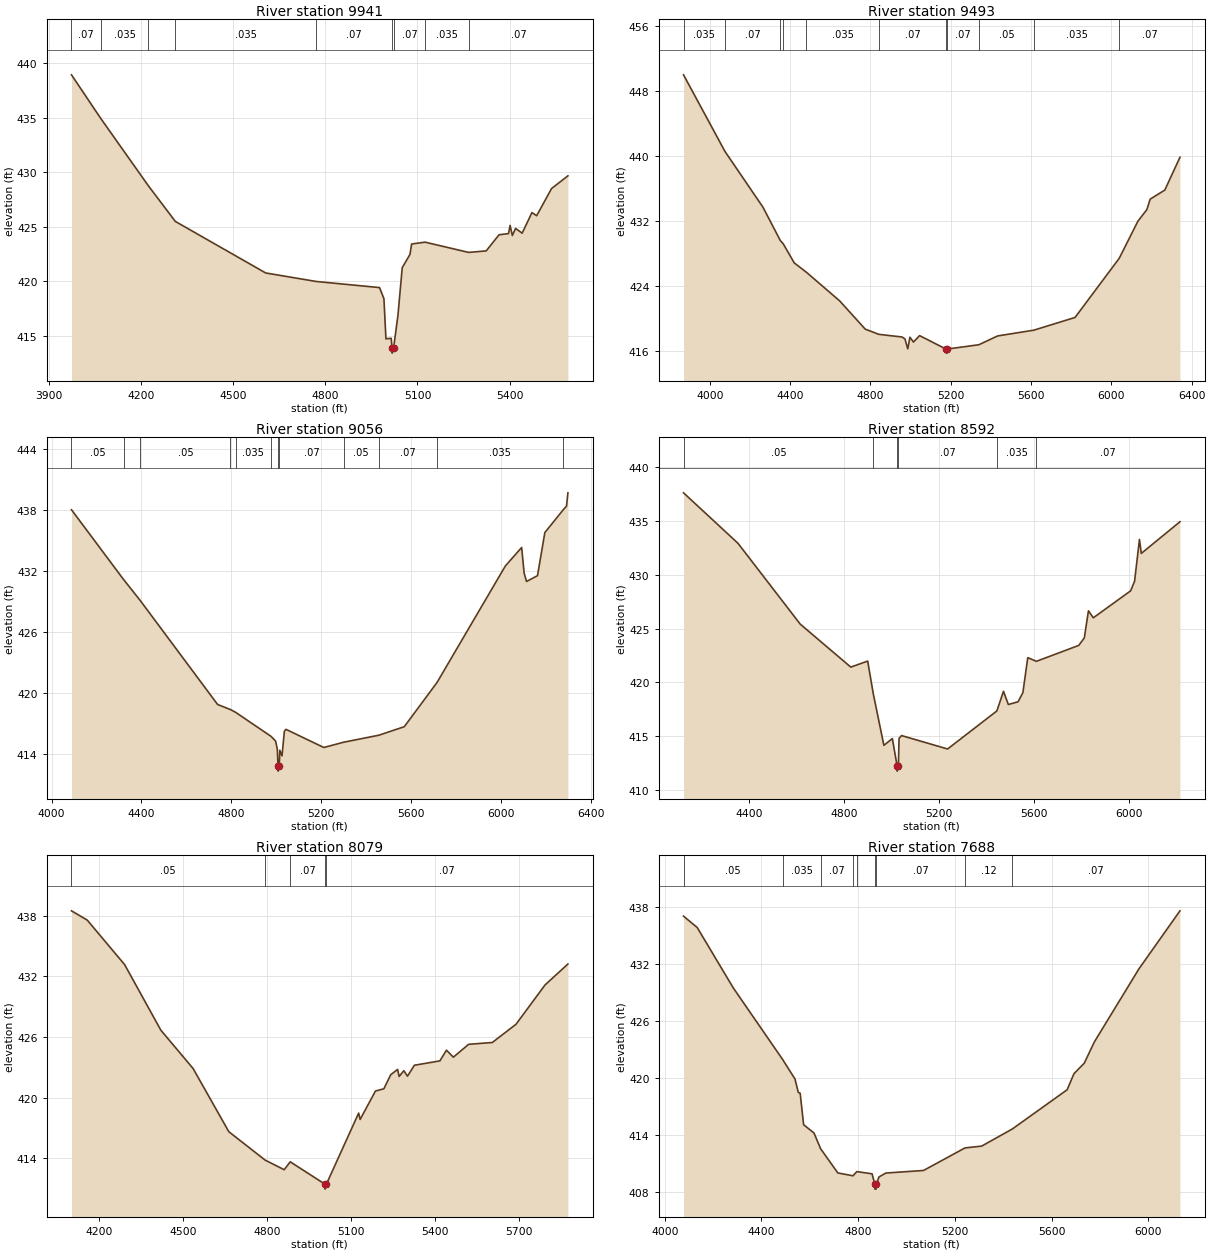
Type RM Length L Ch R = 1,9941,448,448,448
BEGIN DESCRIPTION:
Stream0580 22.0
END DESCRIPTION:
XS GIS Cut Line= 3
      2337375.01     13660024.99      2338025.00     13659225.00
      2338225.00     13658675.00
#Sta/Elev= 30
  3973.7  438.92  4068.4  434.95  4224.0  428.76  4311.7  425.50  4605.8  420.78
  4770.4  420.00  4976.5  419.44  4990.8  418.42  4997.3  414.75  5014.4  414.80
  5017.2  413.94  5017.6  413.44  5022.4  413.94  5036.4  416.90  5050.3  421.26
  5075.6  422.48  5080.9  423.43  5124.5  423.60  5266.8  422.66  5323.7  422.80
  5365.6  424.28  5396.2  424.38  5401.5  425.13  5408.8  424.21  5419.4  424.86
  5440.7  424.42  5472.6  426.31  5487.9  426.02  5536.5  428.51  5589.7  429.67
#Mann=9,-1,0
  3973.7    0.07       0  4068.4   0.035       0  4224.0    0.07       0
  4311.7   0.035       0  4770.4    0.07       0  5017.2    0.05       0
  5022.4    0.07       0  5124.5   0.035       0  5266.8    0.07       0
Bank Sta=5017.2,5022.4
Exp/Cntr=0.3,0.1

Type RM Length L Ch R = 1,9493,437,437,437
BEGIN DESCRIPTION:
Stream0580 21.0
END DESCRIPTION:
XS GIS Cut Line= 3
      2337475.03     13660374.97      2338275.00     13659575.00
      2338875.02     13658374.97
#Sta/Elev= 30
  3868.9  449.96  4075.3  440.55  4264.8  433.69  4351.3  429.59  4365.6  429.20
  4420.4  426.86  4481.3  425.70  4646.7  422.19  4774.0  418.72  4841.5  418.08
  4957.8  417.75  4971.9  417.51  4986.1  416.30  4996.7  417.73  5014.2  417.13
  5044.9  417.92  5176.5  416.27  5176.9  415.77  5181.3  415.77  5181.8  416.27
  5340.1  416.80  5433.5  417.88  5613.9  418.59  5819.2  420.15  6039.4  427.42
  6132.2  431.97  6177.0  433.40  6193.7  434.69  6266.4  435.80  6341.9  439.83
#Mann=11,-1,0
  3868.9   0.035       0  4075.3    0.07       0  4351.3   0.035       0
  4365.6    0.07       0  4481.3   0.035       0  4841.5    0.07       0
  5176.5    0.05       0  5181.8    0.07       0  5340.1    0.05       0
  5613.9   0.035       0  6039.4    0.07       0
Bank Sta=5176.5,5181.8
Exp/Cntr=0.3,0.1

Type RM Length L Ch R = 1,9056,464,464,464
BEGIN DESCRIPTION:
Stream0580 20.0
END DESCRIPTION:
XS GIS Cut Line= 3
      2338407.79     13660540.42      2338675.00     13659675.00
      2339059.42     13658428.99
#Sta/Elev= 30
  4088.6  438.05  4320.2  431.18  4394.4  429.11  4739.0  418.85  4796.3  418.35
  4819.1  418.08  4976.1  415.72  4997.0  415.25  5004.8  414.45  5007.9  412.78
  5008.4  412.28  5013.4  412.78  5015.9  414.34  5025.7  413.79  5036.2  416.21
  5043.3  416.40  5211.8  414.61  5299.9  415.13  5456.8  415.82  5569.9  416.66
  5715.7  421.02  6019.9  432.51  6092.3  434.33  6103.6  431.79  6114.1  430.98
  6162.9  431.55  6195.6  435.80  6276.4  438.02  6292.0  438.41  6298.3  439.72
#Mann=12,-1,0
  4088.6    0.05       0  4320.2   0.035       0  4394.4    0.05       0
  4796.3    0.07       0  4819.1   0.035       0  4976.1    0.07       0
  5007.9    0.05       0  5013.4    0.07       0  5299.9    0.05       0
  5456.8    0.07       0  5715.7   0.035       0  6276.4    0.07       0
Bank Sta=5007.9,5013.4
Exp/Cntr=0.3,0.1

Type RM Length L Ch R = 1,8592,513,513,513
BEGIN DESCRIPTION:
Stream0580 19.0
END DESCRIPTION:
XS GIS Cut Line= 3
      2338983.54     13660489.60      2339125.00     13659625.00
      2339372.65     13658438.16
#Sta/Elev= 30
  4123.9  437.64  4353.1  432.94  4614.9  425.42  4827.7  421.42  4898.7  421.98
  4922.0  418.96  4966.8  414.14  5002.5  414.77  5022.3  412.24  5022.7  411.74
  5027.8  412.24  5030.6  414.78  5040.9  415.05  5234.9  413.80  5442.1  417.34
  5470.0  419.17  5490.3  417.94  5531.2  418.19  5551.6  419.04  5572.1  422.30
  5608.6  421.96  5786.6  423.44  5810.0  424.14  5827.4  426.66  5847.9  426.01
  6004.9  428.52  6021.5  429.41  6042.0  433.30  6049.8  432.00  6212.4  434.95
#Mann=6,-1,0
  4123.9    0.05       0  4922.0    0.07       0  5022.3    0.05       0
  5027.8    0.07       0  5442.1   0.035       0  5608.6    0.07       0
Bank Sta=5022.3,5027.8
Exp/Cntr=0.3,0.1

Type RM Length L Ch R = 1,8079,391,391,391
BEGIN DESCRIPTION:
Stream0580 18.0
END DESCRIPTION:
XS GIS Cut Line= 3
      2339224.84     13660506.54      2339542.35     13659786.86
      2339897.60     13658869.13
#Sta/Elev= 30
  4102.9  438.49  4159.2  437.57  4292.5  433.17  4421.6  426.69  4536.6  422.90
  4664.1  416.65  4793.6  413.84  4861.6  412.89  4883.1  413.67  5006.6  411.47
  5007.1  410.97  5012.3  411.47  5127.2  418.49  5132.5  417.86  5187.1  420.67
  5217.0  420.89  5241.6  422.28  5266.1  422.81  5271.5  422.11  5288.3  422.68
  5301.4  422.14  5326.0  423.22  5416.9  423.65  5440.4  424.71  5465.0  424.02
  5519.5  425.29  5603.9  425.47  5688.4  427.27  5792.0  431.16  5873.6  433.23
#Mann=5,-1,0
  4102.9    0.05       0  4793.6   0.035       0  4883.1    0.07       0
  5006.6    0.05       0  5012.3    0.07       0
Bank Sta=5006.6,5012.3
Exp/Cntr=0.3,0.1

Type RM Length L Ch R = 1,7688,452,452,452
BEGIN DESCRIPTION:
Stream0580 17.0
END DESCRIPTION:
XS GIS Cut Line= 3
      2339324.99     13660525.01      2339925.00     13659825.00
      2340724.97     13659025.03
#Sta/Elev= 30
  4077.8  437.00  4134.3  435.81  4283.6  429.46  4488.3  421.92  4538.8  419.89
  4552.5  418.48  4560.2  418.40  4574.5  415.09  4617.3  414.22  4644.9  412.56
  4716.1  410.02  4778.8  409.72  4794.3  410.16  4857.6  409.93  4869.0  408.82
  4869.5  408.32  4874.3  408.32  4874.8  408.82  4886.2  409.60  4914.7  410.01
  5070.5  410.28  5242.1  412.65  5310.9  412.84  5437.8  414.64  5664.5  418.76
  5692.7  420.45  5735.2  421.55  5777.6  423.81  5961.4  431.46  6131.1  437.56
#Mann=9,-1,0
  4077.8    0.05       0  4488.3   0.035       0  4644.9    0.07       0
  4778.8    0.12       0  4794.3    0.07       0  4869.0    0.05       0
  4874.8    0.07       0  5242.1    0.12       0  5437.8    0.07       0
Bank Sta=4869,4874.8
Exp/Cntr=0.3,0.1

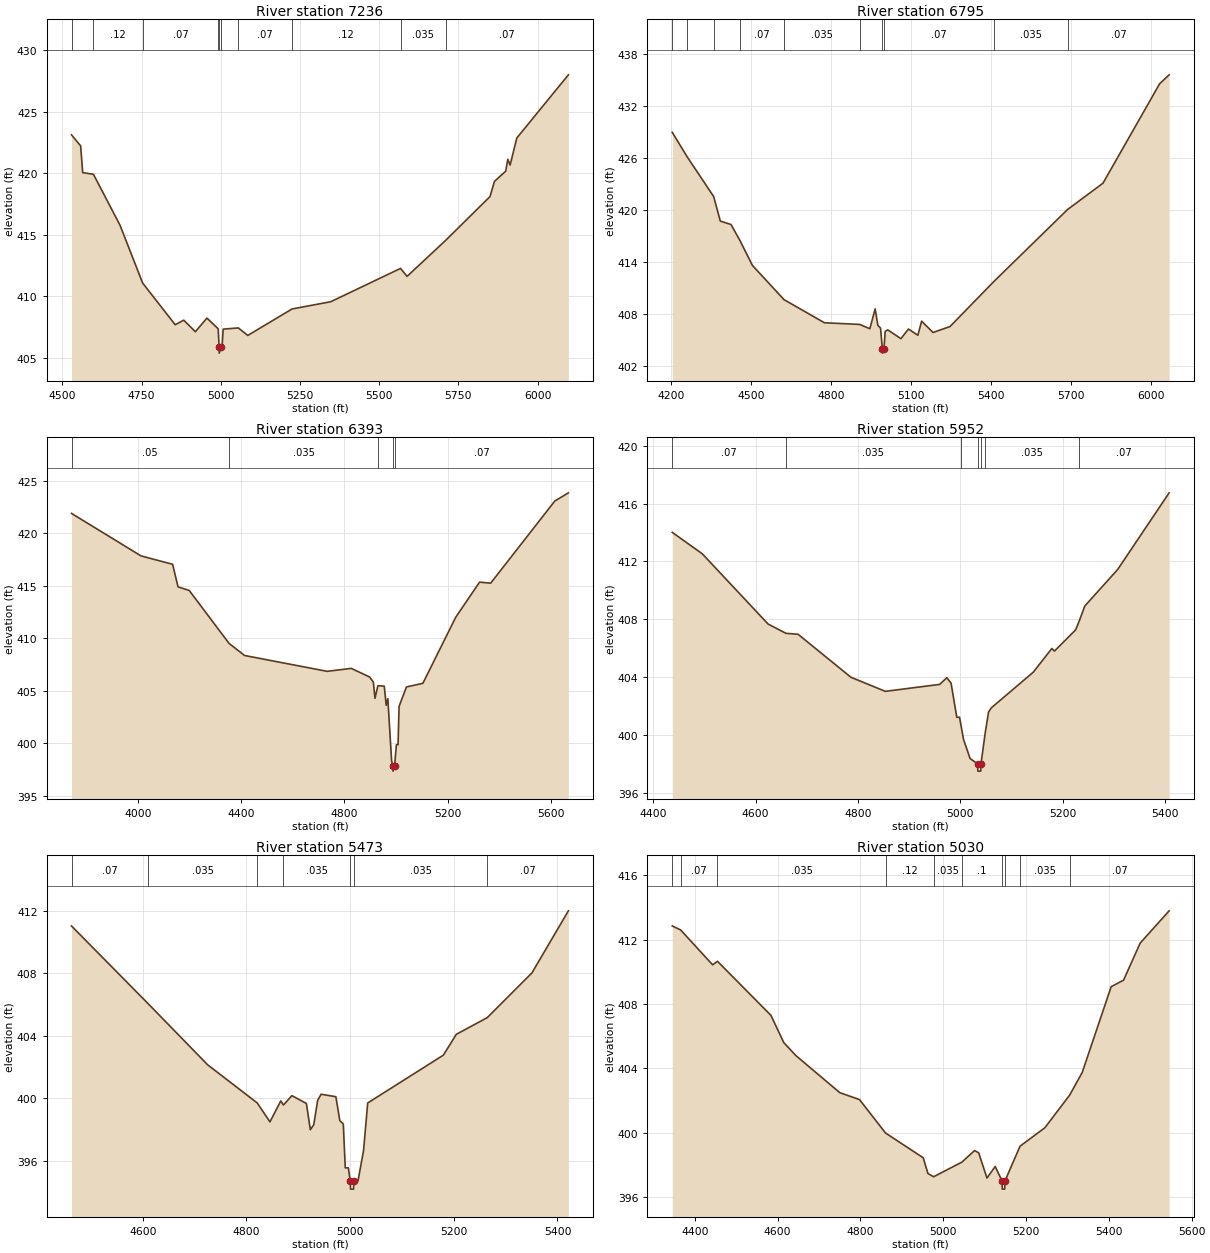
Type RM Length L Ch R = 1,7236,441,441,441
BEGIN DESCRIPTION:
Stream0580 16.0
END DESCRIPTION:
XS GIS Cut Line= 3
      2339725.04     13660424.98      2340125.00     13660175.00
      2340874.97     13659375.03
#Sta/Elev= 30
  4528.9  423.13  4557.8  422.23  4564.2  420.06  4598.2  419.92  4682.2  415.77
  4753.4  411.08  4856.1  407.69  4883.2  408.06  4919.8  407.12  4956.3  408.23
  4991.8  407.36  4994.7  405.88  4995.2  405.38  5000.6  405.88  5004.0  405.88
  5007.6  407.33  5055.4  407.43  5085.3  406.82  5224.9  408.97  5347.1  409.56
  5567.4  412.27  5587.9  411.62  5710.6  414.57  5849.7  418.11  5863.9  419.35
  5899.1  420.17  5905.9  421.14  5913.2  420.67  5934.3  422.87  6097.1  428.01
#Mann=10,-1,0
  4528.9    0.07       0  4598.2    0.12       0  4753.4    0.07       0
  4991.8    0.12       0  4994.7    0.05       0  5000.6    0.12       0
  5055.4    0.07       0  5224.9    0.12       0  5567.4   0.035       0
  5710.6    0.07       0
Bank Sta=4994.7,5000.6
Exp/Cntr=0.3,0.1

Type RM Length L Ch R = 1,6795,402,402,402
BEGIN DESCRIPTION:
Stream0580 15.0
END DESCRIPTION:
XS GIS Cut Line= 3
      2339625.04     13660525.00      2340425.00     13660475.00
      2341224.98     13659775.02
#Sta/Elev= 30
  4203.4  428.95  4260.0  426.10  4358.8  421.55  4383.7  418.72  4423.8  418.33
  4457.6  416.47  4503.9  413.62  4623.0  409.66  4774.5  407.00  4906.7  406.81
  4944.8  406.31  4964.8  408.60  4974.9  406.70  4984.9  406.39  4991.9  404.00
  4992.4  403.50  4997.9  404.00  5002.4  406.00  5012.0  406.18  5061.4  405.17
  5089.9  406.28  5125.0  405.56  5139.2  407.18  5181.9  405.88  5245.5  406.56
  5411.6  411.80  5687.0  420.06  5819.7  423.09  6032.3  434.55  6067.9  435.58
#Mann=10,-1,0
  4203.4    0.05       0  4260.0    0.07       0  4358.8   0.035       0
  4457.6    0.07       0  4623.0   0.035       0  4906.7    0.07       0
  4991.9    0.05       0  4997.9    0.07       0  5411.6   0.035       0
  5687.0    0.07       0
Bank Sta=4991.9,4997.9
Exp/Cntr=0.3,0.1

Type RM Length L Ch R = 1,6393,441,441,441
BEGIN DESCRIPTION:
Stream0580 14.0
END DESCRIPTION:
XS GIS Cut Line= 3
      2339910.68     13661679.16      2340675.00     13660675.00
      2341103.56     13660168.94
#Sta/Elev= 30
  3743.1  421.89  4012.3  417.84  4134.9  417.04  4155.8  414.89  4199.4  414.54
  4353.6  409.50  4413.5  408.35  4733.7  406.84  4827.3  407.12  4898.0  406.30
  4912.5  405.82  4918.8  404.27  4930.2  405.47  4954.8  405.43  4962.4  403.61
  4968.7  404.23  4983.2  398.34  4988.2  397.83  4988.7  397.33  4994.8  397.83
  5001.9  399.85  5008.3  399.85  5012.2  403.50  5040.8  405.35  5104.5  405.70
  5231.9  412.00  5324.2  415.34  5367.1  415.24  5615.3  423.06  5668.2  423.85
#Mann=5,-1,0
  3743.1    0.05       0  4353.6   0.035       0  4930.2    0.07       0
  4988.2    0.05       0  4994.8    0.07       0
Bank Sta=4988.2,4994.8
Exp/Cntr=0.3,0.1

Type RM Length L Ch R = 1,5952,479,479,479
BEGIN DESCRIPTION:
Stream0580 13.0
END DESCRIPTION:
XS GIS Cut Line= 3
      2340725.00     13661475.00      2340975.00     13660975.00
      2341074.99     13660575.02
#Sta/Elev= 30
  4437.0  414.01  4495.7  412.53  4624.3  407.68  4659.0  407.04  4683.0  406.97
  4786.4  404.00  4853.5  403.03  4959.7  403.51  4973.7  403.97  4982.0  403.60
  4993.2  401.24  4998.6  401.24  5000.9  400.79  5006.3  399.72  5019.2  398.39
  5033.9  398.02  5034.4  397.52  5040.0  397.52  5040.5  398.02  5048.8  400.17
  5055.3  401.60  5060.4  401.88  5142.9  404.36  5179.0  405.99  5184.1  405.81
  5225.4  407.27  5232.5  407.88  5243.4  408.92  5307.8  411.45  5408.3  416.74
#Mann=7,-1,0
  4437.0    0.07       0  4659.0   0.035       0  5000.9    0.07       0
  5033.9   0.035       0  5040.5    0.07       0  5048.8   0.035       0
  5232.5    0.07       0
Bank Sta=5033.9,5040.5
Exp/Cntr=0.3,0.1

Type RM Length L Ch R = 1,5473,443,443,443
BEGIN DESCRIPTION:
Stream0580 12.0
END DESCRIPTION:
XS GIS Cut Line= 3
      2341075.02     13661474.98      2341425.00     13661075.00
      2341274.99     13660674.98
#Sta/Elev= 30
  4462.4  411.03  4610.3  406.06  4724.8  402.16  4820.8  399.71  4845.3  398.50
  4866.2  399.84  4871.3  399.58  4887.6  400.18  4915.6  399.68  4923.2  398.00
  4929.8  398.32  4937.4  399.88  4944.0  400.27  4972.5  400.11  4980.1  398.58
  4986.8  398.37  4990.6  395.56  4996.5  395.56  5000.3  394.70  5000.8  394.20
  5006.6  394.20  5007.1  394.70  5015.2  394.73  5025.9  396.67  5033.9  399.71
  5179.9  402.77  5204.8  404.10  5264.6  405.17  5350.8  408.03  5421.1  412.00
#Mann=7,-1,0
  4462.4    0.07       0  4610.3   0.035       0  4820.8    0.07       0
  4871.3   0.035       0  5000.3   0.035       0  5007.1   0.035       0
  5264.6    0.07       0
Bank Sta=5000.3,5007.1
Exp/Cntr=0.3,0.1

Type RM Length L Ch R = 1,5030,449,449,449
BEGIN DESCRIPTION:
Stream0580 11.0
END DESCRIPTION:
XS GIS Cut Line= 3
      2341075.04     13661574.98      2341675.00     13661325.00
      2342225.04     13661325.00
#Sta/Elev= 30
  4345.6  412.86  4365.9  412.61  4443.1  410.44  4454.8  410.66  4583.9  407.30
  4614.8  405.61  4644.0  404.80  4750.2  402.49  4797.8  402.06  4860.7  399.98
  4951.7  398.44  4963.1  397.46  4976.8  397.26  5045.2  398.17  5075.6  398.89
  5085.6  398.75  5105.6  397.18  5125.6  397.90  5142.1  396.99  5142.6  396.49
  5148.5  396.49  5149.0  396.99  5185.5  399.16  5245.6  400.31  5305.4  402.34
  5335.6  403.74  5405.6  409.08  5435.6  409.49  5475.6  411.79  5545.6  413.80
#Mann=10,-1,0
  4345.6   0.035       0  4365.9    0.07       0  4454.8   0.035       0
  4860.7    0.12       0  4976.8   0.035       0  5045.2     0.1       0
  5142.1   0.035       0  5149.0     0.1       0  5185.5   0.035       0
  5305.4    0.07       0
Bank Sta=5142.1,5149
Exp/Cntr=0.3,0.1

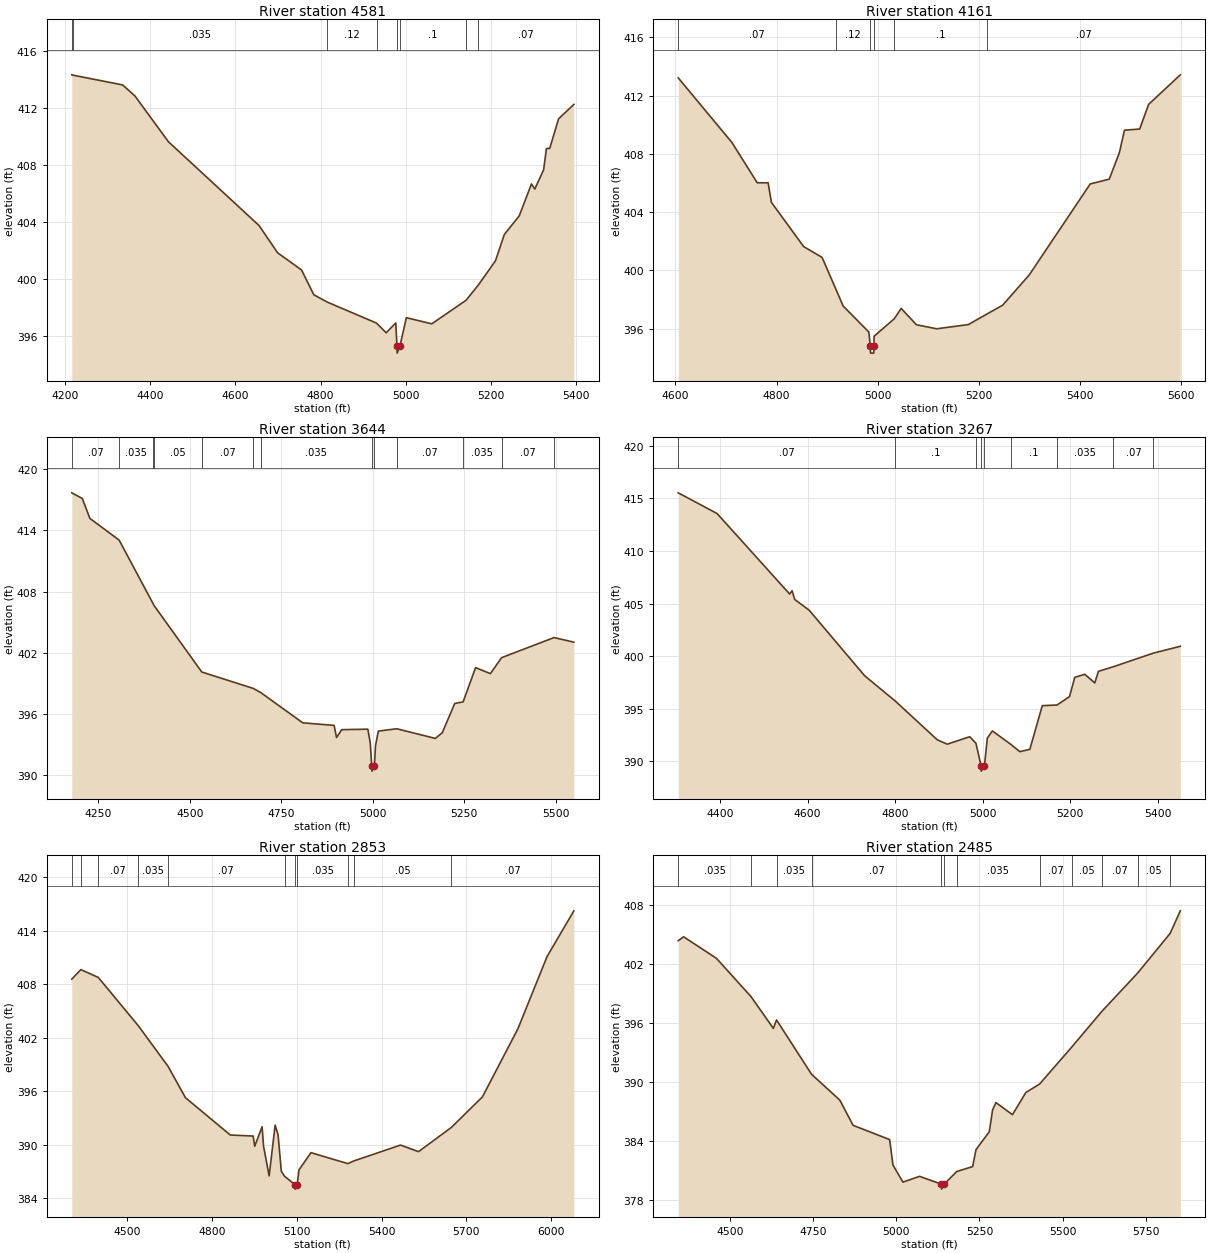
Type RM Length L Ch R = 1,4581,420,420,420
BEGIN DESCRIPTION:
Stream0580 10.0
END DESCRIPTION:
XS GIS Cut Line= 3
      2341438.90     13662297.28      2341925.00     13661675.00
      2342175.03     13661374.97
#Sta/Elev= 30
  4215.3  414.33  4219.2  414.30  4334.8  413.62  4363.7  412.85  4442.4  409.63
  4655.8  403.73  4699.2  401.82  4755.3  400.62  4784.3  398.87  4815.6  398.36
  4931.7  396.88  4954.3  396.20  4976.9  396.89  4979.7  395.27  4980.2  394.77
  4986.7  395.27  5001.8  397.26  5061.6  396.83  5142.0  398.48  5171.3  399.57
  5211.3  401.26  5232.1  403.11  5267.2  404.42  5295.9  406.66  5303.7  406.30
  5324.5  407.66  5331.0  409.15  5338.8  409.16  5359.7  411.24  5395.5  412.25
#Mann=8,-1,0
  4215.3    0.07       0  4219.2   0.035       0  4815.6    0.12       0
  4931.7     0.1       0  4979.7    0.05       0  4986.7     0.1       0
  5142.0   0.035       0  5171.3    0.07       0
Bank Sta=4979.7,4986.7
Exp/Cntr=0.3,0.1

Type RM Length L Ch R = 1,4161,517,517,517
BEGIN DESCRIPTION:
Stream0580 9.0
END DESCRIPTION:
XS GIS Cut Line= 3
      2341925.01     13662274.99      2342175.00     13661975.00
      2342225.00     13661374.98
#Sta/Elev= 30
  4605.7  413.21  4711.8  408.78  4761.9  406.01  4783.4  406.01  4789.9  404.67
  4853.7  401.63  4890.1  400.89  4917.6  398.69  4931.8  397.55  4982.5  395.77
  4985.4  394.82  4985.9  394.32  4992.2  394.32  4992.7  394.82  4992.9  395.48
  5032.9  396.68  5046.4  397.39  5076.5  396.27  5116.6  395.99  5179.3  396.28
  5215.3  396.99  5247.1  397.61  5299.7  399.69  5420.2  405.93  5457.8  406.26
  5477.9  408.08  5487.9  409.62  5518.0  409.70  5535.6  411.39  5598.3  413.42
#Mann=6,-1,0
  4605.7    0.07       0  4917.6    0.12       0  4985.4    0.05       0
  4992.7    0.12       0  5032.9     0.1       0  5215.3    0.07       0
Bank Sta=4985.4,4992.7
Exp/Cntr=0.3,0.1

Type RM Length L Ch R = 1,3644,377,377,377
BEGIN DESCRIPTION:
XS7143
END DESCRIPTION:
XS GIS Cut Line= 3
      2342018.91     13662479.28      2342776.66     13661827.36
      2342721.70     13661459.54
#Sta/Elev= 30
  4177.6  417.69  4206.3  417.14  4227.1  415.18  4307.0  413.05  4399.6  406.82
  4402.3  406.63  4532.8  400.10  4673.4  398.49  4694.4  398.07  4808.7  395.11
  4894.3  394.86  4900.9  393.67  4915.1  394.44  4986.4  394.49  4993.0  393.12
  4997.0  390.87  4997.5  390.37  5004.3  390.87  5007.3  392.87  5015.0  394.30
  5065.4  394.53  5170.8  393.58  5189.7  394.14  5223.7  397.01  5246.7  397.17
  5280.7  400.53  5321.1  399.94  5351.8  401.51  5495.1  403.48  5549.1  403.03
#Mann=13,-1,0
  4177.6    0.07       0  4307.0   0.035       0  4399.6    0.07       0
  4402.3    0.05       0  4532.8    0.07       0  4673.4     0.1       0
  4694.4   0.035       0  4997.0   0.035       0  5004.3   0.035       0
  5065.4    0.07       0  5246.7   0.035       0  5351.8    0.07       0
  5495.1    0.05       0
Bank Sta=4997,5004.3
Exp/Cntr=0.3,0.1

Type RM Length L Ch R = 1,3267,414,414,414
BEGIN DESCRIPTION:
XS7142
END DESCRIPTION:
XS GIS Cut Line= 2
      2343259.26     13662466.58      2342776.65     13661425.16
#Sta/Elev= 30
  4304.2  415.52  4393.1  413.55  4559.0  405.90  4564.5  406.22  4570.5  405.39
  4603.5  404.37  4730.4  398.14  4800.3  395.74  4896.3  392.06  4919.2  391.64
  4970.6  392.35  4984.9  391.72  4996.5  389.58  4997.0  389.08  5004.1  389.58
  5010.9  392.22  5022.3  392.90  5064.3  391.63  5085.1  390.93  5108.0  391.15
  5136.5  395.30  5170.1  395.36  5198.7  396.16  5210.7  397.99  5233.6  398.28
  5256.5  397.46  5264.8  398.56  5299.1  399.00  5390.2  400.29  5452.0  400.94
#Mann=9,-1,0
  4304.2    0.07       0  4800.3     0.1       0  4984.9    0.07       0
  4996.5    0.05       0  5004.1    0.07       0  5064.3     0.1       0
  5170.1   0.035       0  5299.1    0.07       0  5390.2    0.05       0
Bank Sta=4996.5,5004.1
Exp/Cntr=0.3,0.1

Type RM Length L Ch R = 1,2853,368,368,368
BEGIN DESCRIPTION:
XS7141
END DESCRIPTION:
XS GIS Cut Line= 2
      2343437.08     13662195.70      2342865.56     13660515.01
#Sta/Elev= 30
  4304.7  408.58  4336.9  409.65  4398.5  408.77  4539.8  403.36  4644.9  398.81
  4706.8  395.28  4865.2  391.10  4946.2  390.98  4951.5  389.84  4977.6  392.02
  4982.8  389.85  5002.6  386.51  5023.7  392.21  5034.2  391.11  5045.6  387.03
  5057.3  386.47  5093.8  385.53  5094.3  385.03  5101.5  385.53  5108.3  387.20
  5150.4  389.12  5280.6  387.89  5300.9  388.18  5467.3  389.97  5530.7  389.23
  5646.8  391.95  5756.6  395.37  5882.1  403.01  5984.9  411.09  6079.9  416.24
#Mann=11,-1,0
  4304.7    0.07       0  4336.9   0.035       0  4398.5    0.07       0
  4539.8   0.035       0  4644.9    0.07       0  5057.3   0.035       0
  5093.8    0.05       0  5101.5   0.035       0  5280.6    0.07       0
  5300.9    0.05       0  5646.8    0.07       0
Bank Sta=5093.8,5101.5
Exp/Cntr=0.3,0.1

Type RM Length L Ch R = 1,2485,402,402,402
BEGIN DESCRIPTION:
XS7140
END DESCRIPTION:
XS GIS Cut Line= 2
      2343538.67     13662081.34      2343555.61     13660570.04
#Sta/Elev= 30
  4343.2  404.36  4359.5  404.75  4458.1  402.57  4561.8  398.70  4629.6  395.45
  4639.1  396.31  4744.6  390.79  4829.6  388.17  4869.6  385.61  4979.6  384.16
  4989.6  381.58  5019.6  379.84  5069.6  380.43  5135.7  379.63  5136.2  379.13
  5143.4  379.63  5181.8  380.92  5229.6  381.42  5239.6  383.14  5279.6  384.96
  5289.6  387.19  5299.6  387.92  5349.4  386.69  5389.6  388.94  5431.0  389.80
  5529.4  393.62  5619.5  397.22  5726.4  401.08  5823.8  405.09  5854.6  407.39
#Mann=12,-1,0
  4343.2   0.035       0  4561.8    0.07       0  4639.1   0.035       0
  4744.6    0.07       0  5135.7    0.05       0  5143.4    0.07       0
  5181.8   0.035       0  5431.0    0.07       0  5529.4    0.05       0
  5619.5    0.07       0  5726.4    0.05       0  5823.8    0.07       0
Bank Sta=5135.7,5143.4
Exp/Cntr=0.3,0.1

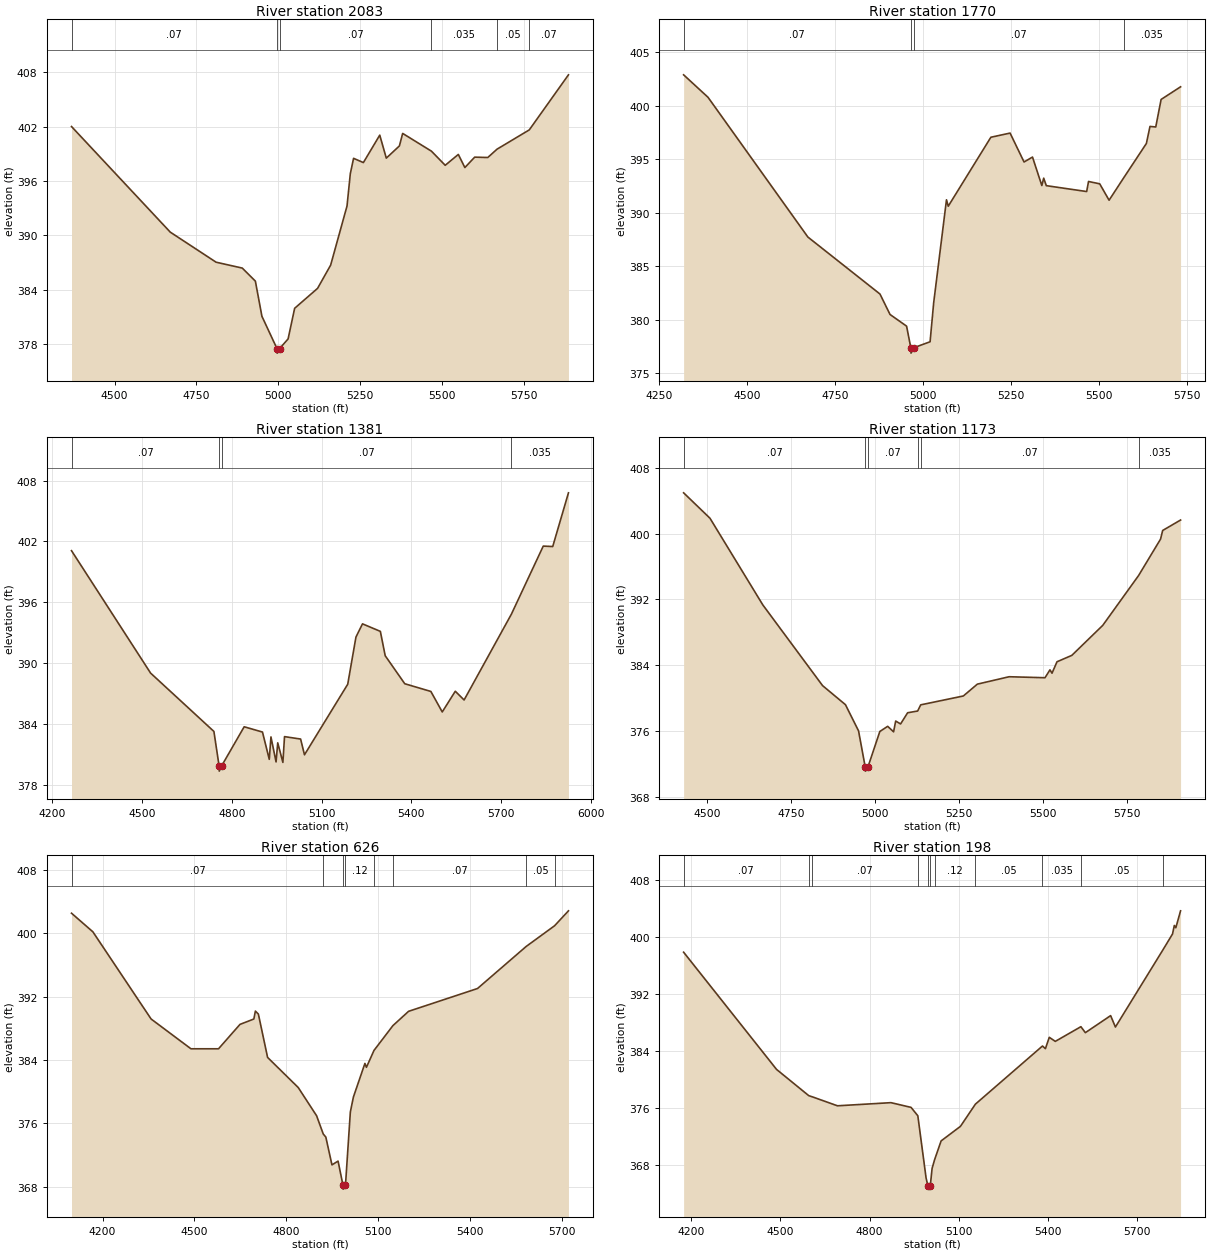
Type RM Length L Ch R = 1,2083,313,313,313
BEGIN DESCRIPTION:
XS7139
END DESCRIPTION:
XS GIS Cut Line= 2
      2343894.28     13662106.72      2343894.28     13660588.52
#Sta/Elev= 30
  4368.3  402.01  4670.0  390.35  4810.0  387.03  4890.0  386.38  4930.0  384.94
  4950.0  381.06  4996.0  377.49  4996.5  376.99  5004.0  377.49  5030.0  378.56
  5050.0  381.94  5120.0  384.14  5160.0  386.71  5210.0  393.24  5220.0  396.79
  5230.0  398.50  5260.0  398.03  5310.0  401.06  5330.0  398.52  5370.0  399.87
  5380.0  401.25  5467.9  399.29  5510.0  397.73  5550.0  398.93  5570.0  397.48
  5600.0  398.63  5640.0  398.59  5668.3  399.51  5766.8  401.64  5886.5  407.72
#Mann=6,-1,0
  4368.3    0.07       0  4996.0    0.05       0  5004.0    0.07       0
  5467.9   0.035       0  5668.3    0.05       0  5766.8    0.07       0
Bank Sta=4996,5004
Exp/Cntr=0.3,0.1

Type RM Length L Ch R = 1,1770,389,389,389
BEGIN DESCRIPTION:
XS7138
END DESCRIPTION:
XS GIS Cut Line= 4
      2344025.52     13662089.80      2344152.52     13661514.09
      2344203.32     13661226.22      2344038.22     13660722.46
#Sta/Elev= 30
  4319.8  402.88  4389.2  400.78  4672.9  387.73  4877.7  382.41  4906.3  380.50
  4953.3  379.41  4965.4  377.39  4965.9  376.89  4973.4  377.39  5020.1  377.95
  5030.3  381.59  5066.7  391.21  5071.7  390.61  5192.8  397.05  5247.4  397.44
  5287.1  394.74  5311.1  395.20  5337.6  392.54  5342.9  393.23  5350.3  392.53
  5465.0  391.98  5470.3  392.92  5502.1  392.70  5528.7  391.17  5571.2  393.31
  5634.7  396.47  5644.9  398.06  5661.3  398.01  5676.5  400.58  5731.8  401.76
#Mann=4,-1,0
  4319.8    0.07       0  4965.4    0.05       0  4973.4    0.07       0
  5571.2   0.035       0
Bank Sta=4965.4,4973.4
Exp/Cntr=0.3,0.1

Type RM Length L Ch R = 1,1381,208,208,208
BEGIN DESCRIPTION:
XS7137
END DESCRIPTION:
XS GIS Cut Line= 4
      2344135.60     13662089.80      2344436.15     13661590.29
      2344520.82     13661412.49      2344098.07     13660638.85
#Sta/Elev= 30
  4263.7  401.09  4528.1  389.03  4739.8  383.28  4757.2  379.87  4757.7  379.37
  4765.3  379.87  4841.0  383.74  4902.2  383.22  4924.9  380.53  4930.5  382.74
  4947.6  380.28  4953.2  382.16  4970.4  380.23  4975.9  382.77  5029.7  382.53
  5042.6  380.98  5187.2  387.93  5214.7  392.58  5236.6  393.88  5296.3  393.14
  5312.5  390.74  5377.9  387.98  5465.2  387.22  5503.2  385.20  5546.8  387.24
  5576.3  386.38  5734.5  394.84  5840.9  401.54  5872.6  401.50  5925.2  406.79
#Mann=4,-1,0
  4263.7    0.07       0  4757.2    0.05       0  4765.3    0.07       0
  5734.5   0.035       0
Bank Sta=4757.2,4765.3
Exp/Cntr=0.3,0.1

Type RM Length L Ch R = 1,1173,547,547,547
BEGIN DESCRIPTION:
XS7136
END DESCRIPTION:
XS GIS Cut Line= 3
      2344863.71     13661958.55      2344664.76     13661370.15
      2344165.20     13660671.63
#Sta/Elev= 30
  4430.8  404.96  4509.3  401.87  4666.8  391.32  4844.6  381.51  4912.8  379.19
  4951.8  376.00  4971.6  371.61  4972.1  371.11  4979.7  371.61  5015.1  375.93
  5038.5  376.56  5056.1  375.89  5062.3  377.20  5077.0  376.85  5097.9  378.21
  5127.8  378.42  5136.8  379.17  5263.8  380.25  5305.5  381.69  5400.1  382.59
  5507.0  382.47  5521.8  383.43  5527.9  383.02  5542.7  384.41  5586.9  385.19
  5679.0  388.84  5785.7  394.90  5851.1  399.33  5857.4  400.38  5910.7  401.65
#Mann=6,-1,0
  4430.8    0.07       0  4971.6    0.05       0  4979.7    0.07       0
  5127.8    0.12       0  5136.8    0.07       0  5785.7   0.035       0
Bank Sta=4971.6,4979.7
Exp/Cntr=0.3,0.1

Type RM Length L Ch R = 1,626,428,428,428
BEGIN DESCRIPTION:
XS7135
END DESCRIPTION:
XS GIS Cut Line= 2
      2344952.63     13661924.72      2344863.73     13660303.36
#Sta/Elev= 30
  4098.5  402.54  4168.3  400.19  4358.6  389.18  4488.8  385.42  4578.9  385.42
  4649.0  388.50  4694.3  389.18  4699.3  390.18  4709.1  389.80  4739.2  384.33
  4839.3  380.53  4899.4  376.96  4921.1  374.66  4929.5  374.27  4949.5  370.76
  4969.5  371.24  4985.5  368.20  4986.0  367.70  4993.7  368.20  5009.6  377.44
  5019.6  379.33  5057.2  383.57  5062.2  383.08  5086.8  385.21  5148.8  388.35
  5199.9  390.15  5425.1  393.03  5584.1  398.34  5677.1  400.96  5722.3  402.84
#Mann=8,-1,0
  4098.5    0.07       0  4921.1    0.12       0  4985.5    0.05       0
  4993.7    0.12       0  5086.8    0.05       0  5148.8    0.07       0
  5584.1    0.05       0  5677.1   0.035       0
Bank Sta=4985.5,4993.7
Exp/Cntr=0.3,0.1

Type RM Length L Ch R = 1,198,0,0,0
BEGIN DESCRIPTION:
XS7134
END DESCRIPTION:
XS GIS Cut Line= 3
      2345130.43     13661928.96      2345304.00     13661192.35
      2345177.25     13660288.18
#Sta/Elev= 30
  4175.4  397.81  4487.7  381.38  4596.0  377.70  4607.0  377.55  4692.4  376.28
  4872.1  376.72  4939.6  376.06  4962.4  374.88  4990.1  366.17  4996.0  365.10
  4996.5  364.60  5004.3  365.10  5010.3  367.50  5018.6  368.71  5040.6  371.36
  5105.6  373.40  5155.8  376.51  5381.2  384.66  5391.1  384.29  5404.1  385.88
  5424.3  385.31  5510.3  387.37  5525.3  386.53  5610.2  388.92  5626.3  387.32
  5786.7  398.19  5818.1  400.36  5824.3  401.56  5829.3  401.24  5845.2  403.61
#Mann=11,-1,0
  4175.4    0.07       0  4596.0    0.12       0  4607.0    0.07       0
  4962.4     0.1       0  4996.0    0.05       0  5004.3     0.1       0
  5018.6    0.12       0  5155.8    0.05       0  5381.2   0.035       0
  5510.3    0.05       0  5786.7    0.07       0
Bank Sta=4996,5004.3
Exp/Cntr=0.3,0.1

Chan Stop Cuts=-1