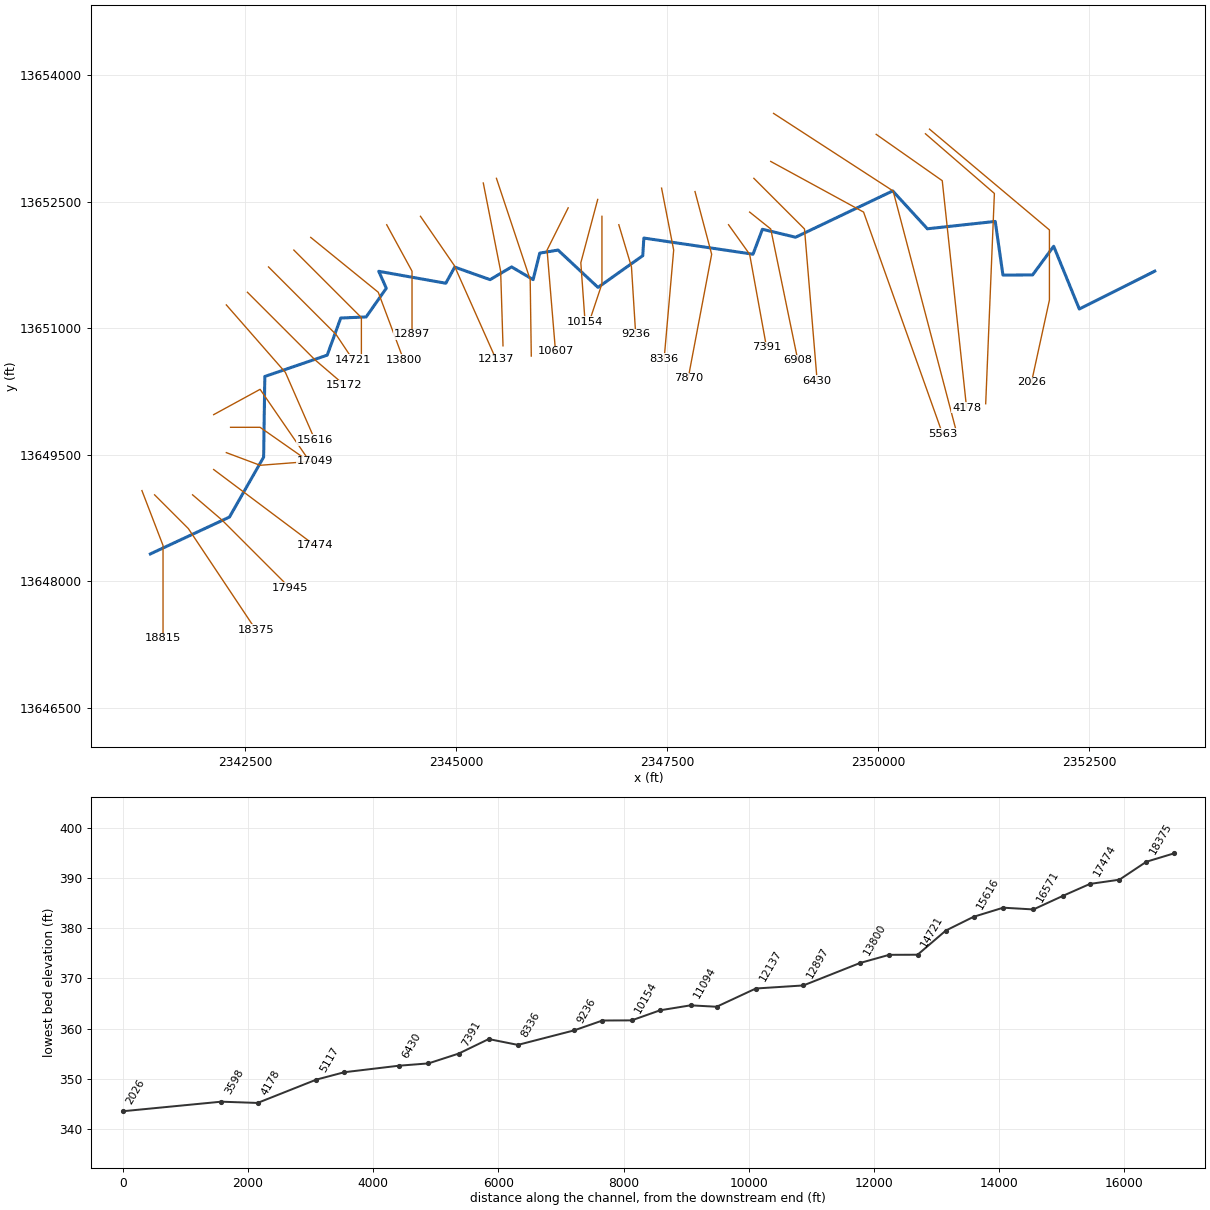
--- Stream0581.prj (project) ---

Proj Title=Stream0581 Base Level Engineering
Current Plan=p01
Default Exp/Contr=0.3,0.1
English Units
Geom File=g01
Flow File=f01
Plan File=p01
Y Axis Title=Elevation
X Axis Title(PF)=Main Channel Distance
X Axis Title(XS)=Station
BEGIN DESCRIPTION:
Stream0581
END DESCRIPTION:
DSS Export Rating Curves= 0
DSS Export Rating Curve Sorted= 0
DSS Export Volume Flow Curves= 0
DXF OffsetX= 0
DXF OffsetY= 0
DXF ScaleX= 1
DXF ScaleY= 10

--- Stream0581.p01 (plan) ---

Plan Title=Multiple Run
Short Identifier=Multiple
Geom File=g01
Flow File=f01
Subcritical Flow
K Sum by GR= 0
Std Step Tol= 0.01
Critical Tol= 0.01
Num of Std Step Trials= 20
Max Error Tol= 0.3
Flow Tol Ratio= 0.001
Split Flow NTrial= 30
Split Flow Tol= 0.02
Split Flow Ratio= 0.02
Log Output Level= 0
Friction Slope Method= 1
Unsteady Friction Slope Method= 2
Unsteady Bridges Friction Slope Method= 1
Parabolic Critical Depth
Global Vel Dist=  1 , 1 , 1
Global Log Level= 0
CheckData=True
Encroach Param= -1, 0, 0, 0
BEGIN DESCRIPTION:
Multiple Run
END DESCRIPTION:

--- Stream0581.f01 (steady flow) ---

Flow Title=Multiple
Number of Profiles=7
Profile Names=10-year,25-year,50-year,1pct_min,100-year,1pct_plu,500-year
River Rch & RM= Stream0581,Reach-1,18815
     576     926    1240     805    1606    3204    2667
River Rch & RM= Stream0581,Reach-1,17945
     900    1486    2026    1336    2666    5319    4578
River Rch & RM= Stream0581,Reach-1,15616
    1692    2898    4050    2733    5452   10879    9806
River Rch & RM= Stream0581,Reach-1,11511
    1858    3180    4442    2994    5973   11918   10719
River Rch & RM= Stream0581,Reach-1,6430
    1951    3335    4652    3129    6243   12457   11163
River Rch & RM= Stream0581,Reach-1,1011
    2124    3640    5086    3426    6836   13640   12259
Boundary for River Rch & Prof#=Stream0581,Reach-1,1
Up Type=0
Dn Type=3
Dn Slope=0.005
Boundary for River Rch & Prof#=Stream0581,Reach-1,2
Up Type=0
Dn Type=3
Dn Slope=0.005
Boundary for River Rch & Prof#=Stream0581,Reach-1,3
Up Type=0
Dn Type=3
Dn Slope=0.005
Boundary for River Rch & Prof#=Stream0581,Reach-1,4
Up Type=0
Dn Type=3
Dn Slope=0.005
Boundary for River Rch & Prof#=Stream0581,Reach-1,5
Up Type=0
Dn Type=3
Dn Slope=0.005
Boundary for River Rch & Prof#=Stream0581,Reach-1,6
Up Type=0
Dn Type=3
Dn Slope=0.005
Boundary for River Rch & Prof#=Stream0581,Reach-1,7
Up Type=0
Dn Type=3
Dn Slope=0.005

--- Stream0581.g01 (geometry) ---

Geom Title=Existing Conditions
Program Version=4.10

River Reach=Stream0581      ,Reach-1
Reach XY= 30
        2341375.       13648325.      2342311.55     13648761.37
      2342716.92      13649471.7      2342730.82     13650427.31
      2343469.96     13650680.08      2343630.41     13651119.83
      2343931.53     13651132.68      2344170.21     13651472.82
       2344080.8     13651673.45      2344875.03     13651531.88
      2344980.69     13651723.12      2345400.04     13651574.51
      2345654.82      13651725.3      2345909.78     13651574.83
       2345988.2     13651888.74      2346204.97     13651924.93
      2346678.34     13651482.58      2347208.87     13651858.52
      2347221.55     13652067.21      2348514.73     13651875.96
      2348626.22     13652171.57      2349019.12     13652076.96
      2350169.98     13652625.84      2350580.83     13652177.06
      2351384.85     13652264.52      2351476.22     13651628.43
      2351827.47     13651630.45       2352077.3     13651969.94
      2352380.84     13651226.57        2353275.       13651675.

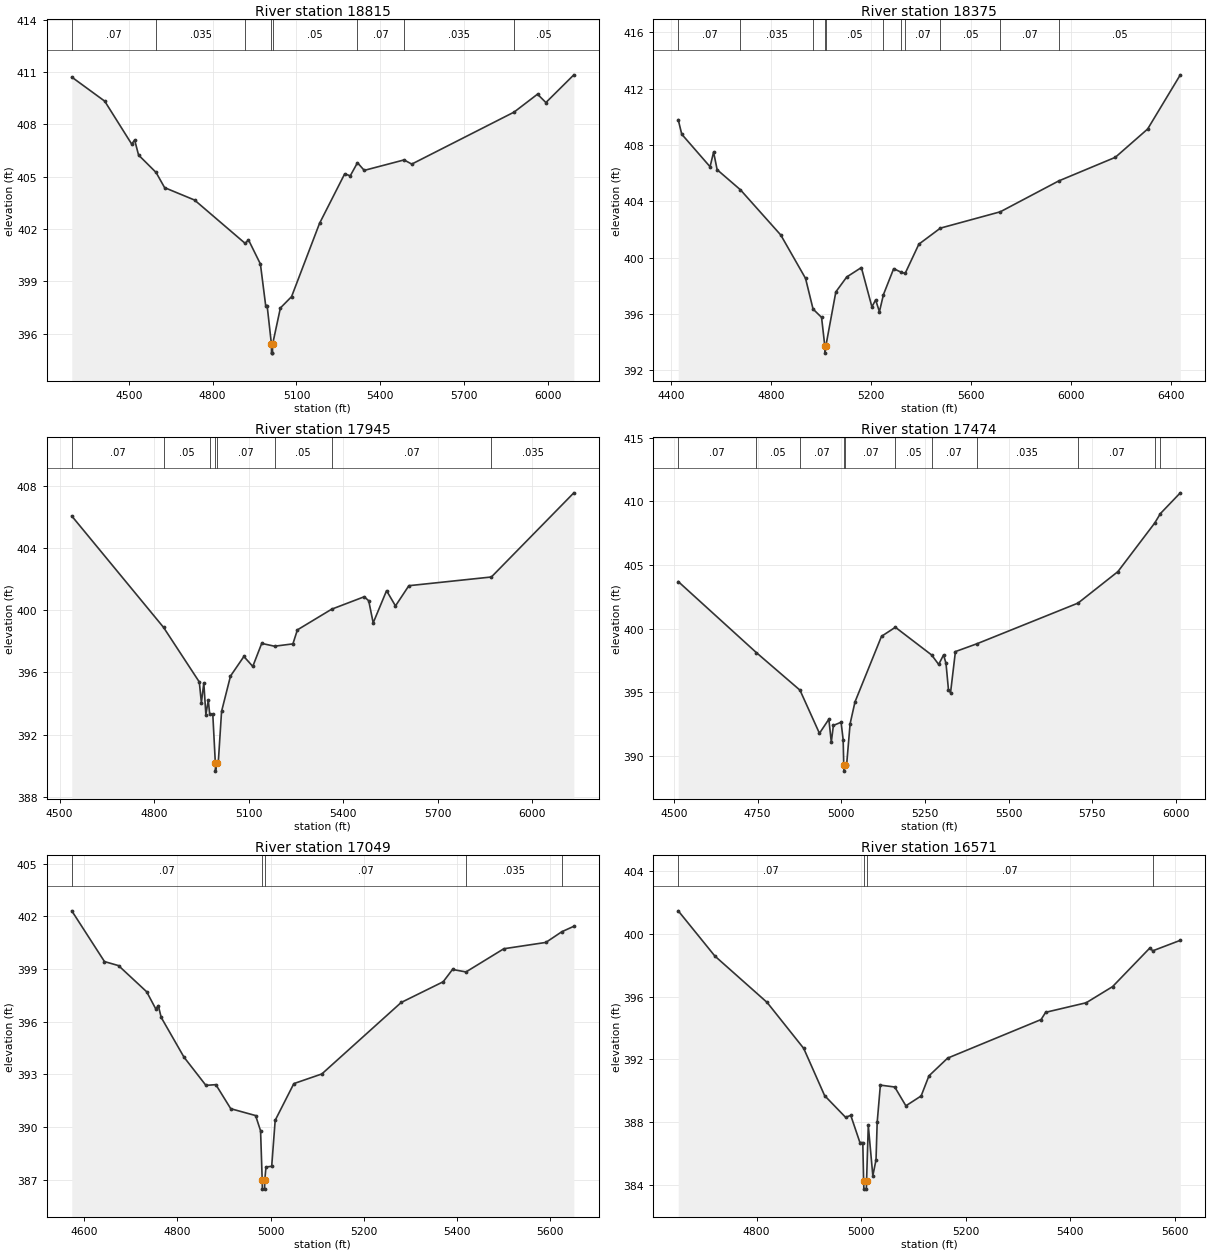
Type RM Length L Ch R = 1 ,18815   ,440,440,440
BEGIN DESCRIPTION:
Stream0581 30.0
END DESCRIPTION:
XS GIS Cut Line= 3
      2341274.99     13649075.03        2341525.       13648425.
        2341525.     13647324.95
#Sta/Elev= 30
    4296  410.71  4413.9  409.33  4510.3  406.87    4521   407.1    4535  406.24
  4597.7  405.24  4628.2  404.37  4735.3  403.66  4916.7  401.17  4928.2  401.38
    4971  399.99  4989.8  397.61    4995  397.61  5010.5  395.38  5010.7  394.88
  5014.2  394.88  5014.5  395.38  5042.5  397.47  5082.5  398.12  5182.5  402.32
  5272.5  405.16  5292.5  405.05  5318.3   405.8  5342.5  405.36  5485.1  405.96
  5512.5  405.72  5878.4   408.7  5962.5  409.73  5992.5  409.25  6092.5  410.84
#Mann= 8 ,-1 , 0
    4296     .07       0  4597.7    .035       0  4916.7     .05       0
  5010.5     .05       0  5014.5     .05       0  5318.3     .07       0
  5485.1    .035       0  5878.4     .05       0
Bank Sta=5010.5,5014.5
XS Rating Curve= 0 ,0
Exp/Cntr=0.3,0.1

Type RM Length L Ch R = 1 ,18375   ,430,430,430
BEGIN DESCRIPTION:
Stream0581 29.0
END DESCRIPTION:
XS GIS Cut Line= 3
        2341425.       13649025.        2341825.       13648625.
      2342624.99     13647425.01
#Sta/Elev= 30
  4429.9   409.8    4444  408.77  4557.2  406.46  4571.3   407.5  4585.5  406.25
  4678.8  404.82    4840  401.61    4939  398.53  4969.1  396.35  5003.1  395.76
  5016.1  393.72  5016.4  393.22  5020.2  393.72  5060.2  397.57  5103.8  398.63
  5162.3   399.3  5204.4  396.51  5219.4     397  5234.5  396.16  5250.6  397.38
  5291.5  399.22  5321.2  398.97  5337.3  398.88  5392.2  400.96  5478.3   402.1
  5717.9  403.26  5951.3  405.45  6177.9  407.13  6307.1  409.14  6437.8  412.99
#Mann= 11 ,-1 , 0
  4429.9     .07       0  4678.8    .035       0  4969.1     .05       0
  5016.1     .05       0  5020.2     .05       0  5250.6     .07       0
  5321.2    .035       0  5337.3     .07       0  5478.3     .05       0
  5717.9     .07       0  5951.3     .05       0
Bank Sta=5016.1,5020.2
XS Rating Curve= 0 ,0
Exp/Cntr=0.3,0.1

Type RM Length L Ch R = 1 ,17945   ,471,471,471
BEGIN DESCRIPTION:
Stream0581 28.0
END DESCRIPTION:
XS GIS Cut Line= 3
      2341874.98     13649025.02        2342225.       13648725.
      2343025.02     13647924.98
#Sta/Elev= 30
  4538.9  406.05    4830  398.89  4943.4  395.38    4950  394.05  4957.7  395.32
  4964.2  393.29  4971.9   394.2  4976.3  393.33  4986.2   393.3  4994.3  390.15
  4994.6  389.65    4999  390.15  5003.4  390.15    5014  393.49  5042.3  395.76
  5084.8  397.02    5113  396.38  5141.3  397.86  5181.9  397.68  5240.3  397.83
  5254.5  398.73  5363.2  400.06  5466.6  400.86  5480.7   400.6  5494.9  399.18
  5537.3  401.25  5565.6  400.27    5608  401.57  5869.8  402.13  6131.3  407.54
#Mann= 8 ,-1 , 0
  4538.9     .07       0    4830     .05       0  4976.3     .07       0
  4994.3     .05       0    4999     .07       0  5181.9     .05       0
  5363.2     .07       0  5869.8    .035       0
Bank Sta=4994.3,4999
XS Rating Curve= 0 ,0
Exp/Cntr=0.3,0.1

Type RM Length L Ch R = 1 ,17474   ,425,425,425
BEGIN DESCRIPTION:
Stream0581 27.0
END DESCRIPTION:
XS GIS Cut Line= 3
        2342125.       13649325.        2342525.       13649025.
        2343325.       13648425.
#Sta/Elev= 30
  4512.9   403.7  4746.3  398.12  4876.6  395.17  4934.8  391.78  4962.9  392.89
  4970.2  391.08  4976.4   392.4  4999.4  392.65  5005.6  391.28  5007.4  389.31
  5007.8  388.81  5012.1  389.31    5016  389.31  5026.4  392.53    5041  394.25
  5120.2   399.4  5161.6  400.11  5270.1  397.93    5291  397.19  5305.6  397.94
  5312.9  397.27  5320.2  395.21  5326.4  394.96    5341   398.2  5404.9  398.81
  5707.4  402.01  5826.4  404.48  5936.5   408.3  5953.4  409.04  6012.9  410.67
#Mann= 11 ,-1 , 0
  4512.9     .07       0  4746.3     .05       0  4876.6     .07       0
  5007.4     .05       0  5012.1     .07       0  5161.6     .05       0
  5270.1     .07       0  5404.9    .035       0  5707.4     .07       0
  5936.5    .035       0  5953.4     .07       0
Bank Sta=5007.4,5012.1
XS Rating Curve= 0 ,0
Exp/Cntr=0.3,0.1

Type RM Length L Ch R = 1 ,17049   ,478,478,478
BEGIN DESCRIPTION:
Stream0581 26.0
END DESCRIPTION:
XS GIS Cut Line= 3
      2342275.04     13649524.99        2342675.       13649375.
      2343325.02       13649425.
#Sta/Elev= 30
  4572.8  402.32  4643.1  399.43  4673.3   399.2  4733.8  397.71  4753.4  396.73
  4758.8  396.92    4765  396.25  4813.9  393.99  4861.1  392.38  4882.5  392.42
  4914.5  391.05  4967.9  390.66  4978.6  389.79  4982.1  386.97  4982.5  386.47
  4987.2  386.47  4987.6  386.97  4990.2  387.73  5002.5  387.77    5010  390.39
  5050.1  392.48  5110.3  393.03  5280.8   397.1  5371.1  398.28  5391.1  398.98
  5420.1  398.84  5501.4  400.16  5591.7  400.52  5626.1  401.13  5651.9  401.44
#Mann= 5 ,-1 , 0
  4572.8     .07       0  4982.1     .05       0  4987.6     .07       0
  5420.1    .035       0  5626.1     .07       0
Bank Sta=4982.1,4987.6
XS Rating Curve= 0 ,0
Exp/Cntr=0.3,0.1

Type RM Length L Ch R = 1 ,16571   ,482,482,482
BEGIN DESCRIPTION:
Stream0581 25.0
END DESCRIPTION:
XS GIS Cut Line= 3
      2342325.01       13649825.        2342675.       13649825.
      2343174.99     13649475.01
#Sta/Elev= 30
  4650.1  401.47  4720.1  398.59  4820.1  395.63  4890.1   392.7  4930.1  389.69
  4970.1  388.31  4980.1  388.43  4997.6   386.7  5003.1   386.7  5004.7  384.23
  5005.2  383.73  5009.9  383.73  5010.3  384.23  5013.6  387.79  5022.3  384.58
  5028.4   385.6  5030.6  387.98  5036.7  390.36  5064.2  390.24  5085.5  389.04
  5114.7  389.67  5129.6  390.95  5165.3  392.08  5344.1  394.54  5352.8     395
  5430.4  395.61  5480.9  396.64  5552.4  399.11  5557.6  398.92  5610.4  399.59
#Mann= 4 ,-1 , 0
  4650.1     .07       0  5004.7     .05       0  5010.3     .07       0
  5557.6    .035       0
Bank Sta=5004.7,5010.3
XS Rating Curve= 0 ,0
Exp/Cntr=0.3,0.1

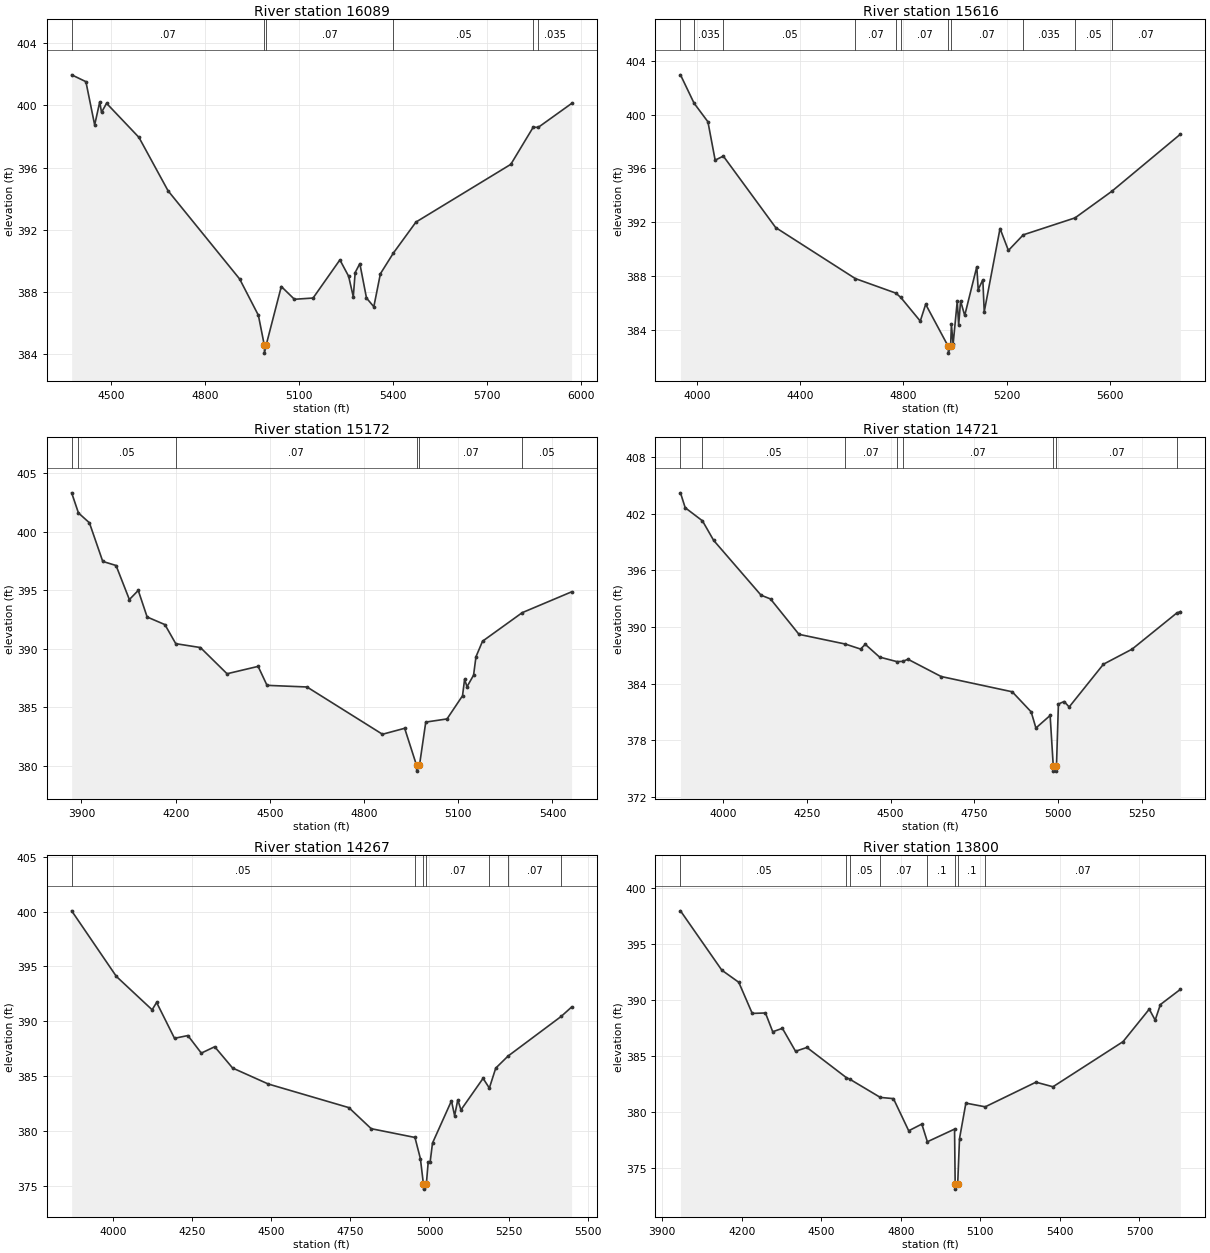
Type RM Length L Ch R = 1 ,16089   ,473,473,473
BEGIN DESCRIPTION:
Stream0581 24.0
END DESCRIPTION:
XS GIS Cut Line= 3
      2342125.03     13649975.02        2342675.       13650275.
      2343225.01     13649474.99
#Sta/Elev= 30
    4374  401.96  4419.5  401.52  4447.5  398.74  4463.7  400.22  4469.4  399.55
  4485.5  400.13    4589  397.94    4682  394.51  4910.8  388.84  4970.6  386.51
  4989.6  384.58    4990  384.08  4995.2  384.58  5043.8  388.36  5085.7  387.54
  5145.3  387.62    5231  390.07  5258.9  389.02  5273.8   387.7  5279.8  389.26
  5294.7  389.83    5316  387.62  5339.4  387.06  5360.4  389.18  5401.9  390.51
    5474   392.5  5777.1  396.21  5848.8   398.6  5864.4  398.58  5971.3  400.12
#Mann= 6 ,-1 , 0
    4374     .07       0  4989.6     .05       0  4995.2     .07       0
  5401.9     .05       0  5848.8     .07       0  5864.4    .035       0
Bank Sta=4989.6,4995.2
XS Rating Curve= 0 ,0
Exp/Cntr=0.3,0.1

Type RM Length L Ch R = 1 ,15616   ,444,444,444
BEGIN DESCRIPTION:
Stream0581 23.0
END DESCRIPTION:
XS GIS Cut Line= 3
      2342275.03     13651274.97        2342975.       13650475.
      2343325.01     13649674.99
#Sta/Elev= 30
  3936.6  402.95  3989.3  400.84  4042.9  399.46  4070.9  396.61  4102.6  396.91
  4305.3   391.6  4613.7  387.81  4770.6  386.73  4789.7  386.41  4865.3  384.65
  4886.2   385.9  4973.6  382.77  4974.1  382.27  4982.9  382.77  4985.8  384.42
  4992.5  382.94  5008.5  386.13    5014  384.37  5021.4  386.14  5037.4  385.07
  5084.2  388.69  5089.6  386.99  5107.6  387.72    5113  385.34  5174.2  391.53
  5206.6   389.9  5264.2  391.06  5464.7  392.32  5606.8  394.29  5872.8  398.54
#Mann= 11 ,-1 , 0
  3936.6     .07       0  3989.3    .035       0  4102.6     .05       0
  4613.7     .07       0  4770.6     .05       0  4789.7     .07       0
  4973.6     .05       0  4982.9     .07       0  5264.2    .035       0
  5464.7     .05       0  5606.8     .07       0
Bank Sta=4973.6,4982.9
XS Rating Curve= 0 ,0
Exp/Cntr=0.3,0.1

Type RM Length L Ch R = 1 ,15172   ,451,451,451
BEGIN DESCRIPTION:
Stream0581 22.0
END DESCRIPTION:
XS GIS Cut Line= 3
      2342525.02     13651424.98        2343325.       13650625.
      2343674.99     13650325.01
#Sta/Elev= 30
  3868.7  403.31  3890.3  401.59  3925.2  400.75  3967.7  397.45  4010.1   397.1
  4052.5  394.19  4080.8  394.97  4109.1   392.7  4165.7  392.05  4200.3  390.42
  4278.8  390.09  4363.6  387.85  4462.6  388.48  4490.9  386.86  4618.2  386.72
  4858.6  382.68  4929.3  383.19  4967.1  380.03  4967.6  379.53  4976.5  380.03
  4996.5  383.72  5064.2  383.99  5113.6  385.97  5120.2  387.38  5127.9  386.74
  5148.8  387.73  5156.4   389.3  5177.3  390.63  5303.7  393.07    5461  394.85
#Mann= 6 ,-1 , 0
  3868.7    .035       0  3890.3     .05       0  4200.3     .07       0
  4967.1     .05       0  4976.5     .07       0  5303.7     .05       0
Bank Sta=4967.1,4976.5
XS Rating Curve= 0 ,0
Exp/Cntr=0.3,0.1

Type RM Length L Ch R = 1 ,14721   ,454,454,454
BEGIN DESCRIPTION:
Stream0581 21.0
END DESCRIPTION:
XS GIS Cut Line= 3
        2342775.       13651725.        2343575.       13650925.
      2343774.98     13650625.02
#Sta/Elev= 30
    3873  404.22  3887.1  402.64  3938.6  401.25    3972  399.18  4113.4  393.37
  4141.7  392.97  4226.6  389.22  4364.9  388.19  4410.4  387.66  4424.5  388.16
    4467  386.81  4518.5  386.33  4536.3  386.35  4551.8  386.58  4650.8  384.75
    4863  383.13  4919.5     381  4933.7  379.29  4976.1  380.62  4985.5  375.22
    4986  374.72  4994.5  374.72    4995  375.22  5000.8  381.83  5017.9   382.1
  5032.9  381.52  5135.1  386.05  5220.7  387.65    5354  391.48  5364.9  391.63
#Mann= 8 ,-1 , 0
    3873    .035       0  3938.6     .05       0  4364.9     .07       0
  4518.5     .05       0  4536.3     .07       0  4985.5     .05       0
    4995     .07       0    5354     .05       0
Bank Sta=4985.5,4995
XS Rating Curve= 0 ,0
Exp/Cntr=0.3,0.1

Type RM Length L Ch R = 1 ,14267   ,467,467,467
BEGIN DESCRIPTION:
Stream0581 20.0
END DESCRIPTION:
XS GIS Cut Line= 3
      2343075.01     13651924.99        2343875.       13651125.
        2343875.     13650674.96
#Sta/Elev= 30
  3868.2  400.07  4009.6  394.09  4122.7  391.05  4136.9  391.72  4193.5  388.45
  4235.9   388.7  4278.3   387.1  4320.7  387.68  4377.3  385.74  4490.4  384.28
    4745  382.13  4815.7  380.21  4954.1  379.41  4971.3  377.48  4980.7   375.2
  4981.2   374.7  4990.2   375.2    4996  377.16  5002.1  377.16  5009.6   378.9
  5069.6  382.75  5079.6  381.39  5089.6  382.85  5099.6  381.92  5169.6   384.8
  5189.4  383.91  5209.6  385.73  5248.6  386.83  5416.9  390.45  5449.6   391.3
#Mann= 7 ,-1 , 0
  3868.2     .05       0  4954.1     .07       0  4980.7     .05       0
  4990.2     .07       0  5189.4     .05       0  5248.6     .07       0
  5416.9     .05       0
Bank Sta=4980.7,4990.2
XS Rating Curve= 0 ,0
Exp/Cntr=0.3,0.1

Type RM Length L Ch R = 1 ,13800   ,903,903,903
BEGIN DESCRIPTION:
Stream0581 19.0
END DESCRIPTION:
XS GIS Cut Line= 3
      2343274.97     13652075.02        2344075.       13651425.
        2344375.     13650625.01
#Sta/Elev= 30
  3969.2  397.92  4125.1  392.62    4189  391.54  4239.8  388.76  4289.6   388.8
  4317.1  387.12  4353.5  387.43  4403.1  385.38    4446  385.72  4595.1  383.02
  4607.4  382.89  4722.7  381.26  4772.3  381.15  4829.8  378.28  4879.3  378.88
  4900.2   377.3  5002.7  378.43    5005  373.57  5005.5  373.07  5014.6  373.57
  5021.4  377.58  5045.4  380.75  5118.4  380.42  5309.7  382.62  5373.8  382.21
  5638.1  386.24  5736.9  389.14  5759.2  388.16  5778.8  389.55  5854.4  390.91
#Mann= 8 ,-1 , 0
  3969.2     .05       0  4595.1     .07       0  4607.4     .05       0
  4722.7     .07       0  4900.2      .1       0    5005     .05       0
  5014.6      .1       0  5118.4     .07       0
Bank Sta=5005,5014.6
XS Rating Curve= 0 ,0
Exp/Cntr=0.3,0.1

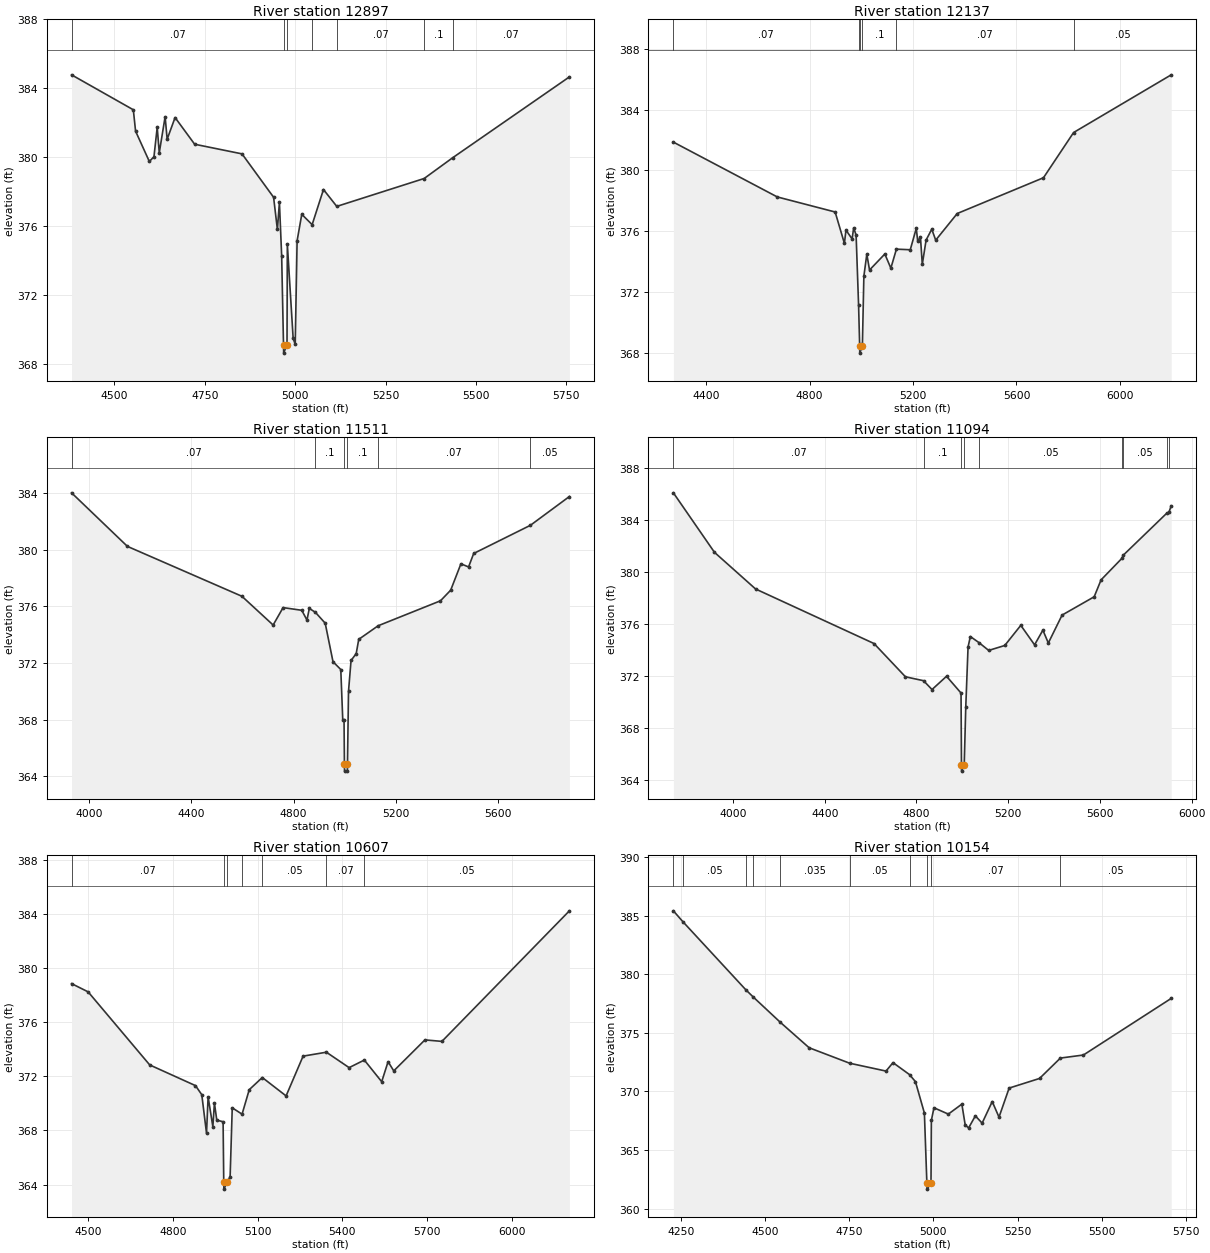
Type RM Length L Ch R = 1 ,12897   ,760,760,760
BEGIN DESCRIPTION:
Stream0581 18.0
END DESCRIPTION:
XS GIS Cut Line= 3
      2344175.01     13652224.99        2344475.       13651675.
        2344475.     13650924.98
#Sta/Elev= 30
  4381.8  384.77  4552.6  382.74  4558.8   381.5  4596.8  379.74  4609.6  380.01
  4618.6  381.72  4624.3  380.24  4640.5  382.34  4646.1  381.03    4668  382.29
  4722.1  380.74  4853.1  380.18  4940.4  377.66  4950.9  375.79  4956.5  377.37
  4962.7  374.26  4967.8  369.11  4968.3  368.61  4977.5  369.11  4978.4  374.94
  4994.5  369.46  5000.2  369.12  5005.4  375.13  5018.3  376.67    5047  376.07
  5078.3  378.11  5115.1  377.13  5356.7  378.75  5435.2  379.95  5758.3  384.65
#Mann= 7 ,-1 , 0
  4381.8     .07       0  4967.8     .05       0  4977.5     .07       0
    5047      .1       0  5115.1     .07       0  5356.7      .1       0
  5435.2     .07       0
Bank Sta=4967.8,4977.5
XS Rating Curve= 0 ,0
Exp/Cntr=0.3,0.1

Type RM Length L Ch R = 1 ,12137   ,626,626,626
BEGIN DESCRIPTION:
Stream0581 17.0
END DESCRIPTION:
XS GIS Cut Line= 3
      2344574.98     13652325.03      2344974.08     13651744.81
      2345471.19     13650628.85
#Sta/Elev= 30
  4272.7  381.86  4674.5  378.26  4898.5  377.27  4934.3  375.21  4940.4  376.08
  4964.1   375.5  4970.2  376.23  4979.6  375.75  4989.2  371.14  4993.3   368.5
  4993.8     368  5003.9   368.5  5009.6  373.05    5021   374.5  5031.5  373.46
  5090.7  374.51    5114  373.58  5135.5  374.83  5189.1  374.79  5212.4   376.2
  5217.8  375.36  5228.5  375.62  5235.6  373.83  5250.4  375.43  5272.3  376.14
  5287.5  375.42  5370.8  377.17  5704.4  379.52  5820.9  382.49  6198.6  386.28
#Mann= 6 ,-1 , 0
  4272.7     .07       0  4989.2      .1       0  4993.3     .05       0
  5003.9      .1       0  5135.5     .07       0  5820.9     .05       0
Bank Sta=4993.3,5003.9
XS Rating Curve= 0 ,0
Exp/Cntr=0.3,0.1

Type RM Length L Ch R = 1 ,11511   ,417,417,417
BEGIN DESCRIPTION:
Stream0581 16.0
END DESCRIPTION:
XS GIS Cut Line= 3
      2345319.36     13652719.68        2345525.       13651675.
      2345552.92     13650790.27
#Sta/Elev= 30
  3930.6  384.01  4149.4  380.23  4597.8  376.71  4720.1  374.68  4759.1  375.91
  4832.3  375.72  4852.6  375.03  4861.8  375.85  4885.5  375.58    4924  374.81
  4954.6  372.09  4985.1  371.54  4992.8  367.98  4997.8  367.98  4999.3  364.87
  4999.8  364.37  5010.8  364.37  5011.3  364.87  5015.3     370  5025.3  372.18
  5045.4  372.66  5055.4  373.67  5131.5  374.63  5375.5  376.39  5415.5  377.14
  5455.6     379  5485.6  378.78  5505.6  379.73  5727.9  381.72  5880.5  383.75
#Mann= 6 ,-1 , 0
  3930.6     .07       0  4885.5      .1       0  4999.3     .05       0
  5011.3      .1       0  5131.5     .07       0  5727.9     .05       0
Bank Sta=4999.3,5011.3
XS Rating Curve= 0 ,0
Exp/Cntr=0.3,0.1

Type RM Length L Ch R = 1 ,11094   ,487,487,487
BEGIN DESCRIPTION:
Stream0581 15.0
END DESCRIPTION:
XS GIS Cut Line= 3
      2345475.01     13652774.97        2345875.       13651575.
      2345888.03     13650669.18
#Sta/Elev= 30
  3740.1  386.07  3919.3  381.49  4098.5  378.67    4615  374.47    4752  371.91
  4830.8  371.61  4867.9  370.93  4931.2  371.95  4994.4  370.66  4996.3  365.15
  4996.8  364.65  5008.3  365.15    5015  369.57    5025   374.2    5035  375.01
  5072.7  374.54    5115  373.94    5185  374.32    5255  375.87    5315  374.37
  5351.3   375.5    5375  374.51    5435  376.66    5575  378.07    5605  379.37
    5696  381.03  5701.8  381.27  5890.8  384.49  5900.5  384.56  5910.9  385.07
#Mann= 9 ,-1 , 0
  3740.1     .07       0  4830.8      .1       0  4996.3     .05       0
  5008.3      .1       0  5072.7     .05       0    5696     .07       0
  5701.8     .05       0  5890.8     .07       0  5900.5     .05       0
Bank Sta=4996.3,5008.3
XS Rating Curve= 0 ,0
Exp/Cntr=0.3,0.1

Type RM Length L Ch R = 1 ,10607   ,453,453,453
BEGIN DESCRIPTION:
Stream0581 14.0
END DESCRIPTION:
XS GIS Cut Line= 3
      2346325.02     13652425.04        2346075.       13651925.
        2346175.     13650725.02
#Sta/Elev= 30
  4441.4  378.85  4500.1  378.24  4718.2  372.84  4880.3  371.31  4902.6  370.64
  4919.4  367.79    4925  370.48  4941.8  368.28  4947.4  370.02  4955.7  368.76
  4978.1  368.64  4980.4  364.16  4980.9  363.66  4992.5  364.16    5003  364.58
  5010.5  369.67  5045.3   369.2  5070.7  371.01  5116.9  371.91  5201.2  370.55
  5261.4  373.49  5343.9  373.78  5424.4  372.64  5478.3   373.2  5539.8   371.6
  5562.4  373.08  5582.5   372.4  5692.9  374.69  5753.1  374.58  6204.6  384.23
#Mann= 7 ,-1 , 0
  4441.4     .07       0  4980.4     .05       0  4992.5     .07       0
  5045.3      .1       0  5116.9     .05       0  5343.9     .07       0
  5478.3     .05       0
Bank Sta=4980.4,4992.5
XS Rating Curve= 0 ,0
Exp/Cntr=0.3,0.1

Type RM Length L Ch R = 1 ,10154   ,467,467,467
BEGIN DESCRIPTION:
Stream0581 13.0
END DESCRIPTION:
XS GIS Cut Line= 3
        2346675.       13652525.        2346475.       13651775.
        2346525.     13651074.99
#Sta/Elev= 30
  4228.2   385.4  4256.2  384.48  4443.4  378.66  4465.6  378.04  4546.1  375.88
  4631.2  373.72  4751.6   372.4  4859.5  371.73  4880.2  372.45  4929.2  371.43
  4946.8  370.83  4973.4  368.15  4980.8  362.16  4981.3  361.66    4993  362.16
  4994.1  367.52  5001.8   368.6  5044.5  368.06  5084.6  368.91  5094.6  367.13
  5104.7  366.88  5124.7  367.91  5144.8  367.29  5174.8  369.13  5194.9   367.8
    5225  370.28  5315.2   371.1  5377.2  372.84  5445.5   373.1  5706.2  377.93
#Mann= 10 ,-1 , 0
  4228.2     .07       0  4256.2     .05       0  4443.4    .035       0
  4465.6     .07       0  4546.1    .035       0  4751.6     .05       0
  4929.2     .07       0  4980.8     .05       0    4993     .07       0
  5377.2     .05       0
Bank Sta=4980.8,4993
XS Rating Curve= 0 ,0
Exp/Cntr=0.3,0.1

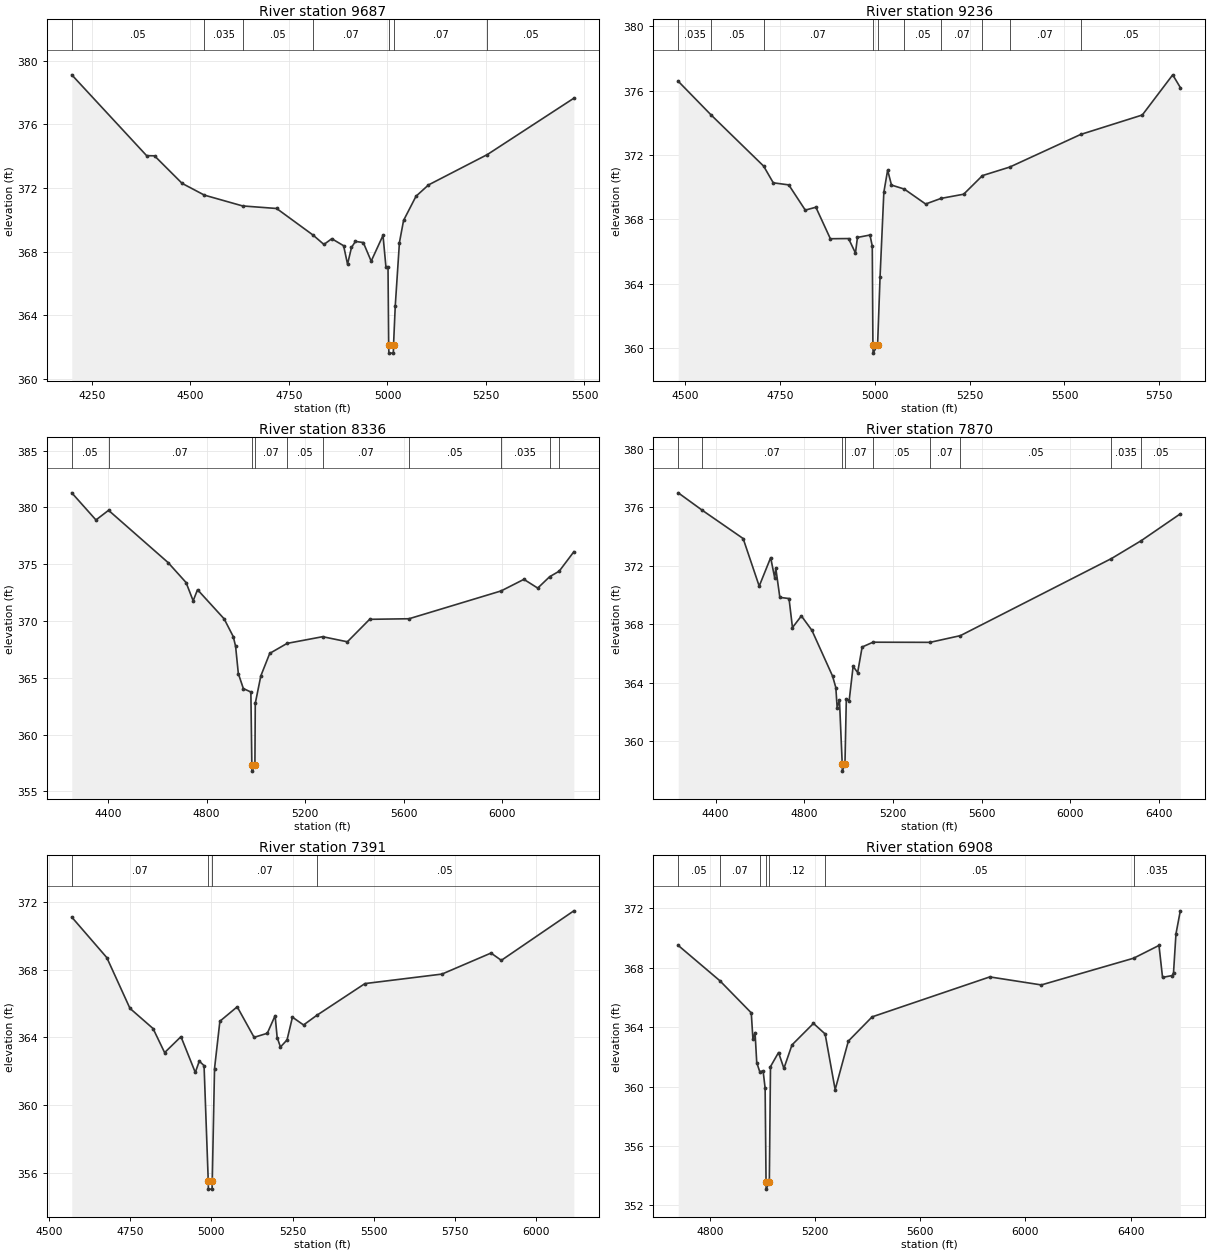
Type RM Length L Ch R = 1 ,9687    ,451,451,451
BEGIN DESCRIPTION:
Stream0581 12.0
END DESCRIPTION:
XS GIS Cut Line= 3
        2346725.     13652325.04        2346725.       13651525.
      2346574.99     13651074.98
#Sta/Elev= 30
  4198.7  379.12  4388.7  374.04  4408.7  374.03  4478.7   372.3  4535.3  371.56
  4632.4  370.88  4718.7  370.72  4811.1  369.05  4838.7  368.46  4858.7  368.82
  4888.7  368.38  4898.7  367.22  4908.7  368.27  4918.7  368.65  4938.7  368.58
  4958.7  367.41  4988.7  369.03  4996.2  367.03  5001.4  367.03  5003.1  362.13
  5003.6  361.63  5014.9  361.63  5015.4  362.13  5019.8   364.6  5030.4  368.58
  5040.9  369.97  5072.5  371.49  5104.1   372.2  5253.6  374.11  5473.1  377.65
#Mann= 7 ,-1 , 0
  4198.7     .05       0  4535.3    .035       0  4632.4     .05       0
  4811.1     .07       0  5003.1     .05       0  5015.4     .07       0
  5253.6     .05       0
Bank Sta=5003.1,5015.4
XS Rating Curve= 0 ,0
Exp/Cntr=0.3,0.1

Type RM Length L Ch R = 1 ,9236    ,900,900,900
BEGIN DESCRIPTION:
Stream0581 11.0
END DESCRIPTION:
XS GIS Cut Line= 3
      2346925.01     13652224.97        2347075.       13651725.
        2347125.     13650925.04
#Sta/Elev= 30
  4481.9  376.59  4567.8  374.51    4707  371.31  4732.4  370.27  4773.3  370.14
  4816.8  368.57  4844.7  368.75  4882.9  366.79  4930.8   366.8  4949.1   365.9
  4954.3  366.87  4987.3  367.02  4993.4  366.33  4995.1  360.17  4995.6  359.67
  5007.4  360.17  5013.9  364.41  5023.9  369.68  5033.9  371.06    5044  370.13
  5077.8  369.88  5134.1  368.95  5174.7   369.3  5234.3  369.56  5283.9  370.72
  5355.8  371.25  5542.8  373.28  5705.2  374.49  5785.4  376.99  5805.4   376.2
#Mann= 10 ,-1 , 0
  4481.9    .035       0  4567.8     .05       0    4707     .07       0
  4995.1     .05       0  5007.4     .07       0  5077.8     .05       0
  5174.7     .07       0  5283.9     .05       0  5355.8     .07       0
  5542.8     .05       0
Bank Sta=4995.1,5007.4
XS Rating Curve= 0 ,0
Exp/Cntr=0.3,0.1

Type RM Length L Ch R = 1 ,8336    ,466,466,466
BEGIN DESCRIPTION:
Stream0581 10.0
END DESCRIPTION:
XS GIS Cut Line= 3
      2347431.64     13652658.74        2347575.       13651925.
      2347462.19     13650638.95
#Sta/Elev= 30
  4252.3  381.29  4350.5   378.9  4401.7  379.75  4643.3  375.15  4716.4  373.39
  4745.2  371.78  4762.9  372.76    4871  370.19  4908.2  368.62  4917.5  367.77
  4928.6  365.37    4949  364.05  4979.5  363.75  4983.5  357.28    4984  356.78
  4995.9  357.28  4997.4  362.75    5020  365.17  5056.1  367.15  5126.6  368.03
  5271.1  368.62  5371.3  368.17  5461.7  370.15  5621.7   370.2  5995.5  372.65
  6088.1  373.67  6144.3   372.9  6192.5   373.9  6231.5  374.39  6290.9   376.1
#Mann= 10 ,-1 , 0
  4252.3     .05       0  4401.7     .07       0  4983.5     .05       0
  4995.9     .07       0  5126.6     .05       0  5271.1     .07       0
  5621.7     .05       0  5995.5    .035       0  6192.5     .05       0
  6231.5    .035       0
Bank Sta=4983.5,4995.9
XS Rating Curve= 0 ,0
Exp/Cntr=0.3,0.1

Type RM Length L Ch R = 1 ,7870    ,479,479,479
BEGIN DESCRIPTION:
Stream0581 9.0
END DESCRIPTION:
XS GIS Cut Line= 3
      2347827.69     13652618.12        2348025.       13651875.
      2347746.44     13650404.32
#Sta/Elev= 30
  4231.1     377  4339.1  375.81    4524  373.87  4596.5  370.61  4648.2  372.56
  4666.2  371.19  4671.4  371.83  4689.6  369.84    4731  369.76  4746.6  367.77
  4786.8  368.57  4834.4  367.58  4927.5  364.45  4942.3  363.66  4948.2  362.28
  4958.6  362.82  4971.1  358.44  4971.6  357.94  4983.5  358.44  4989.6  362.89
  5002.5  362.77  5020.3  365.12  5040.7  364.69    5061  366.44  5110.1  366.77
  5367.6  366.76  5504.5  367.22  6186.2   372.5  6320.1  373.72  6496.8  375.56
#Mann= 9 ,-1 , 0
  4231.1     .05       0  4339.1     .07       0  4971.1     .05       0
  4983.5     .07       0  5110.1     .05       0  5367.6     .07       0
  5504.5     .05       0  6186.2    .035       0  6320.1     .05       0
Bank Sta=4971.1,4983.5
XS Rating Curve= 0 ,0
Exp/Cntr=0.3,0.1

Type RM Length L Ch R = 1 ,7391    ,483,483,483
BEGIN DESCRIPTION:
Stream0581 8.0
END DESCRIPTION:
XS GIS Cut Line= 3
      2348225.03     13652224.96        2348475.       13651875.
        2348675.       13650775.
#Sta/Elev= 30
  4569.4  371.09  4677.5   368.7  4748.8  365.71    4820  364.52  4855.7   363.1
  4906.1  364.04  4950.3  361.93  4962.6   362.6  4977.3  362.33  4990.2  355.55
  4990.7  355.05  5002.1  355.05  5002.6  355.55  5009.6  362.16  5026.1  364.95
  5079.5   365.8  5131.6     364  5172.3  364.24  5196.4  365.28  5202.7  363.99
  5212.9  363.43  5233.2  363.85  5249.8  365.19  5284.1  364.73  5324.3  365.29
  5473.4  367.17  5710.9  367.73  5862.1  368.97  5893.9  368.54  6117.5  371.46
#Mann= 4 ,-1 , 0
  4569.4     .07       0  4990.2     .05       0  5002.6     .07       0
  5324.3     .05       0
Bank Sta=4990.2,5002.6
XS Rating Curve= 0 ,0
Exp/Cntr=0.3,0.1

Type RM Length L Ch R = 1 ,6908    ,478,478,478
BEGIN DESCRIPTION:
Stream0581 7.0
END DESCRIPTION:
XS GIS Cut Line= 3
        2348475.       13652375.        2348725.       13652175.
      2349046.04     13650618.83
#Sta/Elev= 30
  4680.1  369.51  4837.9  367.14  4957.8  364.97  4964.2  363.18  4972.2  363.64
  4978.6  361.62    4990  361.01  5002.8  361.06  5010.5   359.9    5014   353.6
  5014.5   353.1  5026.5   353.6  5030.9  361.35  5061.5   362.3  5081.9  361.23
  5112.6  362.81  5194.3  364.26  5238.6  363.55  5276.8   359.8    5327  363.07
  5417.4   364.7  5864.7  367.39  6060.7  366.85  6411.8  368.65  6508.1  369.51
  6521.6  367.36  6558.3  367.48  6563.4  367.68  6572.7  370.29  6589.2  371.84
#Mann= 7 ,-1 , 0
  4680.1     .05       0  4837.9     .07       0    4990     .12       0
    5014     .05       0  5026.5     .12       0  5238.6     .05       0
  6411.8    .035       0
Bank Sta=5014,5026.5
XS Rating Curve= 0 ,0
Exp/Cntr=0.3,0.1

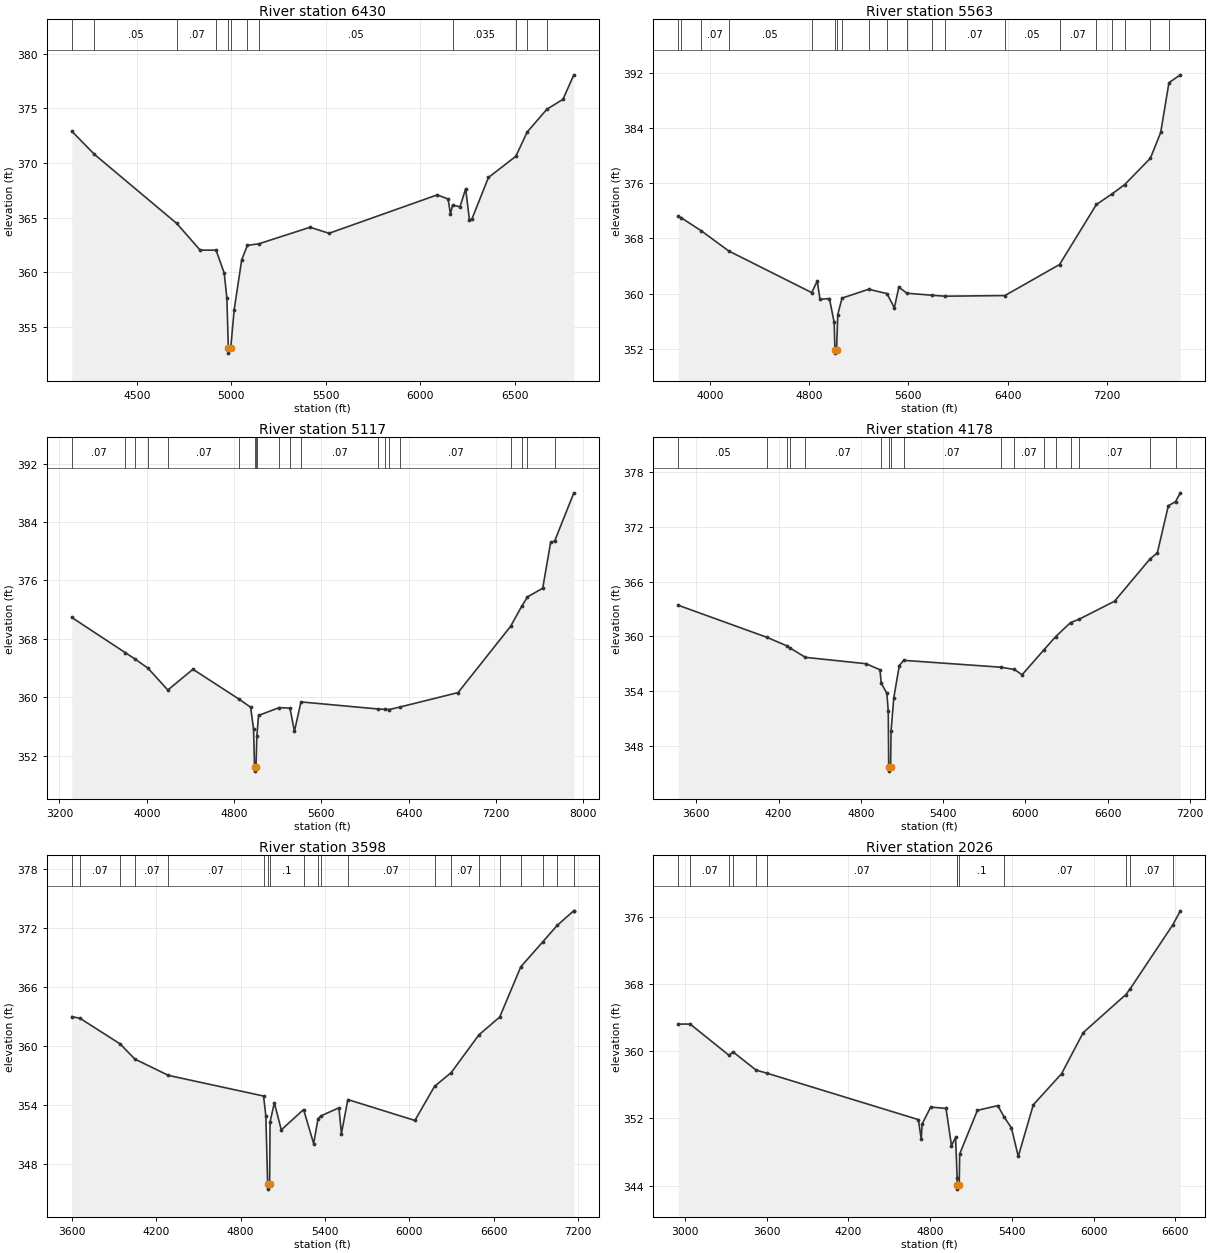
Type RM Length L Ch R = 1 ,6430    ,867,867,867
BEGIN DESCRIPTION:
Stream0581 6.0
END DESCRIPTION:
XS GIS Cut Line= 3
        2348525.       13652775.        2349125.       13652175.
        2349275.     13650374.97
#Sta/Elev= 30
  4156.3  372.91  4275.6   370.8  4711.4  364.48  4835.1  362.04  4919.4  362.04
  4962.4  359.94  4976.5  357.65  4984.2  353.13  4984.7  352.63  4997.1  353.13
  5014.9  356.58    5055  361.17  5085.1  362.48  5145.6  362.62  5416.2  364.13
  5516.6  363.58  6088.6  367.09  6146.3  366.71  6158.8  365.33  6169.7  366.16
    6209     366  6239.1  367.65  6259.2  364.77  6271.7  364.87  6359.5  368.68
  6504.7  370.62  6564.1  372.83  6668.2  374.91  6753.4  375.82  6811.1  378.06
#Mann= 12 ,-1 , 0
  4156.3    .035       0  4275.6     .05       0  4711.4     .07       0
  4919.4     .05       0  4984.2     .05       0  4997.1     .05       0
  5085.1     .12       0  5145.6     .05       0  6169.7    .035       0
  6504.7     .07       0  6564.1    .035       0  6668.2     .07       0
Bank Sta=4984.2,4997.1
XS Rating Curve= 0 ,0
Exp/Cntr=0.3,0.1

Type RM Length L Ch R = 1 ,5563    ,446,446,446
BEGIN DESCRIPTION:
Stream0581 5.0
END DESCRIPTION:
XS GIS Cut Line= 3
      2348724.96     13652975.02        2349825.       13652375.
      2350760.92     13649746.39
#Sta/Elev= 30
  3746.7  371.22  3770.6     371  3930.4  369.13  4153.1  366.18  4821.6  360.13
  4866.4  361.82  4888.2  359.15  4964.1  359.27  5002.4  355.83  5008.7  351.84
  5009.2  351.34  5021.7  351.84  5031.6  356.95  5065.6  359.33  5280.8  360.62
    5428  359.98  5487.2  357.92  5523.3  360.93  5588.1  360.04    5790  359.75
  5893.4  359.61  6377.4   359.7  6817.6  364.21  7114.2  372.93  7238.7  374.44
  7342.2  375.82  7549.2  379.65  7632.2   383.4  7698.5  390.62    7790  391.76
#Mann= 20 ,-1 , 0
  3746.7    .035       0  3770.6     .05       0  3930.4     .07       0
  4153.1     .05       0  4821.6     .07       0  5008.7     .05       0
  5021.7     .05       0  5065.6     .07       0  5280.8     .05       0
    5428    .035       0  5588.1     .07       0    5790    .035       0
  5893.4     .07       0  6377.4     .05       0  6817.6     .07       0
  7114.2     .05       0  7238.7    .035       0  7342.2     .05       0
  7549.2    .035       0  7698.5     .07       0
Bank Sta=5008.7,5021.7
XS Rating Curve= 0 ,0
Exp/Cntr=0.3,0.1

Type RM Length L Ch R = 1 ,5117    ,939,939,939
BEGIN DESCRIPTION:
Stream0581 4.0
END DESCRIPTION:
XS GIS Cut Line= 3
      2348758.71     13653544.37        2350175.       13652625.
       2350915.5     13649809.17
#Sta/Elev= 30
    3313  370.92    3802  366.11    3891  365.24  4010.6  363.98    4193  360.98
  4423.1  363.82  4847.7  359.71  4951.7  358.62  4978.8  355.63  4987.4  350.37
  4987.9  349.87  5000.5  350.37  5008.7  354.66  5024.3   357.5  5213.7  358.57
  5312.2   358.5  5353.1  355.32  5412.9  359.35  6120.5  358.38  6182.7  358.33
  6221.5  358.31  6322.6  358.66  6852.4  360.63  7333.4   369.7  7434.4  372.42
  7488.4  373.74  7627.9  374.92  7700.3  381.19  7737.7   381.4  7913.1  387.99
#Mann= 20 ,-1 , 0
    3313     .07       0    3802     .05       0    3891     .07       0
  4010.6     .05       0    4193     .07       0  4847.7     .05       0
  4987.4     .05       0  5000.5     .05       0  5008.7      .1       0
  5213.7     .07       0  5312.2    .035       0  5412.9     .07       0
  6120.5    .035       0  6182.7     .07       0  6221.5    .035       0
  6322.6     .07       0  7333.4    .035       0  7434.4     .05       0
  7488.4    .035       0  7737.7     .07       0
Bank Sta=4987.4,5000.5
XS Rating Curve= 0 ,0
Exp/Cntr=0.3,0.1

Type RM Length L Ch R = 1 ,4178    ,580,580,580
BEGIN DESCRIPTION:
XS7149
END DESCRIPTION:
XS GIS Cut Line= 3
       2349974.6     13653295.93      2350757.04     13652746.85
      2351045.11     13650058.21
#Sta/Elev= 30
    3469  363.41  4116.3  359.89  4262.3  358.95  4282.4  358.74  4395.8   357.7
  4839.1     357  4939.7  356.34  4948.3   354.9  4989.9  353.75    5000  351.78
  5003.2  345.73  5003.7  345.23    5017  345.73  5020.5  349.62  5040.2  353.26
  5080.5   356.8  5112.5  357.37  5820.8  356.62  5919.5  356.37  5975.5  355.79
  6135.7  358.54  6220.4  359.97  6328.8  361.51  6391.5  361.88  6649.4  363.85
  6907.1  368.47  6961.2  369.14  7041.6  374.32    7094  374.76  7128.9  375.73
#Mann= 17 ,-1 , 0
    3469     .05       0  4116.3     .07       0  4262.3     .05       0
  4282.4    .035       0  4395.8     .07       0  4948.3      .1       0
  5003.2     .05       0    5017      .1       0  5112.5     .07       0
  5820.8    .035       0  5919.5     .07       0  6135.7     .05       0
  6220.4     .07       0  6328.8     .05       0  6391.5     .07       0
  6907.1    .035       0    7094     .07       0
Bank Sta=5003.2,5017
XS Rating Curve= 0 ,0
Exp/Cntr=0.3,0.1

Type RM Length L Ch R = 1 ,3598    ,1572,1572,1572
BEGIN DESCRIPTION:
XS7148
END DESCRIPTION:
XS GIS Cut Line= 3
      2350558.03     13653302.76      2351374.75     13652595.85
       2351271.8     13650104.44
#Sta/Elev= 30
  3598.1  363.01  3656.7  362.84  3941.8  360.24  4047.8  358.69  4285.6  357.04
  4963.1  354.94  4979.4  352.94  4992.5  345.98    4993  345.48  5006.3  345.98
  5009.4  352.31    5040  354.25  5089.5   351.5  5248.2  353.57  5319.7  350.11
  5350.8  352.61    5371  352.92  5499.8  353.74  5517.4  351.12  5563.1  354.58
  6040.3  352.46  6180.6  355.93  6298.9  357.32  6496.3  361.16  6644.3  362.97
  6794.5  368.08  6950.1   370.6  7053.1  372.28  7170.6  373.76  7171.8  373.76
#Mann= 20 ,-1 , 0
  3598.1     .05       0  3656.7     .07       0  3941.8    .035       0
  4047.8     .07       0  4285.6     .07       0  4963.1      .1       0
  4992.5     .05       0  5006.3      .1       0  5248.2     .07       0
  5350.8     .12       0    5371     .07       0  5563.1     .07       0
  6180.6    .035       0  6298.9     .07       0  6496.3     .05       0
  6644.3     .05       0  6794.5     .07       0  6950.1     .05       0
  7053.1     .07       0  7170.6     .05       0
Bank Sta=4992.5,5006.3
XS Rating Curve= 0 ,0
Exp/Cntr=0.3,0.1

Type RM Length L Ch R = 1 ,2026    ,1015,1015,1015
BEGIN DESCRIPTION:
XS7147
END DESCRIPTION:
XS GIS Cut Line= 4
      2350606.04      13653357.7      2352026.78     13652163.45
      2352026.78     13651332.97       2351814.2     13650359.19
#Sta/Elev= 30
  2952.5  363.24  3039.9  363.24  3325.8  359.51  3354.3  359.93  3523.3  357.76
  3603.4  357.39  4714.4  351.86  4735.2   349.5  4741.8  351.34  4804.1  353.35
    4917   353.2    4957  348.76    4987  349.73  4998.8  344.87    5000  344.08
  5000.5  343.58  5013.9  344.08    5017  347.76    5147  352.96    5297  353.53
  5343.1  352.18    5397  350.87    5447  347.47    5557  353.62  5764.7  357.33
  5923.5  362.23  6236.5  366.76  6267.8  367.44  6581.3  375.08  6635.7  376.73
#Mann= 13 ,-1 , 0
  2952.5     .05       0  3039.9     .07       0  3325.8    .035       0
  3354.3     .07       0  3523.3    .035       0  3603.4     .07       0
  4998.8      .1       0    5000     .05       0  5013.9      .1       0
  5343.1     .07       0  6236.5    .035       0  6267.8     .07       0
  6581.3     .05       0
Bank Sta=5000,5013.9
XS Rating Curve= 0 ,0
Exp/Cntr=0.3,0.1