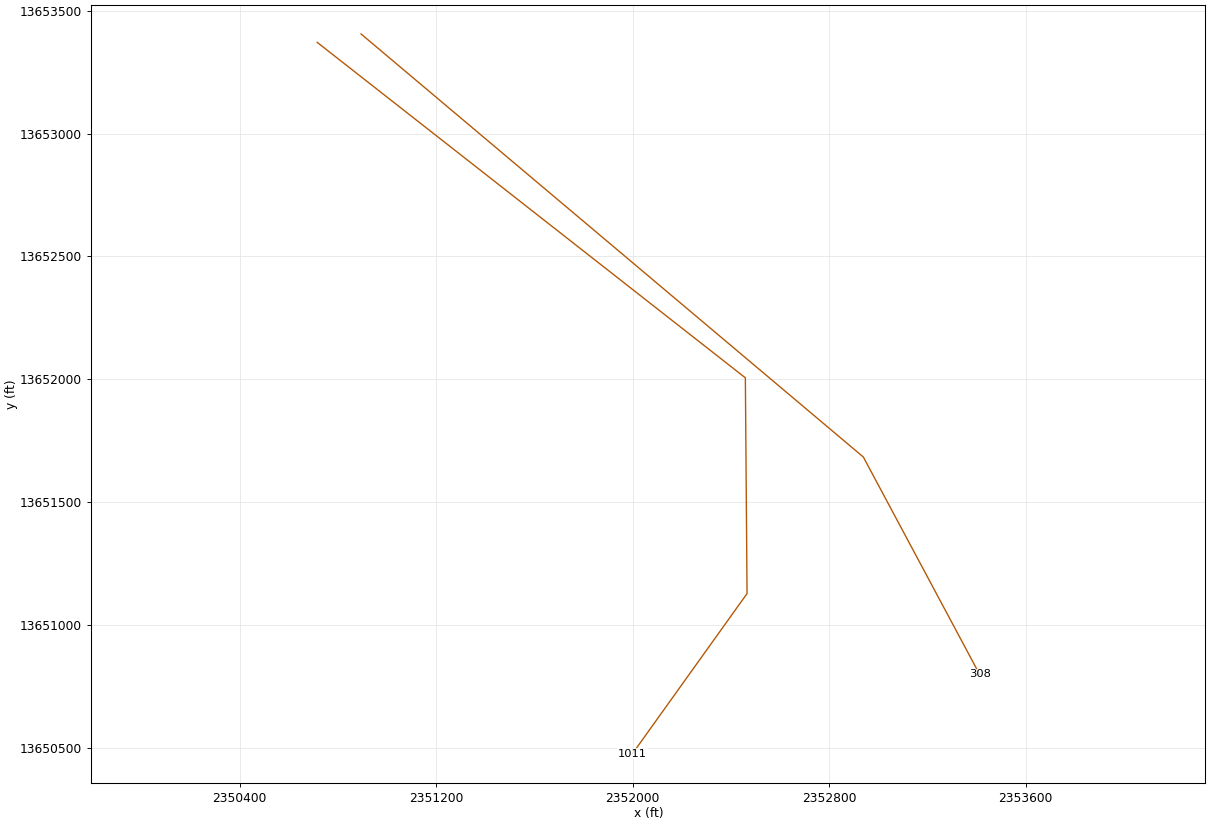
HEC-RAS study Stream0581.prj: Stream0581 Base Level Engineering

--- Stream0581.g01 (geometry) --- (continued)

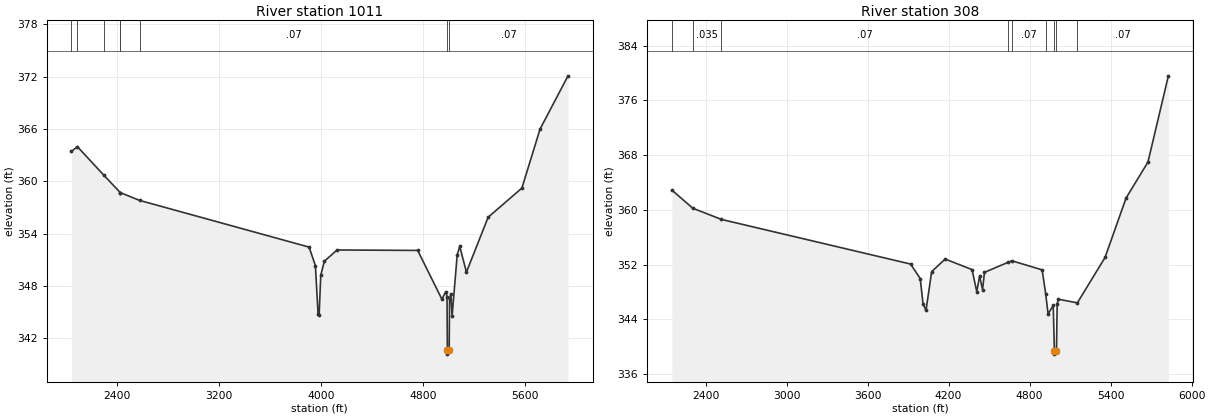
Type RM Length L Ch R = 1 ,1011    ,703,703,703
BEGIN DESCRIPTION:
XS7146
END DESCRIPTION:
XS GIS Cut Line= 4
      2350715.85     13653371.43      2352459.18     13652005.59
      2352466.05     13651127.06      2351999.66      13650475.5
#Sta/Elev= 30
  2043.1  363.42  2089.1  363.97  2298.5  360.67  2426.2   358.7  2426.5   358.7
    2577  357.81  3906.6  352.46  3956.3  350.33  3977.1  344.83  3985.3  344.68
  3998.4  349.26  4026.9  350.85  4126.3  352.13  4758.4  352.08  4948.4  346.49
  4978.4  347.35  4988.4   346.8  4991.3   340.7  4991.8   340.2  5005.5   340.7
  5008.4  346.51  5018.4  347.12  5028.4  344.55  5068.4  351.58  5088.4  352.54
  5140.7  349.59    5311  355.88  5575.8  359.22  5718.3  365.98  5937.6  372.08
#Mann= 8 ,-1 , 0
  2043.1     .05       0  2089.1     .07       0  2298.5    .035       0
  2426.2     .07       0  2426.5    .035       0    2577     .07       0
  4991.3     .05       0  5005.5     .07       0
Bank Sta=4991.3,5005.5
XS Rating Curve= 0 ,0
Exp/Cntr=0.3,0.1

Type RM Length L Ch R = 1 ,308     ,0,0,0
BEGIN DESCRIPTION:
XS7145
END DESCRIPTION:
XS GIS Cut Line= 3
       2350894.3     13653405.75      2352939.63     13651683.01
      2353412.57     13650798.82
#Sta/Elev= 30
  2150.7   362.9  2305.4  360.25  2518.1  358.61  3918.5  352.09  3989.9  349.97
  4010.8  346.29  4032.8  345.32  4074.5  350.98  4174.6  352.82  4373.6  351.28
  4408.7  348.06  4429.5  350.33  4451.6  348.37  4465.8  350.88  4642.5  352.36
  4669.9  352.56  4892.8  351.24  4919.5  347.68  4936.7   344.8  4974.9  346.04
  4983.5  339.43    4984  338.93  4998.9  339.43  5004.1  346.27  5013.1  346.95
  5153.6  346.42  5358.5  353.05  5514.4  361.74  5676.3  366.99  5827.6  379.59
#Mann= 9 ,-1 , 0
  2150.7     .07       0  2305.4    .035       0  2518.1     .07       0
  4642.5      .1       0  4669.9     .07       0  4919.5      .1       0
  4983.5     .05       0  4998.9      .1       0  5153.6     .07       0
Bank Sta=4983.5,4998.9
XS Rating Curve= 0 ,0
Exp/Cntr=0.3,0.1

Chan Stop Cuts=-1
Use User Specified Reach Order=0
Composite Channel Slope=5