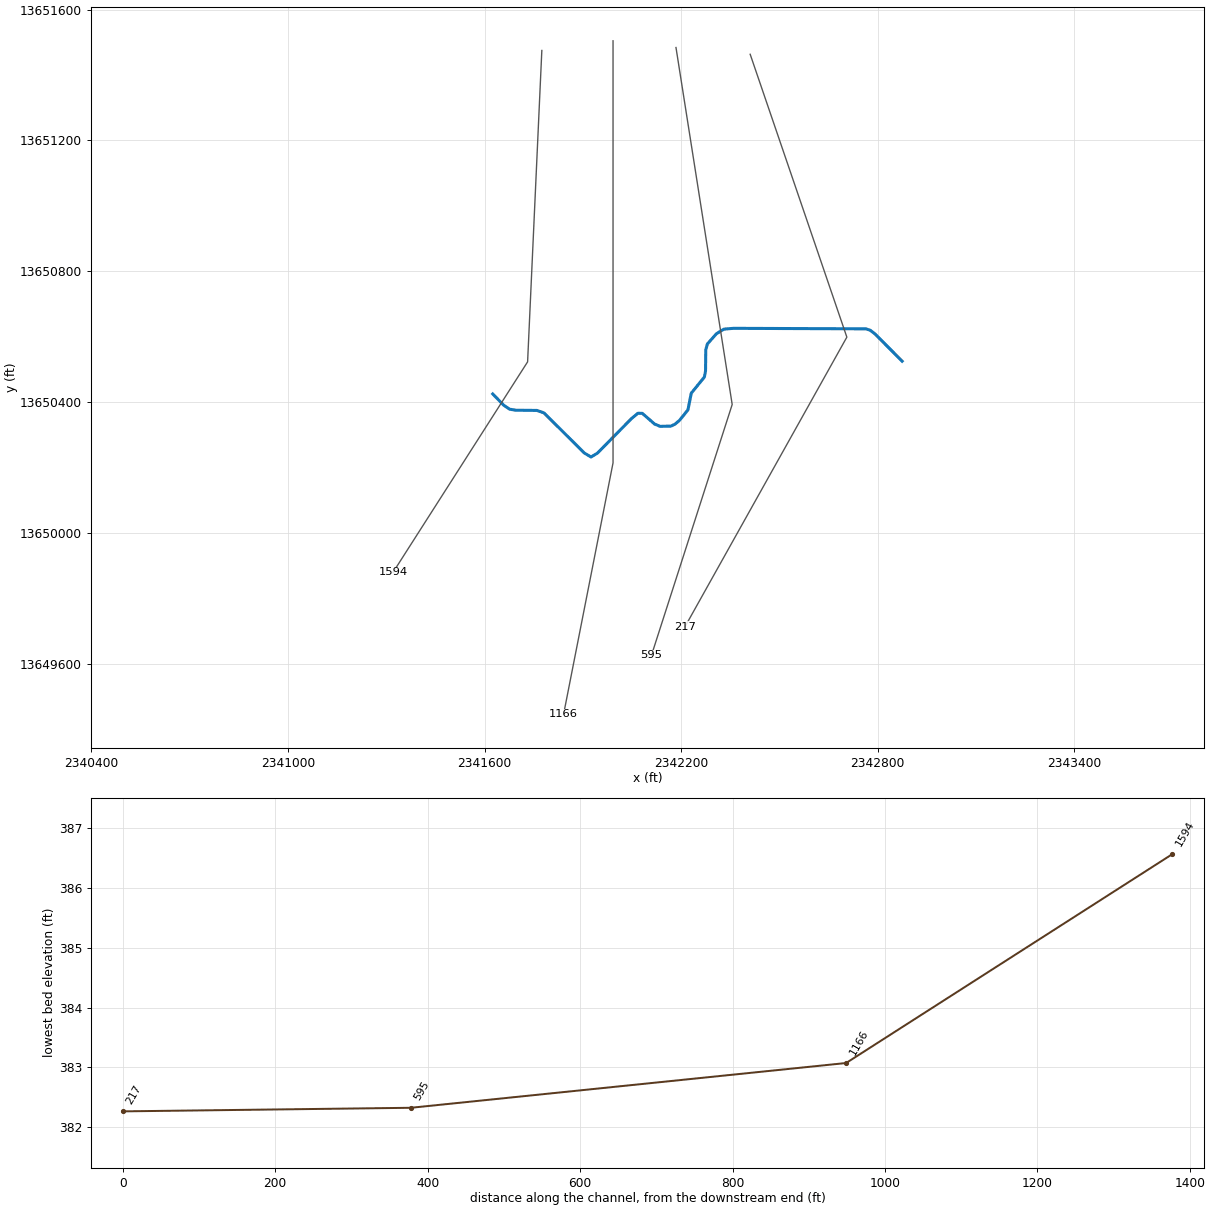
--- Stream0582.prj (project) ---

Proj Title=Stream0582 Base Level Engineering
Current Plan=p01
Default Exp/Contr=0.3,0.1
English Units
Geom File=g01
Flow File=f01
Plan File=p01
BEGIN DESCRIPTION:
Stream0582
END DESCRIPTION:

--- Stream0582.p01 (plan) ---

Plan Title=Multiple Run
Short Identifier=Multiple
Geom File=g01
Flow File=f01
Subcritical Flow
K Sum by GR= 0
Std Step Tol= 0.01
Critical Tol= 0.01
Num of Std Step Trials= 20
Max Error Tol= 0.3
Flow Tol Ratio= 0.001
Split Flow NTrial= 30
Split Flow Tol= 0.02
Split Flow Ratio= 0.02
Log Output Level= 0
Friction Slope Method= 1
Unsteady Friction Slope Method= 2
Unsteady Bridges Friction Slope Method= 1
Parabolic Critical Depth
Global Vel Dist=  1 , 1 , 1
Global Log Level= 0
CheckData=True
Encroach Param= -1, 0, 0, 0
BEGIN DESCRIPTION:
Multiple Run
END DESCRIPTION:

--- Stream0582.f01 (steady flow) ---

Flow Title=Multiple
Number of Profiles=7
Profile Names=10-year,25-year,50-year,1pct_min,100-year,1pct_plu,500-year
River Rch & RM= Stream0582,Reach-1,1594
     851    1412    1932    1280    2553    5095    4421
River Rch & RM= Stream0582,Reach-1,1166
     882    1465    2005    1329    2652    5291    4597
Boundary for River Rch & Prof#=Stream0582,Reach-1,1
Up Type=0
Dn Type=3
Dn Slope=0.005
Boundary for River Rch & Prof#=Stream0582,Reach-1,2
Up Type=0
Dn Type=3
Dn Slope=0.005
Boundary for River Rch & Prof#=Stream0582,Reach-1,3
Up Type=0
Dn Type=3
Dn Slope=0.005
Boundary for River Rch & Prof#=Stream0582,Reach-1,4
Up Type=0
Dn Type=3
Dn Slope=0.005
Boundary for River Rch & Prof#=Stream0582,Reach-1,5
Up Type=0
Dn Type=3
Dn Slope=0.005
Boundary for River Rch & Prof#=Stream0582,Reach-1,6
Up Type=0
Dn Type=3
Dn Slope=0.005
Boundary for River Rch & Prof#=Stream0582,Reach-1,7
Up Type=0
Dn Type=3
Dn Slope=0.005

--- Stream0582.g01 (geometry) ---

Geom Title=Existing Conditions

River Reach=Stream0582,Reach-1
Reach XY= 30
      2341625.00     13650425.00      2341657.95     13650391.13
      2341676.41     13650378.39      2341695.08     13650375.20
      2341759.81     13650374.53      2341781.18     13650367.15
      2341905.00     13650244.21      2341925.00     13650232.07
      2341945.00     13650244.21      2342048.31     13650349.27
      2342068.27     13650365.85      2342081.55     13650365.67
      2342118.97     13650333.12      2342135.69     13650325.87
      2342169.13     13650326.58      2342181.33     13650332.38
      2342195.48     13650344.27      2342221.14     13650376.36
      2342231.15     13650427.14      2342271.17     13650476.59
      2342274.76     13650495.11      2342275.46     13650559.93
      2342280.40     13650577.71      2342307.78     13650608.76
      2342330.65     13650623.03      2342359.74     13650625.52
      2342764.58     13650623.98      2342777.48     13650619.60
      2342791.81     13650608.67      2342875.00     13650525.00

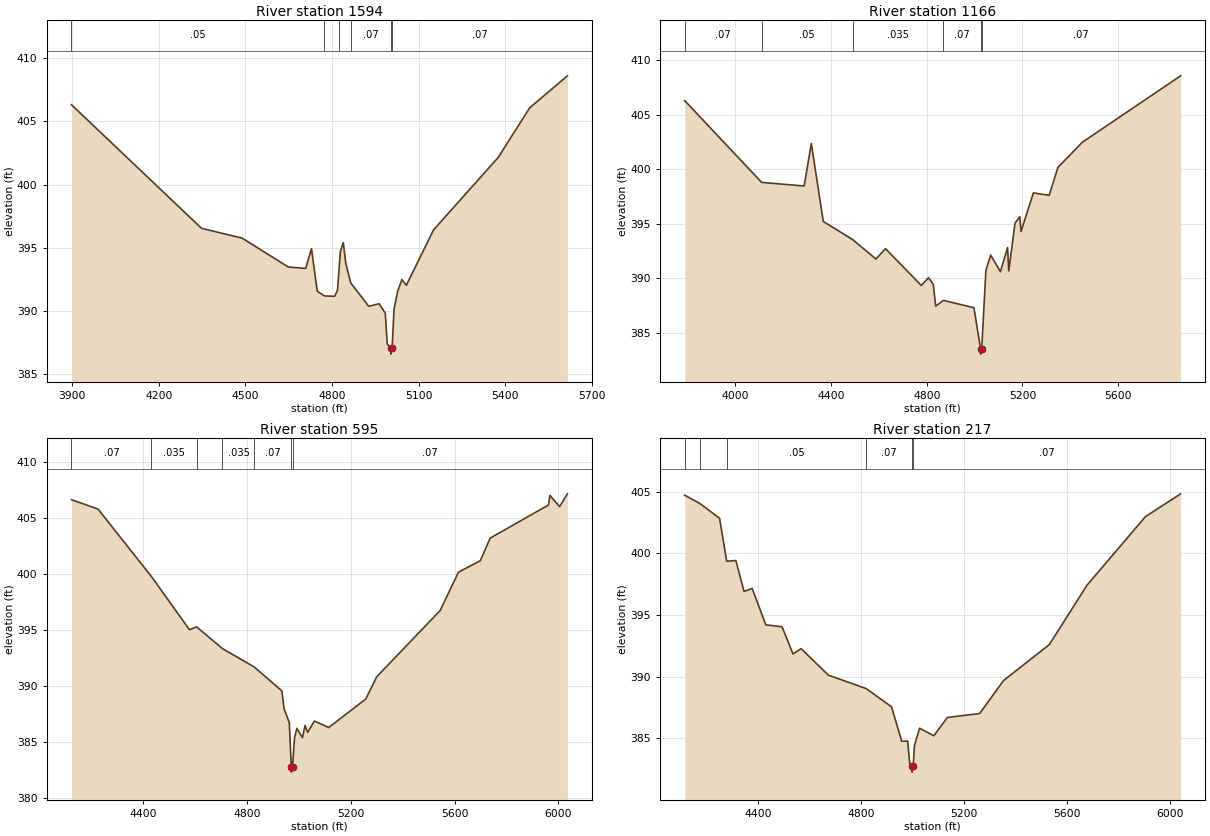
Type RM Length L Ch R = 1,1594,428,428,428
BEGIN DESCRIPTION:
Stream0582 2.0
END DESCRIPTION:
XS GIS Cut Line= 3
      2341775.00     13651475.01      2341731.55     13650523.08
      2341320.57     13649879.19
#Sta/Elev= 30
  3898.1  406.32  4348.6  396.53  4488.7  395.76  4648.9  393.47  4709.0  393.36
  4729.0  394.92  4749.0  391.55  4773.9  391.18  4809.1  391.15  4819.1  391.63
  4823.0  392.83  4829.1  394.71  4839.1  395.40  4847.6  393.78  4864.7  392.22
  4927.1  390.36  4963.4  390.56  4984.6  389.80  4991.1  387.39  5003.4  387.07
  5003.7  386.57  5008.2  387.07  5014.8  390.14  5026.9  391.51  5042.1  392.48
  5057.4  392.02  5151.3  396.40  5375.5  402.15  5484.6  406.08  5614.9  408.61
#Mann=6,-1,0
  3898.1    0.05       0  4773.9    0.07       0  4823.0   0.035       0
  4864.7    0.07       0  5003.4    0.05       0  5008.2    0.07       0
Bank Sta=5003.4,5008.2
Exp/Cntr=0.3,0.1

Type RM Length L Ch R = 1,1166,571,571,571
BEGIN DESCRIPTION:
XS7151
END DESCRIPTION:
XS GIS Cut Line= 3
      2341992.37     13651504.53      2341992.37     13650214.22
      2341841.37     13649445.52
#Sta/Elev= 30
  3787.7  406.29  4109.4  398.80  4287.2  398.47  4317.2  402.36  4367.2  395.22
  4489.6  393.57  4587.2  391.78  4627.2  392.73  4777.2  389.36  4807.2  390.07
  4827.2  389.45  4837.2  387.47  4869.6  387.99  4997.2  387.32  5024.8  383.57
  5025.2  383.07  5029.7  383.57  5047.2  390.73  5067.2  392.14  5107.8  390.62
  5137.7  392.83  5142.8  390.69  5168.9  395.07  5189.1  395.65  5194.2  394.30
  5245.7  397.84  5311.6  397.61  5348.5  400.18  5451.3  402.49  5861.4  408.56
#Mann=6,-1,0
  3787.7    0.07       0  4109.4    0.05       0  4489.6   0.035       0
  4869.6    0.07       0  5024.8    0.05       0  5029.7    0.07       0
Bank Sta=5024.8,5029.7
Exp/Cntr=0.3,0.1

Type RM Length L Ch R = 1,595,378,378,378
BEGIN DESCRIPTION:
XS7150
END DESCRIPTION:
XS GIS Cut Line= 3
      2342184.54     13651484.00      2342356.13     13650392.67
      2342109.53     13649625.47
#Sta/Elev= 30
  4124.0  406.63  4226.4  405.79  4431.5  399.79  4578.5  395.03  4606.4  395.28
  4705.7  393.34  4829.0  391.69  4934.8  389.56  4942.9  387.99  4963.2  386.73
  4970.9  382.82  4971.2  382.32  4975.8  382.82  4983.4  385.39  4992.3  386.23
  5013.8  385.39  5023.9  386.48  5034.0  385.87  5059.9  386.88  5115.0  386.30
  5257.8  388.84  5299.8  390.82  5544.8  396.75  5614.9  400.16  5699.0  401.18
  5737.3  403.20  5961.6  406.15  5967.3  407.01  6004.6  406.01  6034.6  407.15
#Mann=7,-1,0
  4124.0    0.07       0  4431.5   0.035       0  4606.4    0.07       0
  4705.7   0.035       0  4829.0    0.07       0  4970.9    0.05       0
  4975.8    0.07       0
Bank Sta=4970.9,4975.8
Exp/Cntr=0.3,0.1

Type RM Length L Ch R = 1,217,0,0,0
BEGIN DESCRIPTION:
Stream0582 1.0
END DESCRIPTION:
XS GIS Cut Line= 3
      2342411.05     13651463.34      2342706.17     13650598.57
      2342212.00     13649713.18
#Sta/Elev= 30
  4114.4  404.71  4174.5  404.02  4250.0  402.84  4277.6  399.36  4313.4  399.41
  4345.1  396.91  4376.8  397.15  4429.6  394.20  4493.0  394.04  4535.3  391.84
  4567.0  392.27  4673.2  390.12  4820.1  389.03  4918.6  387.55  4957.9  384.76
  4981.2  384.78  4989.6  382.85  4997.7  382.76  4998.1  382.26  5002.7  382.76
  5007.3  384.41  5027.4  385.82  5082.8  385.21  5135.3  386.69  5261.0  387.01
  5353.6  389.68  5531.8  392.60  5678.1  397.41  5905.4  402.97  6042.1  404.82
#Mann=6,-1,0
  4114.4    0.07       0  4174.5   0.035       0  4277.6    0.05       0
  4820.1    0.07       0  4997.7    0.05       0  5002.7    0.07       0
Bank Sta=4997.7,5002.7
Exp/Cntr=0.3,0.1

Chan Stop Cuts=-1