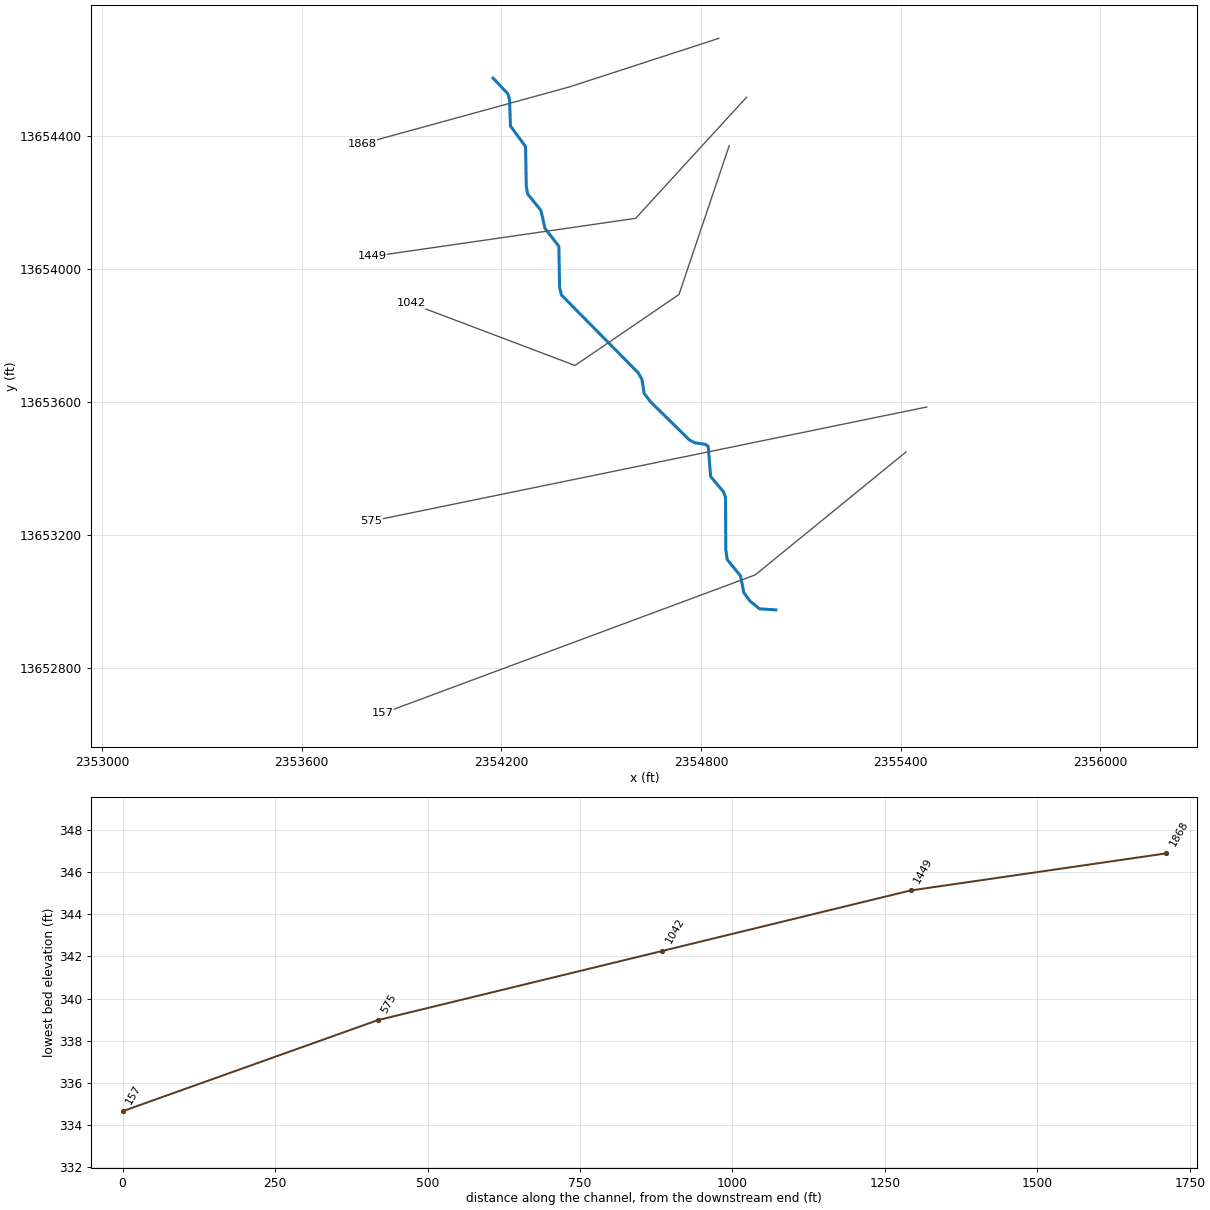
--- Stream0583.prj (project) ---

Proj Title=Stream0583 Base Level Engineering
Current Plan=p01
Default Exp/Contr=0.3,0.1
English Units
Geom File=g01
Flow File=f01
Plan File=p01
BEGIN DESCRIPTION:
Stream0583
END DESCRIPTION:

--- Stream0583.p01 (plan) ---

Plan Title=Multiple Run
Short Identifier=Multiple
Geom File=g01
Flow File=f01
Subcritical Flow
K Sum by GR= 0
Std Step Tol= 0.01
Critical Tol= 0.01
Num of Std Step Trials= 20
Max Error Tol= 0.3
Flow Tol Ratio= 0.001
Split Flow NTrial= 30
Split Flow Tol= 0.02
Split Flow Ratio= 0.02
Log Output Level= 0
Friction Slope Method= 1
Unsteady Friction Slope Method= 2
Unsteady Bridges Friction Slope Method= 1
Parabolic Critical Depth
Global Vel Dist=  1 , 1 , 1
Global Log Level= 0
CheckData=True
Encroach Param= -1, 0, 0, 0
BEGIN DESCRIPTION:
Multiple Run
END DESCRIPTION:

--- Stream0583.f01 (steady flow) ---

Flow Title=Multiple
Number of Profiles=7
Profile Names=10-year,25-year,50-year,1pct_min,100-year,1pct_plu,500-year
River Rch & RM= Stream0583,Reach-1,1868
     479     760    1008     648    1293    2581    2109
Boundary for River Rch & Prof#=Stream0583,Reach-1,1
Up Type=0
Dn Type=3
Dn Slope=0.005
Boundary for River Rch & Prof#=Stream0583,Reach-1,2
Up Type=0
Dn Type=3
Dn Slope=0.005
Boundary for River Rch & Prof#=Stream0583,Reach-1,3
Up Type=0
Dn Type=3
Dn Slope=0.005
Boundary for River Rch & Prof#=Stream0583,Reach-1,4
Up Type=0
Dn Type=3
Dn Slope=0.005
Boundary for River Rch & Prof#=Stream0583,Reach-1,5
Up Type=0
Dn Type=3
Dn Slope=0.005
Boundary for River Rch & Prof#=Stream0583,Reach-1,6
Up Type=0
Dn Type=3
Dn Slope=0.005
Boundary for River Rch & Prof#=Stream0583,Reach-1,7
Up Type=0
Dn Type=3
Dn Slope=0.005

--- Stream0583.g01 (geometry) ---

Geom Title=Existing Conditions

River Reach=Stream0583,Reach-1
Reach XY= 30
      2354175.00     13654575.00      2354219.78     13654527.55
      2354224.47     13654509.78      2354227.32     13654430.96
      2354272.73     13654369.06      2354274.81     13654249.92
      2354278.76     13654226.56      2354318.88     13654177.18
      2354331.12     13654122.82      2354372.75     13654069.07
      2354374.98     13653944.99      2354380.47     13653922.55
      2354611.37     13653688.21      2354622.47     13653668.95
      2354628.98     13653626.65      2354648.01     13653601.53
      2354765.62     13653485.90      2354781.52     13653477.73
      2354813.26     13653473.00      2354821.84     13653466.66
      2354828.89     13653376.67      2354866.86     13653331.06
      2354873.78     13653314.50      2354874.64     13653154.85
      2354878.75     13653126.55      2354918.87     13653077.16
      2354928.83     13653026.45      2354947.72     13653001.15
      2354976.03     13652978.14      2355025.00     13652975.00

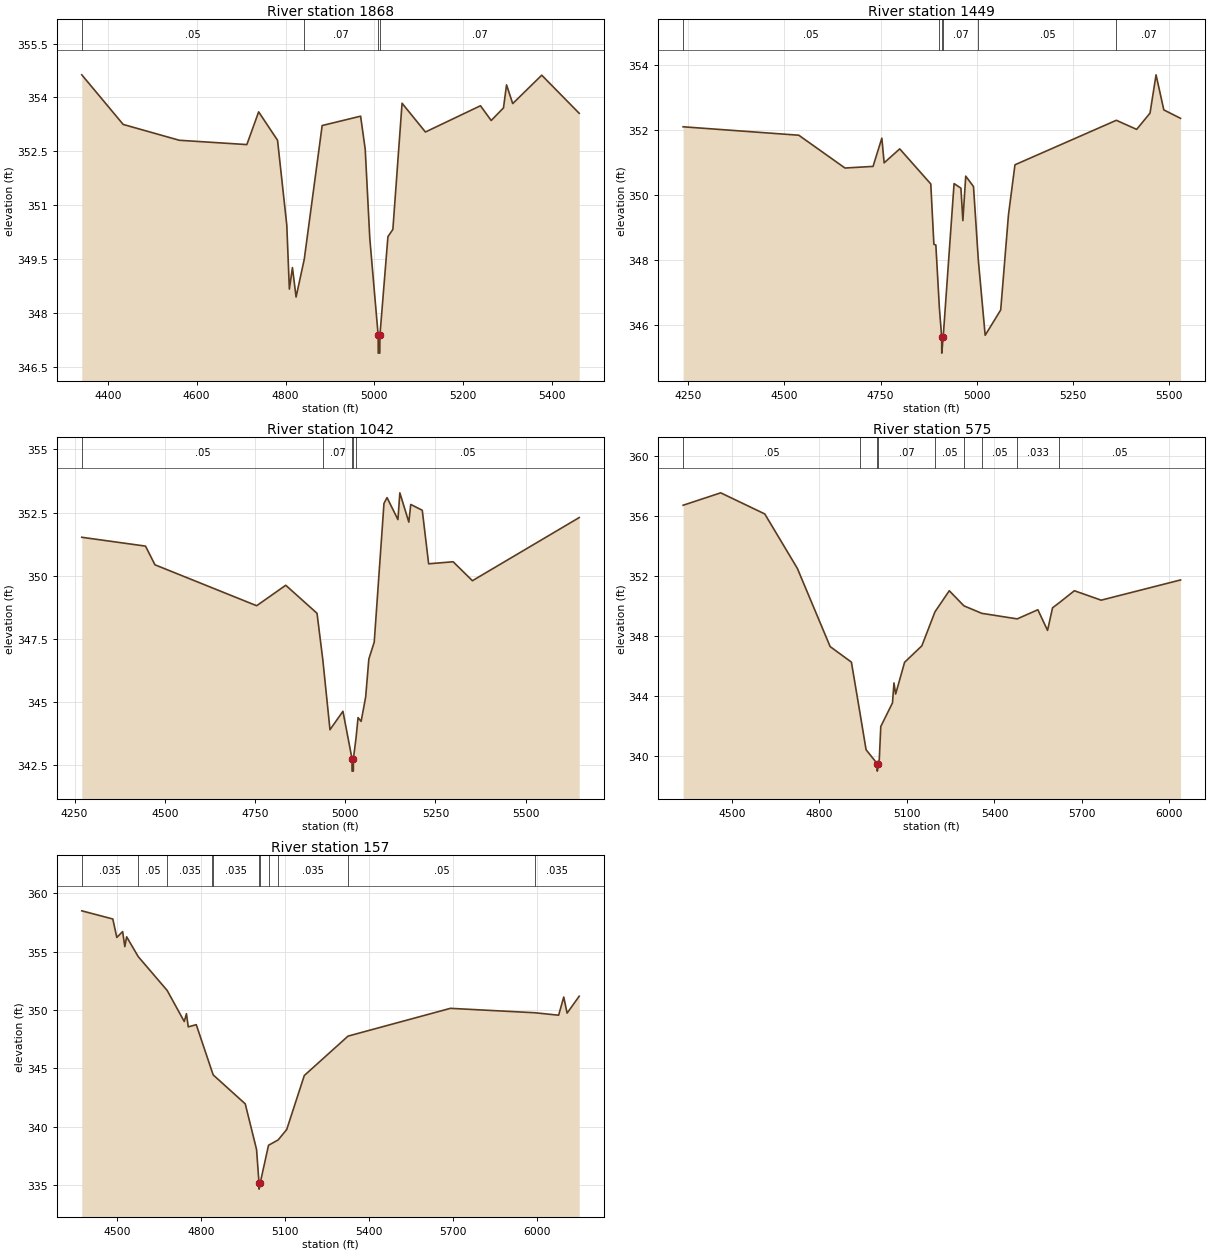
Type RM Length L Ch R = 1,1868,419,419,419
BEGIN DESCRIPTION:
XS7156
END DESCRIPTION:
XS GIS Cut Line= 3
      2354853.66     13654694.80      2354405.73     13654548.96
      2353780.71     13654377.08
#Sta/Elev= 30
  4341.5  354.63  4434.7  353.25  4560.9  352.81  4712.9  352.69  4739.5  353.60
  4782.0  352.81  4802.8  350.45  4808.6  348.67  4815.5  349.27  4823.7  348.45
  4842.1  349.50  4882.4  353.22  4968.9  353.48  4979.3  352.56  4989.6  350.08
  5008.4  347.39  5008.6  346.89  5012.1  346.89  5012.4  347.39  5030.4  350.13
  5041.5  350.33  5062.2  353.84  5114.8  353.04  5238.6  353.77  5262.8  353.36
  5290.4  353.71  5297.3  354.35  5311.2  353.83  5376.5  354.62  5460.8  353.56
#Mann=4,-1,0
  4341.5    0.05       0  4842.1    0.07       0  5008.4    0.05       0
  5012.4    0.07       0
Bank Sta=5008.4,5012.4
Exp/Cntr=0.3,0.1

Type RM Length L Ch R = 1,1449,407,407,407
BEGIN DESCRIPTION:
XS7155
END DESCRIPTION:
XS GIS Cut Line= 3
      2354936.98     13654517.71      2354603.65     13654153.13
      2353812.00     13654038.54
#Sta/Elev= 30
  4236.5  352.10  4537.4  351.84  4657.6  350.83  4730.5  350.88  4753.4  351.75
  4759.4  350.99  4799.9  351.42  4880.7  350.34  4888.8  348.48  4893.9  348.46
  4903.1  346.52  4909.0  345.63  4909.3  345.13  4913.0  345.63  4941.3  350.35
  4959.1  350.21  4964.2  349.21  4971.6  350.58  4991.8  350.26  5004.5  347.98
  5022.2  345.68  5062.6  346.46  5082.8  349.39  5099.7  350.93  5363.4  352.30
  5416.2  352.02  5451.0  352.52  5466.7  353.70  5486.9  352.62  5530.4  352.36
#Mann=6,-1,0
  4236.5    0.05       0  4903.1    0.07       0  4909.0    0.05       0
  4913.0    0.07       0  5004.5    0.05       0  5363.4    0.07       0
Bank Sta=4909,4913
Exp/Cntr=0.3,0.1

Type RM Length L Ch R = 1,1042,467,467,467
BEGIN DESCRIPTION:
XS7154
END DESCRIPTION:
XS GIS Cut Line= 4
      2354884.89     13654371.85      2354733.85     13653923.96
      2354421.35     13653710.42      2353928.33     13653897.25
#Sta/Elev= 30
  4269.9  351.52  4446.5  351.17  4472.7  350.43  4754.5  348.81  4835.1  349.62
  4921.8  348.51  4937.9  346.66  4957.7  343.90  4993.6  344.63  5018.6  342.76
  5018.9  342.26  5022.4  342.26  5022.6  342.76  5029.7  343.55  5035.5  344.38
  5044.0  344.23  5056.5  345.19  5065.4  346.70  5080.3  347.37  5107.3  352.86
  5115.8  353.09  5146.0  352.22  5151.3  353.28  5176.2  352.12  5181.5  352.82
  5213.4  352.59  5231.1  350.47  5299.0  350.55  5352.4  349.80  5648.3  352.30
#Mann=5,-1,0
  4269.9    0.05       0  4937.9    0.07       0  5018.6    0.05       0
  5022.6    0.07       0  5029.7    0.05       0
Bank Sta=5018.6,5022.6
Exp/Cntr=0.3,0.1

Type RM Length L Ch R = 1,575,418,418,418
BEGIN DESCRIPTION:
XS7153
END DESCRIPTION:
XS GIS Cut Line= 2
      2355478.69     13653585.43      2353808.43     13653242.01
#Sta/Elev= 30
  4332.7  356.73  4461.5  357.56  4612.6  356.15  4724.4  352.51  4836.7  347.29
  4909.6  346.25  4937.9  342.98  4959.9  340.40  4998.0  339.47  4998.3  338.97
  5002.0  339.47  5005.2  339.76  5010.3  341.95  5050.4  343.53  5055.5  344.86
  5061.3  344.12  5091.9  346.24  5151.1  347.34  5196.0  349.61  5245.1  351.02
  5295.3  350.01  5356.6  349.51  5477.9  349.14  5548.8  349.75  5582.0  348.37
  5599.1  349.88  5620.8  350.20  5673.9  351.02  5765.8  350.39  6037.9  351.74
#Mann=9,-1,0
  4332.7    0.05       0  4937.9    0.07       0  4998.0    0.05       0
  5002.0    0.07       0  5196.0    0.05       0  5295.3    0.07       0
  5356.6    0.05       0  5477.9   0.033       0  5620.8    0.05       0
Bank Sta=4998,5002
Exp/Cntr=0.3,0.1

Type RM Length L Ch R = 1,157,0,0,0
BEGIN DESCRIPTION:
XS7152
END DESCRIPTION:
XS GIS Cut Line= 3
      2355416.14     13653450.00      2354963.02     13653080.21
      2353843.19     13652663.53
#Sta/Elev= 30
  4372.5  358.51  4483.5  357.81  4497.8  356.23  4518.6  356.73  4526.5  355.44
  4533.0  356.28  4574.3  354.59  4678.1  351.68  4739.1  349.02  4747.0  349.69
  4753.4  348.56  4782.1  348.75  4839.7  344.65  4842.8  344.44  4957.4  341.96
  4997.9  338.04  5006.6  335.15  5006.9  334.65  5010.6  335.15  5040.6  338.41
  5075.1  338.87  5105.7  339.76  5168.6  344.39  5325.2  347.77  5691.5  350.15
  5994.7  349.77  6078.6  349.56  6096.9  351.12  6108.9  349.74  6152.2  351.19
#Mann=11,-1,0
  4372.5   0.035       0  4574.3    0.05       0  4678.1   0.035       0
  4839.7    0.07       0  4842.8   0.035       0  5006.6   0.035       0
  5010.6   0.035       0  5040.6    0.12       0  5075.1   0.035       0
  5325.2    0.05       0  5994.7   0.035       0
Bank Sta=5006.6,5010.6
Exp/Cntr=0.3,0.1

Chan Stop Cuts=-1