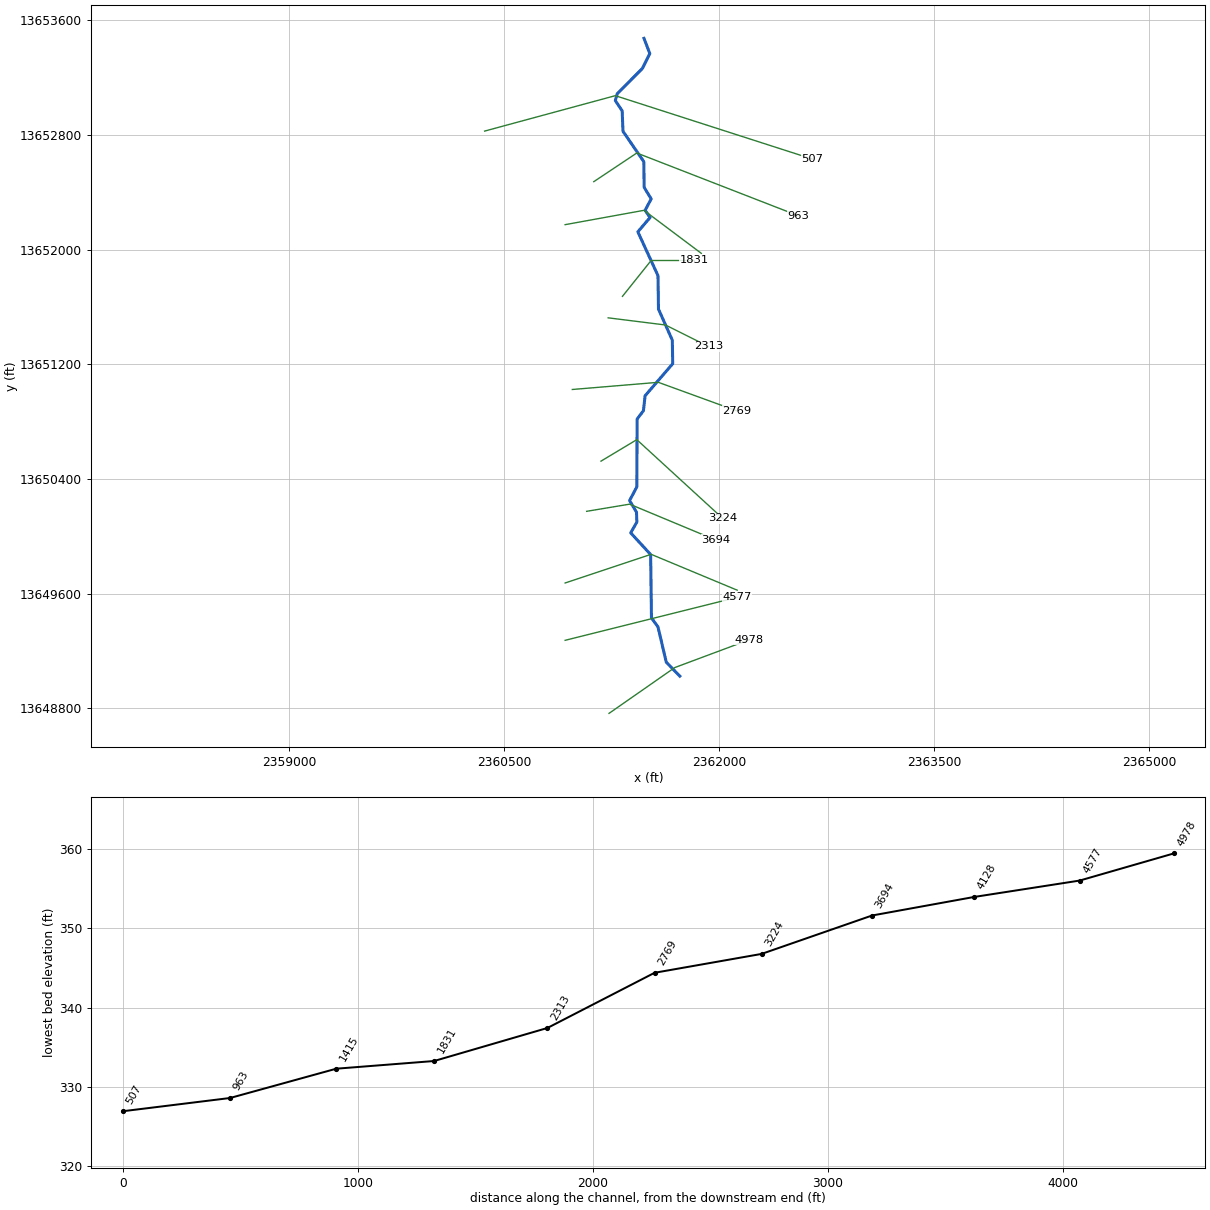
--- Stream0585.prj (project) ---

Proj Title=Stream0585 Base Level Engineering
Current Plan=p01
Default Exp/Contr=0.3,0.1
English Units
Geom File=g01
Flow File=f01
Plan File=p01
BEGIN DESCRIPTION:
Stream0585
END DESCRIPTION:

--- Stream0585.p01 (plan) ---

Plan Title=Multiple Run
Short Identifier=Multiple
Geom File=g01
Flow File=f01
Subcritical Flow
K Sum by GR= 0
Std Step Tol= 0.01
Critical Tol= 0.01
Num of Std Step Trials= 20
Max Error Tol= 0.3
Flow Tol Ratio= 0.001
Split Flow NTrial= 30
Split Flow Tol= 0.02
Split Flow Ratio= 0.02
Log Output Level= 0
Friction Slope Method= 1
Unsteady Friction Slope Method= 2
Unsteady Bridges Friction Slope Method= 1
Parabolic Critical Depth
Global Vel Dist=  1 , 1 , 1
Global Log Level= 0
CheckData=True
Encroach Param= -1, 0, 0, 0
BEGIN DESCRIPTION:
Multiple Run
END DESCRIPTION:

--- Stream0585.f01 (steady flow) ---

Flow Title=Multiple
Number of Profiles=7
Profile Names=10-year,25-year,50-year,1pct_min,100-year,1pct_plu,500-year
River Rch & RM= Stream0585,Reach-1,4978
     313     486     637     405     808    1613    1288
Boundary for River Rch & Prof#=Stream0585,Reach-1,1
Up Type=0
Dn Type=3
Dn Slope=0.005
Boundary for River Rch & Prof#=Stream0585,Reach-1,2
Up Type=0
Dn Type=3
Dn Slope=0.005
Boundary for River Rch & Prof#=Stream0585,Reach-1,3
Up Type=0
Dn Type=3
Dn Slope=0.005
Boundary for River Rch & Prof#=Stream0585,Reach-1,4
Up Type=0
Dn Type=3
Dn Slope=0.005
Boundary for River Rch & Prof#=Stream0585,Reach-1,5
Up Type=0
Dn Type=3
Dn Slope=0.005
Boundary for River Rch & Prof#=Stream0585,Reach-1,6
Up Type=0
Dn Type=3
Dn Slope=0.005
Boundary for River Rch & Prof#=Stream0585,Reach-1,7
Up Type=0
Dn Type=3
Dn Slope=0.005

--- Stream0585.g01 (geometry) ---

Geom Title=Existing Conditions

River Reach=Stream0585,Reach-1
Reach XY= 30
      2361725.00     13649025.00      2361630.46     13649122.55
      2361572.64     13649369.02      2361527.26     13649430.94
      2361521.46     13649873.54      2361382.32     13650024.90
      2361425.31     13650099.96      2361422.80     13650169.03
      2361374.60     13650250.00      2361424.91     13650345.03
      2361427.26     13650819.06      2361471.14     13650876.60
      2361482.86     13650981.17      2361675.44     13651204.82
      2361672.74     13651369.06      2361576.22     13651585.50
      2361572.74     13651819.06      2361432.31     13652125.09
      2361517.43     13652225.00      2361482.84     13652274.91
      2361525.21     13652354.79      2361476.24     13652435.50
      2361473.80     13652614.50      2361328.55     13652826.47
      2361322.70     13652969.07      2361275.03     13653040.42
      2361288.12     13653088.22      2361464.25     13653265.32
      2361515.72     13653368.41      2361475.00     13653475.00

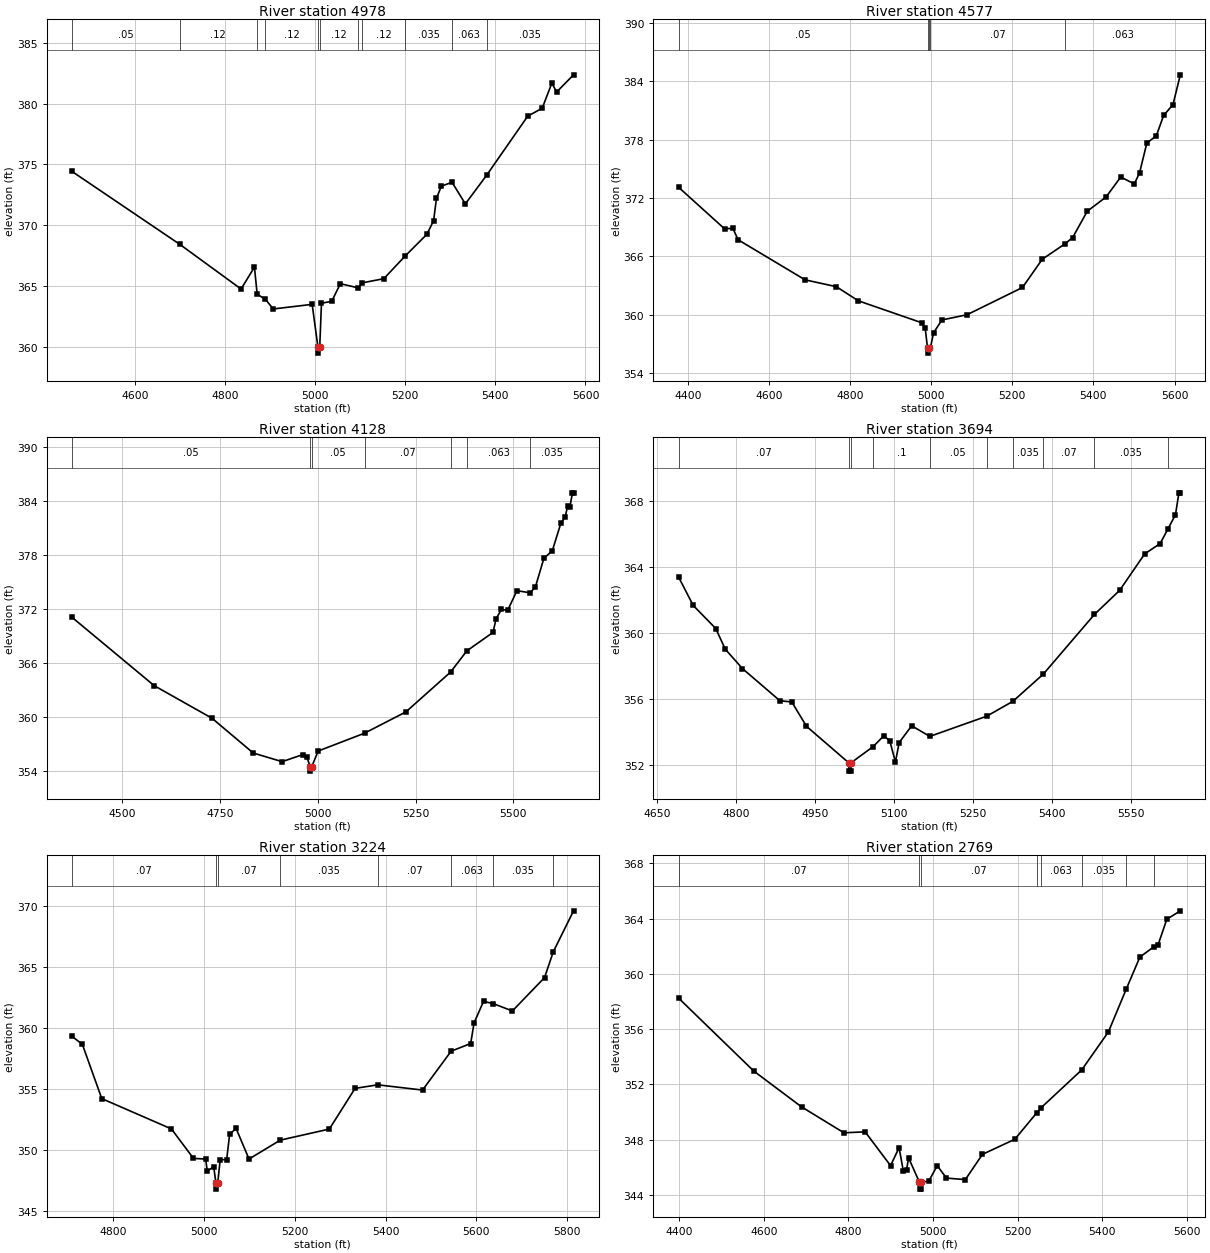
Type RM Length L Ch R = 1,4978,401,401,401
BEGIN DESCRIPTION:
XS7164
END DESCRIPTION:
XS GIS Cut Line= 3
      2361231.21     13648765.25      2361689.58     13649084.72
      2362210.17     13649279.07
#Sta/Elev= 30
  4459.1  374.43  4698.4  368.44  4835.1  364.75  4864.8  366.55  4870.9  364.32
  4889.1  363.91  4906.6  363.11  4993.0  363.49  5005.8  359.98  5006.1  359.48
  5009.8  359.98  5013.7  363.59  5036.3  363.73  5055.6  365.19  5095.8  364.84
  5104.5  365.26  5152.2  365.60  5199.7  367.47  5247.8  369.25  5262.7  370.37
  5269.1  372.21  5279.8  373.20  5303.6  373.53  5333.2  371.75  5380.6  374.11
  5471.9  378.97  5503.9  379.61  5525.3  381.68  5536.0  380.95  5573.5  382.36
#Mann=11,-1,0
  4459.1    0.05       0  4698.4    0.12       0  4870.9    0.05       0
  4889.1    0.12       0  5005.8    0.05       0  5009.8    0.12       0
  5095.8    0.05       0  5104.5    0.12       0  5199.7   0.035       0
  5303.6   0.063       0  5380.6   0.035       0
Bank Sta=5005.8,5009.8
Exp/Cntr=0.3,0.1

Type RM Length L Ch R = 1,4577,449,449,449
BEGIN DESCRIPTION:
Stream0585 10.0
END DESCRIPTION:
XS GIS Cut Line= 3
      2360925.04     13649275.01      2361525.00     13649425.00
      2362125.01     13649575.00
#Sta/Elev= 30
  4377.4  373.11  4490.7  368.84  4511.4  368.88  4524.2  367.71  4689.2  363.59
  4766.5  362.88  4820.6  361.43  4977.8  359.16  4985.5  358.59  4991.2  356.55
  4991.5  356.05  4995.2  356.55  4998.0  356.55  5006.1  358.15  5026.7  359.46
  5088.6  360.00  5225.2  362.80  5274.1  365.71  5330.4  367.30  5348.9  367.94
  5384.9  370.64  5431.3  372.11  5467.4  374.16  5500.9  373.45  5513.8  374.59
  5531.8  377.66  5555.0  378.39  5573.1  380.49  5596.2  381.61  5614.3  384.67
#Mann=5,-1,0
  4377.4    0.05       0  4991.2    0.05       0  4995.2    0.05       0
  4998.0    0.07       0  5330.4   0.063       0
Bank Sta=4991.2,4995.2
Exp/Cntr=0.3,0.1

Type RM Length L Ch R = 1,4128,434,434,434
BEGIN DESCRIPTION:
Stream0585 9.0
END DESCRIPTION:
XS GIS Cut Line= 3
      2360925.00     13649675.00      2361525.00     13649875.00
      2362125.04     13649624.98
#Sta/Elev= 30
  4371.4  371.07  4582.2  363.46  4729.8  359.85  4835.2  355.99  4909.0  355.03
  4961.7  355.81  4972.2  355.55  4980.8  354.48  4981.0  353.98  4984.8  354.48
  5001.2  356.21  5119.7  358.19  5225.4  360.55  5339.6  364.97  5381.1  367.32
  5448.0  369.37  5456.1  370.90  5469.7  371.93  5485.4  371.81  5509.2  374.00
  5543.1  373.77  5556.4  374.41  5578.0  377.58  5599.7  378.44  5621.4  381.48
  5632.2  382.15  5639.2  383.45  5644.6  383.29  5651.1  384.86  5653.9  384.86
#Mann=7,-1,0
  4371.4    0.05       0  4980.8    0.05       0  4984.8    0.05       0
  5119.7    0.07       0  5339.6   0.035       0  5381.1   0.063       0
  5543.1   0.035       0
Bank Sta=4980.8,4984.8
Exp/Cntr=0.3,0.1

Type RM Length L Ch R = 1,3694,470,470,470
BEGIN DESCRIPTION:
Stream0585 8.0
END DESCRIPTION:
XS GIS Cut Line= 3
      2361075.02     13650175.00      2361375.00     13650225.00
      2361974.99     13649975.01
#Sta/Elev= 30
  4690.0  363.38  4717.9  361.66  4760.9  360.26  4778.7  359.02  4811.6  357.84
  4882.6  355.90  4905.4  355.82  4933.3  354.35  5013.8  352.14  5014.0  351.64
  5017.5  351.64  5017.8  352.14  5059.9  353.12  5080.2  353.77  5091.6  353.48
  5102.4  352.19  5109.5  353.37  5133.3  354.38  5167.8  353.74  5275.8  354.96
  5325.7  355.86  5383.7  357.51  5480.9  361.12  5528.7  362.57  5576.4  364.78
  5605.7  365.40  5620.8  366.30  5634.9  367.15  5641.4  368.47  5644.1  368.47
#Mann=10,-1,0
  4690.0    0.07       0  5013.8    0.05       0  5017.8    0.07       0
  5059.9     0.1       0  5167.8    0.05       0  5275.8    0.07       0
  5325.7   0.035       0  5383.7    0.07       0  5480.9   0.035       0
  5620.8   0.063       0
Bank Sta=5013.8,5017.8
Exp/Cntr=0.3,0.1

Type RM Length L Ch R = 1,3224,455,455,455
BEGIN DESCRIPTION:
Stream0585 7.0
END DESCRIPTION:
XS GIS Cut Line= 3
      2361175.02     13650525.01      2361425.00     13650675.00
      2362025.02     13650124.98
#Sta/Elev= 30
  4708.5  359.34  4731.8  358.68  4774.6  354.22  4928.1  351.73  4976.7  349.31
  5003.4  349.26  5007.1  348.28  5021.3  348.62  5026.1  347.29  5026.3  346.79
  5030.1  347.29  5035.5  349.22  5049.7  349.19  5056.4  351.30  5070.6  351.77
  5099.0  349.26  5167.9  350.81  5276.0  351.72  5332.7  355.06  5382.6  355.35
  5481.3  354.92  5544.3  358.11  5587.4  358.74  5594.8  360.43  5615.7  362.20
  5637.4  362.01  5679.2  361.41  5750.1  364.15  5769.3  366.26  5814.0  369.63
#Mann=8,-1,0
  4708.5    0.07       0  5026.1    0.05       0  5030.1    0.07       0
  5167.9   0.035       0  5382.6    0.07       0  5544.3   0.063       0
  5637.4   0.035       0  5769.3   0.063       0
Bank Sta=5026.1,5030.1
Exp/Cntr=0.3,0.1

Type RM Length L Ch R = 1,2769,456,456,456
BEGIN DESCRIPTION:
Stream0585 6.0
END DESCRIPTION:
XS GIS Cut Line= 3
      2360974.99     13651025.00      2361575.00     13651075.00
      2362124.97     13650875.01
#Sta/Elev= 30
  4397.9  358.25  4576.0  352.96  4688.9  350.37  4789.3  348.49  4839.4  348.56
  4899.6  346.11  4919.7  347.41  4929.8  345.73  4937.3  345.80  4942.3  346.67
  4967.9  344.91  4968.1  344.41  4971.6  344.41  4971.9  344.91  4990.0  344.99
  5010.0  346.11  5031.9  345.21  5076.5  345.10  5117.0  346.93  5193.5  348.02
  5246.1  349.96  5254.9  350.28  5352.0  353.05  5415.0  355.80  5457.8  358.94
  5489.5  361.22  5521.8  361.95  5532.0  362.06  5553.3  363.96  5585.2  364.57
#Mann=8,-1,0
  4397.9    0.07       0  4967.9    0.05       0  4971.9    0.07       0
  5246.1   0.035       0  5254.9   0.063       0  5352.0   0.035       0
  5457.8    0.07       0  5521.8   0.063       0
Bank Sta=4967.9,4971.9
Exp/Cntr=0.3,0.1

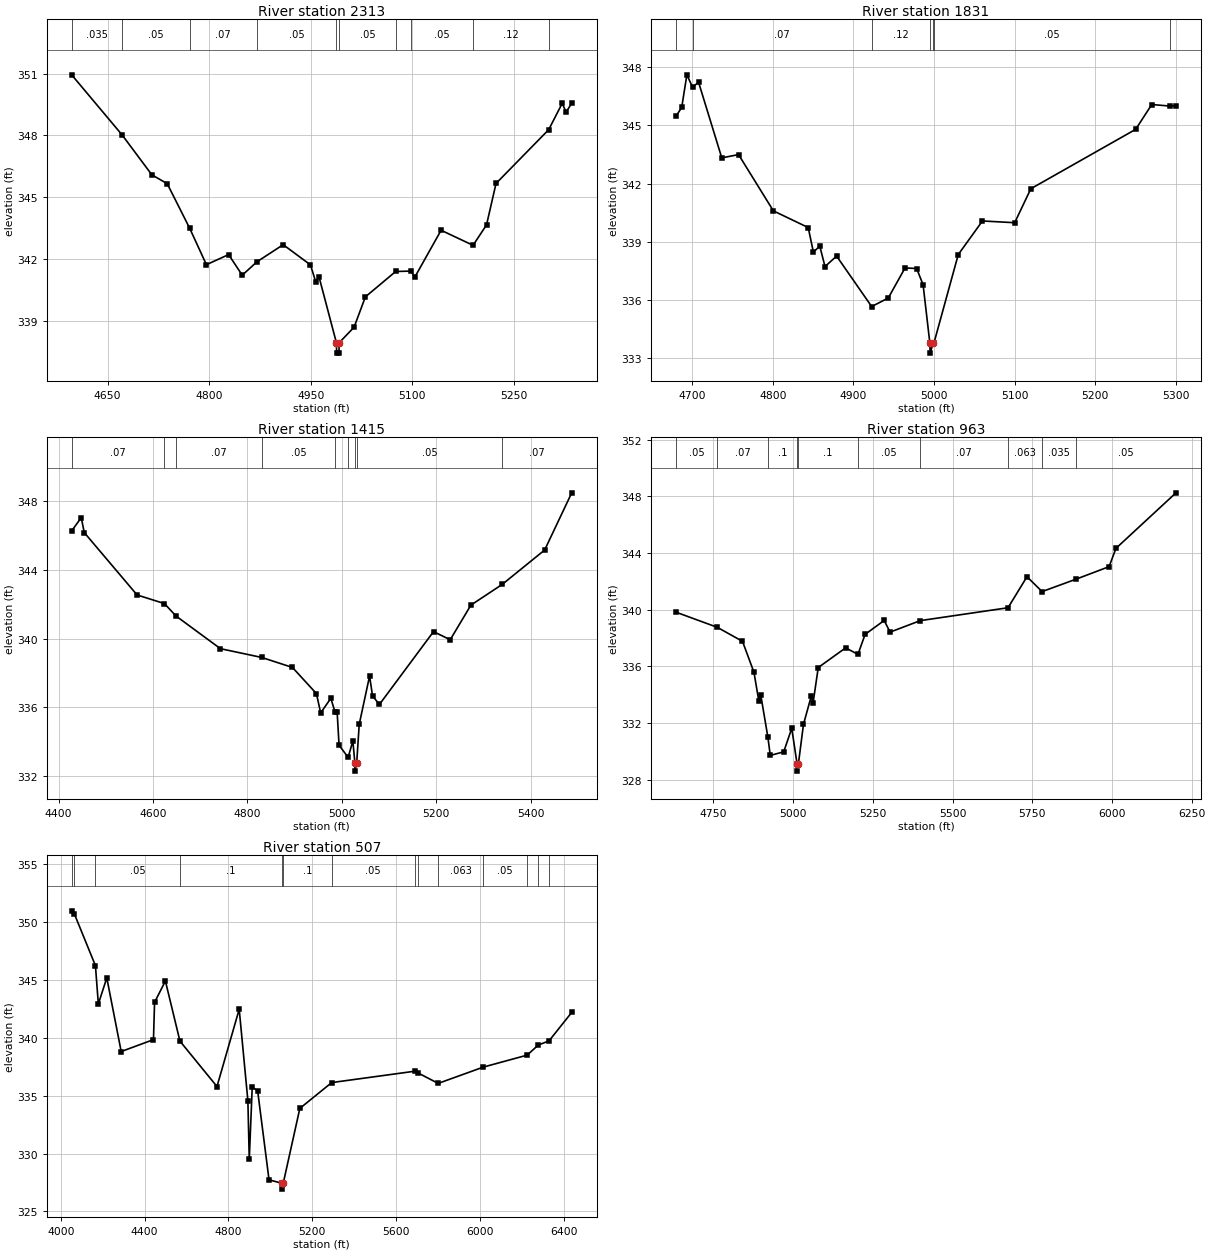
Type RM Length L Ch R = 1,2313,482,482,482
BEGIN DESCRIPTION:
Stream0585 5.0
END DESCRIPTION:
XS GIS Cut Line= 3
      2361225.01     13651525.00      2361625.00     13651475.00
      2361924.99     13651325.00
#Sta/Elev= 30
  4596.9  350.94  4671.5  348.02  4715.3  346.09  4738.0  345.66  4771.0  343.51
  4795.9  341.73  4828.7  342.22  4848.8  341.22  4870.5  341.87  4909.3  342.70
  4949.6  341.72  4957.2  340.91  4962.2  341.14  4987.9  337.94  4988.2  337.44
  4991.7  337.44  4991.9  337.94  5014.0  338.70  5030.7  340.17  5075.4  341.40
  5098.5  341.42  5103.4  341.11  5142.5  343.40  5189.7  342.67  5209.6  343.66
  5223.6  345.67  5301.4  348.28  5321.4  349.56  5327.0  349.13  5335.4  349.56
#Mann=10,-1,0
  4596.9   0.035       0  4671.5    0.05       0  4771.0    0.07       0
  4870.5    0.05       0  4987.9    0.05       0  4991.9    0.05       0
  5075.4    0.07       0  5098.5    0.05       0  5189.7    0.12       0
  5301.4    0.05       0
Bank Sta=4987.9,4991.9
Exp/Cntr=0.3,0.1

Type RM Length L Ch R = 1,1831,416,416,416
BEGIN DESCRIPTION:
Stream0585 4.0
END DESCRIPTION:
XS GIS Cut Line= 3
      2361324.97     13651674.97      2361525.00     13651925.00
      2361825.00     13651925.00
#Sta/Elev= 30
  4679.8  345.47  4687.0  345.93  4693.4  347.61  4700.5  346.97  4707.9  347.23
  4736.7  343.33  4757.5  343.50  4800.7  340.60  4843.9  339.74  4850.3  338.48
  4858.3  338.78  4864.7  337.73  4879.1  338.27  4922.6  335.67  4943.2  336.11
  4964.0  337.66  4978.4  337.63  4986.4  336.79  4994.8  333.77  4995.0  333.27
  4998.8  333.77  4999.7  333.77  5030.0  338.35  5060.0  340.08  5100.0  339.99
  5120.0  341.74  5250.0  344.80  5270.0  346.08  5292.6  346.00  5300.0  346.01
#Mann=7,-1,0
  4679.8    0.05       0  4700.5    0.07       0  4922.6    0.12       0
  4994.8    0.05       0  4998.8    0.12       0  4999.7    0.05       0
  5292.6    0.07       0
Bank Sta=4994.8,4998.8
Exp/Cntr=0.3,0.1

Type RM Length L Ch R = 1,1415,452,452,452
BEGIN DESCRIPTION:
Stream0585 3.0
END DESCRIPTION:
XS GIS Cut Line= 3
      2360924.99     13652175.00      2361475.00     13652275.00
      2361874.97     13651975.02
#Sta/Elev= 30
  4427.8  346.25  4448.1  347.02  4454.5  346.15  4566.3  342.53  4624.2  342.03
  4648.6  341.31  4742.9  339.41  4830.4  338.90  4895.4  338.32  4946.2  336.80
  4955.1  335.68  4976.7  336.53  4985.5  335.73  4990.0  335.73  4994.1  333.80
  5013.3  333.10  5023.3  334.05  5027.5  332.80  5027.8  332.30  5031.5  332.80
  5036.8  335.02  5058.7  337.82  5065.0  336.67  5079.5  336.17  5194.1  340.40
  5229.5  339.93  5273.3  341.94  5339.5  343.14  5429.5  345.14  5486.8  348.46
#Mann=9,-1,0
  4427.8    0.07       0  4624.2    0.05       0  4648.6    0.07       0
  4830.4    0.05       0  4985.5   0.035       0  5013.3    0.05       0
  5027.5   0.035       0  5031.5    0.05       0  5339.5    0.07       0
Bank Sta=5027.5,5031.5
Exp/Cntr=0.3,0.1

Type RM Length L Ch R = 1,963,456,456,456
BEGIN DESCRIPTION:
Stream0585 2.0
END DESCRIPTION:
XS GIS Cut Line= 3
      2361125.03     13652475.02      2361425.00     13652675.00
      2362550.38     13652237.62
#Sta/Elev= 30
  4632.7  339.82  4762.3  338.75  4841.5  337.76  4877.5  335.57  4892.6  333.56
  4898.6  333.99  4920.9  331.02  4928.6  329.71  4970.7  329.96  4995.9  331.62
  5012.7  329.10  5012.9  328.60  5016.7  329.10  5032.7  331.90  5057.2  333.90
  5062.6  333.38  5079.0  335.91  5164.9  337.30  5203.5  336.84  5225.9  338.25
  5285.7  339.23  5304.3  338.41  5398.7  339.22  5674.1  340.13  5733.5  342.32
  5780.9  341.27  5887.7  342.15  5991.0  343.03  6012.4  344.32  6200.6  348.24
#Mann=10,-1,0
  4632.7    0.05       0  4762.3    0.07       0  4920.9     0.1       0
  5012.7    0.05       0  5016.7     0.1       0  5203.5    0.05       0
  5398.7    0.07       0  5674.1   0.063       0  5780.9   0.035       0
  5887.7    0.05       0
Bank Sta=5012.7,5016.7
Exp/Cntr=0.3,0.1

Type RM Length L Ch R = 1,507,0,0,0
BEGIN DESCRIPTION:
Stream0585 1.0
END DESCRIPTION:
XS GIS Cut Line= 3
      2360363.19     13652827.78      2361275.00     13653075.00
      2362647.88     13652633.35
#Sta/Elev= 30
  4051.7  350.96  4064.0  350.72  4165.1  346.23  4179.0  342.92  4219.4  345.17
  4288.1  338.81  4442.2  339.84  4447.4  343.06  4499.1  344.90  4568.5  339.71
  4745.3  335.79  4851.4  342.46  4892.8  334.57  4899.4  329.50  4913.5  335.72
  4939.3  335.44  4993.8  327.73  5057.5  327.43  5057.7  326.93  5061.5  327.43
  5140.8  333.90  5292.9  336.13  5689.1  337.11  5704.2  336.97  5801.2  336.06
  6017.2  337.47  6225.9  338.50  6278.9  339.37  6330.3  339.73  6438.6  342.19
#Mann=14,-1,0
  4051.7   0.035       0  4064.0    0.07       0  4165.1    0.05       0
  4568.5     0.1       0  5057.5    0.05       0  5061.5     0.1       0
  5292.9    0.05       0  5689.1     0.1       0  5704.2    0.05       0
  5801.2   0.063       0  6017.2    0.05       0  6225.9    0.07       0
  6278.9    0.05       0  6330.3    0.07       0
Bank Sta=5057.5,5061.5
Exp/Cntr=0.3,0.1

Chan Stop Cuts=-1