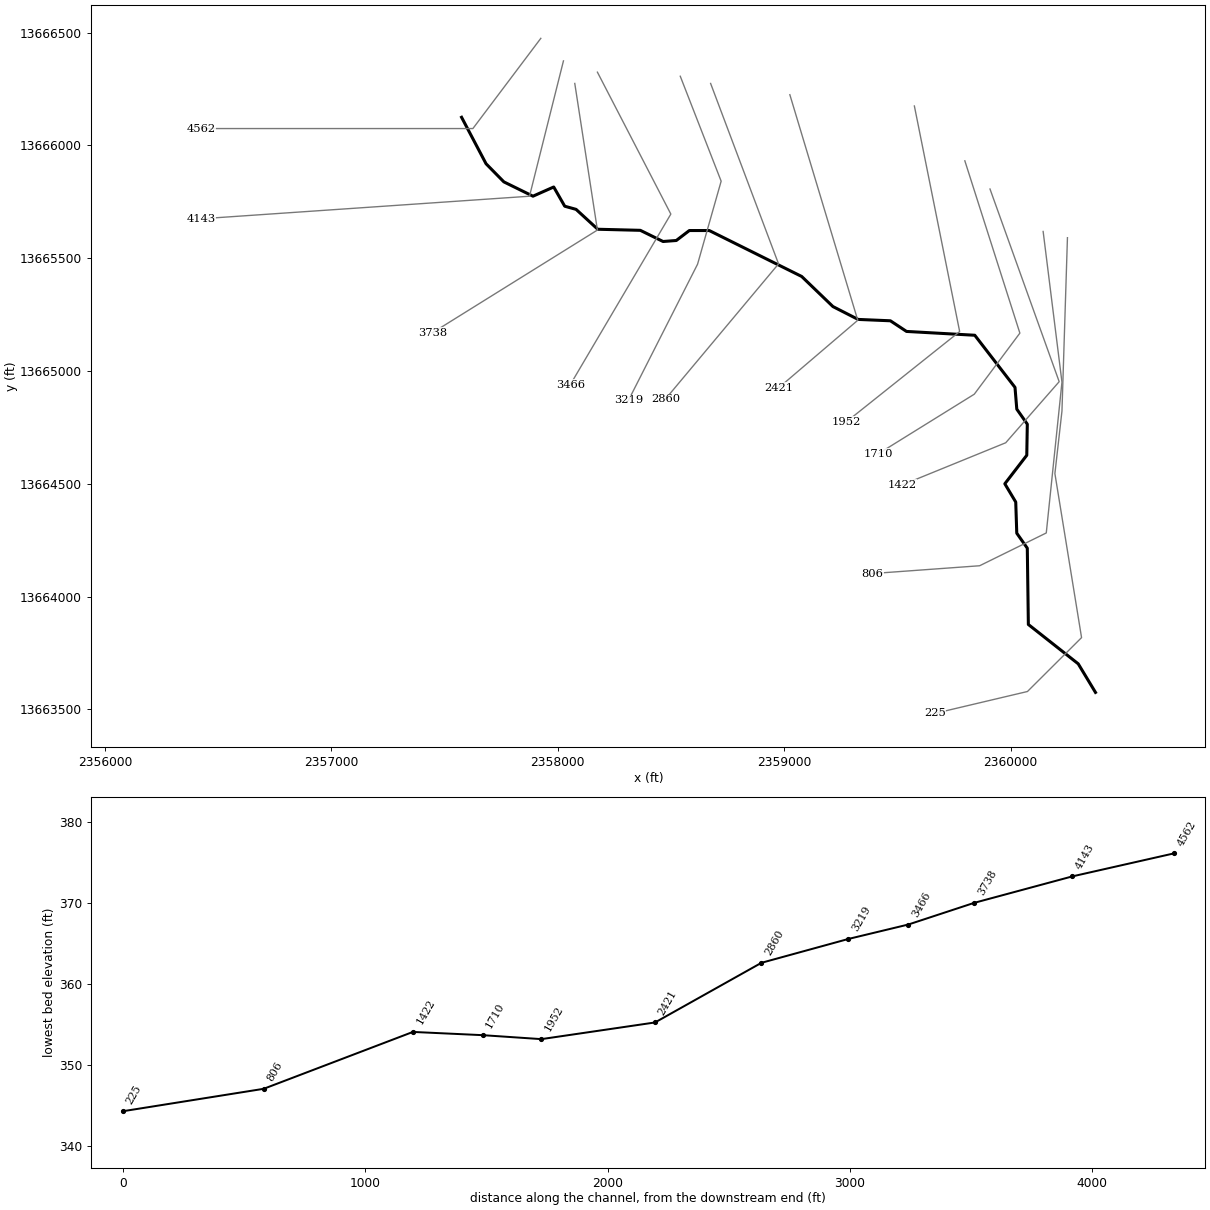
--- Stream0590.prj (project) ---

Proj Title=Stream0590 Base Level Engineering
Current Plan=p01
Default Exp/Contr=0.3,0.1
English Units
Geom File=g01
Flow File=f01
Plan File=p01
BEGIN DESCRIPTION:
Stream0590
END DESCRIPTION:

--- Stream0590.p01 (plan) ---

Plan Title=Multiple Run
Short Identifier=Multiple
Geom File=g01
Flow File=f01
Subcritical Flow
K Sum by GR= 0
Std Step Tol= 0.01
Critical Tol= 0.01
Num of Std Step Trials= 20
Max Error Tol= 0.3
Flow Tol Ratio= 0.001
Split Flow NTrial= 30
Split Flow Tol= 0.02
Split Flow Ratio= 0.02
Log Output Level= 0
Friction Slope Method= 1
Unsteady Friction Slope Method= 2
Unsteady Bridges Friction Slope Method= 1
Parabolic Critical Depth
Global Vel Dist=  1 , 1 , 1
Global Log Level= 0
CheckData=True
Encroach Param= -1, 0, 0, 0
BEGIN DESCRIPTION:
Multiple Run
END DESCRIPTION:

--- Stream0590.f01 (steady flow) ---

Flow Title=Multiple
Number of Profiles=7
Profile Names=10-year,25-year,50-year,1pct_min,100-year,1pct_plu,500-year
River Rch & RM= Stream0590,Reach-1,4562
     710    1158    1566    1024    2044    4078    3454
Boundary for River Rch & Prof#=Stream0590,Reach-1,1
Up Type=0
Dn Type=3
Dn Slope=0.005
Boundary for River Rch & Prof#=Stream0590,Reach-1,2
Up Type=0
Dn Type=3
Dn Slope=0.005
Boundary for River Rch & Prof#=Stream0590,Reach-1,3
Up Type=0
Dn Type=3
Dn Slope=0.005
Boundary for River Rch & Prof#=Stream0590,Reach-1,4
Up Type=0
Dn Type=3
Dn Slope=0.005
Boundary for River Rch & Prof#=Stream0590,Reach-1,5
Up Type=0
Dn Type=3
Dn Slope=0.005
Boundary for River Rch & Prof#=Stream0590,Reach-1,6
Up Type=0
Dn Type=3
Dn Slope=0.005
Boundary for River Rch & Prof#=Stream0590,Reach-1,7
Up Type=0
Dn Type=3
Dn Slope=0.005

--- Stream0590.g01 (geometry) ---

Geom Title=Existing Conditions

River Reach=Stream0590,Reach-1
Reach XY= 30
      2357575.00     13666125.00      2357683.13     13665918.93
      2357761.76     13665838.61      2357890.42     13665775.14
      2357982.00     13665815.92      2358030.62     13665730.68
      2358080.74     13665716.70      2358176.47     13665628.55
      2358364.50     13665623.78      2358464.95     13665574.23
      2358523.40     13665578.71      2358580.97     13665622.83
      2358669.03     13665622.86      2359077.30     13665419.17
      2359215.32     13665285.76      2359326.56     13665228.76
      2359469.06     13665222.73      2359540.22     13665175.52
      2359841.80     13665158.58      2360019.46     13664927.42
      2360027.36     13664830.98      2360073.80     13664764.49
      2360071.46     13664626.47      2359974.51     13664500.04
      2360022.70     13664419.07      2360027.27     13664280.94
      2360073.78     13664214.50      2360078.45     13663876.25
      2360298.72     13663701.83      2360375.00     13663575.00

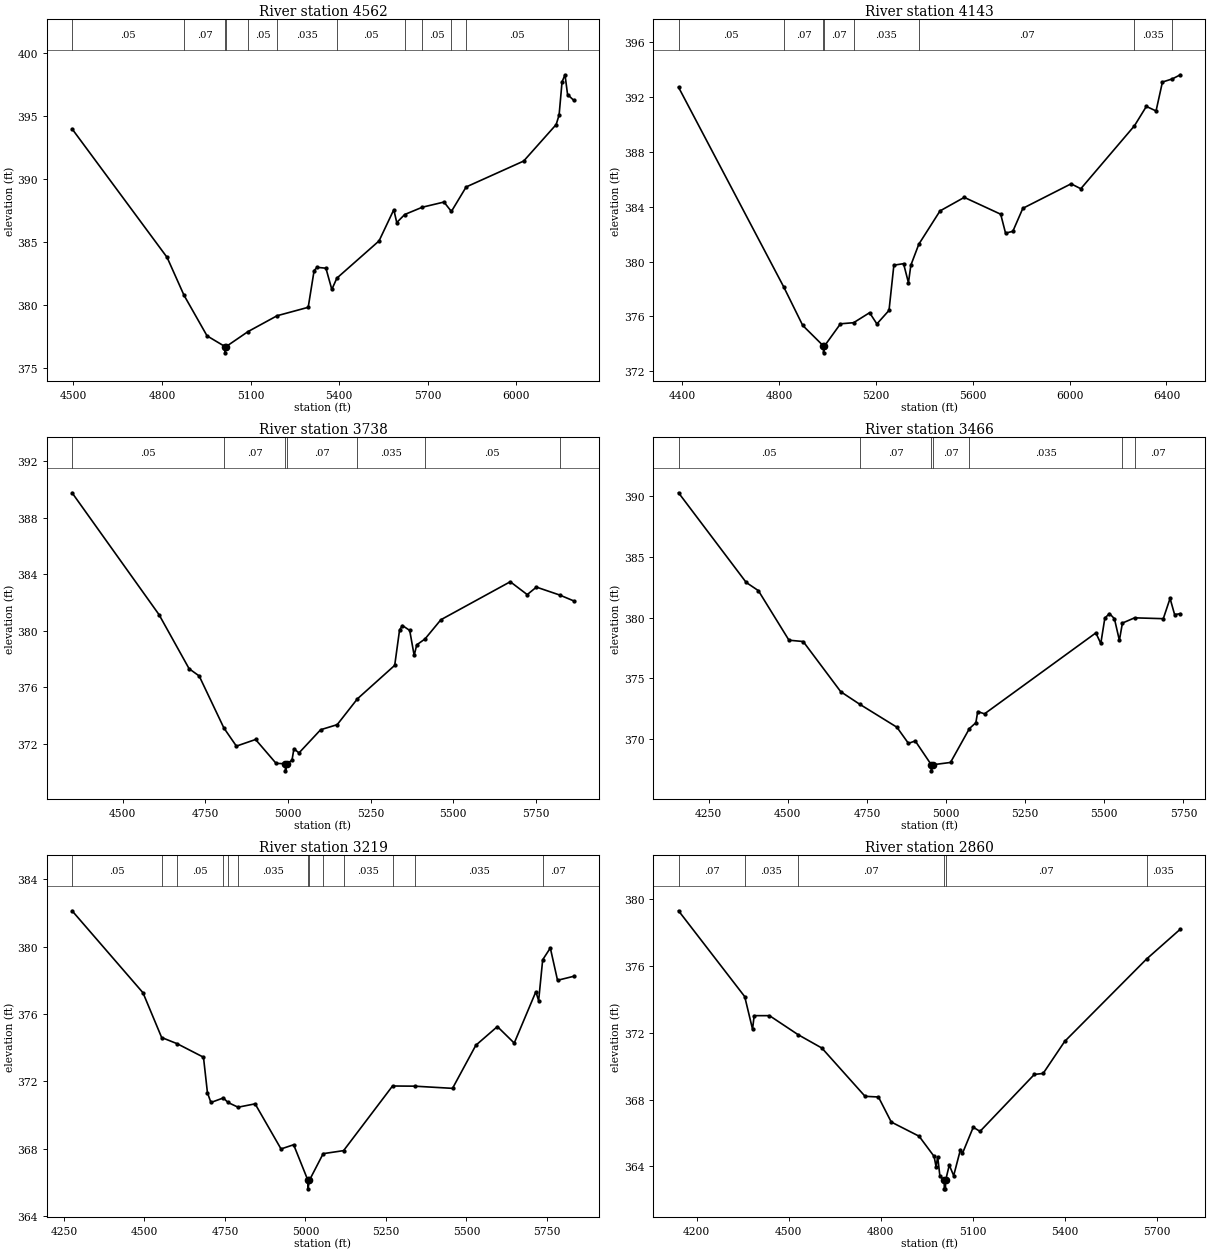
Type RM Length L Ch R = 1,4562,419,419,419
BEGIN DESCRIPTION:
Stream0590 7.0
END DESCRIPTION:
XS GIS Cut Line= 3
      2357925.00     13666475.00      2357625.00     13666075.00
      2356425.00     13666075.00
#Sta/Elev= 30
  4495.4  393.99  4817.3  383.77  4874.6  380.76  4952.7  377.53  5013.4  376.68
  5013.7  376.18  5017.4  376.68  5091.6  377.87  5190.0  379.13  5295.4  379.80
  5315.4  382.72  5325.4  382.98  5355.4  382.91  5375.4  381.22  5392.5  382.12
  5535.4  385.08  5585.4  387.56  5595.4  386.54  5622.4  387.18  5682.1  387.76
  5755.4  388.17  5780.5  387.42  5830.5  389.37  6025.4  391.43  6135.4  394.33
  6145.4  395.09  6155.4  397.73  6165.4  398.29  6174.1  396.72  6195.4  396.25
#Mann=12,-1,0
  4495.4    0.05       0  4874.6    0.07       0  5013.4    0.05       0
  5017.4    0.07       0  5091.6    0.05       0  5190.0   0.035       0
  5392.5    0.05       0  5622.4    0.07       0  5682.1    0.05       0
  5780.5   0.035       0  5830.5    0.05       0  6174.1   0.035       0
Bank Sta=5013.4,5017.4
Exp/Cntr=0.3,0.1

Type RM Length L Ch R = 1,4143,405,405,405
BEGIN DESCRIPTION:
Stream0590 6.0
END DESCRIPTION:
XS GIS Cut Line= 3
      2358025.01     13666375.02      2357875.00     13665775.00
      2356425.04     13665675.00
#Sta/Elev= 30
  4385.4  392.73  4819.8  378.15  4898.2  375.34  4983.8  373.84  4984.0  373.34
  4988.0  373.84  5054.0  375.46  5108.3  375.54  5174.3  376.27  5204.4  375.45
  5254.5  376.44  5274.5  379.74  5314.6  379.85  5334.7  378.46  5344.7  379.74
  5377.5  381.27  5465.0  383.70  5565.2  384.69  5715.6  383.46  5735.6  382.08
  5765.7  382.21  5807.0  383.89  6006.3  385.68  6046.4  385.32  6268.0  389.92
  6317.0  391.33  6357.1  391.00  6383.4  393.11  6424.4  393.34  6457.3  393.64
#Mann=8,-1,0
  4385.4    0.05       0  4819.8    0.07       0  4983.8    0.05       0
  4988.0    0.07       0  5108.3   0.035       0  5377.5    0.07       0
  6268.0   0.035       0  6424.4    0.07       0
Bank Sta=4983.8,4988
Exp/Cntr=0.3,0.1

Type RM Length L Ch R = 1,3738,272,272,272
BEGIN DESCRIPTION:
Stream0590 5.0
END DESCRIPTION:
XS GIS Cut Line= 3
      2358075.00     13666275.03      2358175.00     13665625.00
      2357445.32     13665169.04
#Sta/Elev= 30
  4347.0  389.76  4610.1  381.13  4701.1  377.30  4731.5  376.79  4806.2  373.11
  4844.1  371.82  4902.2  372.29  4964.2  370.60  4992.4  370.57  4992.7  370.07
  4996.7  370.57  5012.3  370.82  5018.2  371.63  5033.6  371.34  5099.0  372.98
  5149.1  373.34  5210.3  375.17  5323.1  377.54  5337.8  380.05  5346.6  380.36
  5368.5  380.01  5382.0  378.24  5389.7  378.99  5414.8  379.41  5462.8  380.77
  5672.7  383.46  5724.0  382.55  5751.8  383.08  5822.2  382.52  5865.1  382.10
#Mann=7,-1,0
  4347.0    0.05       0  4806.2    0.07       0  4992.4    0.05       0
  4996.7    0.07       0  5210.3   0.035       0  5414.8    0.05       0
  5822.2    0.07       0
Bank Sta=4992.4,4996.7
Exp/Cntr=0.3,0.1

Type RM Length L Ch R = 1,3466,247,247,247
BEGIN DESCRIPTION:
Stream0590 4.0
END DESCRIPTION:
XS GIS Cut Line= 3
      2358174.99     13666325.01      2358499.31     13665695.83
      2358055.18     13664939.43
#Sta/Elev= 30
  4155.0  390.27  4368.8  382.89  4407.1  382.22  4503.8  378.14  4548.8  378.03
  4667.4  373.90  4727.3  372.87  4844.7  370.98  4881.2  369.65  4902.7  369.85
  4953.4  367.89  4953.7  367.39  4957.7  367.89  5014.1  368.08  5073.8  370.87
  5094.2  371.35  5100.0  372.27  5121.5  372.08  5473.2  378.74  5488.8  377.87
  5501.6  379.96  5516.1  380.33  5531.8  379.91  5547.5  378.13  5557.1  379.55
  5595.5  379.98  5686.2  379.91  5707.6  381.58  5721.9  380.25  5740.0  380.32
#Mann=7,-1,0
  4155.0    0.05       0  4727.3    0.07       0  4953.4    0.05       0
  4957.7    0.07       0  5073.8   0.035       0  5557.1    0.05       0
  5595.5    0.07       0
Bank Sta=4953.4,4957.7
Exp/Cntr=0.3,0.1

Type RM Length L Ch R = 1,3219,359,359,359
BEGIN DESCRIPTION:
XS7174
END DESCRIPTION:
XS GIS Cut Line= 4
      2358540.97     13666306.95      2358721.53     13665841.67
      2358617.36     13665473.61      2358311.96     13664869.74
#Sta/Elev= 30
  4275.3  382.13  4495.5  377.26  4553.5  374.60  4602.0  374.23  4683.4  373.43
  4695.7  371.32  4706.5  370.74  4745.1  371.01  4759.6  370.74  4790.8  370.46
  4843.7  370.66  4924.2  367.98  4963.4  368.23  5007.8  366.11  5008.1  365.61
  5012.1  366.11  5055.1  367.70  5118.5  367.88  5270.5  371.72  5338.9  371.71
  5456.8  371.58  5529.2  374.14  5596.1  375.25  5648.4  374.27  5715.6  377.32
  5724.2  376.79  5736.8  379.22  5760.5  379.92  5782.9  378.00  5833.6  378.24
#Mann=13,-1,0
  4275.3    0.05       0  4553.5    0.07       0  4602.0    0.05       0
  4745.1   0.035       0  4759.6    0.07       0  4790.8   0.035       0
  5007.8   0.035       0  5012.1   0.035       0  5055.1    0.07       0
  5118.5   0.035       0  5270.5    0.07       0  5338.9   0.035       0
  5736.8    0.07       0
Bank Sta=5007.8,5012.1
Exp/Cntr=0.3,0.1

Type RM Length L Ch R = 1,2860,439,439,439
BEGIN DESCRIPTION:
Stream0590 3.0
END DESCRIPTION:
XS GIS Cut Line= 3
      2358675.01     13666274.98      2358975.00     13665475.00
      2358475.00     13664875.01
#Sta/Elev= 30
  4140.8  379.31  4356.5  374.17  4382.0  372.22  4387.3  373.03  4437.2  373.03
  4530.6  371.89  4608.0  371.09  4748.7  368.20  4792.3  368.16  4834.1  366.66
  4924.9  365.81  4973.8  364.60  4980.1  363.98  4985.4  364.58  4992.5  363.44
  5006.7  363.16  5007.0  362.66  5010.8  362.66  5011.1  363.16  5023.2  364.08
  5037.5  363.45  5059.6  365.01  5066.1  364.78  5101.3  366.35  5123.4  366.10
  5300.4  369.51  5329.1  369.57  5399.4  371.49  5666.1  376.42  5776.2  378.21
#Mann=6,-1,0
  4140.8    0.07       0  4356.5   0.035       0  4530.6    0.07       0
  5006.7    0.05       0  5011.1    0.07       0  5666.1   0.035       0
Bank Sta=5006.7,5011.1
Exp/Cntr=0.3,0.1

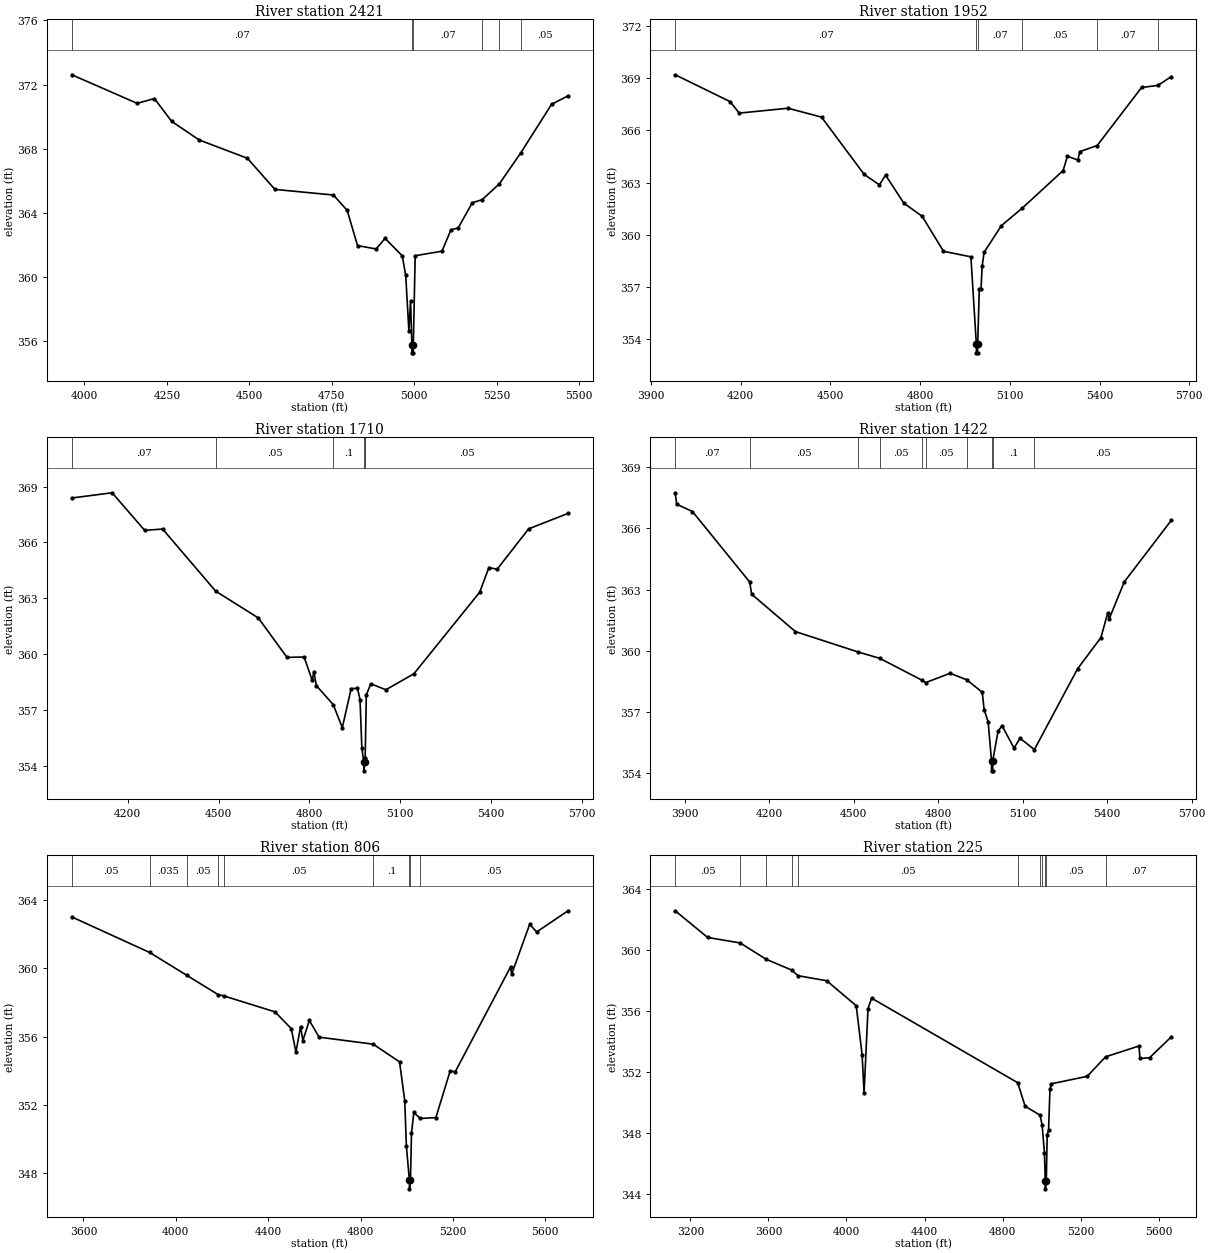
Type RM Length L Ch R = 1,2421,469,469,469
BEGIN DESCRIPTION:
Stream0590 2.0
END DESCRIPTION:
XS GIS Cut Line= 3
      2359024.99     13666225.04      2359325.00     13665225.00
      2358974.96     13664924.97
#Sta/Elev= 30
  3961.5  372.61  4159.9  370.83  4212.1  371.13  4264.3  369.71  4347.8  368.55
  4494.0  367.41  4577.5  365.47  4755.0  365.12  4796.8  364.16  4828.1  361.97
  4884.6  361.76  4911.6  362.42  4963.8  361.33  4974.3  360.11  4983.8  356.68
  4989.0  358.53  4992.9  355.79  4993.2  355.29  4997.0  355.29  4997.3  355.79
  5003.0  361.34  5084.1  361.62  5111.5  362.95  5133.4  363.07  5176.2  364.64
  5206.1  364.83  5258.4  365.82  5323.0  367.74  5416.6  370.77  5466.6  371.30
#Mann=6,-1,0
  3961.5    0.07       0  4992.9    0.05       0  4997.3    0.07       0
  5206.1    0.05       0  5258.4    0.07       0  5323.0    0.05       0
Bank Sta=4992.9,4997.3
Exp/Cntr=0.3,0.1

Type RM Length L Ch R = 1,1952,242,242,242
BEGIN DESCRIPTION:
Stream0590 1.0
END DESCRIPTION:
XS GIS Cut Line= 3
      2359574.99     13666175.03      2359775.00     13665175.00
      2359275.04     13664775.03
#Sta/Elev= 30
  3980.6  369.19  4164.2  367.65  4194.8  366.99  4358.0  367.27  4470.1  366.76
  4612.9  363.47  4663.9  362.87  4684.3  363.43  4745.5  361.82  4806.7  361.07
  4878.1  359.06  4969.8  358.74  4988.0  353.73  4988.3  353.23  4992.2  353.23
  4992.5  353.73  4997.9  356.90  5003.6  356.90  5007.6  358.23  5014.0  359.00
  5071.7  360.53  5140.5  361.52  5278.2  363.69  5292.6  364.51  5327.8  364.30
  5334.2  364.78  5392.3  365.13  5540.7  368.46  5595.4  368.58  5640.7  369.09
#Mann=6,-1,0
  3980.6    0.07       0  4988.0    0.05       0  4992.5    0.07       0
  5140.5    0.05       0  5392.3    0.07       0  5595.4    0.05       0
Bank Sta=4988,4992.5
Exp/Cntr=0.3,0.1

Type RM Length L Ch R = 1,1710,288,288,288
BEGIN DESCRIPTION:
XS7176
END DESCRIPTION:
XS GIS Cut Line= 4
      2359797.92     13665931.94      2360040.97     13665168.06
      2359839.58     13664897.22      2359415.98     13664633.34
#Sta/Elev= 30
  4015.4  368.39  4148.6  368.67  4256.0  366.65  4315.2  366.72  4490.4  363.38
  4631.3  361.94  4725.8  359.82  4782.2  359.84  4809.2  358.58  4814.4  359.04
  4822.9  358.30  4878.5  357.28  4908.4  356.04  4937.6  358.14  4958.4  358.16
  4966.8  357.55  4973.0  354.93  4979.2  354.22  4979.5  353.72  4983.7  354.22
  4983.9  354.40  4987.7  357.80  5002.3  358.40  5052.3  358.08  5144.8  358.94
  5361.7  363.32  5392.4  364.65  5419.5  364.56  5523.4  366.73  5653.6  367.56
#Mann=6,-1,0
  4015.4    0.07       0  4490.4    0.05       0  4878.5     0.1       0
  4979.2    0.05       0  4983.7     0.1       0  4983.9    0.05       0
Bank Sta=4979.2,4983.7
Exp/Cntr=0.3,0.1

Type RM Length L Ch R = 1,1422,616,616,616
BEGIN DESCRIPTION:
XS7175
END DESCRIPTION:
XS GIS Cut Line= 4
      2359909.02     13665806.98      2360214.58     13664952.78
      2359978.47     13664681.94      2359520.15     13664494.45
#Sta/Elev= 30
  3866.6  367.74  3871.8  367.18  3928.0  366.82  4131.0  363.37  4138.1  362.77
  4293.5  360.94  4516.5  359.94  4592.9  359.63  4742.5  358.56  4755.6  358.44
  4842.7  358.90  4901.4  358.58  4956.6  357.97  4963.3  357.12  4977.6  356.51
  4989.5  354.62  4989.8  354.12  4993.7  354.12  4994.0  354.62  5012.7  356.06
  5026.9  356.33  5069.6  355.23  5090.5  355.72  5141.7  355.16  5295.1  359.12
  5378.0  360.65  5402.0  361.85  5407.4  361.57  5461.0  363.38  5628.3  366.40
#Mann=10,-1,0
  3866.6    0.07       0  4131.0    0.05       0  4516.5   0.035       0
  4592.9    0.05       0  4742.5   0.035       0  4755.6    0.05       0
  4901.4     0.1       0  4989.5    0.05       0  4994.0     0.1       0
  5141.7    0.05       0
Bank Sta=4989.5,4994
Exp/Cntr=0.3,0.1

Type RM Length L Ch R = 1,806,581,581,581
BEGIN DESCRIPTION:
E21177
END DESCRIPTION:
XS GIS Cut Line= 5
      2360143.75     13665618.78      2360226.86     13664950.43
      2360157.60     13664282.07      2359863.25     13664136.63
      2359389.37     13664102.04
#Sta/Elev= 30
  3549.5  363.01  3886.5  360.93  4047.5  359.59  4183.3  358.46  4209.3  358.38
  4429.5  357.45  4499.9  356.47  4520.0  355.09  4540.1  356.59  4550.2  355.77
  4578.0  356.95  4620.5  355.97  4854.9  355.56  4968.8  354.52  4991.3  352.25
  4998.2  349.62  5011.4  347.59  5011.8  347.09  5016.0  347.59  5020.5  350.34
  5030.6  351.56  5058.1  351.21  5125.9  351.26  5187.7  353.98  5210.1  353.95
  5449.4  360.08  5454.4  359.66  5532.3  362.58  5562.4  362.13  5698.4  363.37
#Mann=9,-1,0
  3549.5    0.05       0  3886.5   0.035       0  4047.5    0.05       0
  4183.3   0.035       0  4209.3    0.05       0  4854.9     0.1       0
  5011.4    0.05       0  5016.0     0.1       0  5058.1    0.05       0
Bank Sta=5011.4,5016
Exp/Cntr=0.3,0.1

Type RM Length L Ch R = 1,225,0,0,0
BEGIN DESCRIPTION:
E21176
END DESCRIPTION:
XS GIS Cut Line= 6
      2360251.10     13665591.10      2360226.86     13664822.30
      2360195.69     13664545.26      2360313.44     13663818.04
      2360074.49     13663579.09      2359665.82     13663482.12
#Sta/Elev= 30
  3122.5  362.56  3288.7  360.81  3455.4  360.45  3588.3  359.38  3719.7  358.67
  3752.1  358.30  3899.0  357.97  4050.0  356.33  4080.2  353.12  4090.2  350.60
  4110.4  356.13  4128.7  356.83  4877.6  351.28  4915.3  349.74  4991.9  349.15
  5002.4  348.52  5014.3  346.69  5018.8  344.82  5019.2  344.32  5023.8  344.82
  5028.4  347.88  5035.5  348.17  5042.6  350.84  5049.6  351.21  5233.5  351.70
  5327.6  352.98  5498.7  353.69  5503.8  352.87  5552.9  352.92  5665.1  354.30
#Mann=11,-1,0
  3122.5    0.05       0  3455.4   0.035       0  3588.3    0.05       0
  3719.7   0.035       0  3752.1    0.05       0  4877.6    0.07       0
  4991.9     0.1       0  5002.4    0.05       0  5018.8    0.05       0
  5023.8    0.05       0  5327.6    0.07       0
Bank Sta=5018.8,5023.8
Exp/Cntr=0.3,0.1

Chan Stop Cuts=-1