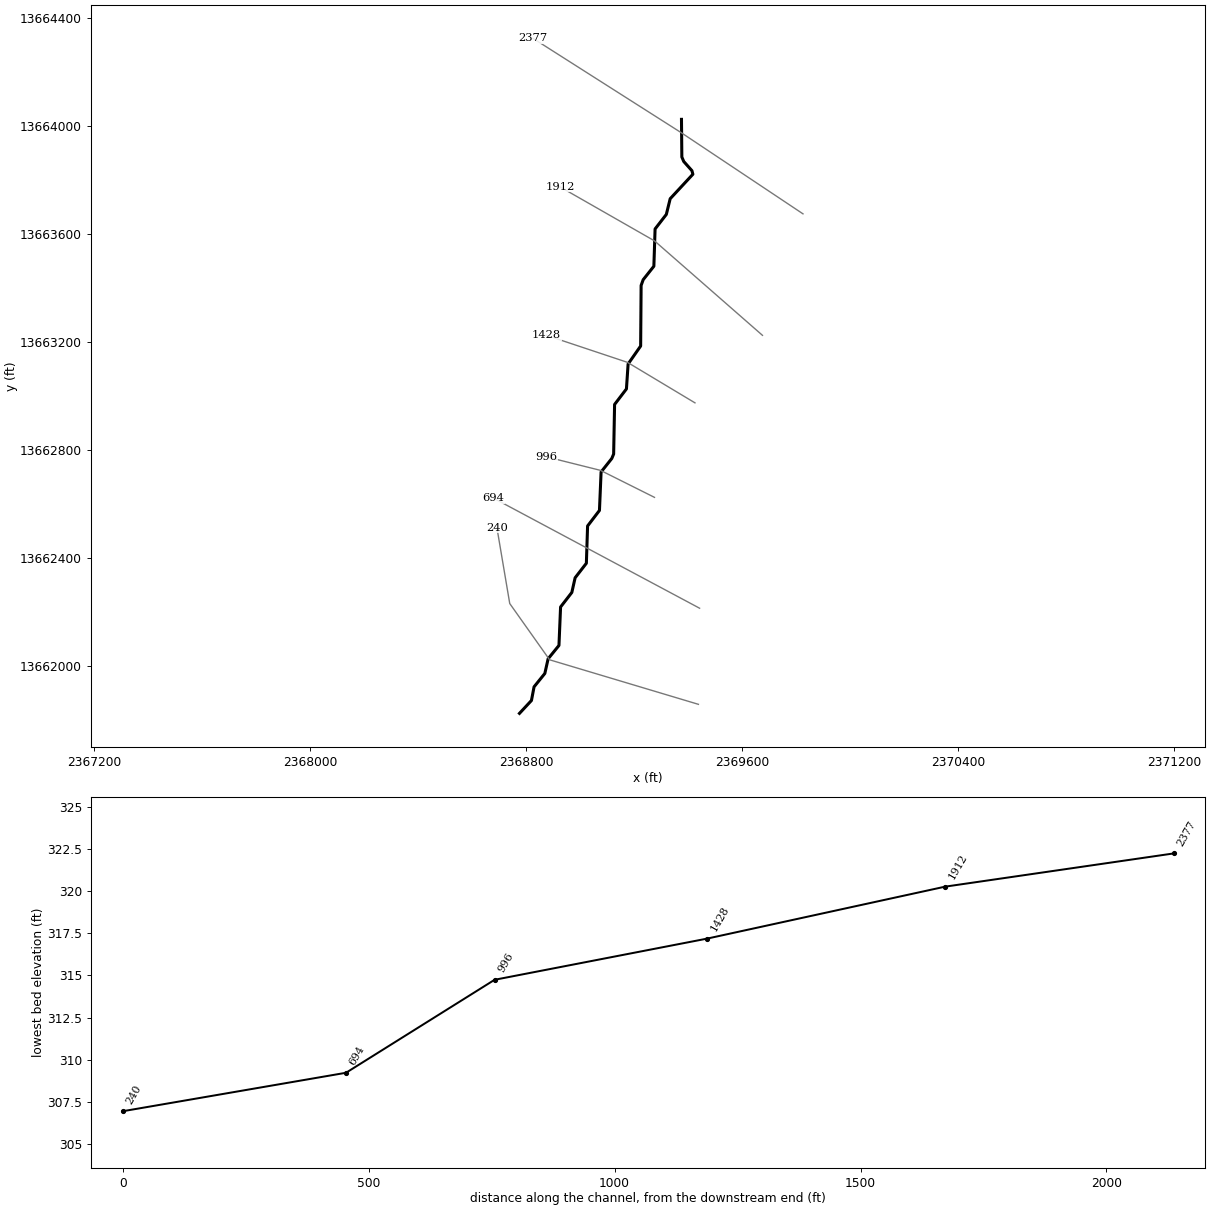
--- Stream0593.prj (project) ---

Proj Title=Stream0593 Base Level Engineering
Current Plan=p01
Default Exp/Contr=0.3,0.1
English Units
Geom File=g01
Flow File=f01
Plan File=p01
BEGIN DESCRIPTION:
Stream0593
END DESCRIPTION:

--- Stream0593.p01 (plan) ---

Plan Title=Multiple Run
Short Identifier=Multiple
Geom File=g01
Flow File=f01
Subcritical Flow
K Sum by GR= 0
Std Step Tol= 0.01
Critical Tol= 0.01
Num of Std Step Trials= 20
Max Error Tol= 0.3
Flow Tol Ratio= 0.001
Split Flow NTrial= 30
Split Flow Tol= 0.02
Split Flow Ratio= 0.02
Log Output Level= 0
Friction Slope Method= 1
Unsteady Friction Slope Method= 2
Unsteady Bridges Friction Slope Method= 1
Parabolic Critical Depth
Global Vel Dist=  1 , 1 , 1
Global Log Level= 0
CheckData=True
Encroach Param= -1, 0, 0, 0
BEGIN DESCRIPTION:
Multiple Run
END DESCRIPTION:

--- Stream0593.f01 (steady flow) ---

Flow Title=Multiple
Number of Profiles=7
Profile Names=10-year,25-year,50-year,1pct_min,100-year,1pct_plu,500-year
River Rch & RM= Stream0593,Reach-1,2377
     426     674     893     574    1145    2285    1866
Boundary for River Rch & Prof#=Stream0593,Reach-1,1
Up Type=0
Dn Type=3
Dn Slope=0.005
Boundary for River Rch & Prof#=Stream0593,Reach-1,2
Up Type=0
Dn Type=3
Dn Slope=0.005
Boundary for River Rch & Prof#=Stream0593,Reach-1,3
Up Type=0
Dn Type=3
Dn Slope=0.005
Boundary for River Rch & Prof#=Stream0593,Reach-1,4
Up Type=0
Dn Type=3
Dn Slope=0.005
Boundary for River Rch & Prof#=Stream0593,Reach-1,5
Up Type=0
Dn Type=3
Dn Slope=0.005
Boundary for River Rch & Prof#=Stream0593,Reach-1,6
Up Type=0
Dn Type=3
Dn Slope=0.005
Boundary for River Rch & Prof#=Stream0593,Reach-1,7
Up Type=0
Dn Type=3
Dn Slope=0.005

--- Stream0593.g01 (geometry) ---

Geom Title=Existing Conditions

River Reach=Stream0593,Reach-1
Reach XY= 30
      2369375.00     13664025.00      2369376.35     13663885.41
      2369383.47     13663868.80      2369413.68     13663834.85
      2369417.20     13663821.59      2369333.18     13663731.06
      2369318.86     13663672.83      2369277.25     13663619.07
      2369272.73     13663480.94      2369233.14     13663431.06
      2369225.52     13663409.78      2369223.78     13663185.50
      2369177.36     13663119.02      2369171.14     13663026.60
      2369127.26     13662969.06      2369123.78     13662785.51
      2369116.86     13662768.94      2369077.27     13662719.06
      2369071.21     13662576.57      2369027.27     13662519.06
      2369022.75     13662380.93      2368981.12     13662327.18
      2368968.88     13662272.82      2368927.25     13662219.07
      2368921.24     13662076.56      2368881.12     13662027.18
      2368868.93     13661972.80      2368829.04     13661923.33
      2368819.33     13661872.64      2368775.00     13661825.00

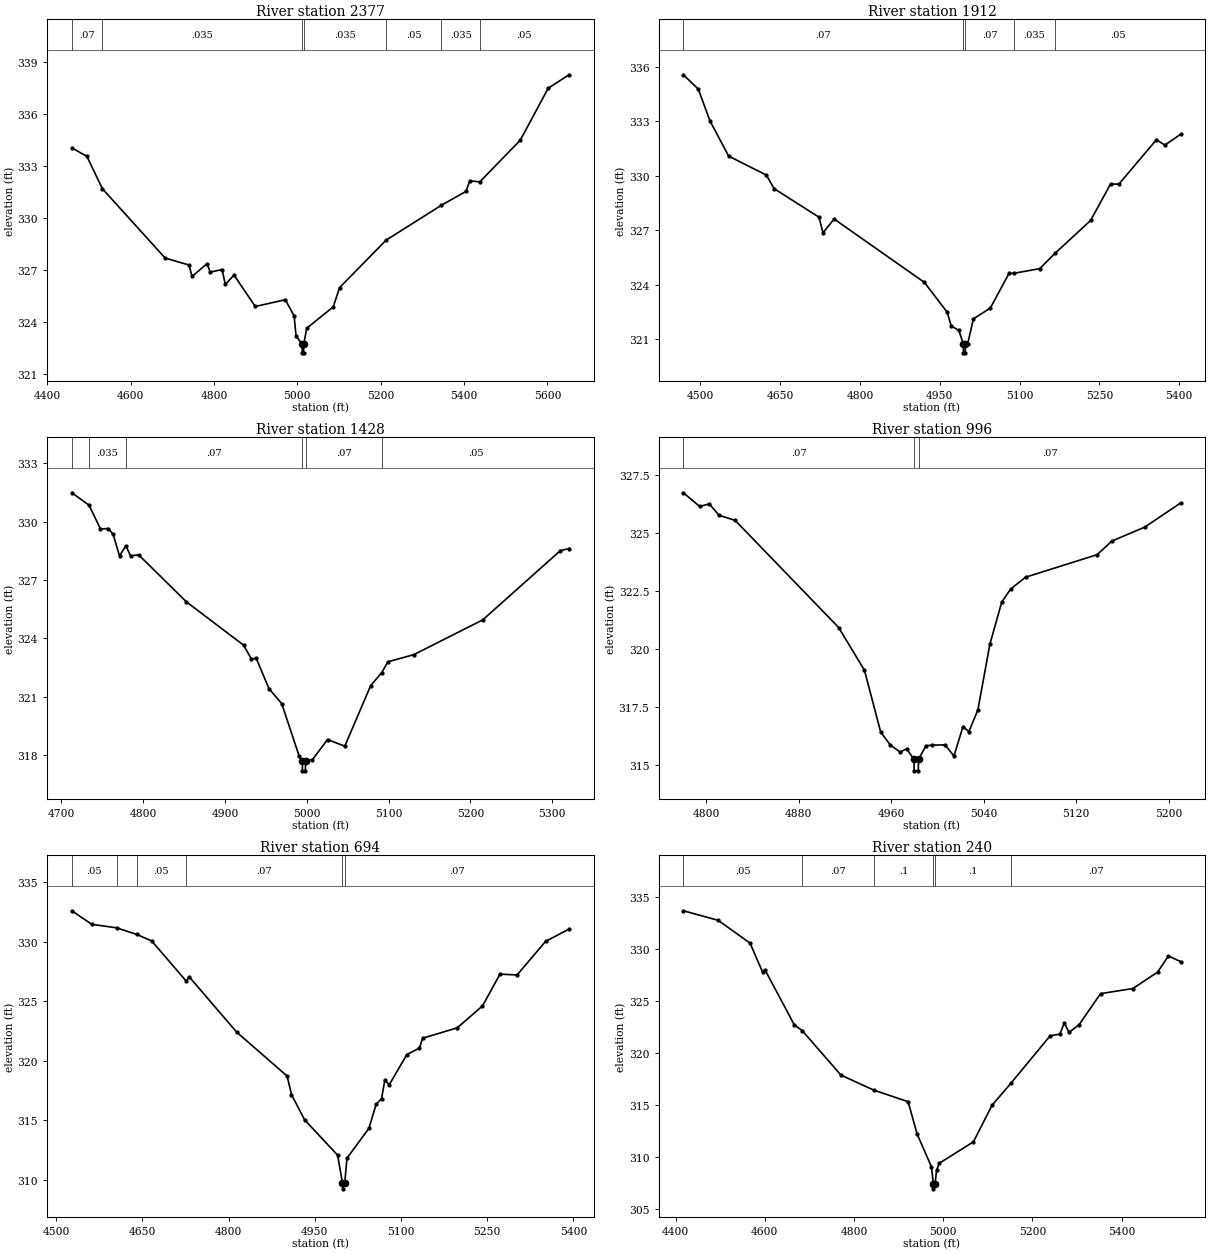
Type RM Length L Ch R = 1,2377,465,465,465
BEGIN DESCRIPTION:
Stream0593 5.0
END DESCRIPTION:
XS GIS Cut Line= 3
      2369825.03     13663674.98      2369375.00     13663975.00
      2368824.99     13664325.01
#Sta/Elev= 30
  4459.0  334.04  4495.1  333.55  4532.5  331.68  4682.9  327.69  4740.0  327.29
  4747.5  326.63  4783.5  327.37  4791.0  326.88  4819.6  327.03  4827.1  326.17
  4848.1  326.71  4899.2  324.90  4971.3  325.29  4992.4  324.35  4996.9  323.21
  5011.4  322.73  5011.7  322.23  5015.2  322.23  5015.4  322.73  5022.7  323.65
  5086.2  324.88  5101.5  325.99  5212.9  328.72  5345.5  330.73  5404.6  331.53
  5413.9  332.14  5437.8  332.08  5535.0  334.48  5601.8  337.47  5651.8  338.25
#Mann=7,-1,0
  4459.0    0.07       0  4532.5   0.035       0  5011.4   0.035       0
  5015.4   0.035       0  5212.9    0.05       0  5345.5   0.035       0
  5437.8    0.05       0
Bank Sta=5011.4,5015.4
Exp/Cntr=0.3,0.1

Type RM Length L Ch R = 1,1912,484,484,484
BEGIN DESCRIPTION:
Stream0593 4.0
END DESCRIPTION:
XS GIS Cut Line= 3
      2369675.00     13663225.00      2369275.00     13663575.00
      2368925.02     13663774.99
#Sta/Elev= 30
  4468.1  335.55  4496.1  334.76  4517.9  333.02  4553.1  331.08  4624.2  330.03
  4638.5  329.29  4722.9  327.72  4730.5  326.86  4751.4  327.62  4921.3  324.13
  4964.0  322.49  4971.6  321.74  4985.9  321.49  4994.3  320.76  4994.5  320.26
  4998.0  320.26  4998.3  320.76  5002.5  320.76  5013.3  322.13  5045.0  322.72
  5080.2  324.63  5088.7  324.63  5137.8  324.89  5166.6  325.73  5233.6  327.54
  5271.0  329.54  5286.8  329.54  5357.4  331.98  5373.2  331.68  5402.7  332.28
#Mann=5,-1,0
  4468.1    0.07       0  4994.3    0.05       0  4998.3    0.07       0
  5088.7   0.035       0  5166.6    0.05       0
Bank Sta=4994.3,4998.3
Exp/Cntr=0.3,0.1

Type RM Length L Ch R = 1,1428,432,432,432
BEGIN DESCRIPTION:
Stream0593 3.0
END DESCRIPTION:
XS GIS Cut Line= 3
      2369425.01     13662974.99      2369175.00     13663125.00
      2368874.99     13663225.00
#Sta/Elev= 30
  4712.7  331.49  4733.8  330.85  4747.7  329.63  4757.4  329.65  4763.2  329.35
  4771.0  328.24  4778.7  328.76  4784.6  328.24  4794.3  328.30  4852.7  325.88
  4922.6  323.65  4932.3  322.94  4938.2  322.97  4953.7  321.41  4969.3  320.64
  4990.7  317.93  4994.5  317.68  4994.7  317.18  4998.2  317.18  4998.5  317.68
  5006.9  317.76  5025.3  318.79  5046.4  318.45  5078.0  321.56  5091.7  322.24
  5099.1  322.79  5130.8  323.16  5215.1  324.95  5309.9  328.51  5320.5  328.62
#Mann=6,-1,0
  4712.7    0.07       0  4733.8   0.035       0  4778.7    0.07       0
  4994.5    0.05       0  4998.5    0.07       0  5091.7    0.05       0
Bank Sta=4994.5,4998.5
Exp/Cntr=0.3,0.1

Type RM Length L Ch R = 1,996,302,302,302
BEGIN DESCRIPTION:
Stream0593 2.0
END DESCRIPTION:
XS GIS Cut Line= 3
      2369275.02     13662624.99      2369075.00     13662725.00
      2368874.98     13662775.00
#Sta/Elev= 30
  4780.5  326.73  4794.5  326.14  4802.9  326.25  4811.3  325.76  4825.2  325.54
  4914.7  320.92  4937.0  319.08  4951.0  316.42  4959.4  315.85  4967.8  315.55
  4973.4  315.69  4979.8  315.24  4980.0  314.74  4983.5  314.74  4983.8  315.24
  4990.2  315.82  4995.7  315.85  5006.7  315.86  5014.4  315.38  5022.2  316.65
  5027.3  316.43  5035.1  317.37  5045.4  320.19  5055.7  322.02  5063.4  322.58
  5076.3  323.09  5138.1  324.06  5151.0  324.65  5179.4  325.25  5210.3  326.29
#Mann=3,-1,0
  4780.5    0.07       0  4979.8    0.05       0  4983.8    0.07       0
Bank Sta=4979.8,4983.8
Exp/Cntr=0.3,0.1

Type RM Length L Ch R = 1,694,454,454,454
BEGIN DESCRIPTION:
XS7179
END DESCRIPTION:
XS GIS Cut Line= 2
      2369442.13     13662214.39      2368679.14     13662621.90
#Sta/Elev= 30
  4527.3  332.58  4562.1  331.44  4605.3  331.15  4639.9  330.60  4666.2  330.05
  4725.9  326.70  4732.0  327.01  4814.1  322.39  4901.9  318.70  4909.5  317.15
  4932.2  315.03  4989.7  312.06  4998.2  309.73  4998.5  309.23  5002.2  309.73
  5006.0  311.80  5044.3  314.32  5056.9  316.35  5066.2  316.80  5071.9  318.37
  5079.6  317.97  5110.1  320.50  5132.1  321.05  5137.7  321.88  5197.9  322.75
  5241.8  324.59  5272.3  327.26  5302.0  327.19  5351.6  330.01  5392.3  331.04
#Mann=6,-1,0
  4527.3    0.05       0  4605.3    0.07       0  4639.9    0.05       0
  4725.9    0.07       0  4998.2    0.05       0  5002.2    0.07       0
Bank Sta=4998.2,5002.2
Exp/Cntr=0.3,0.1

Type RM Length L Ch R = 1,240,0,0,0
BEGIN DESCRIPTION:
XS7178
END DESCRIPTION:
XS GIS Cut Line= 4
      2369437.77     13661858.50      2368886.55     13662023.44
      2368738.98     13662231.77      2368691.57     13662511.91
#Sta/Elev= 30
  4417.5  333.63  4495.6  332.71  4567.0  330.52  4594.9  327.76  4600.1  327.99
  4666.3  322.67  4683.7  322.14  4770.8  317.86  4844.0  316.43  4921.4  315.31
  4941.5  312.21  4973.6  309.08  4977.9  307.45  4978.1  306.95  4981.9  307.45
  4985.1  308.71  4991.1  309.40  5067.8  311.46  5109.6  314.97  5151.5  317.06
  5239.9  321.64  5261.6  321.79  5271.7  322.89  5281.9  321.96  5304.6  322.69
  5352.9  325.68  5425.4  326.17  5480.7  327.74  5505.0  329.29  5532.3  328.76
#Mann=6,-1,0
  4417.5    0.05       0  4683.7    0.07       0  4844.0     0.1       0
  4977.9    0.05       0  4981.9     0.1       0  5151.5    0.07       0
Bank Sta=4977.9,4981.9
Exp/Cntr=0.3,0.1

Chan Stop Cuts=-1