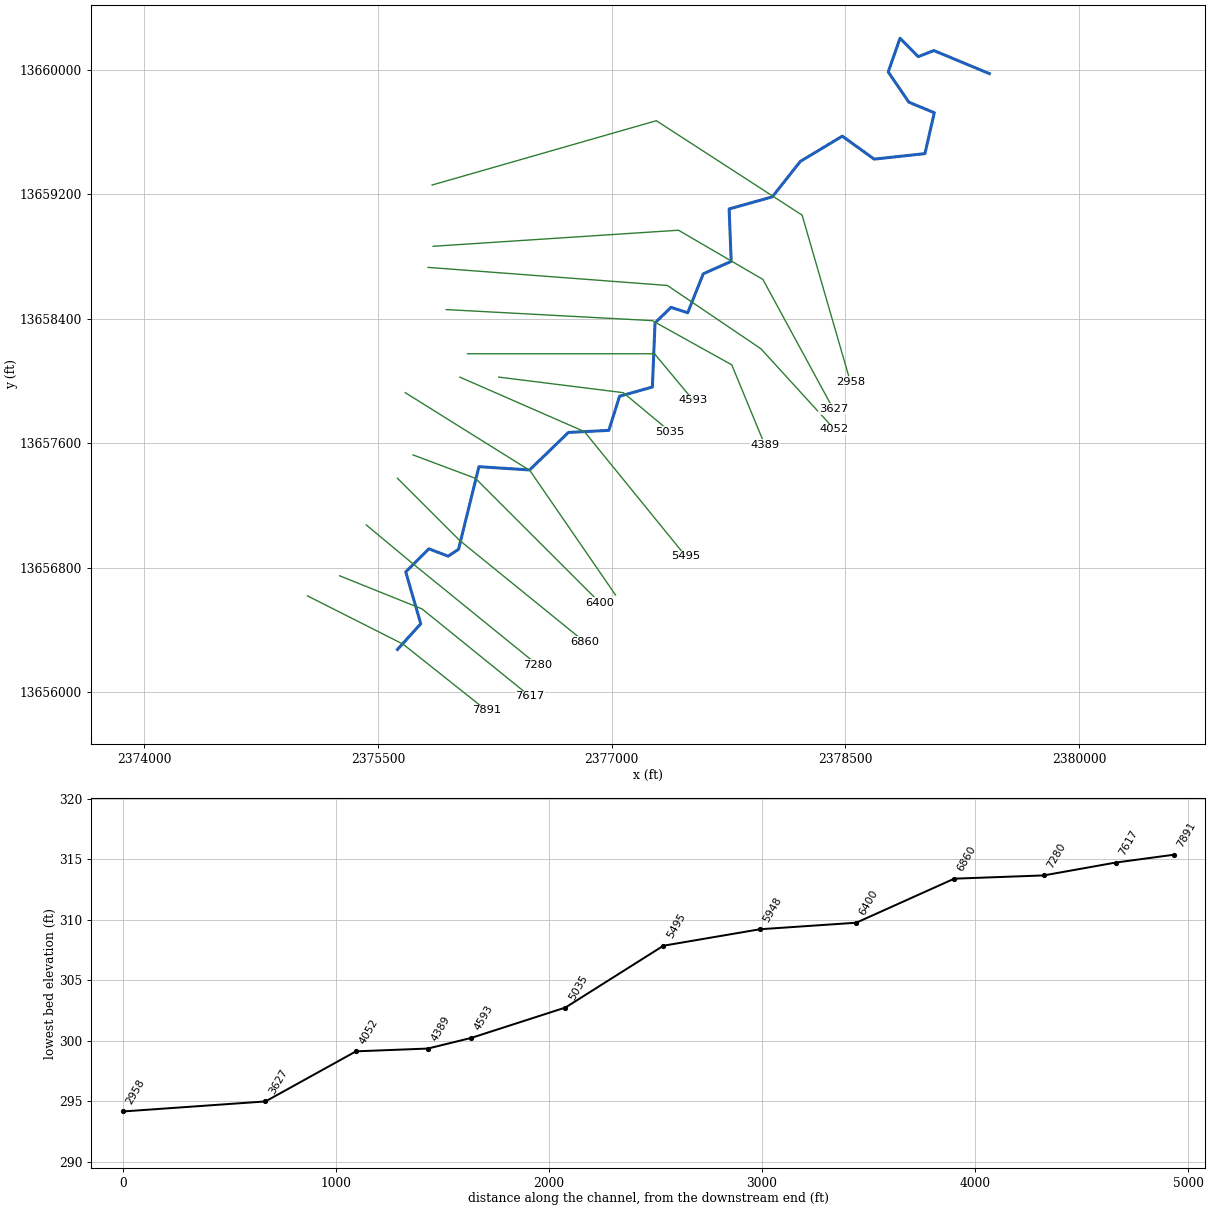
--- Stream0596.prj (project) ---

Proj Title=Stream0596 Base Level Engineering
Current Plan=p01
Default Exp/Contr=0.3,0.1
English Units
Geom File=g01
Flow File=f01
Plan File=p01
BEGIN DESCRIPTION:
Stream0596
END DESCRIPTION:

--- Stream0596.p01 (plan) ---

Plan Title=Multiple Run
Short Identifier=Multiple
Geom File=g01
Flow File=f01
Subcritical Flow
K Sum by GR= 0
Std Step Tol= 0.01
Critical Tol= 0.01
Num of Std Step Trials= 20
Max Error Tol= 0.3
Flow Tol Ratio= 0.001
Split Flow NTrial= 30
Split Flow Tol= 0.02
Split Flow Ratio= 0.02
Log Output Level= 0
Friction Slope Method= 1
Unsteady Friction Slope Method= 2
Unsteady Bridges Friction Slope Method= 1
Parabolic Critical Depth
Global Vel Dist=  1 , 1 , 1
Global Log Level= 0
CheckData=True
Encroach Param= -1, 0, 0, 0
BEGIN DESCRIPTION:
Multiple Run
END DESCRIPTION:

--- Stream0596.f01 (steady flow) ---

Flow Title=Multiple
Number of Profiles=7
Profile Names=10-year,25-year,50-year,1pct_min,100-year,1pct_plu,500-year
River Rch & RM= Stream0596,Reach-1,7891
     644    1044    1407     918    1832    3655    3076
River Rch & RM= Stream0596,Reach-1,7280
     869    1430    1945    1278    2551    5089    4353
Boundary for River Rch & Prof#=Stream0596,Reach-1,1
Up Type=0
Dn Type=3
Dn Slope=0.005
Boundary for River Rch & Prof#=Stream0596,Reach-1,2
Up Type=0
Dn Type=3
Dn Slope=0.005
Boundary for River Rch & Prof#=Stream0596,Reach-1,3
Up Type=0
Dn Type=3
Dn Slope=0.005
Boundary for River Rch & Prof#=Stream0596,Reach-1,4
Up Type=0
Dn Type=3
Dn Slope=0.005
Boundary for River Rch & Prof#=Stream0596,Reach-1,5
Up Type=0
Dn Type=3
Dn Slope=0.005
Boundary for River Rch & Prof#=Stream0596,Reach-1,6
Up Type=0
Dn Type=3
Dn Slope=0.005
Boundary for River Rch & Prof#=Stream0596,Reach-1,7
Up Type=0
Dn Type=3
Dn Slope=0.005

--- Stream0596.g01 (geometry) ---

Geom Title=Existing Conditions

River Reach=Stream0596,Reach-1
Reach XY= 30
      2375625.00     13656275.00      2375774.64     13656440.16
      2375678.12     13656773.37      2375826.63     13656921.87
      2375950.12     13656874.48      2376017.00     13656918.57
      2376147.99     13657449.41      2376473.50     13657428.46
      2376722.55     13657669.54      2376981.82     13657682.81
      2377051.09     13657902.29      2377261.65     13657961.19
      2377278.53     13658373.55      2377381.04     13658473.35
      2377488.41     13658438.53      2377588.20     13658688.73
      2377767.65     13658768.62      2377754.34     13659105.60
      2378031.34     13659183.02      2378211.79     13659411.37
      2378481.12     13659573.24      2378685.62     13659425.60
      2379011.39     13659460.97      2379071.57     13659723.77
      2378908.21     13659791.44      2378775.79     13659985.70
      2378851.62     13660202.64      2378967.99     13660084.04
      2379068.86     13660123.14      2379425.00     13659975.00

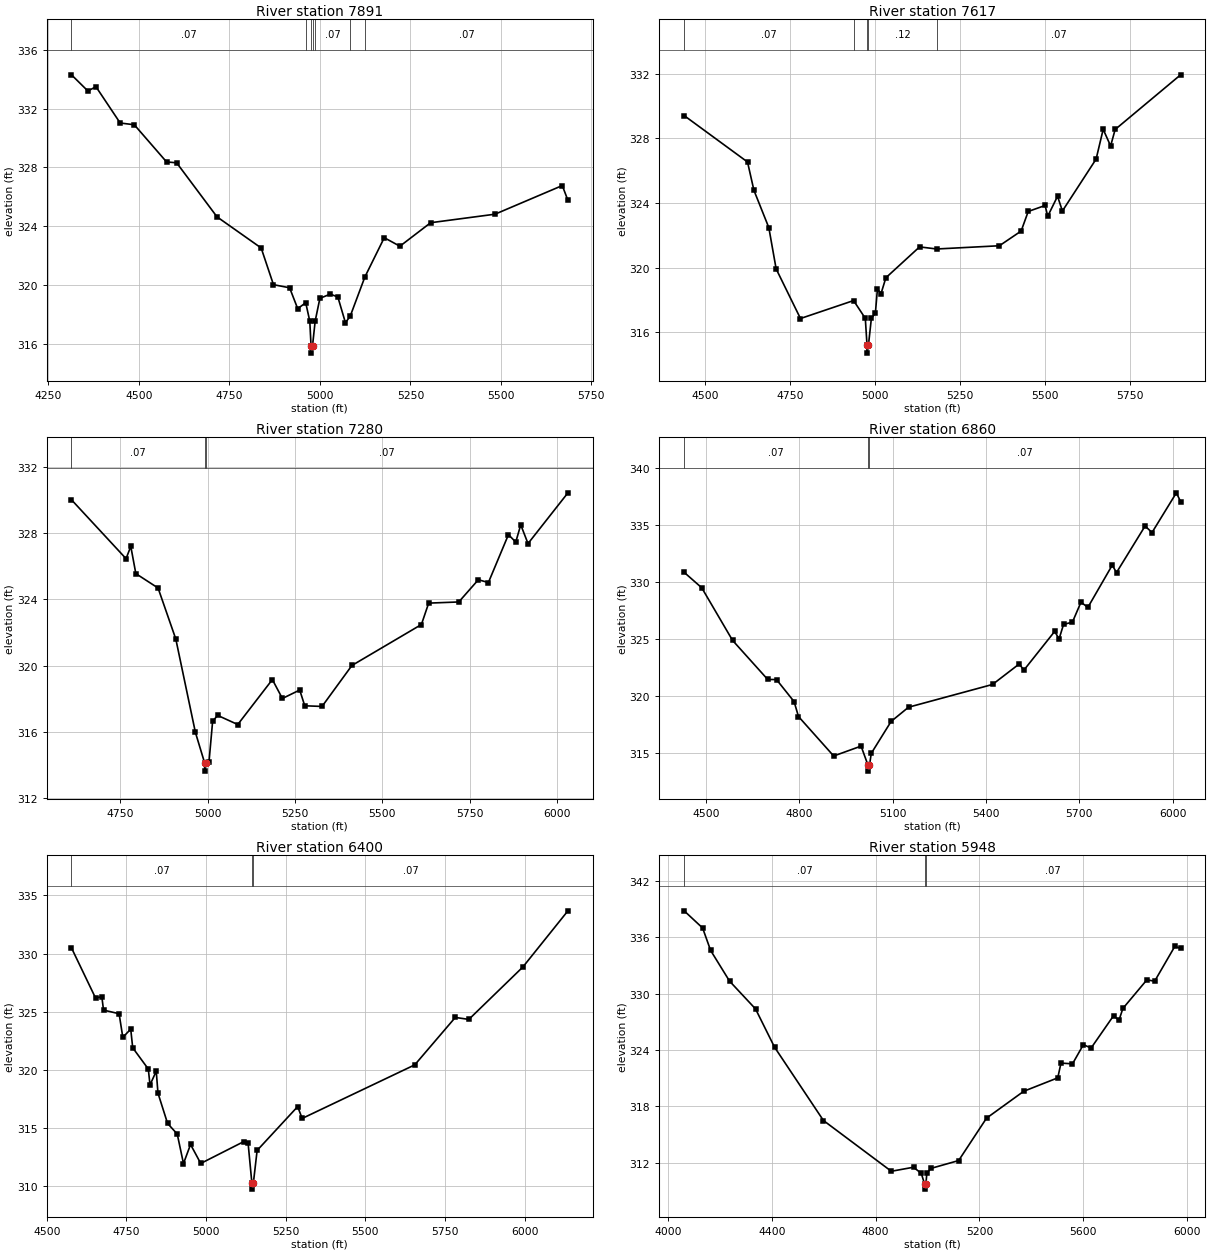
Type RM Length L Ch R = 1,7891,274,274,274
BEGIN DESCRIPTION:
XS7191
END DESCRIPTION:
XS GIS Cut Line= 3
      2375047.28     13656619.28      2375660.44     13656309.47
      2376196.22     13655883.44
#Sta/Elev= 30
  4313.7  334.31  4359.0  333.21  4381.3  333.50  4448.2  331.03  4487.2  330.91
  4576.3  328.38  4604.2  328.32  4715.7  324.64  4837.7  322.52  4871.7  320.02
  4916.3  319.81  4938.6  318.39  4960.8  318.79  4972.0  317.54  4975.5  315.86
  4975.8  315.36  4979.6  315.86  4986.9  317.54  4999.9  319.09  5028.8  319.38
  5049.6  319.18  5070.4  317.44  5083.5  317.86  5124.3  320.55  5177.8  323.22
  5221.0  322.64  5305.9  324.24  5483.7  324.82  5669.6  326.77  5685.2  325.76
#Mann=7,-1,0
  4313.7    0.07       0  4960.8    0.12       0  4975.5    0.05       0
  4979.6    0.12       0  4986.9    0.07       0  5083.5    0.12       0
  5124.3    0.07       0
Bank Sta=4975.5,4979.6
Exp/Cntr=0.3,0.1

Type RM Length L Ch R = 1,7617,337,337,337
BEGIN DESCRIPTION:
Stream0596 12.0
END DESCRIPTION:
XS GIS Cut Line= 3
      2375253.83     13656748.38      2375783.08     13656535.39
      2376475.01     13655974.99
#Sta/Elev= 30
  4437.7  329.40  4624.2  326.53  4643.0  324.78  4686.9  322.47  4708.4  319.92
  4780.0  316.85  4936.3  317.96  4970.8  316.86  4975.8  315.21  4976.1  314.71
  4980.1  315.21  4988.7  316.87  5000.4  317.17  5006.5  318.68  5016.9  318.38
  5031.3  319.37  5130.5  321.28  5180.7  321.15  5365.4  321.35  5429.4  322.26
  5450.2  323.47  5499.8  323.84  5507.7  323.18  5536.5  324.41  5550.8  323.50
  5650.0  326.71  5670.8  328.55  5692.7  327.52  5706.0  328.54  5898.6  331.92
#Mann=5,-1,0
  4437.7    0.07       0  4936.3    0.12       0  4975.8    0.05       0
  4980.1    0.12       0  5180.7    0.07       0
Bank Sta=4975.8,4980.1
Exp/Cntr=0.3,0.1

Type RM Length L Ch R = 1,7280,420,420,420
BEGIN DESCRIPTION:
Stream0596 11.0
END DESCRIPTION:
XS GIS Cut Line= 3
      2375425.02     13657074.98      2375725.00     13656825.00
      2376525.03     13656174.98
#Sta/Elev= 30
  4609.8  330.01  4766.0  326.46  4779.6  327.20  4794.0  325.56  4857.7  324.69
  4908.5  321.61  4964.5  315.99  4990.9  314.15  4991.2  313.65  4995.3  314.15
  5003.5  314.21  5013.9  316.66  5028.3  317.01  5085.8  316.46  5184.9  319.17
  5213.6  318.03  5263.2  318.54  5277.6  317.59  5327.1  317.55  5412.6  320.02
  5611.6  322.49  5632.4  323.78  5718.6  323.85  5774.6  325.19  5803.4  325.02
  5860.8  327.91  5881.7  327.46  5896.0  328.50  5916.8  327.37  6031.1  330.43
#Mann=3,-1,0
  4609.8    0.07       0  4990.9    0.05       0  4995.3    0.07       0
Bank Sta=4990.9,4995.3
Exp/Cntr=0.3,0.1

Type RM Length L Ch R = 1,6860,460,460,460
BEGIN DESCRIPTION:
Stream0596 10.0
END DESCRIPTION:
XS GIS Cut Line= 3
      2375624.97     13657375.03      2376025.00     13656975.00
      2376825.00     13656325.00
#Sta/Elev= 30
  4429.2  330.86  4485.8  329.50  4584.8  324.88  4697.9  321.44  4726.2  321.43
  4782.8  319.49  4796.9  318.18  4910.1  314.71  4998.2  315.58  5020.7  313.88
  5021.0  313.38  5025.2  313.88  5030.9  314.94  5094.8  317.75  5150.8  319.00
  5420.9  321.00  5507.1  322.81  5521.5  322.25  5620.6  325.66  5635.0  325.01
  5649.3  326.28  5677.8  326.48  5705.3  328.23  5727.6  327.78  5805.9  331.49
  5819.6  330.84  5911.5  334.93  5933.8  334.36  6012.1  337.85  6025.7  337.08
#Mann=3,-1,0
  4429.2    0.07       0  5020.7    0.05       0  5025.2    0.07       0
Bank Sta=5020.7,5025.2
Exp/Cntr=0.3,0.1

Type RM Length L Ch R = 1,6400,452,452,452
BEGIN DESCRIPTION:
Stream0596 9.0
END DESCRIPTION:
XS GIS Cut Line= 3
      2375724.99     13657525.00      2376125.00     13657375.00
      2376925.01     13656574.99
#Sta/Elev= 30
  4577.4  330.49  4653.1  326.17  4672.6  326.30  4678.0  325.14  4726.9  324.83
  4738.5  322.80  4763.4  323.50  4769.6  321.90  4818.6  320.07  4823.9  318.70
  4843.5  319.89  4848.9  318.00  4879.1  315.39  4909.4  314.48  4929.0  311.94
  4951.2  313.58  4983.2  311.95  5117.7  313.82  5131.9  313.69  5143.8  310.24
  5144.1  309.74  5148.3  310.24  5160.2  313.07  5287.5  316.84  5301.6  315.82
  5655.1  320.43  5782.4  324.51  5824.9  324.34  5994.6  328.85  6136.0  333.68
#Mann=3,-1,0
  4577.4    0.07       0  5143.8    0.05       0  5148.3    0.07       0
Bank Sta=5143.8,5148.3
Exp/Cntr=0.3,0.1

Type RM Length L Ch R = 1,5948,453,453,453
BEGIN DESCRIPTION:
Stream0596 8.0
END DESCRIPTION:
XS GIS Cut Line= 3
      2375675.04     13657924.98      2376475.00     13657425.00
      2377025.01     13656624.98
#Sta/Elev= 30
  4061.5  338.81  4132.8  336.98  4163.5  334.60  4236.6  331.33  4336.8  328.37
  4409.9  324.31  4598.6  316.50  4860.4  311.10  4945.9  311.53  4976.0  310.87
  4989.0  309.70  4989.3  309.20  4993.6  309.70  4997.2  310.88  5012.3  311.40
  5119.9  312.24  5227.4  316.75  5370.8  319.61  5502.1  321.04  5514.5  322.61
  5558.9  322.53  5600.9  324.57  5630.6  324.21  5717.2  327.65  5738.2  327.17
  5753.1  328.42  5845.8  331.47  5875.6  331.32  5953.3  335.02  5975.7  334.82
#Mann=3,-1,0
  4061.5    0.07       0  4989.0    0.05       0  4993.6    0.07       0
Bank Sta=4989,4993.6
Exp/Cntr=0.3,0.1

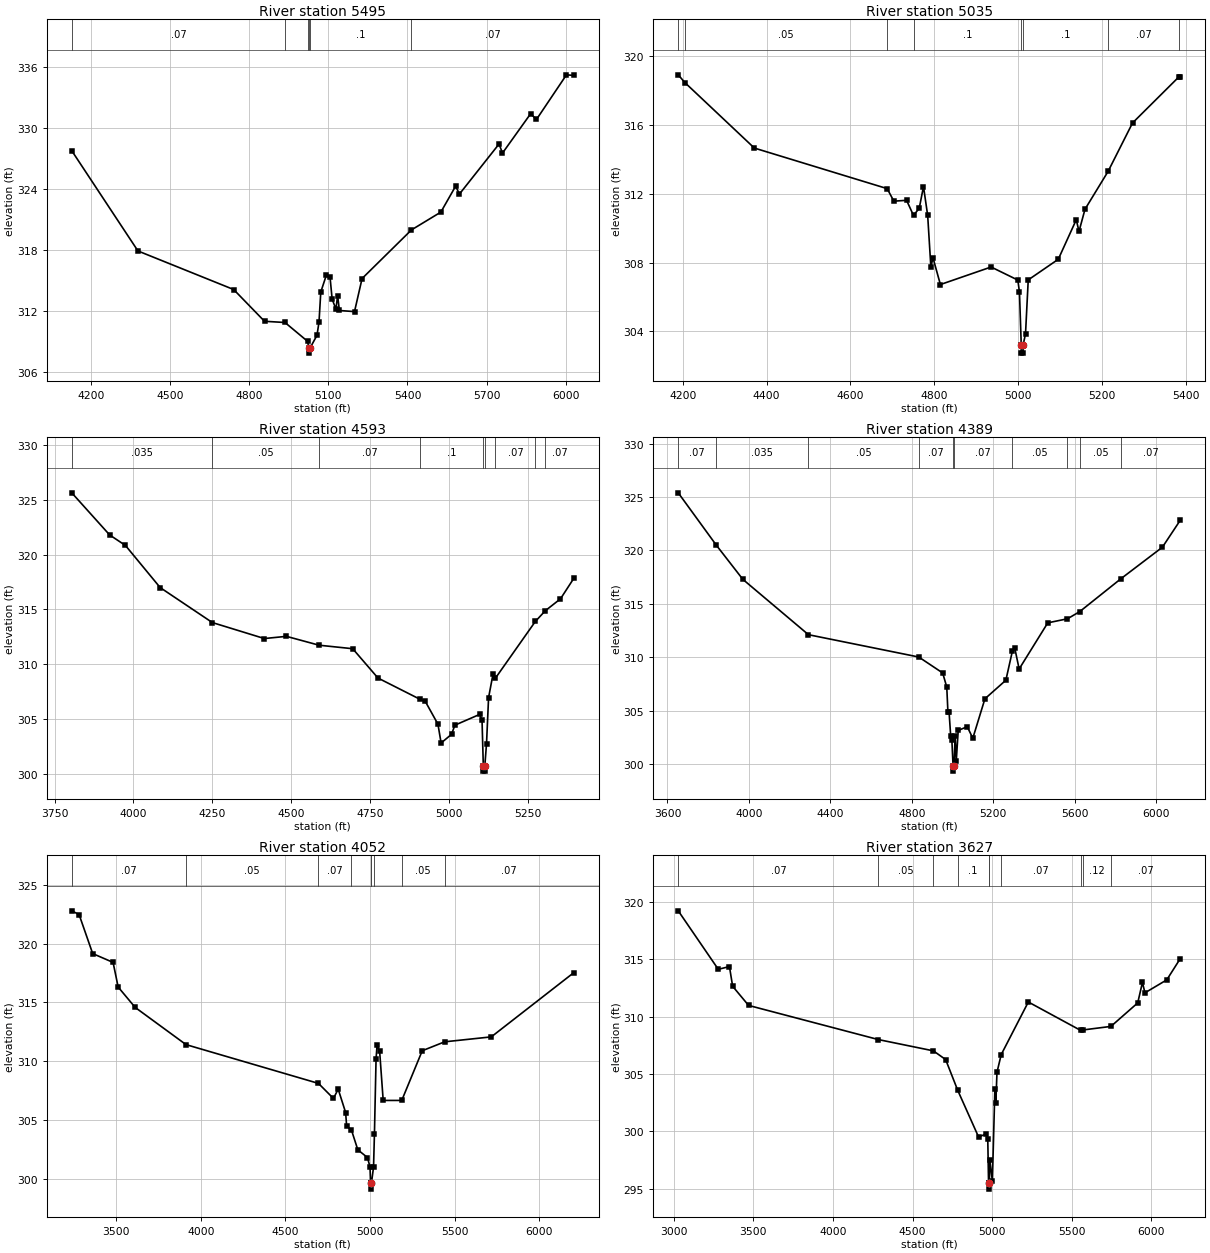
Type RM Length L Ch R = 1,5495,460,460,460
BEGIN DESCRIPTION:
Stream0596 7.0
END DESCRIPTION:
XS GIS Cut Line= 3
      2376025.01     13658025.00      2376825.00     13657675.00
      2377475.01     13656874.99
#Sta/Elev= 30
  4127.0  327.73  4378.0  317.88  4741.0  314.09  4857.9  310.97  4935.6  310.85
  5021.3  309.00  5025.9  308.34  5026.2  307.84  5030.6  308.34  5056.9  309.59
  5064.6  310.90  5071.3  313.84  5092.1  315.48  5106.5  315.29  5114.4  313.14
  5128.8  312.17  5135.2  313.50  5141.9  312.03  5199.2  311.92  5227.9  315.17
  5415.2  319.95  5526.7  321.70  5582.7  324.25  5597.1  323.47  5747.3  328.39
  5760.4  327.50  5867.2  331.37  5889.2  330.80  6003.0  335.19  6031.0  335.13
#Mann=6,-1,0
  4127.0    0.07       0  4935.6    0.12       0  5021.3     0.1       0
  5025.9    0.05       0  5030.6     0.1       0  5415.2    0.07       0
Bank Sta=5025.9,5030.6
Exp/Cntr=0.3,0.1

Type RM Length L Ch R = 1,5035,442,442,442
BEGIN DESCRIPTION:
Stream0596 6.0
END DESCRIPTION:
XS GIS Cut Line= 3
      2376274.95     13658025.01      2377075.00     13657925.00
      2377375.01     13657674.99
#Sta/Elev= 30
  4189.4  318.92  4205.2  318.47  4370.8  314.66  4687.4  312.30  4703.4  311.57
  4733.7  311.62  4750.2  310.74  4763.9  311.16  4774.0  312.42  4784.0  310.74
  4791.6  307.74  4796.6  308.28  4814.3  306.72  4935.2  307.74  4998.9  306.98
  5002.8  306.27  5007.0  303.23  5007.3  302.73  5011.3  302.73  5011.7  303.23
  5017.2  303.85  5023.7  306.99  5095.3  308.19  5138.2  310.49  5144.7  309.81
  5159.0  311.10  5214.0  313.30  5272.3  316.12  5382.8  318.80  5386.2  318.80
#Mann=8,-1,0
  4189.4   0.035       0  4205.2    0.05       0  4687.4    0.07       0
  4750.2     0.1       0  5007.0    0.05       0  5011.7     0.1       0
  5214.0    0.07       0  5382.8    0.05       0
Bank Sta=5007,5011.7
Exp/Cntr=0.3,0.1

Type RM Length L Ch R = 1,4593,204,204,204
BEGIN DESCRIPTION:
Stream0596 5.0
END DESCRIPTION:
XS GIS Cut Line= 3
      2376075.03     13658175.00      2377275.00     13658175.00
      2377525.01     13657874.99
#Sta/Elev= 30
  3804.6  325.66  3924.6  321.81  3974.6  320.85  4084.6  317.00  4250.0  313.80
  4414.6  312.34  4484.6  312.54  4588.1  311.73  4694.6  311.41  4774.6  308.73
  4907.6  306.79  4924.6  306.59  4964.6  304.51  4974.6  302.79  5007.8  303.59
  5018.2  304.42  5096.3  305.40  5104.2  304.93  5108.3  300.72  5108.6  300.22
  5112.7  300.22  5113.1  300.72  5118.5  302.74  5125.0  306.94  5139.3  309.13
  5146.5  308.71  5273.1  313.90  5304.6  314.88  5352.8  315.97  5395.1  317.85
#Mann=9,-1,0
  3804.6   0.035       0  4250.0    0.05       0  4588.1    0.07       0
  4907.6     0.1       0  5108.3    0.05       0  5113.1     0.1       0
  5146.5    0.07       0  5273.1    0.05       0  5304.6    0.07       0
Bank Sta=5108.3,5113.1
Exp/Cntr=0.3,0.1

Type RM Length L Ch R = 1,4389,337,337,337
BEGIN DESCRIPTION:
XS7190
END DESCRIPTION:
XS GIS Cut Line= 4
      2375938.02     13658458.91      2377261.22     13658387.91
      2377771.15     13658103.90      2377983.63     13657588.79
#Sta/Elev= 30
  3653.0  325.39  3840.0  320.49  3970.4  317.29  4292.6  312.11  4834.5  310.02
  4951.8  308.53  4971.9  307.21  4977.5  304.91  4983.1  304.91  4991.3  302.60
  4997.0  302.22  5002.9  299.84  5003.3  299.34  5007.7  299.84  5013.0  302.66
  5018.7  300.33  5028.2  303.15  5072.4  303.50  5099.9  302.42  5159.3  306.11
  5262.2  307.85  5294.5  310.60  5305.6  310.88  5327.4  308.90  5468.0  313.22
  5564.8  313.60  5624.9  314.27  5828.0  317.36  6031.0  320.30  6119.0  322.83
#Mann=10,-1,0
  3653.0    0.07       0  3840.0   0.035       0  4292.6    0.05       0
  4834.5    0.07       0  5002.9    0.05       0  5007.7    0.07       0
  5294.5    0.05       0  5564.8    0.07       0  5624.9    0.05       0
  5828.0    0.07       0
Bank Sta=5002.9,5007.7
Exp/Cntr=0.3,0.1

Type RM Length L Ch R = 1,4052,425,425,425
BEGIN DESCRIPTION:
XS7189
END DESCRIPTION:
XS GIS Cut Line= 4
      2375821.82     13658730.01      2377358.04     13658613.83
      2377958.34     13658207.18      2378429.51     13657690.82
#Sta/Elev= 30
  3238.6  322.80  3281.9  322.48  3362.1  319.16  3482.5  318.41  3512.6  316.31
  3612.8  314.58  3913.4  311.41  4695.2  308.11  4783.8  306.83  4811.8  307.62
  4855.7  305.63  4861.7  304.47  4889.7  304.16  4927.6  302.46  4984.5  301.80
  4999.5  301.01  5003.1  299.61  5003.5  299.11  5007.9  299.61  5020.5  300.98
  5025.8  303.78  5035.4  310.20  5041.5  311.39  5056.4  310.87  5077.5  306.66
  5187.1  306.66  5308.1  310.89  5440.6  311.65  5715.8  312.07  6203.3  317.54
#Mann=9,-1,0
  3238.6    0.07       0  3913.4    0.05       0  4695.2    0.07       0
  4889.7     0.1       0  5003.1    0.05       0  5007.9     0.1       0
  5025.8    0.07       0  5187.1    0.05       0  5440.6    0.07       0
Bank Sta=5003.1,5007.9
Exp/Cntr=0.3,0.1

Type RM Length L Ch R = 1,3627,669,669,669
BEGIN DESCRIPTION:
XS7188
END DESCRIPTION:
XS GIS Cut Line= 4
      2375854.07     13658865.56      2377429.05     13658968.84
      2377971.25     13658652.56      2378423.07     13657819.91
#Sta/Elev= 30
  3028.2  319.24  3279.7  314.14  3349.8  314.38  3369.9  312.66  3470.1  310.99
  4285.8  308.01  4630.5  307.03  4707.7  306.27  4783.5  303.59  4914.5  299.52
  4964.0  299.79  4972.3  299.33  4977.3  295.47  4977.7  294.97  4982.1  295.47
  4985.5  297.55  5001.2  295.65  5016.9  303.67  5022.7  302.46  5030.2  305.16
  5056.6  306.70  5227.0  311.29  5554.8  308.82  5569.6  308.85  5745.7  309.16
  5914.1  311.21  5943.6  312.99  5959.6  312.09  6096.6  313.22  6181.6  315.08
#Mann=10,-1,0
  3028.2    0.07       0  4285.8    0.05       0  4630.5    0.07       0
  4783.5     0.1       0  4977.3    0.05       0  4982.1     0.1       0
  5056.6    0.07       0  5554.8   0.035       0  5569.6    0.12       0
  5745.7    0.07       0
Bank Sta=4977.3,4982.1
Exp/Cntr=0.3,0.1

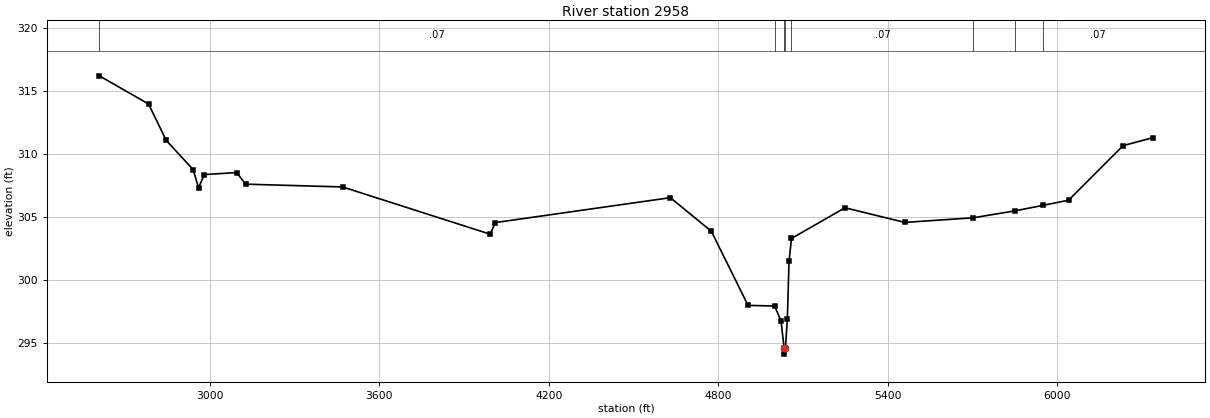
Type RM Length L Ch R = 1,2958,0,0,0
BEGIN DESCRIPTION:
XS7187
END DESCRIPTION:
XS GIS Cut Line= 4
      2375847.59     13659259.29      2377287.04     13659672.41
      2378222.98     13659065.66      2378532.82     13657994.12
#Sta/Elev= 30
  2609.5  316.18  2783.7  313.95  2846.1  311.07  2941.6  308.75  2960.5  307.32
  2981.3  308.36  3095.8  308.52  3127.0  307.60  3470.3  307.38  3992.6  303.64
  4011.3  304.56  4630.6  306.53  4775.6  303.87  4905.5  298.00  4999.7  297.95
  5022.3  296.77  5033.0  294.64  5033.3  294.14  5037.9  294.64  5044.6  296.92
  5050.6  301.49  5059.3  303.30  5248.5  305.73  5460.5  304.57  5703.3  304.94
  5848.7  305.48  5949.3  305.92  6040.0  306.33  6232.9  310.65  6337.9  311.28
#Mann=8,-1,0
  2609.5    0.07       0  4999.7     0.1       0  5033.0    0.05       0
  5037.9     0.1       0  5059.3    0.07       0  5703.3    0.12       0
  5848.7   0.035       0  5949.3    0.07       0
Bank Sta=5033,5037.9
Exp/Cntr=0.3,0.1

Chan Stop Cuts=-1