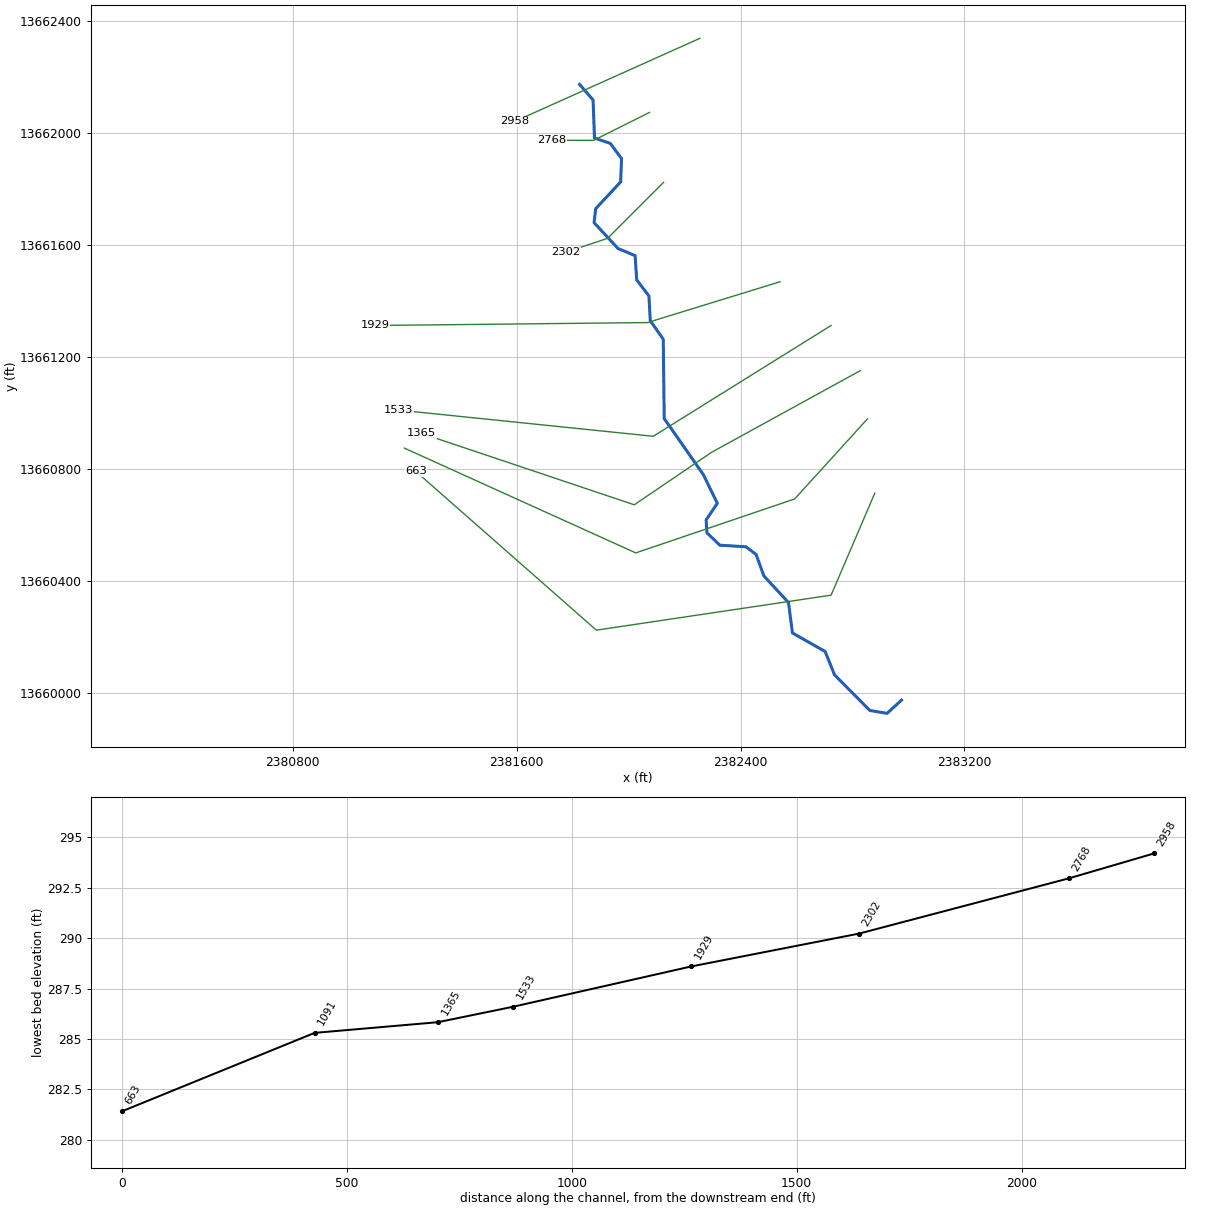
--- Stream0598.prj (project) ---

Proj Title=Stream0598 Base Level Engineering
Current Plan=p01
Default Exp/Contr=0.3,0.1
English Units
Geom File=g01
Flow File=f01
Plan File=p01
BEGIN DESCRIPTION:
Stream0598
END DESCRIPTION:

--- Stream0598.p01 (plan) ---

Plan Title=Multiple Run
Short Identifier=Multiple
Geom File=g01
Flow File=f01
Subcritical Flow
K Sum by GR= 0
Std Step Tol= 0.01
Critical Tol= 0.01
Num of Std Step Trials= 20
Max Error Tol= 0.3
Flow Tol Ratio= 0.001
Split Flow NTrial= 30
Split Flow Tol= 0.02
Split Flow Ratio= 0.02
Log Output Level= 0
Friction Slope Method= 1
Unsteady Friction Slope Method= 2
Unsteady Bridges Friction Slope Method= 1
Parabolic Critical Depth
Global Vel Dist=  1 , 1 , 1
Global Log Level= 0
CheckData=True
Encroach Param= -1, 0, 0, 0
BEGIN DESCRIPTION:
Multiple Run
END DESCRIPTION:

--- Stream0598.f01 (steady flow) ---

Flow Title=Multiple
Number of Profiles=7
Profile Names=10-year,25-year,50-year,1pct_min,100-year,1pct_plu,500-year
River Rch & RM= Stream0598,Reach-1,2958
     563     905    1213     788    1573    3138    2616
Boundary for River Rch & Prof#=Stream0598,Reach-1,1
Up Type=0
Dn Type=3
Dn Slope=0.005
Boundary for River Rch & Prof#=Stream0598,Reach-1,2
Up Type=0
Dn Type=3
Dn Slope=0.005
Boundary for River Rch & Prof#=Stream0598,Reach-1,3
Up Type=0
Dn Type=3
Dn Slope=0.005
Boundary for River Rch & Prof#=Stream0598,Reach-1,4
Up Type=0
Dn Type=3
Dn Slope=0.005
Boundary for River Rch & Prof#=Stream0598,Reach-1,5
Up Type=0
Dn Type=3
Dn Slope=0.005
Boundary for River Rch & Prof#=Stream0598,Reach-1,6
Up Type=0
Dn Type=3
Dn Slope=0.005
Boundary for River Rch & Prof#=Stream0598,Reach-1,7
Up Type=0
Dn Type=3
Dn Slope=0.005

--- Stream0598.g01 (geometry) ---

Geom Title=Existing Conditions

River Reach=Stream0598,Reach-1
Reach XY= 30
      2381825.00     13662175.00      2381873.09     13662119.20
      2381878.10     13661983.31      2381934.76     13661964.25
      2381974.80     13661909.90      2381971.53     13661826.50
      2381882.48     13661731.04      2381876.58     13661681.04
      2381962.02     13661588.73      2382023.26     13661563.13
      2382028.89     13661476.67      2382072.65     13661419.03
      2382077.36     13661330.98      2382123.78     13661264.50
      2382127.24     13660980.93      2382266.86     13660781.04
      2382316.93     13660678.31      2382276.96     13660618.91
      2382280.00     13660572.43      2382326.22     13660528.53
      2382419.28     13660522.92      2382455.41     13660495.57
      2382483.19     13660418.98      2382571.37     13660323.50
      2382585.39     13660214.90      2382702.13     13660148.83
      2382735.79     13660065.34      2382861.77     13659938.14
      2382923.38     13659927.67      2382975.00     13659975.00

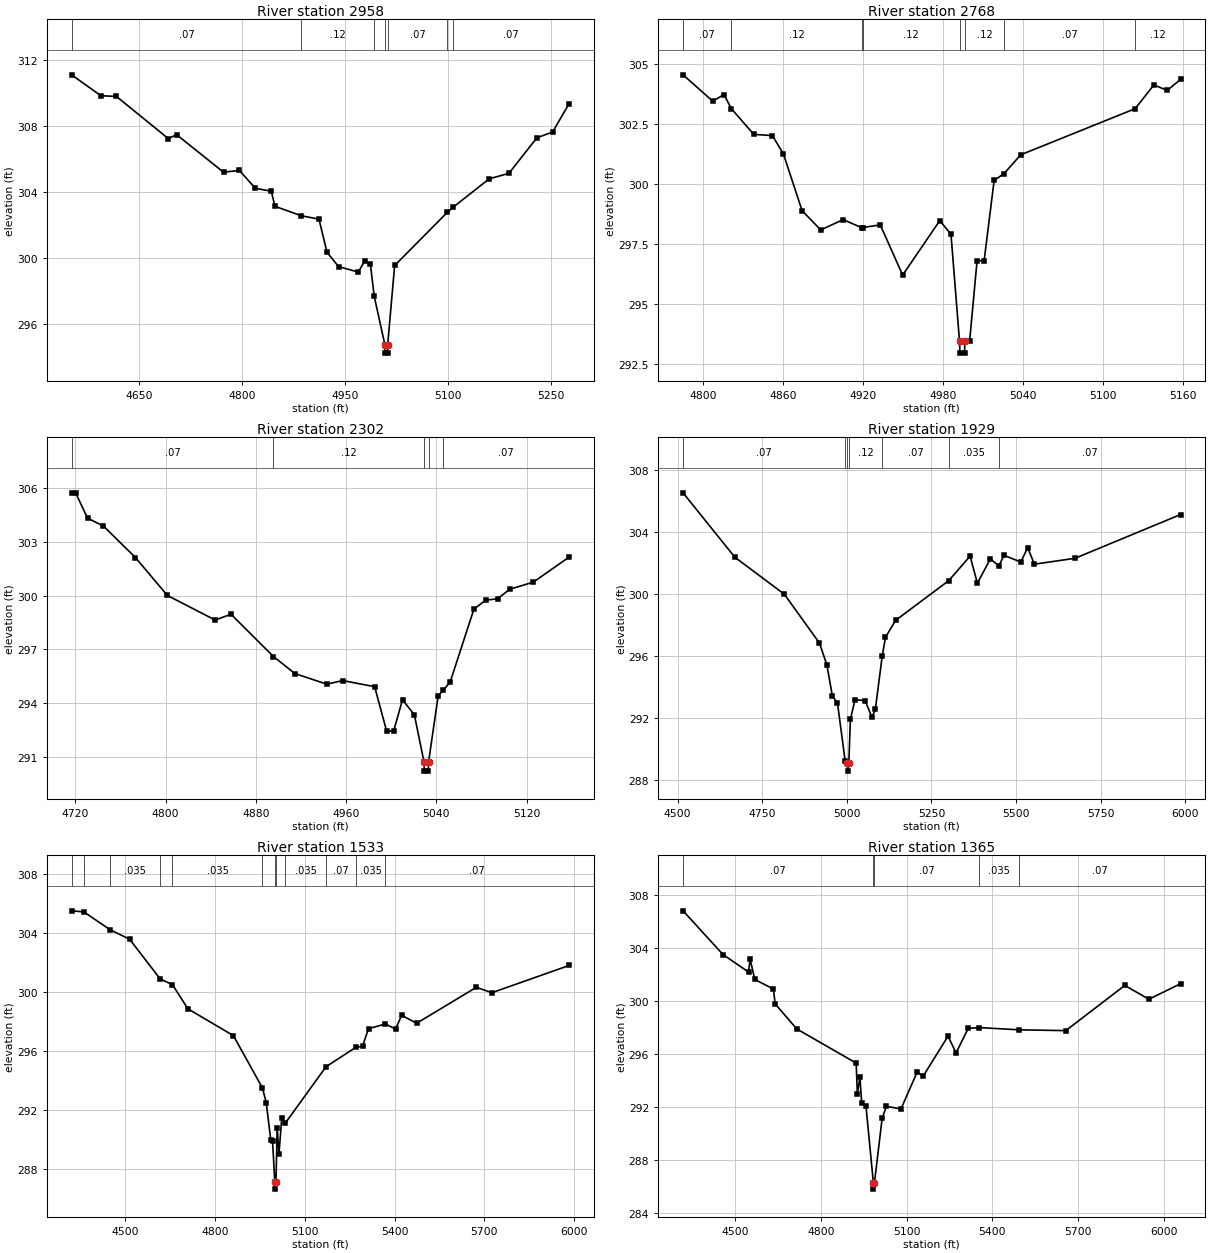
Type RM Length L Ch R = 1,2958,190,190,190
BEGIN DESCRIPTION:
XS7197
END DESCRIPTION:
XS GIS Cut Line= 2
      2382254.64     13662339.56      2381593.21     13662042.70
#Sta/Elev= 30
  4551.2  311.10  4594.1  309.83  4616.6  309.79  4692.2  307.23  4704.3  307.47
  4772.7  305.19  4795.9  305.30  4819.1  304.21  4842.2  304.04  4847.7  303.12
  4885.8  302.55  4911.8  302.34  4923.5  300.33  4940.4  299.46  4969.1  299.13
  4978.3  299.79  4986.7  299.62  4992.3  297.66  5007.9  294.71  5008.2  294.21
  5011.7  294.21  5011.9  294.71  5022.1  299.53  5098.8  302.75  5106.9  303.05
  5159.9  304.79  5188.6  305.12  5229.4  307.28  5252.3  307.63  5276.2  309.34
#Mann=7,-1,0
  4551.2    0.07       0  4885.8    0.12       0  4992.3    0.07       0
  5007.9    0.05       0  5011.9    0.07       0  5098.8    0.12       0
  5106.9    0.07       0
Bank Sta=5007.9,5011.9
Exp/Cntr=0.3,0.1

Type RM Length L Ch R = 1,2768,466,466,466
BEGIN DESCRIPTION:
Stream0598 6.0
END DESCRIPTION:
XS GIS Cut Line= 3
      2382074.98     13662074.99      2381875.00     13661975.00
      2381724.99     13661975.00
#Sta/Elev= 30
  4784.9  304.56  4807.2  303.46  4815.6  303.74  4821.2  303.15  4838.0  302.08
  4852.0  302.03  4860.3  301.26  4874.3  298.90  4888.3  298.10  4905.1  298.53
  4919.3  298.19  4919.7  298.20  4933.0  298.31  4949.8  296.22  4977.7  298.49
  4986.1  297.92  4992.5  293.47  4992.8  292.97  4996.3  292.97  4996.5  293.47
  5000.1  293.47  5005.7  296.82  5011.0  296.82  5018.5  300.16  5026.0  300.45
  5038.5  301.23  5124.4  303.15  5138.5  304.14  5148.5  303.91  5158.5  304.37
#Mann=8,-1,0
  4784.9    0.07       0  4821.2    0.12       0  4919.3    0.07       0
  4919.7    0.12       0  4992.5    0.05       0  4996.5    0.12       0
  5026.0    0.07       0  5124.4    0.12       0
Bank Sta=4992.5,4996.5
Exp/Cntr=0.3,0.1

Type RM Length L Ch R = 1,2302,373,373,373
BEGIN DESCRIPTION:
Stream0598 5.0
END DESCRIPTION:
XS GIS Cut Line= 3
      2382125.02     13661825.02      2381925.00     13661625.00
      2381774.98     13661574.99
#Sta/Elev= 30
  4716.6  305.72  4720.2  305.72  4730.8  304.31  4744.9  303.87  4773.2  302.12
  4801.5  300.01  4843.9  298.64  4858.0  298.96  4895.6  296.61  4914.6  295.66
  4942.9  295.07  4957.0  295.27  4985.3  294.93  4995.9  292.46  5002.1  292.46
  5010.0  294.20  5020.5  293.37  5029.1  290.73  5029.3  290.23  5032.8  290.23
  5033.1  290.73  5041.6  294.42  5045.8  294.72  5052.2  295.18  5073.3  299.25
  5083.8  299.75  5094.3  299.82  5104.9  300.35  5126.0  300.75  5157.6  302.14
#Mann=5,-1,0
  4716.6    0.07       0  4895.6    0.12       0  5029.1    0.05       0
  5033.1    0.12       0  5045.8    0.07       0
Bank Sta=5029.1,5033.1
Exp/Cntr=0.3,0.1

Type RM Length L Ch R = 1,1929,396,396,396
BEGIN DESCRIPTION:
XS7196
END DESCRIPTION:
XS GIS Cut Line= 3
      2382541.16     13661469.80      2382067.19     13661323.96
      2381093.24     13661313.54
#Sta/Elev= 30
  4516.0  306.54  4668.9  302.39  4815.4  300.00  4919.1  296.85  4941.0  295.44
  4957.0  293.46  4972.3  292.98  4994.8  289.27  5001.7  289.10  5002.0  288.60
  5005.7  289.10  5010.4  291.93  5024.1  293.21  5054.1  293.14  5074.1  292.07
  5084.1  292.58  5104.3  296.00  5114.1  297.23  5144.1  298.32  5301.0  300.88
  5364.1  302.46  5385.6  300.71  5424.1  302.29  5449.0  301.82  5464.1  302.51
  5514.1  302.08  5534.1  303.01  5554.1  301.94  5674.1  302.32  5985.9  305.14
#Mann=7,-1,0
  4516.0    0.07       0  4994.8    0.12       0  5001.7    0.05       0
  5005.7    0.12       0  5104.3    0.07       0  5301.0   0.035       0
  5449.0    0.07       0
Bank Sta=5001.7,5005.7
Exp/Cntr=0.3,0.1

Type RM Length L Ch R = 1,1533,168,168,168
BEGIN DESCRIPTION:
XS7195
END DESCRIPTION:
XS GIS Cut Line= 3
      2382723.44     13661313.55      2382088.02     13660917.71
      2381178.25     13661011.28
#Sta/Elev= 30
  4319.8  305.49  4360.9  305.42  4447.7  304.22  4514.0  303.56  4616.4  300.86
  4657.2  300.48  4708.7  298.84  4860.9  297.02  4958.0  293.47  4970.7  292.47
  4986.0  289.92  4991.9  289.85  4999.3  287.10  4999.6  286.60  5003.3  287.10
  5007.3  290.77  5013.2  288.97  5022.6  291.44  5033.8  291.06  5170.7  294.91
  5269.9  296.22  5292.6  296.30  5312.7  297.49  5369.1  297.81  5403.2  297.46
  5423.3  298.40  5473.6  297.86  5673.4  300.30  5724.9  299.93  5983.0  301.78
#Mann=12,-1,0
  4319.8   0.035       0  4360.9    0.07       0  4447.7   0.035       0
  4616.4    0.07       0  4657.2   0.035       0  4958.0    0.07       0
  4999.3    0.05       0  5003.3    0.07       0  5033.8   0.035       0
  5170.7    0.07       0  5269.9   0.035       0  5369.1    0.07       0
Bank Sta=4999.3,5003.3
Exp/Cntr=0.3,0.1

Type RM Length L Ch R = 1,1365,274,274,274
BEGIN DESCRIPTION:
XS7194
END DESCRIPTION:
XS GIS Cut Line= 4
      2382827.63     13661152.10      2382296.35     13660860.42
      2382020.31     13660672.92      2381259.97     13660928.10
#Sta/Elev= 30
  4317.2  306.83  4457.1  303.53  4546.4  302.21  4552.1  303.18  4568.2  301.65
  4633.6  300.93  4639.6  299.81  4715.1  297.92  4923.3  295.34  4927.5  293.00
  4936.4  294.29  4942.4  292.36  4957.4  292.13  4983.4  286.33  4983.6  285.83
  4987.4  286.33  5014.3  291.19  5029.2  292.08  5080.1  291.88  5137.0  294.67
  5158.0  294.36  5244.8  297.37  5273.1  296.11  5315.6  297.96  5354.3  298.02
  5495.0  297.85  5657.3  297.79  5863.8  301.20  5948.2  300.16  6059.0  301.33
#Mann=5,-1,0
  4317.2    0.07       0  4983.4    0.05       0  4987.4    0.07       0
  5354.3   0.035       0  5495.0    0.07       0
Bank Sta=4983.4,4987.4
Exp/Cntr=0.3,0.1

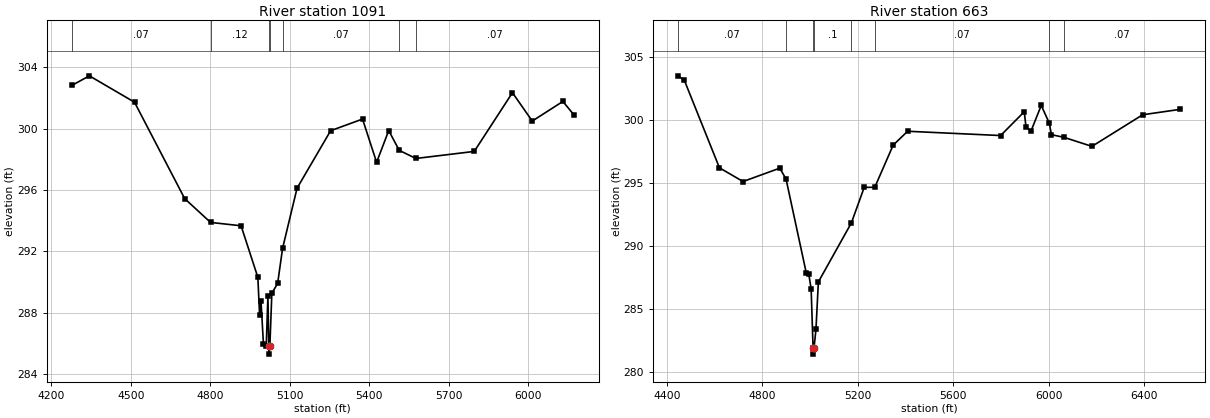
Type RM Length L Ch R = 1,1091,428,428,428
BEGIN DESCRIPTION:
XS7193
END DESCRIPTION:
XS GIS Cut Line= 4
      2382853.68     13660980.24      2382593.23     13660693.75
      2382025.52     13660501.04      2381198.66     13660875.47
#Sta/Elev= 30
  4277.3  302.82  4343.7  303.45  4514.0  301.73  4703.4  295.44  4801.0  293.89
  4916.1  293.67  4979.4  290.31  4986.0  287.84  4991.3  288.76  5000.5  285.96
  5011.1  285.86  5017.4  289.10  5020.7  285.80  5020.9  285.30  5024.7  285.80
  5032.2  289.27  5054.1  289.91  5072.7  292.20  5127.3  296.12  5254.0  299.87
  5374.4  300.63  5427.5  297.81  5473.2  299.88  5512.8  298.59  5575.7  298.06
  5795.9  298.52  5940.0  302.35  6014.8  300.50  6130.3  301.78  6171.7  300.91
#Mann=7,-1,0
  4277.3    0.07       0  4801.0    0.12       0  5020.7    0.05       0
  5024.7    0.12       0  5072.7    0.07       0  5512.8   0.035       0
  5575.7    0.07       0
Bank Sta=5020.7,5024.7
Exp/Cntr=0.3,0.1

Type RM Length L Ch R = 1,663,0,0,0
BEGIN DESCRIPTION:
XS7192
END DESCRIPTION:
XS GIS Cut Line= 4
      2382879.70     13660714.62      2382723.44     13660350.00
      2381884.90     13660225.00      2381239.50     13660792.33
#Sta/Elev= 30
  4447.8  303.50  4473.5  303.14  4620.4  296.20  4719.4  295.11  4873.2  296.17
  4899.5  295.31  4984.8  287.81  4994.6  287.79  5004.7  286.58  5012.8  281.91
  5013.0  281.41  5016.8  281.91  5024.9  283.37  5035.0  287.14  5173.4  291.83
  5227.1  294.65  5271.3  294.65  5348.4  298.00  5409.1  299.10  5798.7  298.76
  5897.7  300.65  5905.2  299.41  5926.1  299.12  5968.8  301.15  6002.8  299.74
  6011.5  298.83  6063.7  298.62  6181.3  297.90  6393.9  300.41  6551.6  300.84
#Mann=8,-1,0
  4447.8    0.07       0  4899.5     0.1       0  5012.8    0.05       0
  5016.8     0.1       0  5173.4    0.12       0  5271.3    0.07       0
  6002.8   0.035       0  6063.7    0.07       0
Bank Sta=5012.8,5016.8
Exp/Cntr=0.3,0.1

Chan Stop Cuts=-1