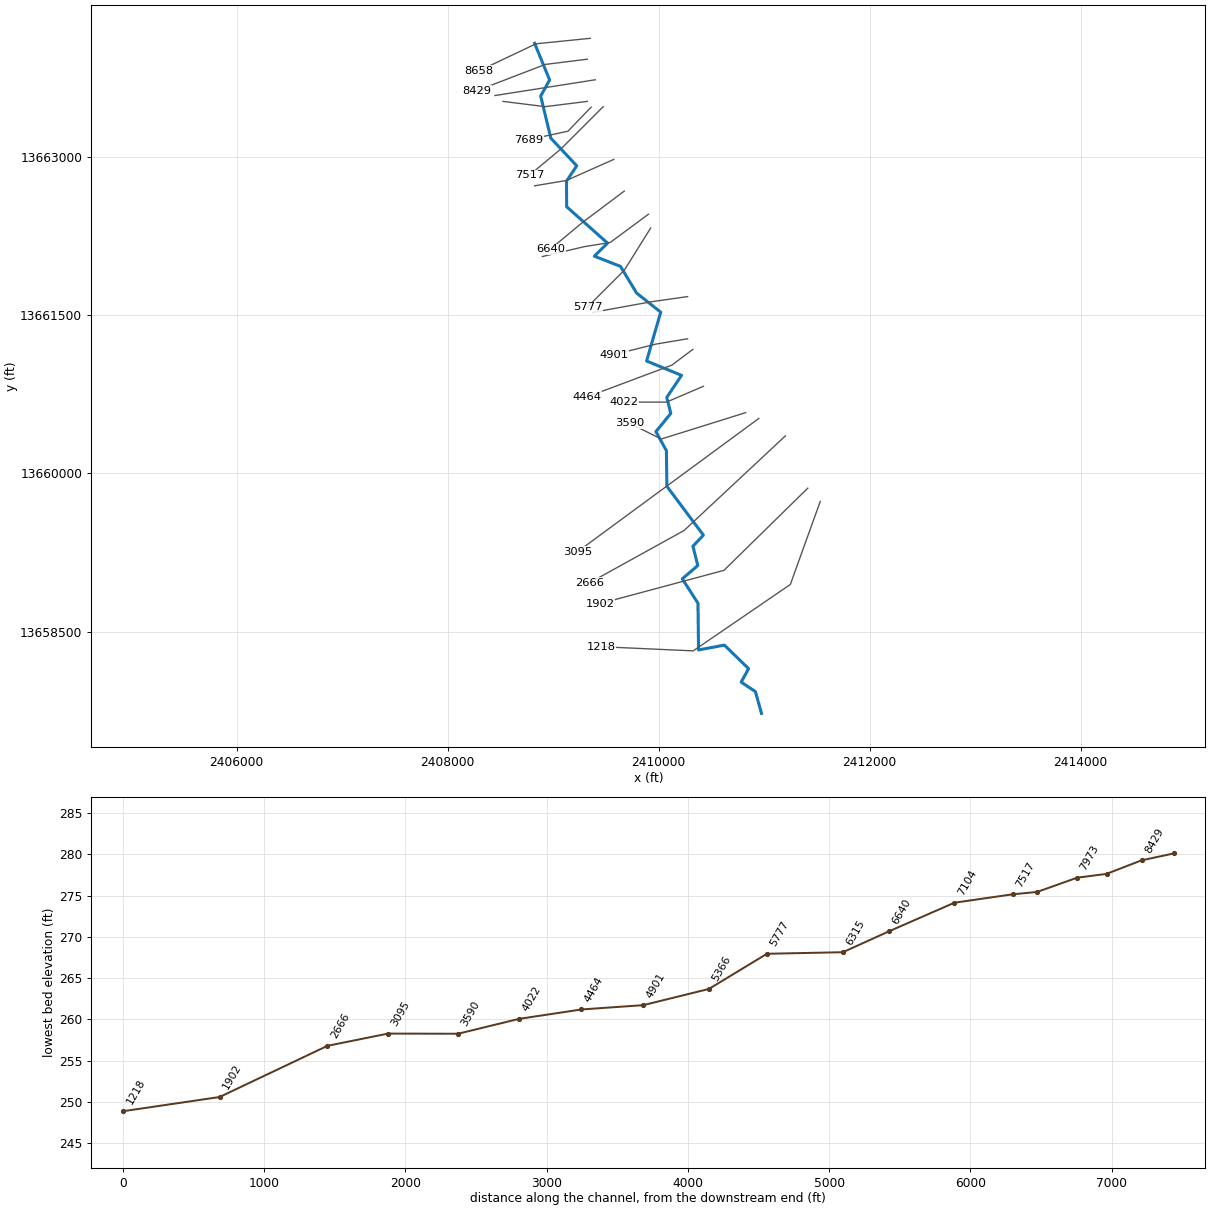
--- Stream0605.prj (project) ---

Proj Title=Stream0605 Base Level Engineering
Current Plan=p01
Default Exp/Contr=0.3,0.1
English Units
Geom File=g01
Flow File=f01
Plan File=p01
BEGIN DESCRIPTION:
Stream0605
END DESCRIPTION:

--- Stream0605.p01 (plan) ---

Plan Title=Multiple Run
Short Identifier=Multiple
Geom File=g01
Flow File=f01
Subcritical Flow
K Sum by GR= 0
Std Step Tol= 0.01
Critical Tol= 0.01
Num of Std Step Trials= 20
Max Error Tol= 0.3
Flow Tol Ratio= 0.001
Split Flow NTrial= 30
Split Flow Tol= 0.02
Split Flow Ratio= 0.02
Log Output Level= 0
Friction Slope Method= 1
Unsteady Friction Slope Method= 2
Unsteady Bridges Friction Slope Method= 1
Parabolic Critical Depth
Global Vel Dist=  1 , 1 , 1
Global Log Level= 0
CheckData=True
Encroach Param= -1, 0, 0, 0
BEGIN DESCRIPTION:
Multiple Run
END DESCRIPTION:

--- Stream0605.f01 (steady flow) ---

Flow Title=Multiple
Number of Profiles=7
Profile Names=10-year,25-year,50-year,1pct_min,100-year,1pct_plu,500-year
River Rch & RM= Stream0605,Reach-1,8658
     629    1012    1356     880    1756    3504    2916
River Rch & RM= Stream0605,Reach-1,7689
     922    1512    2052    1346    2686    5358    4562
Boundary for River Rch & Prof#=Stream0605,Reach-1,1
Up Type=0
Dn Type=3
Dn Slope=0.005
Boundary for River Rch & Prof#=Stream0605,Reach-1,2
Up Type=0
Dn Type=3
Dn Slope=0.005
Boundary for River Rch & Prof#=Stream0605,Reach-1,3
Up Type=0
Dn Type=3
Dn Slope=0.005
Boundary for River Rch & Prof#=Stream0605,Reach-1,4
Up Type=0
Dn Type=3
Dn Slope=0.005
Boundary for River Rch & Prof#=Stream0605,Reach-1,5
Up Type=0
Dn Type=3
Dn Slope=0.005
Boundary for River Rch & Prof#=Stream0605,Reach-1,6
Up Type=0
Dn Type=3
Dn Slope=0.005
Boundary for River Rch & Prof#=Stream0605,Reach-1,7
Up Type=0
Dn Type=3
Dn Slope=0.005

--- Stream0605.g01 (geometry) ---

Geom Title=Existing Conditions

River Reach=Stream0605,Reach-1
Reach XY= 30
      2408825.00     13664075.00      2408966.94     13663728.29
      2408882.53     13663575.01      2408978.53     13663176.45
      2409224.30     13662914.30      2409127.07     13662769.14
      2409128.54     13662526.46      2409516.18     13662181.78
      2409391.00     13662058.04      2409638.33     13661961.61
      2409791.63     13661708.29      2410019.92     13661527.31
      2409885.92     13661064.57      2410217.24     13660928.42
      2410076.98     13660719.10      2410115.87     13660568.26
      2409974.63     13660395.20      2410073.80     13660214.50
      2410078.37     13659876.73      2410424.31     13659414.25
      2410325.25     13659308.98      2410371.63     13659126.28
      2410224.46     13659000.12      2410372.94     13658769.15
      2410378.53     13658325.99      2410623.38     13658371.88
      2410852.76     13658148.70      2410782.50     13658021.42
      2410917.25     13657931.46      2410975.00     13657725.00

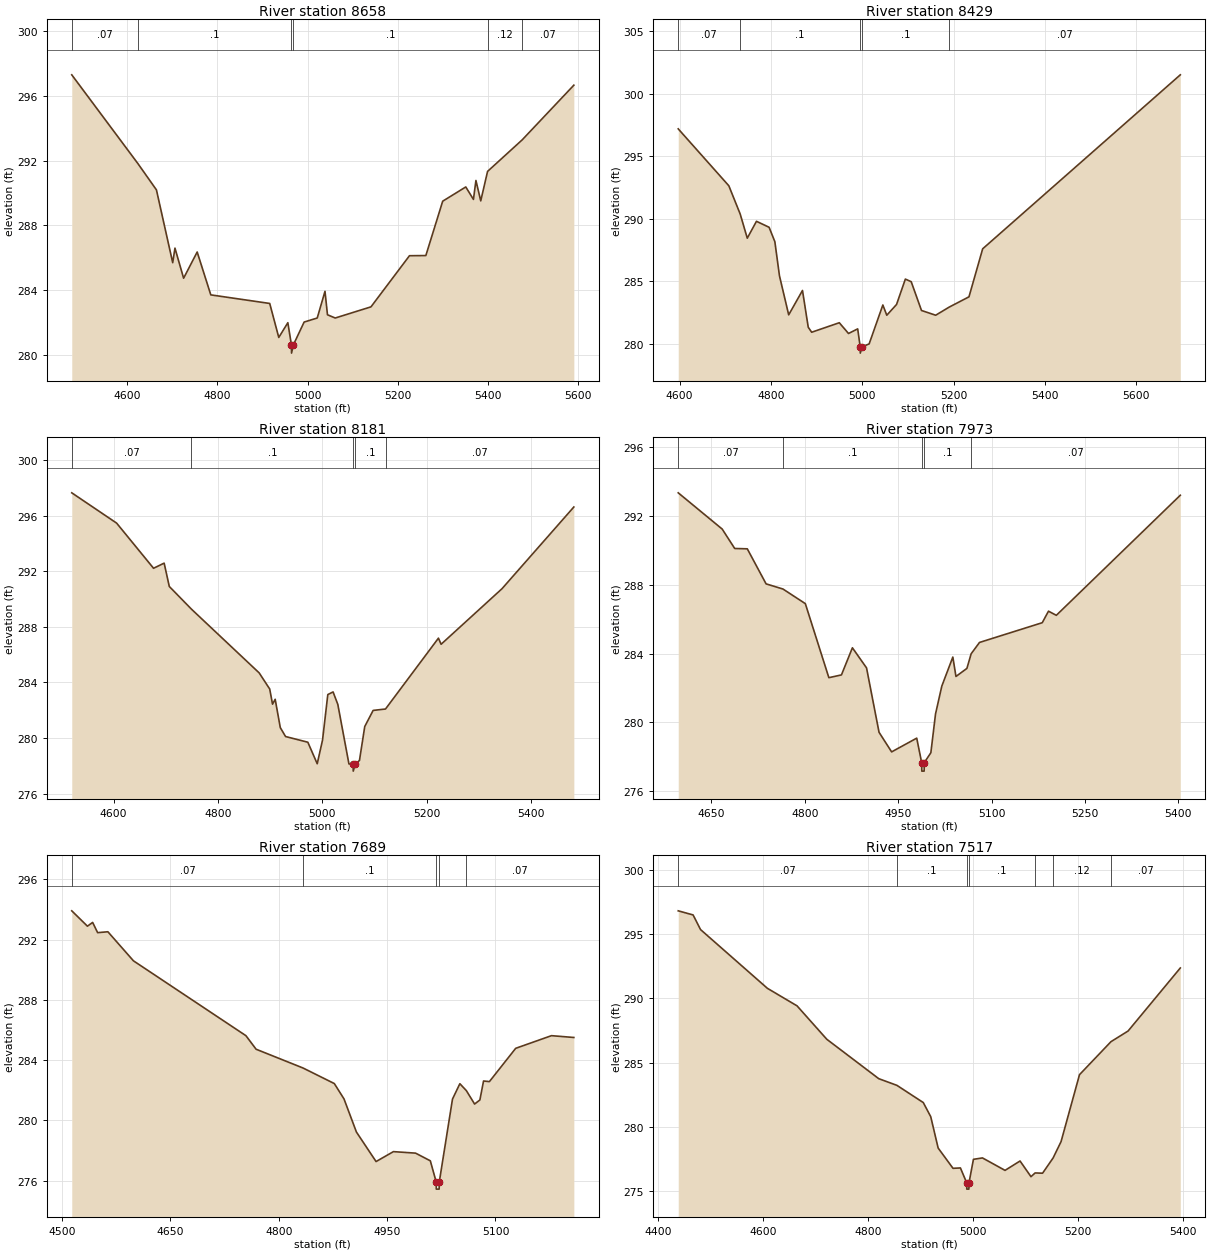
Type RM Length L Ch R = 1,8658,229,229,229
BEGIN DESCRIPTION:
XS7221
END DESCRIPTION:
XS GIS Cut Line= 3
      2409351.85     13664122.50      2408838.05     13664070.80
      2408298.44     13663814.69
#Sta/Elev= 30
  4477.0  297.30  4623.3  291.83  4664.8  290.19  4700.9  285.69  4705.9  286.59
  4725.1  284.73  4755.2  286.35  4785.4  283.70  4916.1  283.17  4936.2  281.07
  4956.3  281.98  4964.3  280.60  4964.5  280.10  4968.4  280.60  4992.4  282.02
  5021.5  282.27  5038.7  283.92  5044.2  282.47  5061.4  282.27  5140.7  282.96
  5226.1  286.12  5262.4  286.13  5299.8  289.49  5351.0  290.37  5368.0  289.60
  5373.5  290.77  5384.2  289.51  5399.3  291.33  5476.1  293.28  5590.7  296.66
#Mann=6,-1,0
  4477.0    0.07       0  4623.3     0.1       0  4964.3    0.05       0
  4968.4     0.1       0  5399.3    0.12       0  5476.1    0.07       0
Bank Sta=4964.3,4968.4
Exp/Cntr=0.3,0.1

Type RM Length L Ch R = 1,8429,248,248,248
BEGIN DESCRIPTION:
Stream0605 18.0
END DESCRIPTION:
XS GIS Cut Line= 3
      2409324.99     13663925.00      2408925.00     13663875.00
      2408275.02     13663625.01
#Sta/Elev= 30
  4596.9  297.19  4707.7  292.64  4732.6  290.38  4748.1  288.45  4768.2  289.80
  4795.9  289.32  4808.5  288.17  4818.6  285.44  4838.8  282.32  4869.0  284.27
  4881.6  281.33  4889.1  280.93  4949.6  281.69  4969.8  280.83  4989.9  281.20
  4995.4  279.76  4995.6  279.26  4999.6  279.76  5015.0  280.00  5045.0  283.11
  5053.6  282.29  5075.0  283.15  5094.3  285.18  5107.1  284.97  5129.6  282.67
  5160.7  282.29  5190.3  282.94  5233.6  283.76  5263.6  287.60  5696.4  301.51
#Mann=5,-1,0
  4596.9    0.07       0  4732.6     0.1       0  4995.4    0.05       0
  4999.6     0.1       0  5190.3    0.07       0
Bank Sta=4995.4,4999.6
Exp/Cntr=0.3,0.1

Type RM Length L Ch R = 1,8181,208,208,208
BEGIN DESCRIPTION:
XS7220
END DESCRIPTION:
XS GIS Cut Line= 2
      2409399.95     13663729.76      2408449.00     13663580.44
#Sta/Elev= 30
  4519.8  297.65  4605.8  295.47  4676.6  292.22  4696.9  292.59  4706.8  290.91
  4749.2  289.28  4879.1  284.69  4899.3  283.53  4904.7  282.44  4909.8  282.79
  4919.6  280.75  4929.7  280.11  4972.4  279.70  4990.4  278.15  5000.6  279.86
  5010.7  283.13  5020.8  283.32  5029.9  282.42  5051.2  278.14  5059.2  278.12
  5059.5  277.62  5063.4  278.12  5071.4  278.39  5081.5  280.83  5097.6  281.99
  5121.3  282.09  5222.8  287.19  5227.9  286.75  5344.7  290.75  5482.4  296.63
#Mann=5,-1,0
  4519.8    0.07       0  4749.2     0.1       0  5059.2    0.05       0
  5063.4     0.1       0  5121.3    0.07       0
Bank Sta=5059.2,5063.4
Exp/Cntr=0.3,0.1

Type RM Length L Ch R = 1,7973,284,284,284
BEGIN DESCRIPTION:
Stream0605 17.0
END DESCRIPTION:
XS GIS Cut Line= 3
      2409325.05     13663525.01      2408925.00     13663475.00
      2408524.98     13663525.00
#Sta/Elev= 30
  4596.8  293.36  4667.4  291.25  4687.5  290.12  4707.7  290.10  4737.9  288.06
  4765.0  287.76  4800.9  286.91  4838.7  282.60  4858.9  282.76  4876.5  284.34
  4899.2  283.17  4919.3  279.42  4939.5  278.28  4979.8  279.08  4987.7  277.66
  4988.0  277.16  4991.7  277.16  4992.0  277.66  5002.5  278.23  5010.0  280.49
  5020.1  282.11  5037.8  283.80  5042.8  282.67  5060.4  283.14  5067.2  283.99
  5080.6  284.65  5181.4  285.80  5191.4  286.47  5204.0  286.23  5403.1  293.22
#Mann=5,-1,0
  4596.8    0.07       0  4765.0     0.1       0  4987.7    0.05       0
  4992.0     0.1       0  5067.2    0.07       0
Bank Sta=4987.7,4992
Exp/Cntr=0.3,0.1

Type RM Length L Ch R = 1,7689,172,172,172
BEGIN DESCRIPTION:
XS7219
END DESCRIPTION:
XS GIS Cut Line= 3
      2409360.61     13663470.17      2409140.33     13663242.02
      2408770.64     13663163.37
#Sta/Elev= 30
  4513.4  293.91  4535.1  292.89  4542.3  293.14  4549.2  292.46  4563.4  292.52
  4598.8  290.59  4754.5  285.62  4768.6  284.72  4833.7  283.47  4876.9  282.44
  4890.3  281.42  4907.5  279.22  4934.7  277.26  4958.7  277.92  4989.4  277.82
  5009.8  277.31  5017.8  275.93  5018.1  275.43  5022.0  275.43  5022.3  275.93
  5040.5  281.41  5050.7  282.43  5059.7  281.97  5071.1  281.08  5078.4  281.35
  5083.5  282.61  5091.6  282.57  5128.0  284.78  5177.5  285.62  5208.5  285.50
#Mann=5,-1,0
  4513.4    0.07       0  4833.7     0.1       0  5017.8    0.05       0
  5022.3     0.1       0  5059.7    0.07       0
Bank Sta=5017.8,5022.3
Exp/Cntr=0.3,0.1

Type RM Length L Ch R = 1,7517,413,413,413
BEGIN DESCRIPTION:
Stream0605 16.0
END DESCRIPTION:
XS GIS Cut Line= 3
      2409475.03     13663475.03      2409075.00     13663075.00
      2408775.03     13662825.03
#Sta/Elev= 30
  4439.1  296.82  4467.4  296.50  4481.6  295.36  4608.8  290.79  4665.4  289.42
  4722.0  286.82  4821.0  283.75  4855.6  283.23  4905.8  281.89  4920.0  280.79
  4934.1  278.35  4962.4  276.77  4976.5  276.80  4988.4  275.65  4988.7  275.15
  4992.6  275.15  4992.9  275.65  5001.3  277.47  5018.5  277.58  5061.5  276.61
  5090.1  277.34  5110.9  276.12  5118.8  276.41  5133.0  276.39  5153.1  277.58
  5168.2  278.85  5203.3  284.06  5263.2  286.63  5295.8  287.46  5395.3  292.37
#Mann=7,-1,0
  4439.1    0.07       0  4855.6     0.1       0  4988.4    0.05       0
  4992.9     0.1       0  5118.8    0.07       0  5153.1    0.12       0
  5263.2    0.07       0
Bank Sta=4988.4,4992.9
Exp/Cntr=0.3,0.1

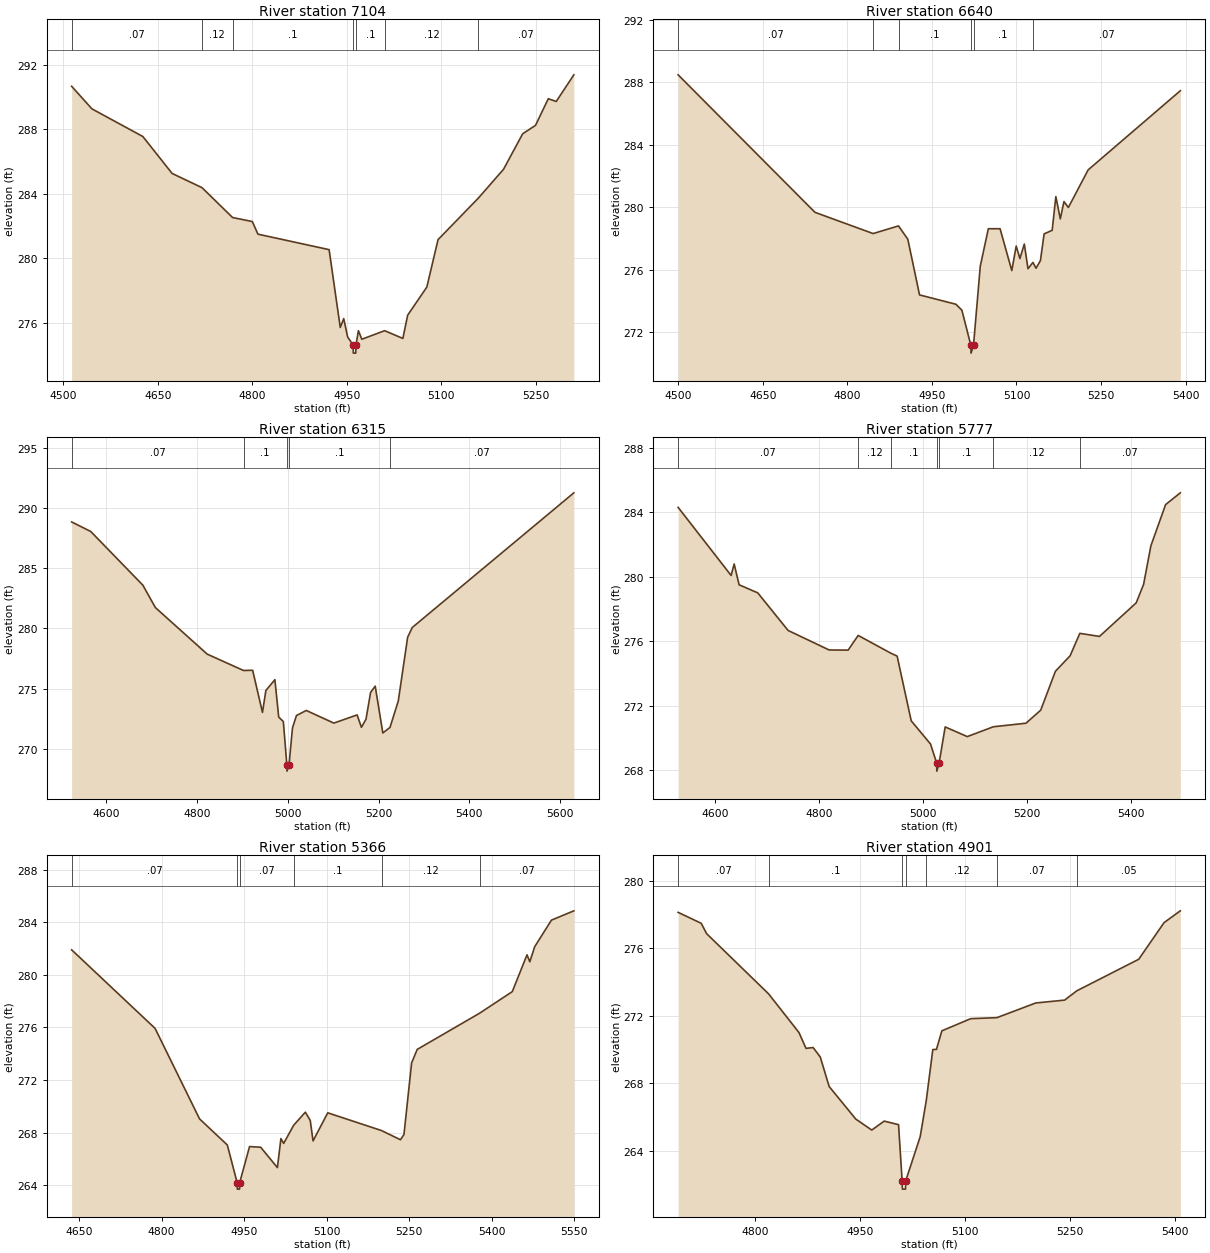
Type RM Length L Ch R = 1,7104,464,464,464
BEGIN DESCRIPTION:
Stream0605 15.0
END DESCRIPTION:
XS GIS Cut Line= 3
      2409575.04     13662975.02      2409125.00     13662775.00
      2408825.02     13662725.00
#Sta/Elev= 30
  4513.5  290.66  4545.7  289.26  4626.4  287.55  4672.9  285.26  4720.3  284.38
  4768.8  282.53  4800.1  282.28  4809.0  281.50  4921.9  280.54  4939.6  275.72
  4945.1  276.27  4951.3  275.13  4960.0  274.63  4960.3  274.13  4964.2  274.13
  4964.5  274.63  4968.4  275.52  4973.8  274.99  5010.0  275.52  5038.9  275.04
  5046.5  276.48  5076.9  278.22  5094.7  281.16  5158.8  283.74  5198.6  285.52
  5229.0  287.72  5249.3  288.24  5269.6  289.89  5282.2  289.72  5310.1  291.37
#Mann=7,-1,0
  4513.5    0.07       0  4720.3    0.12       0  4768.8     0.1       0
  4960.0    0.05       0  4964.5     0.1       0  5010.0    0.12       0
  5158.8    0.07       0
Bank Sta=4960,4964.5
Exp/Cntr=0.3,0.1

Type RM Length L Ch R = 1,6640,325,325,325
BEGIN DESCRIPTION:
Stream0605 14.0
END DESCRIPTION:
XS GIS Cut Line= 3
      2409674.98     13662674.98      2409275.00     13662375.00
      2408974.99     13662124.99
#Sta/Elev= 30
  4500.0  288.49  4742.7  279.68  4845.8  278.32  4890.8  278.81  4907.3  277.96
  4928.1  274.39  4992.7  273.79  5003.2  273.41  5019.1  271.16  5019.4  270.66
  5023.8  271.16  5035.8  276.23  5050.1  278.63  5070.9  278.63  5091.7  275.95
  5099.5  277.52  5106.1  276.72  5113.9  277.65  5120.4  276.07  5129.2  276.47
  5134.7  276.10  5142.5  276.59  5149.0  278.30  5163.3  278.53  5169.8  280.69
  5177.7  279.26  5184.2  280.37  5192.0  279.99  5227.1  282.40  5390.5  287.47
#Mann=6,-1,0
  4500.0    0.07       0  4845.8    0.12       0  4890.8     0.1       0
  5019.1    0.05       0  5023.8     0.1       0  5129.2    0.07       0
Bank Sta=5019.1,5023.8
Exp/Cntr=0.3,0.1

Type RM Length L Ch R = 1,6315,538,538,538
BEGIN DESCRIPTION:
XS7218
END DESCRIPTION:
XS GIS Cut Line= 4
      2409903.43     13662455.37      2409541.53     13662187.88
      2409297.66     13662148.55      2408898.22     13662054.56
#Sta/Elev= 30
  4523.2  288.84  4565.3  288.05  4680.2  283.59  4707.8  281.73  4822.1  277.86
  4902.2  276.50  4922.3  276.52  4944.0  273.02  4951.5  274.84  4971.4  275.74
  4979.8  272.63  4990.0  272.26  4997.8  268.64  4998.1  268.14  5002.5  268.64
  5010.2  271.74  5019.0  272.76  5040.6  273.18  5101.4  272.13  5152.7  272.81
  5162.2  271.78  5172.3  272.45  5182.4  274.68  5192.6  275.20  5209.4  271.31
  5225.2  271.77  5243.5  273.97  5264.1  279.26  5274.3  280.07  5630.6  291.26
#Mann=5,-1,0
  4523.2    0.07       0  4902.2     0.1       0  4997.8    0.05       0
  5002.5     0.1       0  5225.2    0.07       0
Bank Sta=4997.8,5002.5
Exp/Cntr=0.3,0.1

Type RM Length L Ch R = 1,5777,411,411,411
BEGIN DESCRIPTION:
Stream0605 13.0
END DESCRIPTION:
XS GIS Cut Line= 3
      2409925.01     13662325.02      2409675.00     13661925.00
      2409325.00     13661575.00
#Sta/Elev= 30
  4528.8  284.30  4630.8  280.08  4636.7  280.79  4646.2  279.50  4682.1  279.00
  4740.5  276.67  4819.5  275.46  4856.1  275.45  4875.4  276.36  4938.9  275.25
  4950.4  275.08  4977.5  271.07  5014.7  269.63  5026.5  268.45  5026.8  267.95
  5031.2  268.45  5042.9  270.69  5085.4  270.09  5135.7  270.70  5198.5  270.92
  5226.8  271.73  5255.1  274.14  5283.4  275.10  5302.1  276.49  5339.9  276.30
  5410.6  278.38  5424.8  279.52  5438.9  281.92  5467.2  284.47  5495.5  285.20
#Mann=7,-1,0
  4528.8    0.07       0  4875.4    0.12       0  4938.9     0.1       0
  5026.5    0.05       0  5031.2     0.1       0  5135.7    0.12       0
  5302.1    0.07       0
Bank Sta=5026.5,5031.2
Exp/Cntr=0.3,0.1

Type RM Length L Ch R = 1,5366,465,465,465
BEGIN DESCRIPTION:
Stream0605 12.0
END DESCRIPTION:
XS GIS Cut Line= 3
      2410275.03     13661675.00      2409925.00     13661625.00
      2409375.00     13661525.00
#Sta/Elev= 30
  4636.6  281.91  4788.2  275.93  4869.0  269.04  4919.5  267.05  4937.3  264.19
  4937.7  263.69  4941.7  263.69  4942.0  264.19  4959.9  266.93  4980.1  266.88
  5010.5  265.33  5016.9  267.54  5021.9  267.17  5040.0  268.55  5061.3  269.55
  5070.2  268.92  5075.3  267.36  5102.0  269.50  5199.7  268.15  5234.1  267.45
  5240.5  267.85  5254.4  273.30  5264.6  274.33  5377.8  277.08  5437.4  278.73
  5464.1  281.53  5469.2  281.00  5478.1  282.15  5508.5  284.17  5549.2  284.88
#Mann=6,-1,0
  4636.6    0.07       0  4937.3    0.05       0  4942.0    0.07       0
  5040.0     0.1       0  5199.7    0.12       0  5377.8    0.07       0
Bank Sta=4937.3,4942
Exp/Cntr=0.3,0.1

Type RM Length L Ch R = 1,4901,437,437,437
BEGIN DESCRIPTION:
Stream0605 11.0
END DESCRIPTION:
XS GIS Cut Line= 3
      2410275.02     13661275.00      2409975.00     13661225.00
      2409574.97     13661124.99
#Sta/Elev= 30
  4690.5  278.13  4723.5  277.48  4731.1  276.87  4819.6  273.30  4862.9  271.01
  4873.0  270.07  4883.1  270.12  4893.3  269.56  4906.0  267.81  4944.0  265.88
  4966.8  265.23  4984.5  265.76  5005.0  265.55  5010.1  262.23  5010.5  261.73
  5014.9  261.73  5015.3  262.23  5035.9  264.84  5044.6  266.99  5053.9  270.00
  5059.1  270.01  5066.8  271.11  5108.0  271.83  5145.3  271.89  5200.8  272.76
  5242.0  272.93  5259.3  273.48  5347.7  275.35  5383.8  277.52  5407.0  278.22
#Mann=7,-1,0
  4690.5    0.07       0  4819.6     0.1       0  5010.1    0.05       0
  5015.3     0.1       0  5044.6    0.12       0  5145.3    0.07       0
  5259.3    0.05       0
Bank Sta=5010.1,5015.3
Exp/Cntr=0.3,0.1

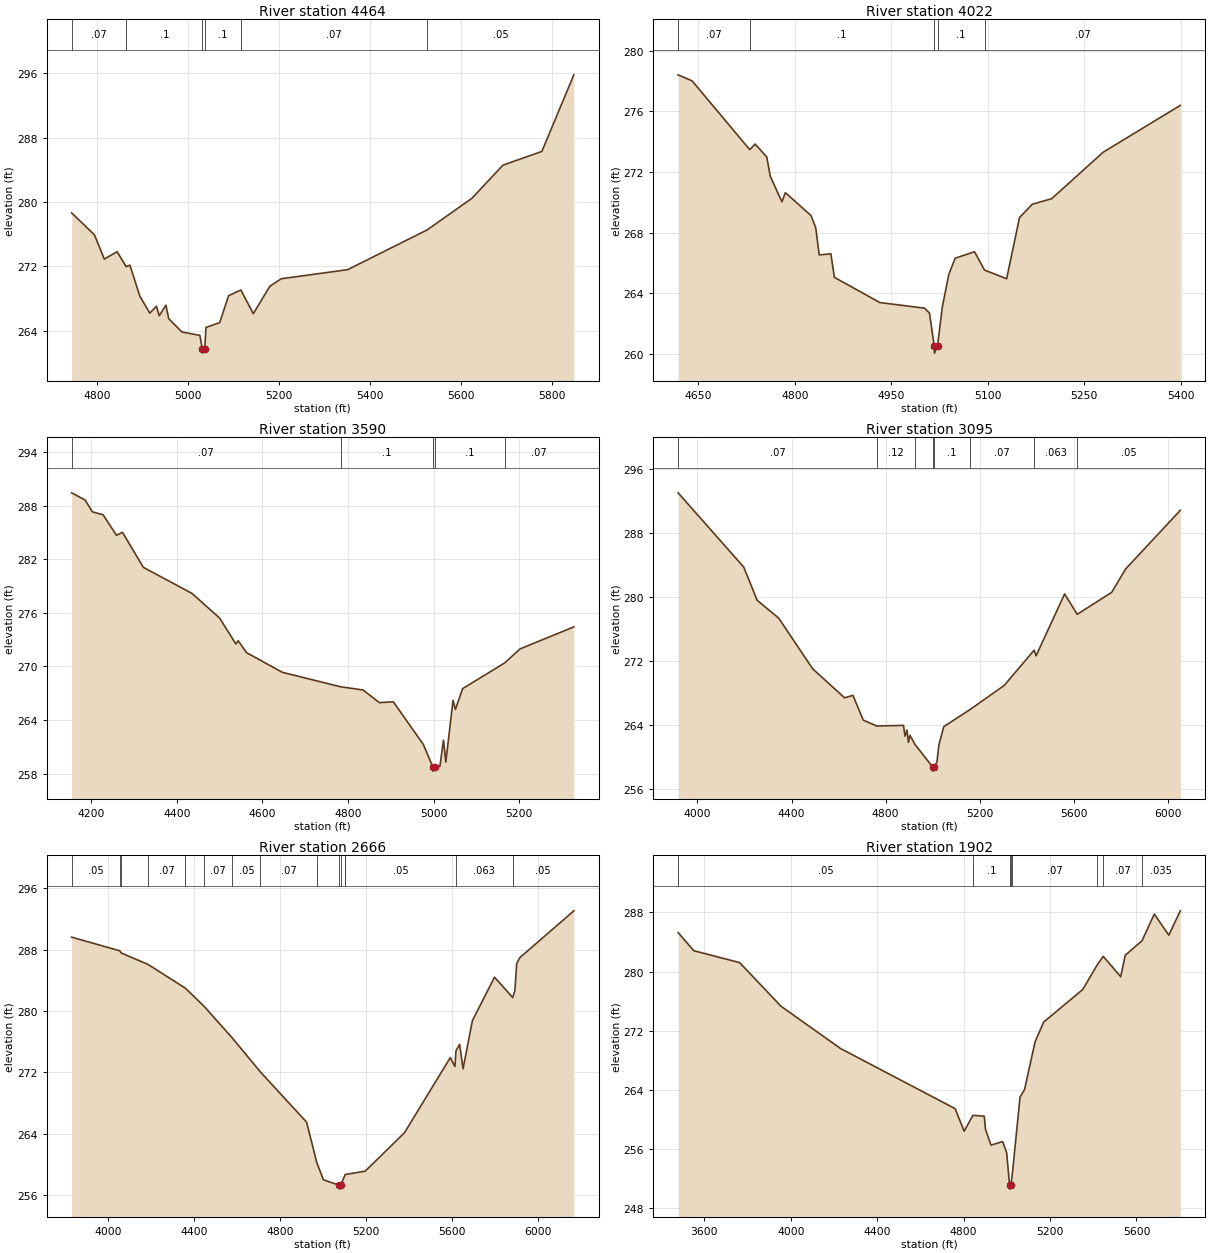
Type RM Length L Ch R = 1,4464,442,442,442
BEGIN DESCRIPTION:
Stream0605 10.0
END DESCRIPTION:
XS GIS Cut Line= 3
      2410324.97     13661174.98      2410125.00     13661025.00
      2409324.97     13660724.99
#Sta/Elev= 30
  4744.0  278.63  4794.0  275.92  4815.8  272.90  4844.0  273.81  4863.9  271.96
  4872.1  272.14  4894.0  268.29  4915.8  266.18  4930.4  267.03  4936.7  265.86
  4951.3  267.17  4957.5  265.49  4986.7  263.83  5026.0  263.42  5031.4  261.71
  5031.8  261.21  5036.6  261.71  5039.4  264.40  5069.6  265.00  5089.2  268.35
  5116.1  269.05  5143.5  266.11  5180.0  269.53  5204.9  270.45  5350.9  271.58
  5525.5  276.51  5624.1  280.44  5692.6  284.57  5778.1  286.27  5848.4  295.79
#Mann=6,-1,0
  4744.0    0.07       0  4863.9     0.1       0  5031.4    0.05       0
  5036.6     0.1       0  5116.1    0.07       0  5525.5    0.05       0
Bank Sta=5031.4,5036.6
Exp/Cntr=0.3,0.1

Type RM Length L Ch R = 1,4022,432,432,432
BEGIN DESCRIPTION:
Stream0605 9.0
END DESCRIPTION:
XS GIS Cut Line= 3
      2410425.00     13660825.00      2410075.00     13660675.00
      2409674.98     13660675.00
#Sta/Elev= 30
  4618.4  278.40  4640.2  278.00  4729.8  273.47  4738.1  273.84  4756.2  272.99
  4761.6  271.73  4779.8  270.03  4785.2  270.64  4825.1  269.13  4832.4  268.32
  4837.8  266.54  4855.9  266.61  4861.4  265.06  4932.1  263.40  5001.7  263.03
  5009.2  262.71  5016.5  260.57  5017.0  260.07  5021.8  260.57  5029.2  263.11
  5039.2  265.25  5049.2  266.32  5079.2  266.75  5094.8  265.54  5129.2  264.97
  5149.2  269.00  5169.2  269.88  5199.2  270.24  5279.2  273.30  5399.2  276.39
#Mann=5,-1,0
  4618.4    0.07       0  4729.8     0.1       0  5016.5    0.05       0
  5021.8     0.1       0  5094.8    0.07       0
Bank Sta=5016.5,5021.8
Exp/Cntr=0.3,0.1

Type RM Length L Ch R = 1,3590,495,495,495
BEGIN DESCRIPTION:
Stream0605 8.0
END DESCRIPTION:
XS GIS Cut Line= 3
      2410824.96     13660574.99      2410025.00     13660325.00
      2409725.02     13660474.99
#Sta/Elev= 30
  4154.1  289.45  4185.5  288.65  4202.8  287.31  4227.4  287.00  4258.8  284.70
  4273.0  285.02  4321.7  281.10  4435.4  278.18  4499.8  275.42  4538.0  272.51
  4543.3  272.88  4562.7  271.55  4646.5  269.34  4782.5  267.72  4835.1  267.36
  4873.3  265.94  4905.8  266.04  4976.0  261.25  4997.9  258.77  4998.3  258.27
  5003.2  258.77  5014.6  258.81  5023.0  261.74  5028.5  259.29  5045.3  266.21
  5050.9  265.18  5067.7  267.51  5165.6  270.38  5201.8  271.96  5327.6  274.43
#Mann=5,-1,0
  4154.1    0.07       0  4782.5     0.1       0  4997.9    0.05       0
  5003.2     0.1       0  5165.6    0.07       0
Bank Sta=4997.9,5003.2
Exp/Cntr=0.3,0.1

Type RM Length L Ch R = 1,3095,429,429,429
BEGIN DESCRIPTION:
XS7217
END DESCRIPTION:
XS GIS Cut Line= 2
      2410949.67     13660520.12      2409228.45     13659254.75
#Sta/Elev= 30
  3917.6  292.99  4196.5  283.74  4253.9  279.59  4345.7  277.36  4490.0  271.05
  4625.8  267.43  4661.3  267.74  4705.2  264.65  4762.1  263.92  4876.5  263.99
  4882.7  262.65  4891.2  263.40  4897.4  261.87  4903.9  262.75  4925.4  261.61
  5001.0  258.79  5001.5  258.29  5006.7  258.79  5018.5  259.41  5026.9  261.54
  5047.8  263.84  5158.1  265.94  5304.7  268.97  5432.0  273.37  5440.5  272.67
  5561.7  280.38  5615.3  277.84  5762.3  280.59  5820.9  283.48  6053.9  290.81
#Mann=8,-1,0
  3917.6    0.07       0  4762.1    0.12       0  4925.4     0.1       0
  5001.0    0.05       0  5006.7     0.1       0  5158.1    0.07       0
  5432.0   0.063       0  5615.3    0.05       0
Bank Sta=5001,5006.7
Exp/Cntr=0.3,0.1

Type RM Length L Ch R = 1,2666,764,764,764
BEGIN DESCRIPTION:
XS7216
END DESCRIPTION:
XS GIS Cut Line= 3
      2411201.39     13660354.91      2410241.67     13659458.12
      2409344.91     13658962.54
#Sta/Elev= 30
  3828.5  289.62  4051.9  287.85  4059.9  287.55  4183.1  286.09  4357.6  282.99
  4445.4  280.61  4576.5  276.49  4707.7  272.06  4922.4  265.53  4970.0  260.25
  5000.6  258.03  5075.4  257.31  5075.9  256.81  5081.1  257.31  5101.1  258.65
  5101.9  258.72  5194.9  259.14  5378.1  264.15  5591.2  273.93  5613.0  272.78
  5617.8  274.81  5634.8  275.67  5650.8  272.48  5694.3  278.75  5797.4  284.41
  5882.2  281.75  5892.3  282.70  5900.5  286.19  5915.1  286.95  6166.6  293.05
#Mann=15,-1,0
  3828.5    0.05       0  4051.9    0.07       0  4059.9    0.05       0
  4183.1    0.07       0  4357.6    0.05       0  4445.4    0.07       0
  4576.5    0.05       0  4707.7    0.07       0  4970.0    0.05       0
  5075.4    0.05       0  5081.1    0.05       0  5101.1    0.07       0
  5101.9    0.05       0  5617.8   0.063       0  5882.2    0.05       0
Bank Sta=5075.4,5081.1
Exp/Cntr=0.3,0.1

Type RM Length L Ch R = 1,1902,684,684,684
BEGIN DESCRIPTION:
XS7215
END DESCRIPTION:
XS GIS Cut Line= 3
      2411413.80     13659859.30      2410619.28     13659080.51
      2409448.58     13658766.23
#Sta/Elev= 30
  3478.3  285.27  3551.2  282.82  3763.3  281.21  3954.2  275.33  4230.1  269.61
  4760.9  261.48  4802.4  258.43  4842.8  260.58  4895.6  260.46  4901.1  258.70
  4926.6  256.56  4981.0  257.03  4999.1  255.54  5012.9  251.11  5013.4  250.61
  5018.8  251.11  5025.4  252.65  5061.2  263.06  5081.9  264.04  5130.7  270.51
  5170.7  273.19  5351.1  277.57  5417.8  280.87  5446.2  282.06  5527.2  279.31
  5547.9  282.20  5625.6  284.16  5682.5  287.77  5749.8  284.92  5803.0  288.21
#Mann=8,-1,0
  3478.3    0.05       0  4842.8     0.1       0  5012.9    0.05       0
  5018.8     0.1       0  5025.4    0.07       0  5417.8    0.05       0
  5446.2    0.07       0  5625.6   0.035       0
Bank Sta=5012.9,5018.8
Exp/Cntr=0.3,0.1

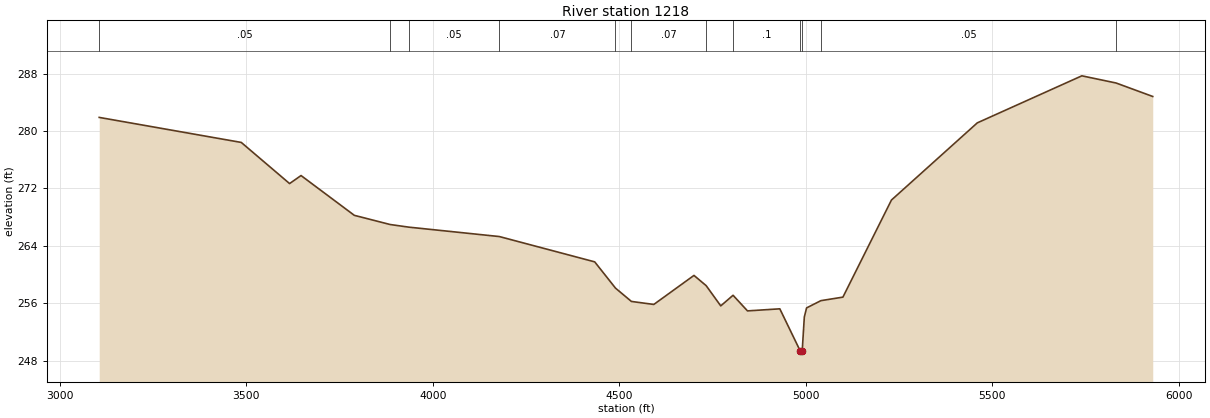
Type RM Length L Ch R = 1,1218,0,0,0
BEGIN DESCRIPTION:
XS7214
END DESCRIPTION:
XS GIS Cut Line= 4
      2411531.80     13659733.41      2411248.62     13658946.78
      2410328.21     13658317.44      2409455.05     13658356.77
#Sta/Elev= 30
  3105.3  281.91  3486.2  278.42  3615.8  272.68  3646.5  273.80  3789.4  268.25
  3885.4  266.97  3935.9  266.60  4178.3  265.29  4434.0  261.76  4489.7  258.10
  4532.4  256.24  4592.5  255.82  4700.2  259.87  4732.9  258.44  4772.0  255.62
  4805.0  257.10  4843.7  254.92  4930.4  255.21  4984.6  249.39  4985.1  248.89
  4990.5  249.39  4996.1  254.07  5002.2  255.34  5040.6  256.35  5099.6  256.84
  5229.7  270.38  5460.0  281.15  5740.3  287.71  5832.0  286.71  5930.4  284.83
#Mann=12,-1,0
  3105.3    0.05       0  3885.4    0.07       0  3935.9    0.05       0
  4178.3    0.07       0  4489.7    0.05       0  4532.4    0.07       0
  4732.9    0.05       0  4805.0     0.1       0  4984.6    0.05       0
  4990.5     0.1       0  5040.6    0.05       0  5832.0   0.035       0
Bank Sta=4984.6,4990.5
Exp/Cntr=0.3,0.1

Chan Stop Cuts=-1