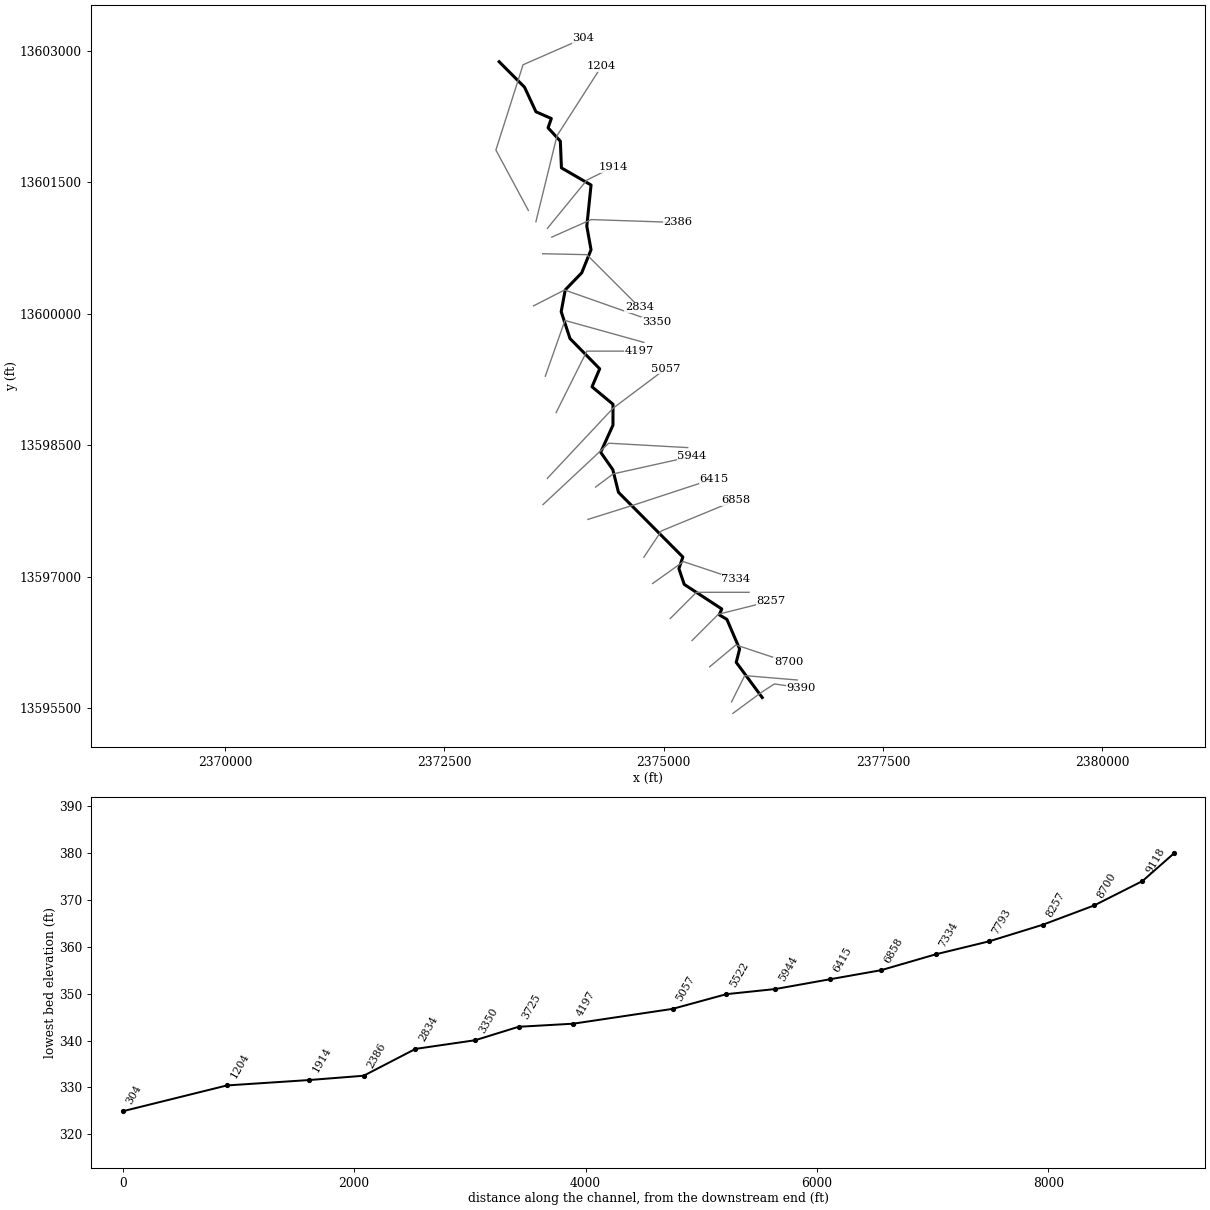
--- Stream0614.prj (project) ---

Proj Title=Stream0614 Base Level Engineering
Current Plan=p01
Default Exp/Contr=0.3,0.1
English Units
Geom File=g01
Flow File=f01
Plan File=p01
BEGIN DESCRIPTION:
Stream0614
END DESCRIPTION:

--- Stream0614.p01 (plan) ---

Plan Title=Multiple Run
Short Identifier=Multiple
Geom File=g01
Flow File=f01
Subcritical Flow
K Sum by GR= 0
Std Step Tol= 0.01
Critical Tol= 0.01
Num of Std Step Trials= 20
Max Error Tol= 0.3
Flow Tol Ratio= 0.001
Split Flow NTrial= 30
Split Flow Tol= 0.02
Split Flow Ratio= 0.02
Log Output Level= 0
Friction Slope Method= 1
Unsteady Friction Slope Method= 2
Unsteady Bridges Friction Slope Method= 1
Parabolic Critical Depth
Global Vel Dist=  1 , 1 , 1
Global Log Level= 0
CheckData=True
Encroach Param= -1, 0, 0, 0
BEGIN DESCRIPTION:
Multiple Run
END DESCRIPTION:

--- Stream0614.f01 (steady flow) ---

Flow Title=Multiple
Number of Profiles=7
Profile Names=10-year,25-year,50-year,1pct_min,100-year,1pct_plu,500-year
River Rch & RM= Stream0614,Reach-1,9390
     282     437     571     362     723    1443    1147
River Rch & RM= Stream0614,Reach-1,5057
     587     942    1260     816    1628    3247    2691
Boundary for River Rch & Prof#=Stream0614,Reach-1,1
Up Type=0
Dn Type=3
Dn Slope=0.005
Boundary for River Rch & Prof#=Stream0614,Reach-1,2
Up Type=0
Dn Type=3
Dn Slope=0.005
Boundary for River Rch & Prof#=Stream0614,Reach-1,3
Up Type=0
Dn Type=3
Dn Slope=0.005
Boundary for River Rch & Prof#=Stream0614,Reach-1,4
Up Type=0
Dn Type=3
Dn Slope=0.005
Boundary for River Rch & Prof#=Stream0614,Reach-1,5
Up Type=0
Dn Type=3
Dn Slope=0.005
Boundary for River Rch & Prof#=Stream0614,Reach-1,6
Up Type=0
Dn Type=3
Dn Slope=0.005
Boundary for River Rch & Prof#=Stream0614,Reach-1,7
Up Type=0
Dn Type=3
Dn Slope=0.005

--- Stream0614.g01 (geometry) ---

Geom Title=Existing Conditions

River Reach=Stream0614,Reach-1
Reach XY= 30
      2376125.00     13595625.00      2375828.47     13596026.50
      2375867.19     13596178.41      2375721.79     13596516.66
      2375634.23     13596568.07      2375663.75     13596635.04
      2375235.51     13596915.19      2375174.72     13597095.18
      2375219.91     13597227.30      2374485.51     13597965.19
      2374421.38     13598223.50      2374282.85     13598421.77
      2374422.98     13598730.83      2374423.23     13598969.45
      2374183.96     13599168.33      2374271.54     13599373.50
      2373932.81     13599718.79      2373832.53     13600024.99
      2373878.75     13600273.45      2374066.98     13600468.66
      2374172.74     13600730.94      2374124.60     13601000.00
      2374172.95     13601469.16      2373835.32     13601664.82
      2373822.94     13601969.15      2373682.82     13602121.59
      2373720.00     13602227.57      2373544.59     13602304.43
      2373414.48     13602584.79      2373125.00     13602875.00

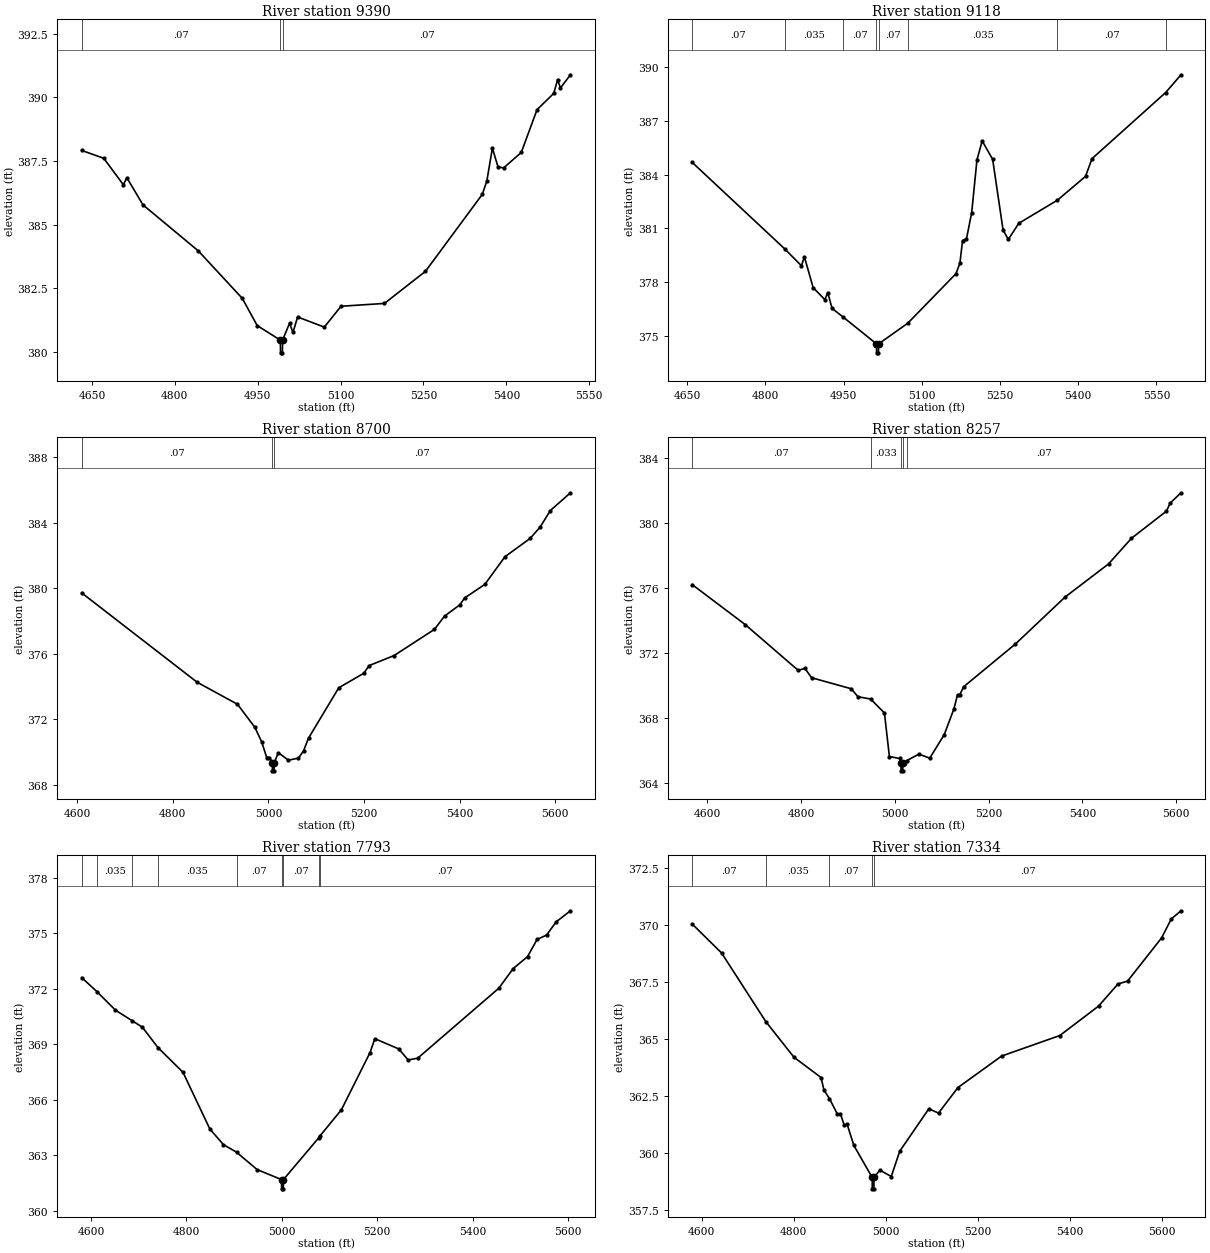
Type RM Length L Ch R = 1,9390,272,272,272
BEGIN DESCRIPTION:
XS7259
END DESCRIPTION:
XS GIS Cut Line= 4
      2375790.37     13595444.36      2376117.38     13595685.32
      2376263.69     13595779.99      2376564.87     13595736.96
#Sta/Elev= 30
  4631.3  387.91  4671.3  387.60  4706.8  386.56  4713.0  386.84  4742.3  385.77
  4842.6  383.96  4922.0  382.10  4949.0  381.03  4990.9  380.46  4991.2  379.96
  4994.7  379.96  4994.9  380.46  5007.6  381.12  5013.8  380.76  5022.1  381.37
  5070.4  380.97  5100.8  381.79  5179.3  381.90  5253.5  383.16  5356.3  386.18
  5364.6  386.70  5374.7  388.00  5384.8  387.27  5394.9  387.22  5427.0  387.83
  5455.5  389.51  5485.8  390.15  5492.7  390.69  5497.8  390.36  5516.0  390.88
#Mann=3,-1,0
  4631.3    0.07       0  4990.9    0.05       0  4994.9    0.07       0
Bank Sta=4990.9,4994.9
Exp/Cntr=0.3,0.1

Type RM Length L Ch R = 1,9118,418,418,418
BEGIN DESCRIPTION:
Stream0614 16.0
END DESCRIPTION:
XS GIS Cut Line= 3
      2375774.99     13595574.99      2375925.00     13595875.00
      2376525.00     13595825.00
#Sta/Elev= 30
  4659.6  384.68  4836.8  379.86  4869.2  378.91  4874.8  379.41  4891.6  377.69
  4914.0  377.02  4919.6  377.41  4927.9  376.53  4948.6  376.06  5013.1  374.55
  5013.3  374.05  5016.8  374.05  5017.1  374.55  5073.0  375.70  5165.6  378.47
  5173.1  379.06  5178.2  380.32  5185.7  380.41  5195.7  381.88  5205.8  384.82
  5215.8  385.88  5235.9  384.85  5255.9  380.90  5266.0  380.38  5286.0  381.28
  5360.1  382.57  5414.0  383.90  5426.5  384.89  5567.8  388.58  5597.1  389.57
#Mann=8,-1,0
  4659.6    0.07       0  4836.8   0.035       0  4948.6    0.07       0
  5013.1    0.05       0  5017.1    0.07       0  5073.0   0.035       0
  5360.1    0.07       0  5567.8   0.035       0
Bank Sta=5013.1,5017.1
Exp/Cntr=0.3,0.1

Type RM Length L Ch R = 1,8700,443,443,443
BEGIN DESCRIPTION:
Stream0614 15.0
END DESCRIPTION:
XS GIS Cut Line= 3
      2375525.00     13595975.00      2375825.00     13596225.00
      2376425.03     13596024.99
#Sta/Elev= 30
  4609.2  379.72  4850.7  374.26  4935.3  372.91  4971.7  371.50  4986.0  370.61
  4996.5  369.65  5002.3  369.65  5008.3  369.34  5008.5  368.84  5012.0  368.84
  5012.3  369.34  5020.8  369.95  5041.9  369.49  5063.0  369.62  5073.5  370.06
  5084.0  370.84  5147.3  373.92  5200.0  374.81  5210.5  375.27  5263.2  375.89
  5347.6  377.49  5368.6  378.30  5400.3  378.98  5410.8  379.41  5453.0  380.24
  5495.1  381.93  5547.8  383.05  5568.9  383.75  5590.0  384.75  5632.2  385.84
#Mann=3,-1,0
  4609.2    0.07       0  5008.3    0.05       0  5012.3    0.07       0
Bank Sta=5008.3,5012.3
Exp/Cntr=0.3,0.1

Type RM Length L Ch R = 1,8257,464,464,464
BEGIN DESCRIPTION:
Stream0614 14.0
END DESCRIPTION:
XS GIS Cut Line= 3
      2375325.00     13596275.00      2375625.00     13596575.00
      2376224.97     13596724.99
#Sta/Elev= 30
  4567.6  376.19  4680.7  373.73  4793.9  370.91  4808.0  371.04  4822.2  370.46
  4907.0  369.78  4921.2  369.29  4948.2  369.15  4977.7  368.29  4988.3  365.61
  5009.9  365.49  5013.1  365.23  5013.3  364.73  5016.8  364.73  5017.1  365.23
  5025.6  365.36  5051.1  365.76  5074.3  365.51  5105.2  366.95  5125.9  368.54
  5133.6  369.41  5138.7  369.42  5146.5  369.90  5257.3  372.54  5362.9  375.42
  5455.7  377.46  5504.7  379.04  5579.4  380.71  5587.1  381.20  5610.3  381.84
#Mann=5,-1,0
  4567.6    0.07       0  4948.2   0.033       0  5013.1   0.033       0
  5017.1   0.033       0  5025.6    0.07       0
Bank Sta=5013.1,5017.1
Exp/Cntr=0.3,0.1

Type RM Length L Ch R = 1,7793,459,459,459
BEGIN DESCRIPTION:
Stream0614 13.0
END DESCRIPTION:
XS GIS Cut Line= 3
      2375074.97     13596524.97      2375375.00     13596825.00
      2375974.99     13596825.00
#Sta/Elev= 30
  4580.5  372.60  4612.6  371.84  4651.3  370.84  4686.4  370.27  4707.8  369.92
  4740.4  368.82  4792.7  367.49  4849.2  364.42  4877.5  363.58  4905.0  363.17
  4948.2  362.23  4999.3  361.69  4999.5  361.19  5003.0  361.19  5003.3  361.69
  5077.1  363.94  5079.9  364.05  5124.8  365.46  5184.8  368.55  5194.8  369.30
  5244.8  368.75  5264.8  368.15  5284.8  368.25  5454.8  372.03  5484.8  373.09
  5514.8  373.73  5534.8  374.66  5554.8  374.90  5574.8  375.61  5604.8  376.21
#Mann=9,-1,0
  4580.5    0.07       0  4612.6   0.035       0  4686.4    0.07       0
  4740.4   0.035       0  4905.0    0.07       0  4999.3    0.05       0
  5003.3    0.07       0  5077.1   0.033       0  5079.9    0.07       0
Bank Sta=4999.3,5003.3
Exp/Cntr=0.3,0.1

Type RM Length L Ch R = 1,7334,476,476,476
BEGIN DESCRIPTION:
Stream0614 12.0
END DESCRIPTION:
XS GIS Cut Line= 3
      2374874.99     13596924.99      2375225.00     13597175.00
      2375825.01     13596975.00
#Sta/Elev= 30
  4579.0  370.04  4642.9  368.77  4739.1  365.76  4800.2  364.20  4859.2  363.31
  4865.4  362.76  4877.3  362.39  4894.8  361.70  4901.0  361.73  4909.6  361.22
  4915.7  361.27  4930.5  360.33  4970.3  358.93  4970.5  358.43  4974.0  358.43
  4974.3  358.93  4987.0  359.25  5011.8  358.97  5030.2  360.08  5093.5  361.94
  5114.5  361.75  5156.7  362.87  5251.6  364.25  5378.1  365.15  5462.4  366.44
  5504.6  367.41  5525.6  367.54  5599.4  369.43  5620.5  370.26  5641.6  370.62
#Mann=5,-1,0
  4579.0    0.07       0  4739.1   0.035       0  4877.3    0.07       0
  4970.3    0.05       0  4974.3    0.07       0
Bank Sta=4970.3,4974.3
Exp/Cntr=0.3,0.1

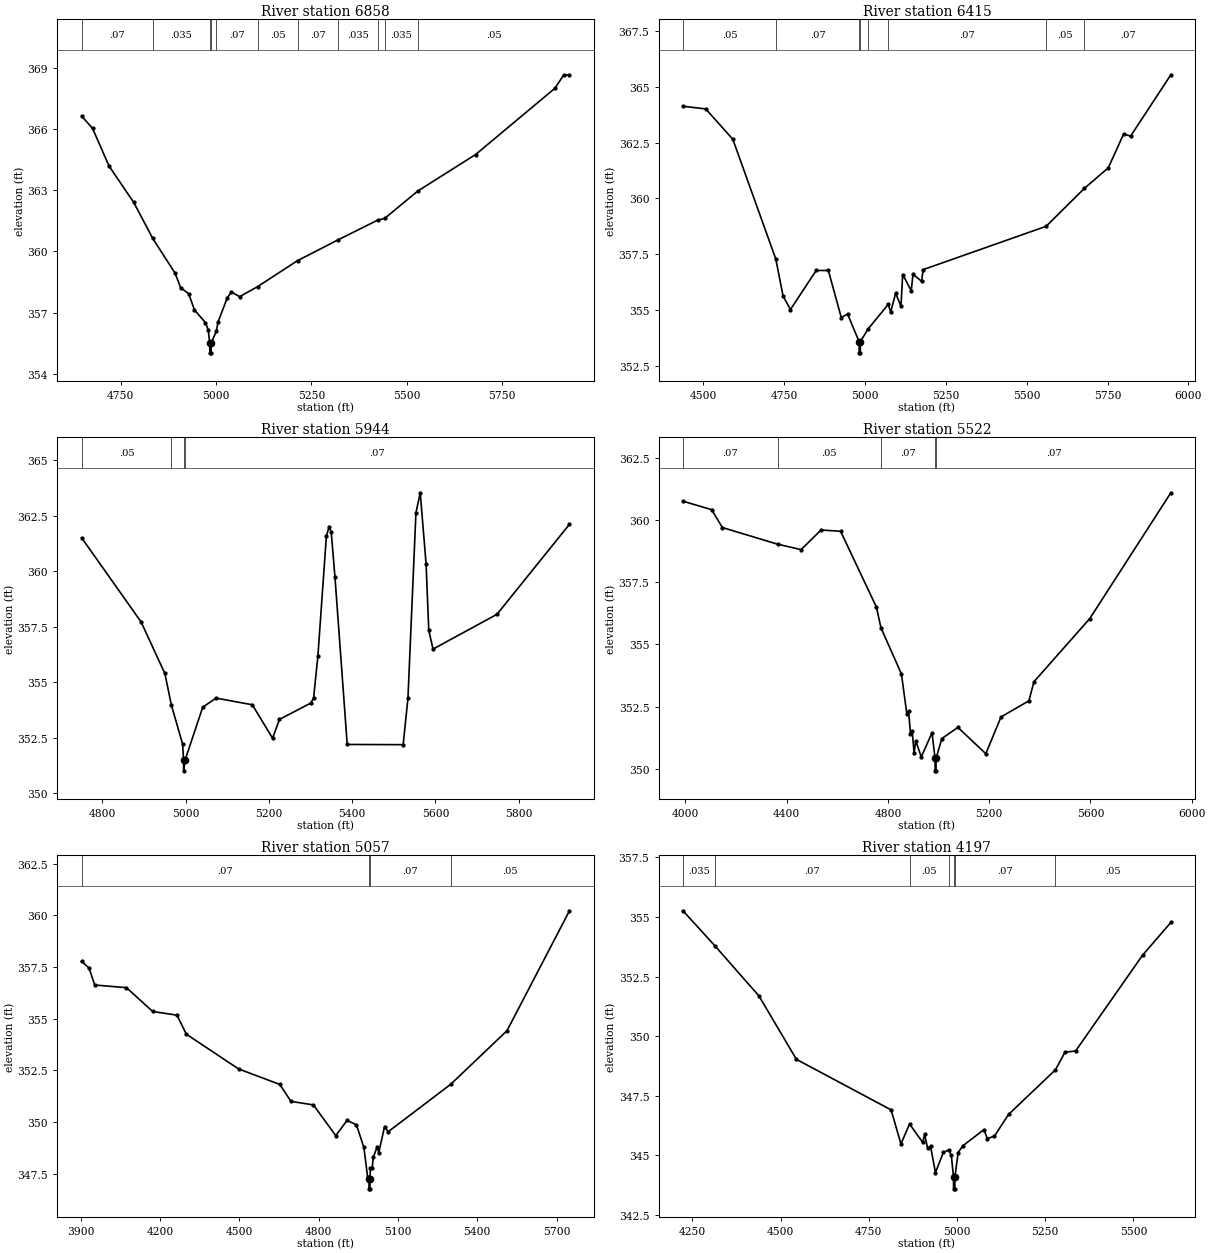
Type RM Length L Ch R = 1,6858,443,443,443
BEGIN DESCRIPTION:
Stream0614 11.0
END DESCRIPTION:
XS GIS Cut Line= 3
      2374774.99     13597224.99      2374975.00     13597525.00
      2375824.99     13597875.00
#Sta/Elev= 30
  4647.4  366.65  4676.0  366.05  4719.5  364.19  4784.1  362.41  4834.0  360.64
  4892.3  358.94  4907.3  358.22  4928.3  357.92  4943.4  357.13  4971.9  356.51
  4979.4  356.16  4983.4  355.52  4983.7  355.02  4987.2  355.02  4987.4  355.52
  5001.0  356.08  5005.0  356.52  5029.6  357.73  5040.4  358.01  5062.0  357.78
  5108.8  358.27  5213.9  359.55  5319.0  360.56  5424.2  361.54  5442.2  361.62
  5529.3  362.97  5680.8  364.76  5888.6  368.01  5912.5  368.68  5927.2  368.66
#Mann=11,-1,0
  4647.4    0.07       0  4834.0   0.035       0  4983.4   0.035       0
  4987.4   0.035       0  5001.0    0.07       0  5108.8    0.05       0
  5213.9    0.07       0  5319.0   0.035       0  5424.2    0.07       0
  5442.2   0.035       0  5529.3    0.05       0
Bank Sta=4983.4,4987.4
Exp/Cntr=0.3,0.1

Type RM Length L Ch R = 1,6415,471,471,471
BEGIN DESCRIPTION:
Stream0614 10.0
END DESCRIPTION:
XS GIS Cut Line= 3
      2374137.96     13597656.19      2374675.00     13597825.00
      2375573.74     13598120.44
#Sta/Elev= 30
  4436.8  364.13  4507.1  364.01  4590.9  362.65  4723.9  357.28  4746.3  355.63
  4769.1  355.02  4848.7  356.77  4886.4  356.77  4926.4  354.66  4945.9  354.82
  4981.5  353.58  4981.8  353.08  4985.3  353.08  4985.5  353.58  5008.8  354.14
  5071.5  355.25  5079.2  354.91  5094.5  355.75  5111.0  355.17  5116.3  356.59
  5142.8  355.86  5148.1  356.60  5174.6  356.29  5179.9  356.81  5560.0  358.75
  5678.3  360.45  5752.3  361.37  5799.8  362.89  5821.2  362.79  5945.8  365.54
#Mann=8,-1,0
  4436.8    0.05       0  4723.9    0.07       0  4981.5    0.05       0
  4985.5    0.07       0  5008.8   0.035       0  5071.5    0.07       0
  5560.0    0.05       0  5678.3    0.07       0
Bank Sta=4981.5,4985.5
Exp/Cntr=0.3,0.1

Type RM Length L Ch R = 1,5944,422,422,422
BEGIN DESCRIPTION:
Stream0614 9.0
END DESCRIPTION:
XS GIS Cut Line= 3
      2374225.03     13598025.02      2374425.00     13598175.00
      2375324.98     13598375.00
#Sta/Elev= 30
  4750.0  361.51  4892.7  357.72  4950.0  355.39  4965.4  353.98  4992.7  352.20
  4994.8  351.50  4995.1  351.00  4998.8  351.50  5040.9  353.87  5072.9  354.28
  5160.0  353.98  5208.7  352.47  5225.3  353.32  5300.9  354.06  5307.3  354.30
  5317.5  356.16  5338.0  361.59  5344.4  362.00  5349.5  361.78  5358.5  359.76
  5388.0  352.19  5522.4  352.18  5533.9  354.28  5553.1  362.64  5563.4  363.54
  5577.5  360.32  5583.9  357.34  5594.1  356.49  5747.8  358.06  5921.9  362.12
#Mann=4,-1,0
  4750.0    0.05       0  4965.4    0.07       0  4994.8    0.05       0
  4998.8    0.07       0
Bank Sta=4994.8,4998.8
Exp/Cntr=0.3,0.1

Type RM Length L Ch R = 1,5522,465,465,465
BEGIN DESCRIPTION:
Stream0614 8.0
END DESCRIPTION:
XS GIS Cut Line= 3
      2373624.99     13597824.99      2374375.00     13598525.00
      2375274.99     13598475.00
#Sta/Elev= 30
  3990.5  360.77  4103.6  360.43  4146.1  359.71  4363.9  359.04  4457.3  358.82
  4535.5  359.61  4613.1  359.56  4754.8  356.50  4772.3  355.68  4853.5  353.81
  4875.0  352.19  4881.8  352.32  4889.2  351.40  4896.0  351.53  4903.3  350.63
  4910.2  351.12  4931.7  350.47  4974.2  351.44  4986.3  350.41  4986.6  349.91
  4990.1  349.91  4990.3  350.41  5013.0  351.21  5076.5  351.66  5186.7  350.60
  5246.8  352.08  5356.9  352.73  5377.0  353.50  5597.3  356.04  5917.8  361.11
#Mann=5,-1,0
  3990.5    0.07       0  4363.9    0.05       0  4772.3    0.07       0
  4986.3    0.05       0  4990.3    0.07       0
Bank Sta=4986.3,4990.3
Exp/Cntr=0.3,0.1

Type RM Length L Ch R = 1,5057,860,860,860
BEGIN DESCRIPTION:
Stream0614 7.0
END DESCRIPTION:
XS GIS Cut Line= 3
      2373674.98     13598124.98      2374425.00     13598925.00
      2375024.98     13599374.99
#Sta/Elev= 30
  3902.5  357.77  3930.6  357.45  3952.1  356.63  4072.3  356.50  4171.4  355.35
  4263.3  355.17  4298.9  354.25  4496.7  352.57  4652.6  351.82  4695.0  351.00
  4779.8  350.83  4864.6  349.34  4907.1  350.08  4942.7  349.87  4971.0  348.77
  4985.2  347.32  4990.0  347.27  4990.3  346.77  4993.8  346.77  4994.0  347.27
  4995.7  347.76  5002.2  347.76  5006.4  348.29  5021.0  348.80  5027.2  348.52
  5049.1  349.78  5062.7  349.53  5299.9  351.83  5512.7  354.42  5749.1  360.22
#Mann=4,-1,0
  3902.5    0.07       0  4990.0    0.05       0  4994.0    0.07       0
  5299.9    0.05       0
Bank Sta=4990,4994
Exp/Cntr=0.3,0.1

Type RM Length L Ch R = 1,4197,472,472,472
BEGIN DESCRIPTION:
Stream0614 6.0
END DESCRIPTION:
XS GIS Cut Line= 3
      2373775.00     13598875.01      2374125.00     13599575.00
      2374724.98     13599575.00
#Sta/Elev= 30
  4223.3  355.26  4313.2  353.80  4438.5  351.69  4544.7  349.03  4813.1  346.91
  4841.0  345.48  4865.3  346.32  4902.5  345.55  4908.1  345.88  4916.5  345.30
  4924.9  345.38  4938.8  344.28  4961.2  345.13  4976.7  345.23  4983.6  345.02
  4989.9  344.10  4990.2  343.60  4993.7  343.60  4993.9  344.10  5003.1  345.12
  5015.9  345.40  5075.9  346.08  5085.9  345.71  5105.9  345.81  5145.9  346.72
  5278.8  348.59  5305.9  349.33  5335.9  349.38  5525.9  353.40  5605.9  354.77
#Mann=7,-1,0
  4223.3   0.035       0  4313.2    0.07       0  4865.3    0.05       0
  4976.7    0.07       0  4989.9    0.05       0  4993.9    0.07       0
  5278.8    0.05       0
Bank Sta=4989.9,4993.9
Exp/Cntr=0.3,0.1

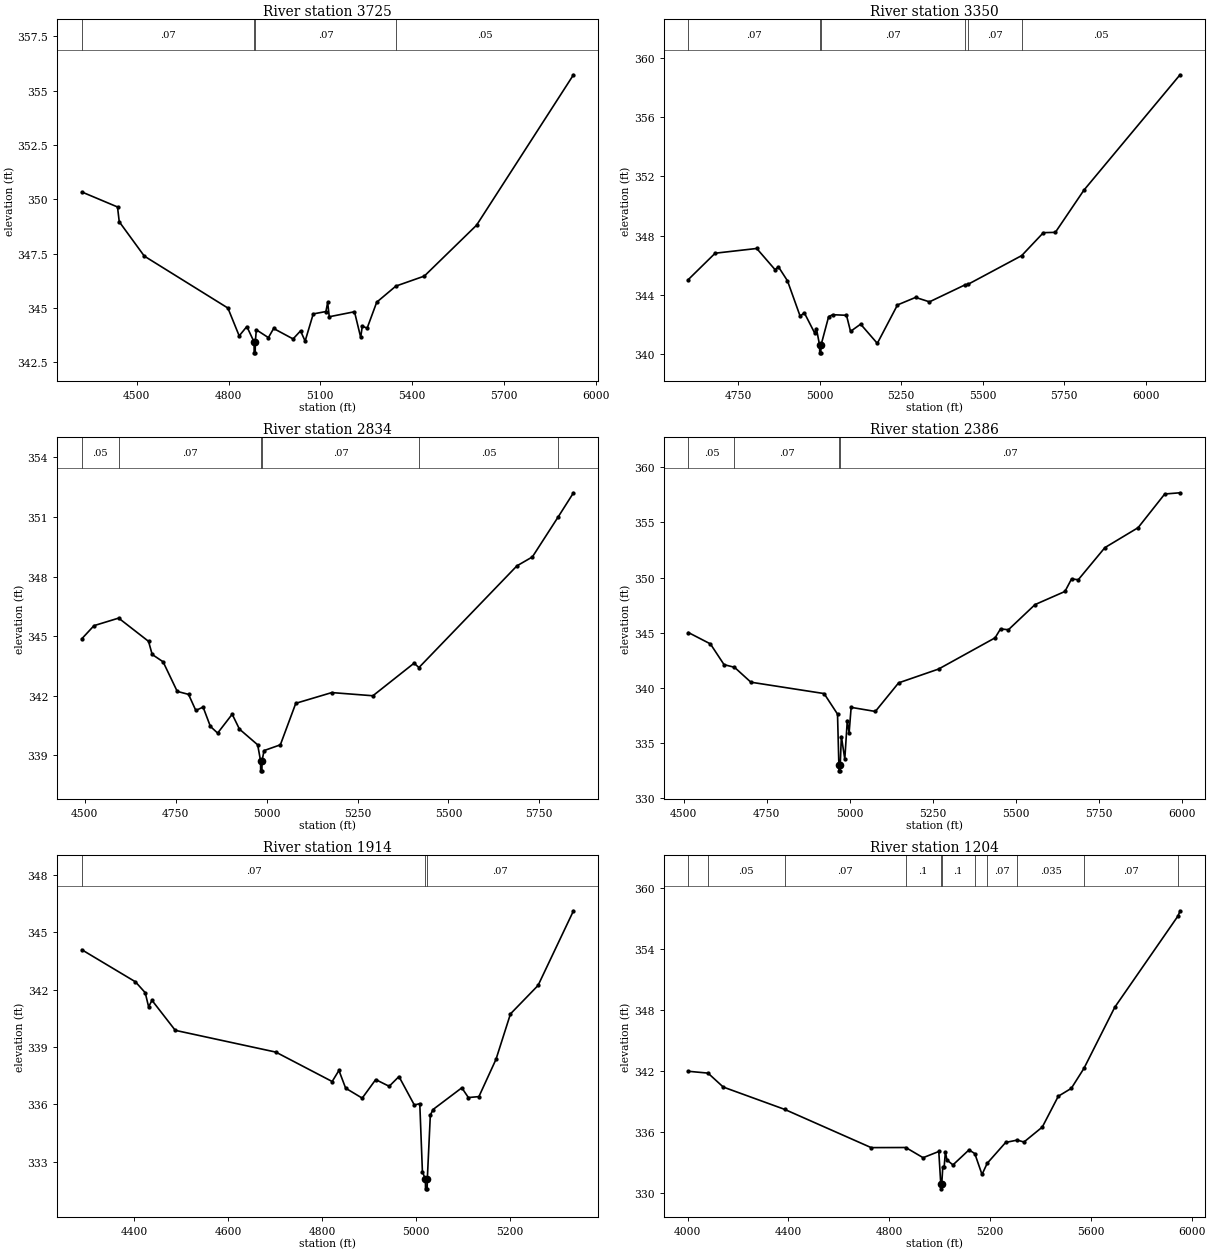
Type RM Length L Ch R = 1,3725,375,375,375
BEGIN DESCRIPTION:
Stream0614 5.0
END DESCRIPTION:
XS GIS Cut Line= 3
      2373651.44     13599289.52      2373875.00     13599925.00
      2374774.96     13599675.01
#Sta/Elev= 30
  4320.3  350.34  4437.0  349.65  4442.7  348.97  4524.6  347.39  4798.0  345.00
  4834.9  343.72  4859.9  344.15  4883.6  343.44  4883.8  342.94  4887.3  342.94
  4887.6  343.44  4890.9  344.00  4930.4  343.64  4947.5  344.06  5011.1  343.58
  5035.5  343.95  5050.5  343.48  5077.0  344.73  5118.5  344.84  5124.2  345.26
  5129.4  344.60  5211.9  344.83  5232.2  343.65  5237.3  344.16  5253.4  344.08
  5284.6  345.27  5347.2  346.01  5440.2  346.47  5611.0  348.81  5928.0  355.73
#Mann=4,-1,0
  4320.3    0.07       0  4883.6    0.05       0  4887.6    0.07       0
  5347.2    0.05       0
Bank Sta=4883.6,4887.6
Exp/Cntr=0.3,0.1

Type RM Length L Ch R = 1,3350,516,516,516
BEGIN DESCRIPTION:
XS7260
END DESCRIPTION:
XS GIS Cut Line= 3
      2373518.22     13600091.75      2373871.12     13600272.51
      2374920.55     13599902.63
#Sta/Elev= 30
  4596.6  345.03  4678.9  346.81  4806.5  347.13  4862.6  345.70  4873.1  345.89
  4900.9  344.94  4939.7  342.55  4952.5  342.78  4984.1  341.42  4989.7  341.71
  4999.6  340.57  4999.8  340.07  5003.3  340.07  5003.6  340.57  5027.2  342.52
  5039.6  342.65  5082.0  342.61  5094.4  341.52  5125.4  342.01  5176.6  340.71
  5238.5  343.31  5294.1  343.82  5336.7  343.52  5445.0  344.66  5456.3  344.72
  5619.9  346.65  5686.4  348.20  5723.1  348.22  5810.6  351.07  6105.8  358.88
#Mann=6,-1,0
  4596.6    0.07       0  4999.6    0.05       0  5003.6    0.07       0
  5445.0    0.05       0  5456.3    0.07       0  5619.9    0.05       0
Bank Sta=4999.6,5003.6
Exp/Cntr=0.3,0.1

Type RM Length L Ch R = 1,2834,448,448,448
BEGIN DESCRIPTION:
Stream0614 4.0
END DESCRIPTION:
XS GIS Cut Line= 3
      2373621.55     13600685.61      2374125.00     13600675.00
      2374725.01     13600074.99
#Sta/Elev= 30
  4491.8  344.87  4525.3  345.53  4593.1  345.91  4675.3  344.74  4685.3  344.08
  4715.3  343.71  4754.2  342.22  4785.3  342.07  4805.3  341.26  4825.3  341.43
  4845.3  340.46  4865.3  340.12  4905.3  341.07  4925.3  340.32  4975.4  339.53
  4983.4  338.72  4983.6  338.22  4987.1  338.22  4987.4  338.72  4992.9  339.24
  5037.8  339.53  5080.2  341.62  5179.2  342.16  5292.3  342.00  5405.5  343.64
  5418.9  343.42  5688.3  348.54  5730.8  348.99  5802.3  351.02  5843.9  352.22
#Mann=6,-1,0
  4491.8    0.05       0  4593.1    0.07       0  4983.4    0.05       0
  4987.4    0.07       0  5418.9    0.05       0  5802.3    0.07       0
Bank Sta=4983.4,4987.4
Exp/Cntr=0.3,0.1

Type RM Length L Ch R = 1,2386,472,472,472
BEGIN DESCRIPTION:
Stream0614 3.0
END DESCRIPTION:
XS GIS Cut Line= 3
      2373724.99     13600875.00      2374175.00     13601075.00
      2375161.00     13601041.95
#Sta/Elev= 30
  4514.1  345.02  4580.4  343.99  4621.5  342.11  4652.9  341.87  4702.2  340.52
  4922.4  339.49  4962.8  337.63  4966.9  332.99  4967.2  332.49  4970.7  332.49
  4970.9  332.99  4974.4  335.60  4984.7  333.55  4992.2  337.05  4997.7  335.93
  5003.8  338.24  5076.6  337.87  5146.6  340.46  5266.7  341.71  5436.8  344.54
  5453.1  345.35  5476.8  345.27  5556.9  347.55  5646.9  348.74  5666.9  349.88
  5686.9  349.80  5767.0  352.71  5867.0  354.52  5947.1  357.57  5993.1  357.68
#Mann=4,-1,0
  4514.1    0.05       0  4652.9    0.07       0  4966.9    0.05       0
  4970.9    0.07       0
Bank Sta=4966.9,4970.9
Exp/Cntr=0.3,0.1

Type RM Length L Ch R = 1,1914,710,710,710
BEGIN DESCRIPTION:
Stream0614 2.0
END DESCRIPTION:
XS GIS Cut Line= 3
      2373675.01     13600975.01      2374125.00     13601525.00
      2374424.98     13601674.99
#Sta/Elev= 30
  4288.9  344.09  4403.0  342.41  4423.8  341.84  4431.0  341.10  4438.2  341.44
  4487.7  339.87  4701.6  338.73  4821.5  337.19  4835.9  337.77  4850.2  336.84
  4885.4  336.32  4914.1  337.29  4942.8  336.94  4963.6  337.45  4996.3  335.96
  5007.9  336.03  5013.5  332.46  5019.9  332.07  5020.1  331.57  5023.6  331.57
  5023.9  332.07  5030.3  335.42  5035.9  335.72  5097.3  336.86  5111.3  336.35
  5133.7  336.40  5170.0  338.35  5200.8  340.73  5259.5  342.22  5334.9  346.13
#Mann=3,-1,0
  4288.9    0.07       0  5019.9    0.05       0  5023.9    0.07       0
Bank Sta=5019.9,5023.9
Exp/Cntr=0.3,0.1

Type RM Length L Ch R = 1,1204,900,900,900
BEGIN DESCRIPTION:
Stream0614 1.0
END DESCRIPTION:
XS GIS Cut Line= 3
      2373544.08     13601050.49      2373785.06     13602031.65
      2374292.82     13602823.40
#Sta/Elev= 30
  4003.1  341.97  4081.1  341.79  4141.6  340.42  4384.9  338.23  4728.5  334.47
  4865.9  334.48  4934.5  333.48  4996.8  334.09  5004.6  330.92  5004.8  330.42
  5008.6  330.92  5012.6  332.55  5018.0  332.55  5023.0  334.03  5029.3  333.25
  5053.0  332.77  5116.8  334.25  5139.7  333.88  5168.3  331.83  5188.9  332.93
  5262.2  334.98  5308.1  335.21  5334.8  335.02  5407.5  336.49  5471.0  339.52
  5522.5  340.29  5572.6  342.25  5695.0  348.26  5946.5  357.25  5954.0  357.74
#Mann=11,-1,0
  4003.1    0.07       0  4081.1    0.05       0  4384.9    0.07       0
  4865.9     0.1       0  5004.6    0.05       0  5008.6     0.1       0
  5139.7   0.035       0  5188.9    0.07       0  5308.1   0.035       0
  5572.6    0.07       0  5946.5   0.035       0
Bank Sta=5004.6,5008.6
Exp/Cntr=0.3,0.1

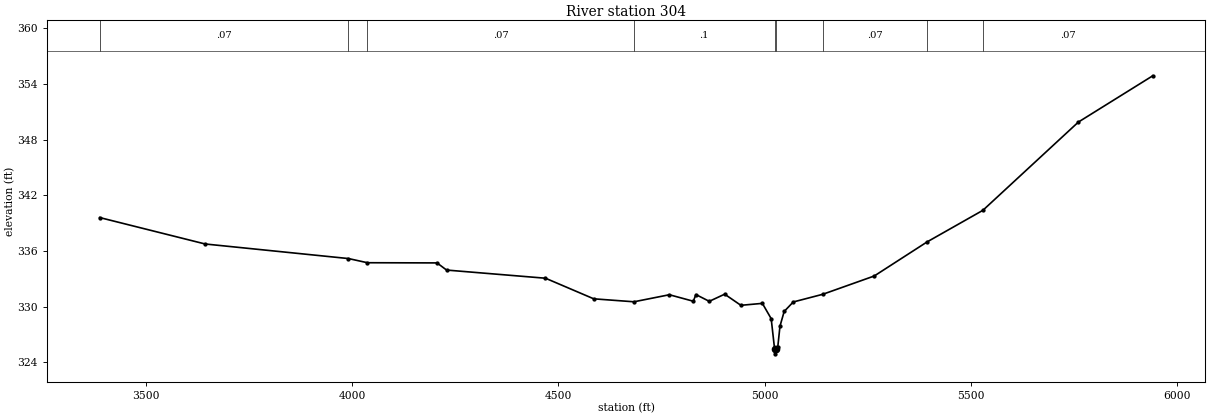
Type RM Length L Ch R = 1,304,0,0,0
BEGIN DESCRIPTION:
XS7261
END DESCRIPTION:
XS GIS Cut Line= 4
      2373458.01     13601179.63      2373087.95     13601868.12
      2373397.78     13602840.64      2374086.24     13603141.85
#Sta/Elev= 30
  3387.4  339.60  3643.3  336.75  3990.8  335.18  4036.8  334.73  4205.6  334.71
  4228.7  333.94  4468.6  333.06  4585.6  330.84  4683.1  330.52  4769.0  331.28
  4827.0  330.58  4833.4  331.30  4865.7  330.57  4903.1  331.34  4942.4  330.14
  4994.5  330.35  5015.9  328.70  5024.2  325.41  5024.5  324.91  5028.5  325.41
  5032.0  325.70  5037.2  327.89  5047.4  329.48  5069.4  330.50  5141.1  331.33
  5265.8  333.30  5394.2  336.98  5529.3  340.38  5760.8  349.89  5941.2  354.88
#Mann=9,-1,0
  3387.4    0.07       0  3990.8    0.05       0  4036.8    0.07       0
  4683.1     0.1       0  5024.2    0.05       0  5028.5     0.1       0
  5141.1    0.07       0  5394.2   0.035       0  5529.3    0.07       0
Bank Sta=5024.2,5028.5
Exp/Cntr=0.3,0.1

Chan Stop Cuts=-1