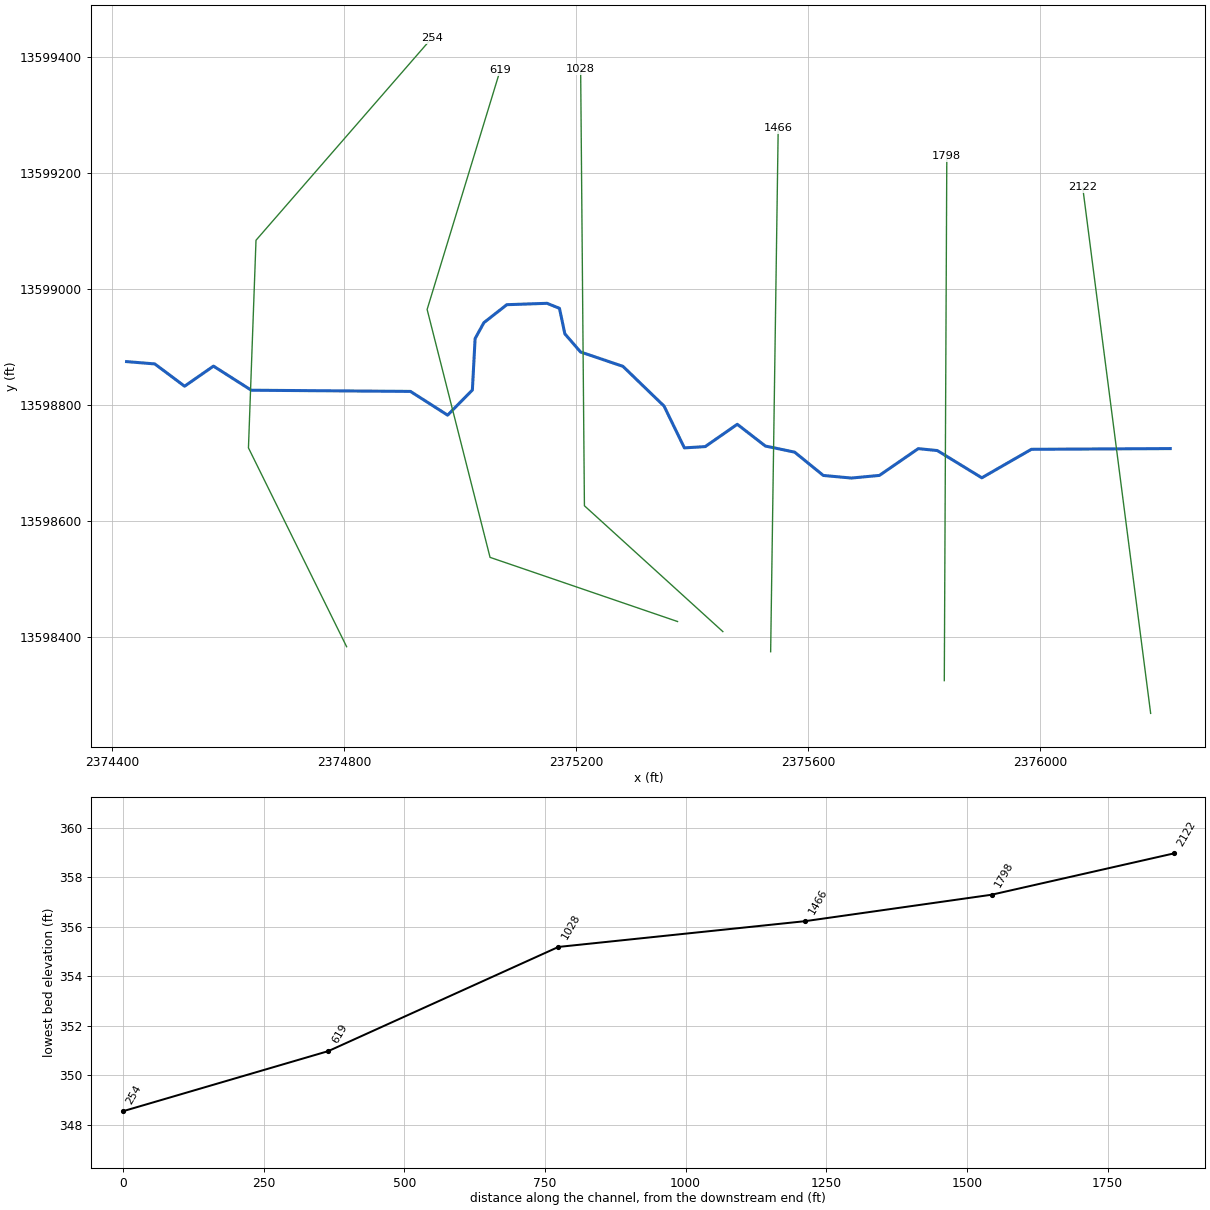
--- Stream0615.prj (project) ---

Proj Title=Stream0615 Base Level Engineering
Current Plan=p01
Default Exp/Contr=0.3,0.1
English Units
Geom File=g01
Flow File=f01
Plan File=p01
BEGIN DESCRIPTION:
Stream0615
END DESCRIPTION:

--- Stream0615.p01 (plan) ---

Plan Title=Multiple Run
Short Identifier=Multiple
Geom File=g01
Flow File=f01
Subcritical Flow
K Sum by GR= 0
Std Step Tol= 0.01
Critical Tol= 0.01
Num of Std Step Trials= 20
Max Error Tol= 0.3
Flow Tol Ratio= 0.001
Split Flow NTrial= 30
Split Flow Tol= 0.02
Split Flow Ratio= 0.02
Log Output Level= 0
Friction Slope Method= 1
Unsteady Friction Slope Method= 2
Unsteady Bridges Friction Slope Method= 1
Parabolic Critical Depth
Global Vel Dist=  1 , 1 , 1
Global Log Level= 0
CheckData=True
Encroach Param= -1, 0, 0, 0
BEGIN DESCRIPTION:
Multiple Run
END DESCRIPTION:

--- Stream0615.f01 (steady flow) ---

Flow Title=Multiple
Number of Profiles=7
Profile Names=10-year,25-year,50-year,1pct_min,100-year,1pct_plu,500-year
River Rch & RM= Stream0615,Reach-1,2122
     178     265     339     210     420     838     637
Boundary for River Rch & Prof#=Stream0615,Reach-1,1
Up Type=0
Dn Type=3
Dn Slope=0.005
Boundary for River Rch & Prof#=Stream0615,Reach-1,2
Up Type=0
Dn Type=3
Dn Slope=0.005
Boundary for River Rch & Prof#=Stream0615,Reach-1,3
Up Type=0
Dn Type=3
Dn Slope=0.005
Boundary for River Rch & Prof#=Stream0615,Reach-1,4
Up Type=0
Dn Type=3
Dn Slope=0.005
Boundary for River Rch & Prof#=Stream0615,Reach-1,5
Up Type=0
Dn Type=3
Dn Slope=0.005
Boundary for River Rch & Prof#=Stream0615,Reach-1,6
Up Type=0
Dn Type=3
Dn Slope=0.005
Boundary for River Rch & Prof#=Stream0615,Reach-1,7
Up Type=0
Dn Type=3
Dn Slope=0.005

--- Stream0615.g01 (geometry) ---

Geom Title=Existing Conditions

River Reach=Stream0615,Reach-1
Reach XY= 30
      2376225.00     13598725.00      2375985.50     13598723.76
      2375900.00     13598674.61      2375823.28     13598721.60
      2375790.40     13598724.90      2375723.42     13598678.74
      2375675.00     13598674.18      2375626.58     13598678.68
      2375577.17     13598718.90      2375526.64     13598729.42
      2375478.28     13598766.92      2375422.99     13598728.43
      2375387.03     13598726.22      2375351.95     13598798.34
      2375281.05     13598866.84      2375207.99     13598891.59
      2375180.91     13598922.87      2375171.57     13598966.92
      2375150.11     13598975.54      2375080.78     13598973.16
      2375041.28     13598942.23      2375026.10     13598914.68
      2375021.39     13598826.02      2374978.70     13598782.68
      2374914.57     13598823.61      2374640.16     13598825.65
      2374574.90     13598867.23      2374525.06     13598832.57
      2374473.64     13598871.02      2374425.00     13598875.00

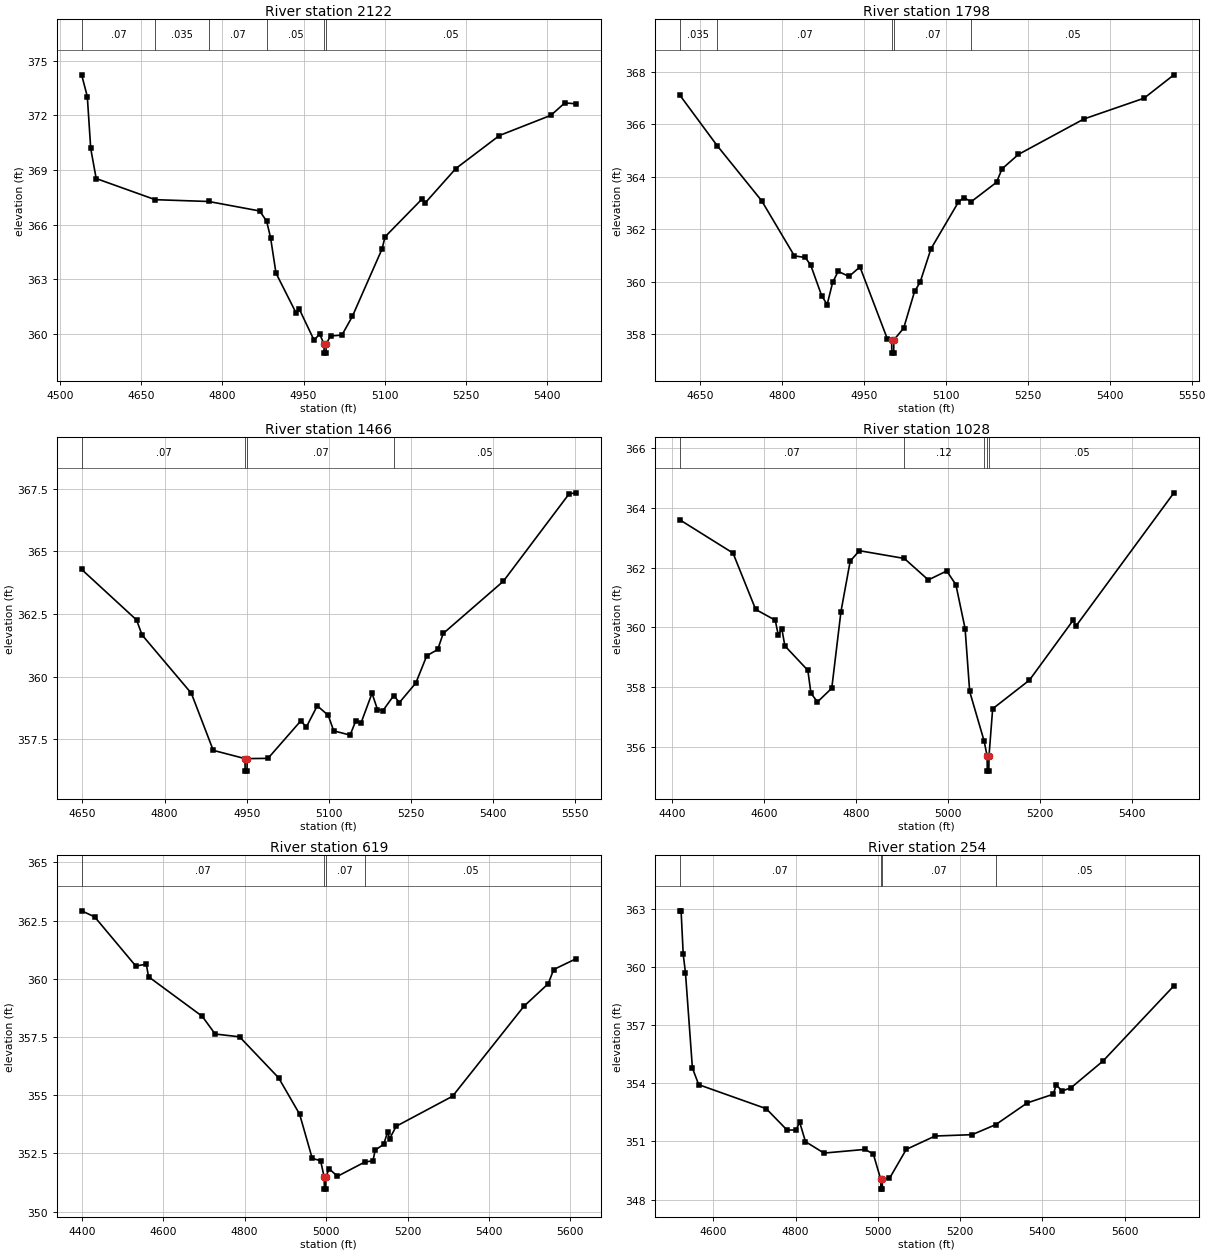
Type RM Length L Ch R = 1,2122,324,324,324
BEGIN DESCRIPTION:
XS7267
END DESCRIPTION:
XS GIS Cut Line= 2
      2376191.19     13598268.33      2376074.01     13599175.39
#Sta/Elev= 30
  4539.5  374.23  4550.0  373.04  4556.3  370.19  4566.4  368.54  4675.6  367.38
  4774.5  367.28  4868.9  366.76  4881.8  366.20  4889.1  365.29  4899.1  363.35
  4936.7  361.14  4941.8  361.40  4969.7  359.66  4979.8  360.02  4987.9  359.46
  4988.1  358.96  4991.6  358.96  4991.9  359.46  5000.0  359.90  5021.1  359.95
  5040.3  360.97  5095.4  364.68  5100.8  365.34  5169.8  367.43  5174.8  367.19
  5231.9  369.09  5312.5  370.90  5407.8  372.01  5433.5  372.69  5454.1  372.64
#Mann=6,-1,0
  4539.5    0.07       0  4675.6   0.035       0  4774.5    0.07       0
  4881.8    0.05       0  4987.9    0.05       0  4991.9    0.05       0
Bank Sta=4987.9,4991.9
Exp/Cntr=0.3,0.1

Type RM Length L Ch R = 1,1798,332,332,332
BEGIN DESCRIPTION:
XS7266
END DESCRIPTION:
XS GIS Cut Line= 2
      2375835.29     13598324.77      2375839.63     13599229.66
#Sta/Elev= 30
  4612.6  367.12  4681.2  365.19  4762.8  363.09  4822.8  360.99  4842.8  360.93
  4852.8  360.63  4872.8  359.47  4882.8  359.14  4892.8  359.98  4902.8  360.40
  4922.8  360.21  4942.8  360.57  4992.8  357.84  5000.8  357.79  5001.1  357.29
  5004.6  357.29  5004.8  357.79  5022.8  358.24  5042.8  359.64  5052.8  359.98
  5072.8  361.26  5122.8  363.03  5132.8  363.21  5146.3  363.05  5192.8  363.79
  5202.8  364.30  5232.8  364.85  5352.8  366.20  5462.8  366.99  5517.5  367.88
#Mann=5,-1,0
  4612.6   0.035       0  4681.2    0.07       0  5000.8    0.05       0
  5004.8    0.07       0  5146.3    0.05       0
Bank Sta=5000.8,5004.8
Exp/Cntr=0.3,0.1

Type RM Length L Ch R = 1,1466,438,438,438
BEGIN DESCRIPTION:
XS7265
END DESCRIPTION:
XS GIS Cut Line= 2
      2375535.81     13598374.66      2375548.83     13599277.47
#Sta/Elev= 30
  4648.6  364.28  4748.9  362.26  4759.0  361.66  4849.0  359.33  4889.0  357.05
  4947.0  356.72  4947.2  356.22  4950.7  356.22  4951.0  356.72  4989.0  356.73
  5049.0  358.23  5059.0  357.98  5079.0  358.83  5099.0  358.45  5109.0  357.83
  5139.0  357.66  5149.0  358.21  5159.0  358.15  5179.0  359.33  5189.0  358.68
  5199.0  358.64  5218.7  359.24  5229.0  358.96  5259.0  359.74  5279.0  360.83
  5299.0  361.08  5309.0  361.72  5419.0  363.81  5539.0  367.30  5551.5  367.34
#Mann=4,-1,0
  4648.6    0.07       0  4947.0    0.05       0  4951.0    0.07       0
  5218.7    0.05       0
Bank Sta=4947,4951
Exp/Cntr=0.3,0.1

Type RM Length L Ch R = 1,1028,409,409,409
BEGIN DESCRIPTION:
XS7264
END DESCRIPTION:
XS GIS Cut Line= 3
      2375453.36     13598409.36      2375214.63     13598626.39
      2375208.12     13599379.42
#Sta/Elev= 30
  4415.9  363.61  4532.2  362.49  4581.5  360.60  4624.1  360.24  4630.8  359.73
  4638.3  359.96  4645.0  359.38  4695.0  358.56  4701.8  357.79  4716.0  357.50
  4747.1  357.96  4767.1  360.53  4787.2  362.22  4807.2  362.57  4904.9  362.31
  4957.2  361.59  4997.2  361.89  5017.2  361.43  5037.2  359.96  5047.2  357.85
  5078.6  356.19  5085.2  355.68  5085.4  355.18  5088.9  355.18  5089.2  355.68
  5097.2  357.27  5177.2  358.23  5272.9  360.25  5277.9  360.03  5491.6  364.51
#Mann=5,-1,0
  4415.9    0.07       0  4904.9    0.12       0  5078.6    0.05       0
  5085.2    0.05       0  5089.2    0.05       0
Bank Sta=5085.2,5089.2
Exp/Cntr=0.3,0.1

Type RM Length L Ch R = 1,619,365,365,365
BEGIN DESCRIPTION:
XS7263
END DESCRIPTION:
XS GIS Cut Line= 4
      2375375.24     13598426.73      2375051.87     13598537.41
      2374943.36     13598964.93      2375069.24     13599377.28
#Sta/Elev= 30
  4399.7  362.92  4431.7  362.66  4532.7  360.55  4558.5  360.63  4564.0  360.09
  4695.9  358.39  4727.6  357.63  4787.6  357.51  4883.4  355.75  4935.0  354.19
  4966.0  352.29  4986.6  352.19  4995.5  351.47  4995.8  350.97  4999.3  350.97
  4999.5  351.47  5007.2  351.85  5027.9  351.52  5094.8  352.13  5115.2  352.19
  5120.7  352.65  5141.4  352.89  5151.0  353.41  5156.2  353.14  5172.3  353.67
  5310.7  354.96  5485.8  358.82  5545.6  359.79  5559.0  360.40  5613.7  360.86
#Mann=4,-1,0
  4399.7    0.07       0  4995.5    0.05       0  4999.5    0.07       0
  5094.8    0.05       0
Bank Sta=4995.5,4999.5
Exp/Cntr=0.3,0.1

Type RM Length L Ch R = 1,254,0,0,0
BEGIN DESCRIPTION:
XS7262
END DESCRIPTION:
XS GIS Cut Line= 4
      2374804.47     13598383.33      2374635.20     13598726.22
      2374648.22     13599084.29      2374951.04     13599432.54
#Sta/Elev= 30
  4517.9  362.90  4521.6  362.90  4526.7  360.67  4532.2  359.71  4549.1  354.79
  4564.4  353.93  4728.7  352.69  4779.2  351.59  4801.6  351.59  4809.7  352.01
  4824.1  350.99  4869.0  350.40  4969.1  350.59  4989.1  350.35  5007.2  349.04
  5007.4  348.54  5010.9  348.54  5011.2  349.04  5028.3  349.09  5069.2  350.59
  5139.2  351.28  5229.3  351.35  5287.0  351.87  5363.5  352.99  5427.1  353.44
  5433.7  353.93  5447.9  353.60  5469.8  353.77  5547.7  355.15  5720.1  359.03
#Mann=4,-1,0
  4517.9    0.07       0  5007.2    0.05       0  5011.2    0.07       0
  5287.0    0.05       0
Bank Sta=5007.2,5011.2
Exp/Cntr=0.3,0.1

Chan Stop Cuts=-1