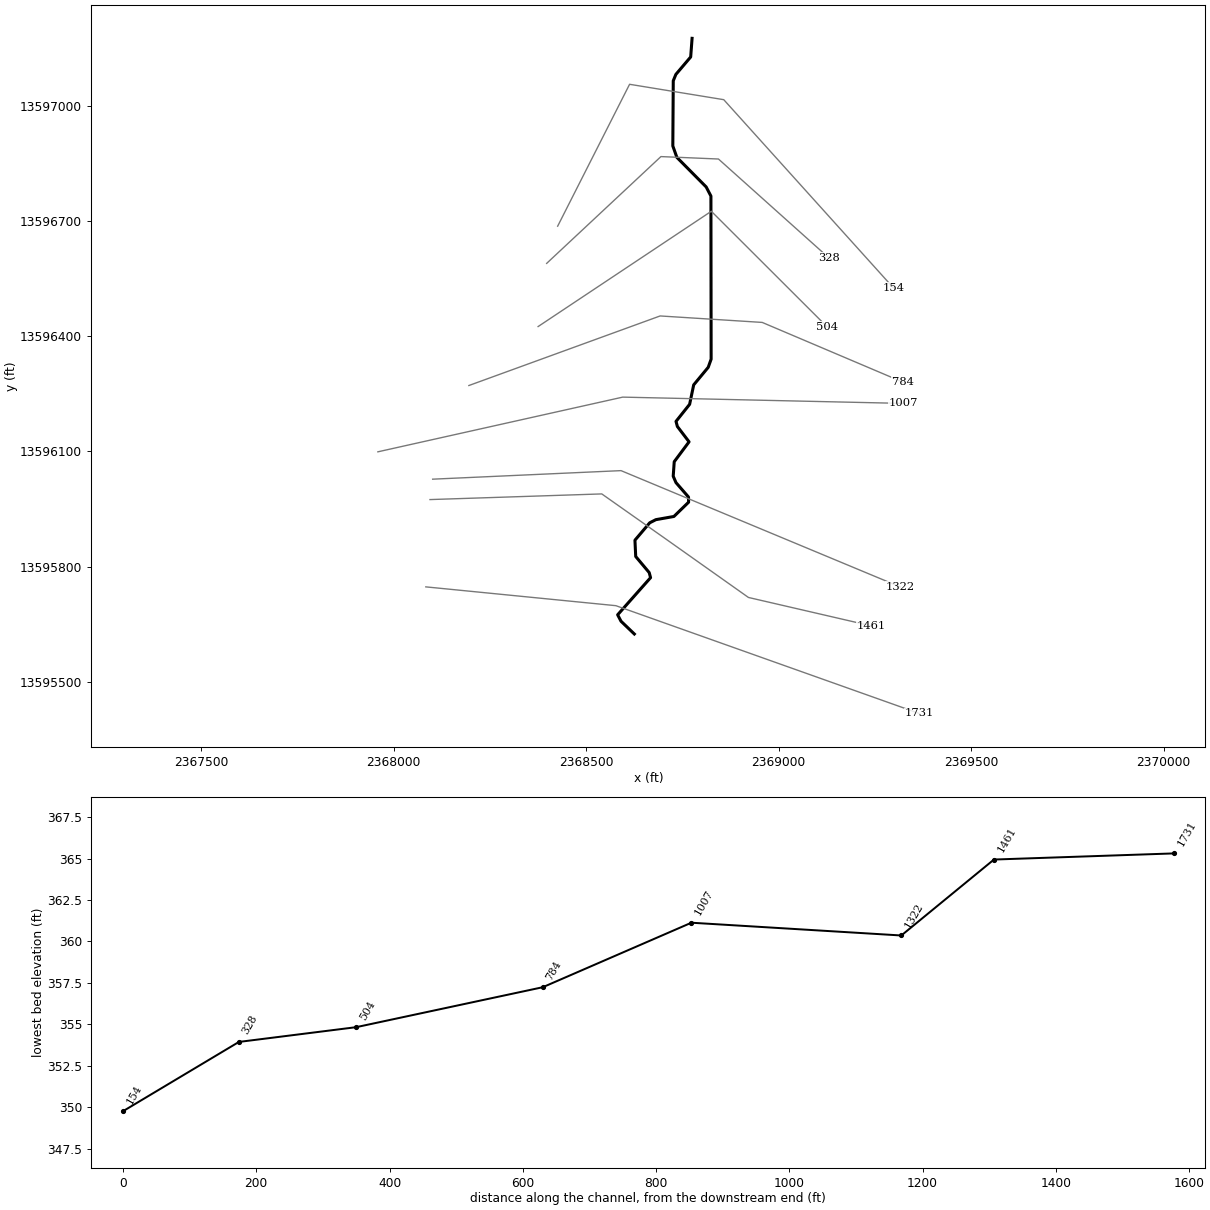
--- Stream0617.prj (project) ---

Proj Title=Stream0617 Base Level Engineering
Current Plan=p01
Default Exp/Contr=0.3,0.1
English Units
Geom File=g01
Flow File=f01
Plan File=p01
BEGIN DESCRIPTION:
Stream0617
END DESCRIPTION:

--- Stream0617.p01 (plan) ---

Plan Title=Multiple Run
Short Identifier=Multiple
Geom File=g01
Flow File=f01
Subcritical Flow
K Sum by GR= 0
Std Step Tol= 0.01
Critical Tol= 0.01
Num of Std Step Trials= 20
Max Error Tol= 0.3
Flow Tol Ratio= 0.001
Split Flow NTrial= 30
Split Flow Tol= 0.02
Split Flow Ratio= 0.02
Log Output Level= 0
Friction Slope Method= 1
Unsteady Friction Slope Method= 2
Unsteady Bridges Friction Slope Method= 1
Parabolic Critical Depth
Global Vel Dist=  1 , 1 , 1
Global Log Level= 0
CheckData=True
Encroach Param= -1, 0, 0, 0
BEGIN DESCRIPTION:
Multiple Run
END DESCRIPTION:

--- Stream0617.f01 (steady flow) ---

Flow Title=Multiple
Number of Profiles=7
Profile Names=10-year,25-year,50-year,1pct_min,100-year,1pct_plu,500-year
River Rch & RM= Stream0617,Reach-1,1731
     158     234     296     183     365     728     547
Boundary for River Rch & Prof#=Stream0617,Reach-1,1
Up Type=0
Dn Type=3
Dn Slope=0.005
Boundary for River Rch & Prof#=Stream0617,Reach-1,2
Up Type=0
Dn Type=3
Dn Slope=0.005
Boundary for River Rch & Prof#=Stream0617,Reach-1,3
Up Type=0
Dn Type=3
Dn Slope=0.005
Boundary for River Rch & Prof#=Stream0617,Reach-1,4
Up Type=0
Dn Type=3
Dn Slope=0.005
Boundary for River Rch & Prof#=Stream0617,Reach-1,5
Up Type=0
Dn Type=3
Dn Slope=0.005
Boundary for River Rch & Prof#=Stream0617,Reach-1,6
Up Type=0
Dn Type=3
Dn Slope=0.005
Boundary for River Rch & Prof#=Stream0617,Reach-1,7
Up Type=0
Dn Type=3
Dn Slope=0.005

--- Stream0617.g01 (geometry) ---

Geom Title=Existing Conditions

River Reach=Stream0617,Reach-1
Reach XY= 30
      2368625.00     13595625.00      2368590.40     13595658.22
      2368581.61     13595675.00      2368667.16     13595771.59
      2368663.60     13595784.87      2368628.57     13595826.68
      2368626.58     13595869.13      2368664.92     13595914.35
      2368680.90     13595922.54      2368727.82     13595930.86
      2368765.97     13595967.99      2368765.73     13595981.40
      2368733.17     13596018.93      2368725.99     13596035.63
      2368728.63     13596073.35      2368767.17     13596125.08
      2368736.81     13596164.96      2368733.24     13596178.23
      2368768.63     13596222.70      2368779.16     13596273.25
      2368816.90     13596318.92      2368824.49     13596340.21
      2368823.94     13596764.56      2368811.60     13596788.31
      2368735.50     13596865.21      2368724.96     13596894.98
      2368726.12     13597064.54      2368732.89     13597081.16
      2368771.35     13597126.51      2368775.00     13597175.00

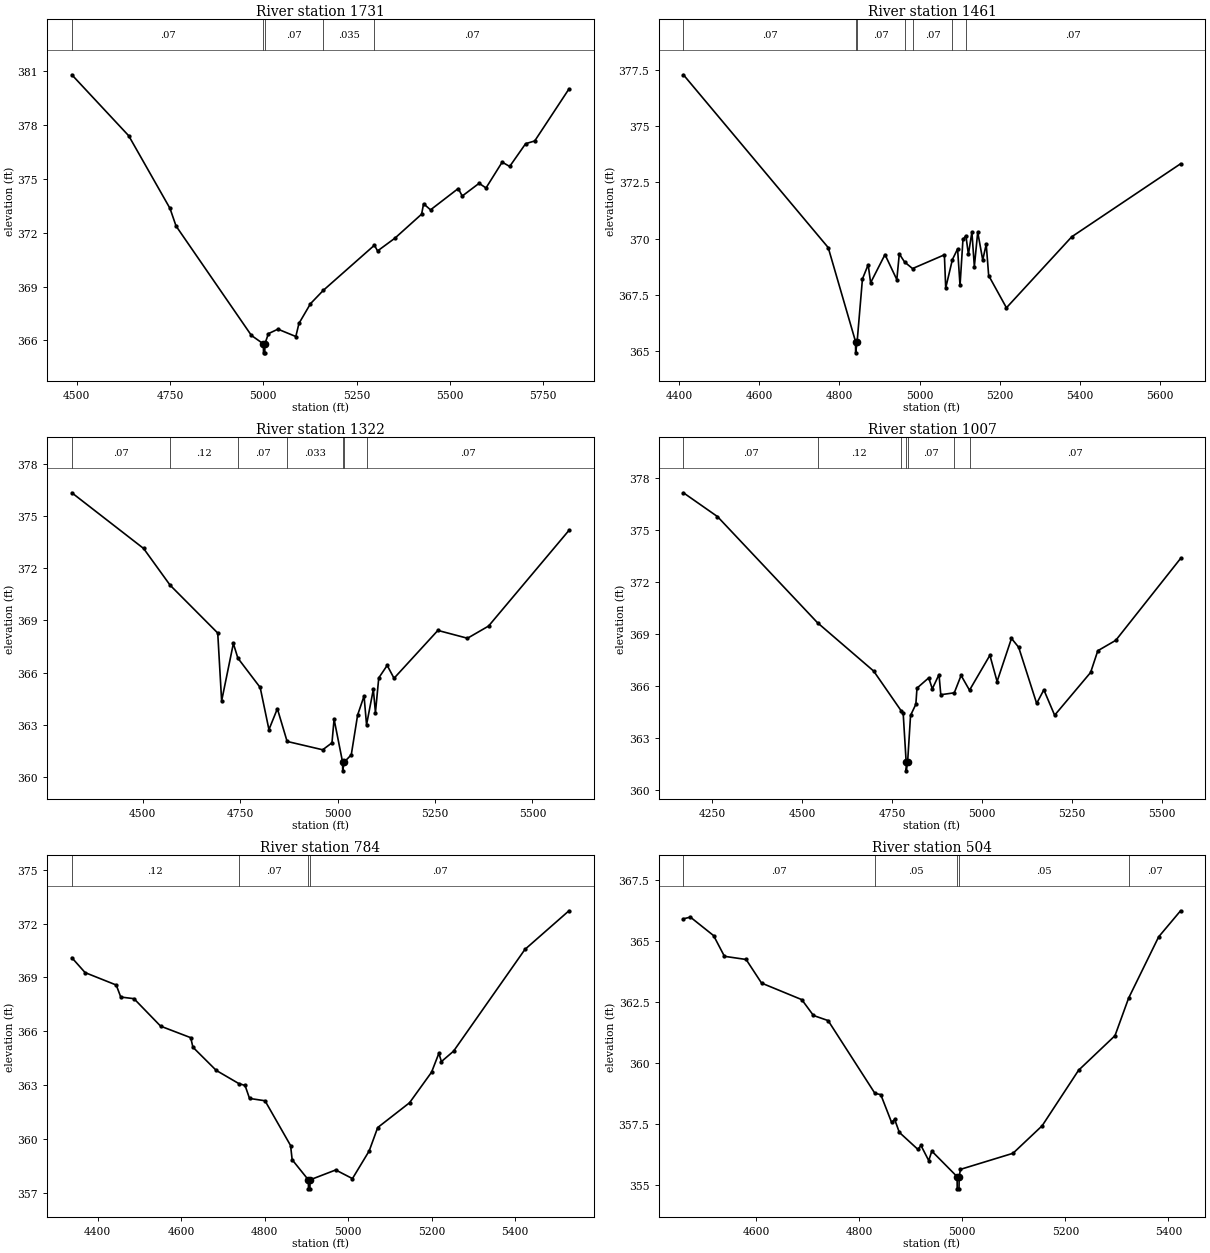
Type RM Length L Ch R = 1,1731,270,270,270
BEGIN DESCRIPTION:
XS7275
END DESCRIPTION:
XS GIS Cut Line= 3
      2368083.32     13595747.65      2368577.05     13595698.72
      2369364.41     13595418.48
#Sta/Elev= 30
  4487.2  380.81  4639.6  377.41  4750.2  373.36  4766.4  372.38  4968.3  366.28
  5000.4  365.81  5000.7  365.31  5004.2  365.31  5004.4  365.81  5013.9  366.38
  5039.4  366.63  5087.3  366.22  5095.7  366.95  5126.6  368.05  5160.8  368.79
  5297.9  371.31  5306.3  370.99  5352.7  371.70  5424.3  373.04  5429.6  373.62
  5448.2  373.28  5522.5  374.47  5533.1  374.05  5578.4  374.76  5596.8  374.50
  5640.1  375.94  5660.3  375.70  5703.0  376.97  5727.3  377.12  5819.1  380.02
#Mann=5,-1,0
  4487.2    0.07       0  5000.4    0.05       0  5004.4    0.07       0
  5160.8   0.035       0  5297.9    0.07       0
Bank Sta=5000.4,5004.4
Exp/Cntr=0.3,0.1

Type RM Length L Ch R = 1,1461,139,139,139
BEGIN DESCRIPTION:
E21180
END DESCRIPTION:
XS GIS Cut Line= 5
      2368094.17     13595974.80      2368540.42     13595989.54
      2368704.61     13595873.77      2368921.41     13595720.10
      2369239.26     13595646.43
#Sta/Elev= 30
  4411.2  377.28  4772.2  369.61  4840.3  365.44  4840.5  364.94  4844.3  365.44
  4857.5  368.22  4871.8  368.85  4877.9  368.05  4913.7  369.30  4943.2  368.19
  4949.4  369.33  4962.6  368.97  4982.4  368.68  5061.8  369.29  5065.1  367.82
  5081.8  369.08  5094.7  369.55  5100.8  367.93  5108.1  369.97  5115.4  370.14
  5121.7  369.31  5130.4  370.30  5136.5  368.77  5144.9  370.30  5157.4  369.06
  5166.1  369.76  5172.2  368.37  5216.5  366.94  5379.3  370.09  5650.6  373.33
#Mann=7,-1,0
  4411.2    0.07       0  4840.3    0.05       0  4844.3    0.07       0
  4962.6   0.033       0  4982.4    0.07       0  5081.8   0.033       0
  5115.4    0.07       0
Bank Sta=4840.3,4844.3
Exp/Cntr=0.3,0.1

Type RM Length L Ch R = 1,1322,315,315,315
BEGIN DESCRIPTION:
XS7276
END DESCRIPTION:
XS GIS Cut Line= 3
      2368101.07     13596027.89      2368590.40     13596050.13
      2369315.40     13595747.67
#Sta/Elev= 30
  4318.3  376.34  4502.4  373.14  4570.4  371.03  4692.6  368.28  4702.6  364.38
  4732.7  367.68  4744.2  366.84  4801.5  365.15  4824.0  362.73  4845.6  363.93
  4870.6  362.05  4961.9  361.57  4985.7  361.97  4991.1  363.33  5012.9  360.86
  5013.2  360.36  5016.9  360.86  5035.2  361.28  5051.5  363.57  5068.0  364.66
  5074.4  363.01  5091.8  365.04  5097.2  363.71  5105.7  365.70  5127.3  366.42
  5144.9  365.68  5257.4  368.43  5333.3  367.98  5387.4  368.68  5593.7  374.18
#Mann=7,-1,0
  4318.3    0.07       0  4570.4    0.12       0  4744.2    0.07       0
  4870.6   0.033       0  5012.9   0.033       0  5016.9   0.033       0
  5074.4    0.07       0
Bank Sta=5012.9,5016.9
Exp/Cntr=0.3,0.1

Type RM Length L Ch R = 1,1007,223,223,223
BEGIN DESCRIPTION:
Stream0617 2.0
END DESCRIPTION:
XS GIS Cut Line= 3
      2367958.73     13596099.05      2368594.85     13596241.40
      2369325.01     13596225.00
#Sta/Elev= 30
  4169.5  377.13  4264.2  375.76  4542.4  369.65  4698.5  366.87  4774.4  364.60
  4780.5  364.44  4788.8  361.63  4789.0  361.13  4792.8  361.63  4801.0  364.32
  4815.7  364.96  4818.9  365.89  4851.5  366.48  4861.5  365.85  4880.1  366.67
  4885.1  365.51  4922.6  365.62  4941.5  366.62  4964.9  365.77  5021.6  367.78
  5041.6  366.27  5081.6  368.75  5101.6  368.24  5151.6  365.01  5171.6  365.79
  5201.6  364.33  5301.6  366.79  5321.6  368.04  5371.6  368.64  5551.7  373.35
#Mann=7,-1,0
  4169.5    0.07       0  4542.4    0.12       0  4774.4    0.07       0
  4788.8    0.05       0  4792.8    0.07       0  4922.6   0.033       0
  4964.9    0.07       0
Bank Sta=4788.8,4792.8
Exp/Cntr=0.3,0.1

Type RM Length L Ch R = 1,784,280,280,280
BEGIN DESCRIPTION:
E21179
END DESCRIPTION:
XS GIS Cut Line= 4
      2368195.17     13596271.58      2368691.98     13596452.62
      2368957.20     13596435.78      2369321.77     13596280.74
#Sta/Elev= 30
  4337.9  370.10  4369.7  369.27  4444.2  368.58  4455.1  367.91  4486.7  367.82
  4550.6  366.29  4622.6  365.65  4627.9  365.12  4683.7  363.83  4737.6  363.10
  4752.8  362.99  4763.5  362.27  4800.6  362.14  4861.8  359.65  4865.6  358.86
  4904.4  357.74  4904.7  357.24  4908.2  357.24  4908.4  357.74  4969.9  358.29
  5010.0  357.81  5050.1  359.35  5070.5  360.65  5146.8  362.03  5199.5  363.73
  5217.0  364.78  5223.1  364.32  5252.2  364.90  5423.1  370.56  5528.6  372.71
#Mann=4,-1,0
  4337.9    0.12       0  4737.6    0.07       0  4904.4    0.05       0
  4908.4    0.07       0
Bank Sta=4904.4,4908.4
Exp/Cntr=0.3,0.1

Type RM Length L Ch R = 1,504,176,176,176
BEGIN DESCRIPTION:
Stream0617 1.0
END DESCRIPTION:
XS GIS Cut Line= 3
      2368375.02     13596425.02      2368825.00     13596725.00
      2369125.02     13596424.98
#Sta/Elev= 30
  4458.6  365.92  4472.1  365.99  4517.2  365.23  4538.2  364.38  4580.3  364.25
  4610.3  363.28  4688.4  362.60  4711.0  361.95  4739.5  361.74  4830.4  358.75
  4841.7  358.70  4862.7  357.56  4868.7  357.68  4877.7  357.15  4913.8  356.45
  4919.8  356.61  4934.8  355.99  4940.8  356.38  4989.9  355.33  4990.1  354.83
  4993.6  354.83  4993.9  355.33  4996.4  355.63  5098.4  356.29  5155.0  357.42
  5225.7  359.70  5296.4  361.12  5322.8  362.66  5381.2  365.18  5423.7  366.25
#Mann=5,-1,0
  4458.6    0.07       0  4830.4    0.05       0  4989.9    0.05       0
  4993.9    0.05       0  5322.8    0.07       0
Bank Sta=4989.9,4993.9
Exp/Cntr=0.3,0.1

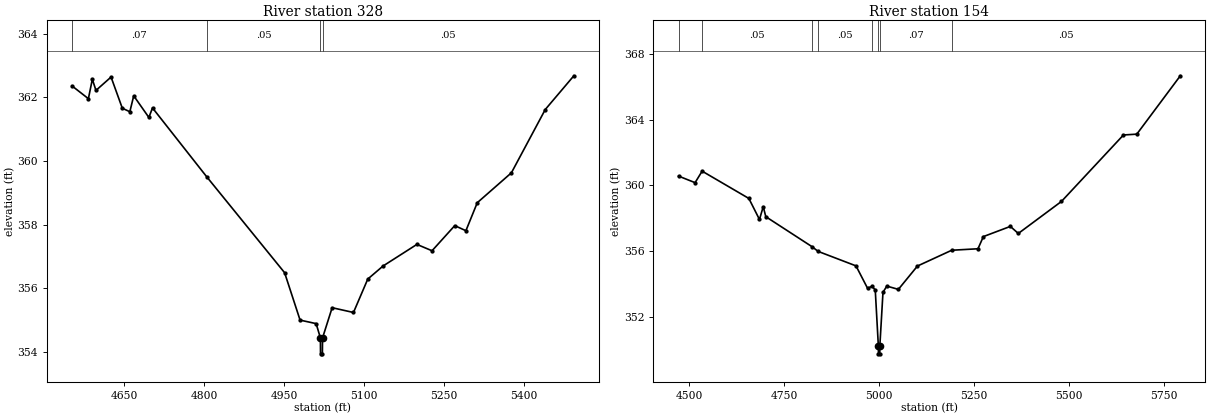
Type RM Length L Ch R = 1,328,174,174,174
BEGIN DESCRIPTION:
E21178
END DESCRIPTION:
XS GIS Cut Line= 4
      2368397.25     13596589.41      2368694.08     13596867.30
      2368843.53     13596860.98      2369129.83     13596604.16
#Sta/Elev= 30
  4552.2  362.36  4582.8  361.96  4590.2  362.57  4597.0  362.22  4625.3  362.64
  4646.4  361.66  4660.5  361.55  4667.8  362.05  4696.2  361.37  4703.0  361.67
  4804.4  359.51  4950.7  356.49  4979.7  355.00  5009.8  354.89  5017.8  354.44
  5018.0  353.94  5021.5  353.94  5021.8  354.44  5039.8  355.39  5079.8  355.24
  5106.6  356.29  5135.2  356.70  5198.7  357.38  5227.1  357.18  5269.7  357.97
  5290.6  357.81  5311.9  358.69  5375.9  359.63  5439.4  361.62  5493.0  362.68
#Mann=4,-1,0
  4552.2    0.07       0  4804.4    0.05       0  5017.8    0.05       0
  5021.8    0.05       0
Bank Sta=5017.8,5021.8
Exp/Cntr=0.3,0.1

Type RM Length L Ch R = 1,154,0,0,0
BEGIN DESCRIPTION:
XS7274
END DESCRIPTION:
XS GIS Cut Line= 4
      2368425.81     13596686.21      2368612.64     13597055.42
      2368857.29     13597015.38      2369297.68     13596526.06
#Sta/Elev= 30
  4472.8  360.57  4516.3  360.17  4534.9  360.87  4657.8  359.21  4685.7  357.93
  4695.6  358.71  4702.4  358.10  4824.4  356.27  4840.0  355.99  4939.6  355.11
  4970.0  353.75  4982.1  353.87  4990.3  353.64  4998.4  350.26  4998.7  349.76
  5002.2  349.76  5002.4  350.26  5010.6  353.50  5020.7  353.88  5051.1  353.68
  5101.3  355.10  5191.5  356.06  5260.5  356.15  5274.7  356.89  5345.7  357.51
  5366.6  357.08  5480.2  359.03  5643.2  363.07  5678.3  363.12  5792.8  366.67
#Mann=8,-1,0
  4472.8    0.07       0  4534.9    0.05       0  4824.4    0.07       0
  4840.0    0.05       0  4982.1    0.07       0  4998.4    0.05       0
  5002.4    0.07       0  5191.5    0.05       0
Bank Sta=4998.4,5002.4
Exp/Cntr=0.3,0.1

Chan Stop Cuts=-1