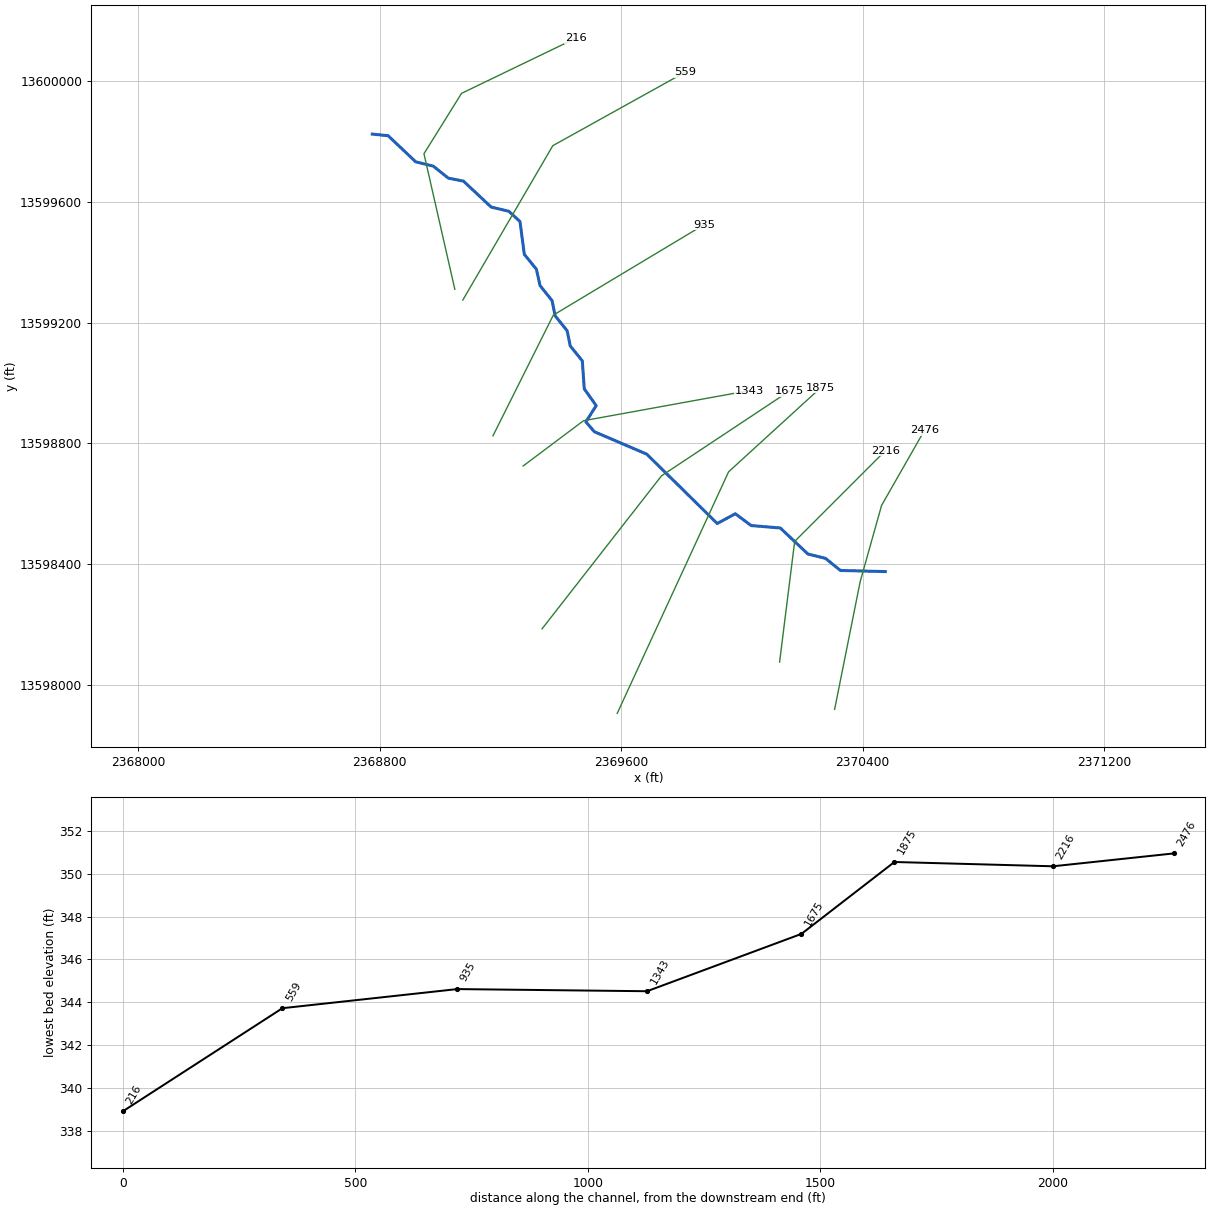
--- Stream0618.prj (project) ---

Proj Title=Stream0618 Base Level Engineering
Current Plan=p01
Default Exp/Contr=0.3,0.1
English Units
Geom File=g01
Flow File=f01
Plan File=p01
Y Axis Title=Elevation
X Axis Title(PF)=Main Channel Distance
X Axis Title(XS)=Station
BEGIN DESCRIPTION:
Stream0618
END DESCRIPTION:
DSS Export Rating Curves= 0
DSS Export Rating Curve Sorted= 0
DSS Export Volume Flow Curves= 0
DXF OffsetX= 0
DXF OffsetY= 0
DXF ScaleX= 1
DXF ScaleY= 10

--- Stream0618.p01 (plan) ---

Plan Title=Multiple Run
Short Identifier=Multiple
Geom File=g01
Flow File=f01
Subcritical Flow
K Sum by GR= 0
Std Step Tol= 0.01
Critical Tol= 0.01
Num of Std Step Trials= 20
Max Error Tol= 0.3
Flow Tol Ratio= 0.001
Split Flow NTrial= 30
Split Flow Tol= 0.02
Split Flow Ratio= 0.02
Log Output Level= 0
Friction Slope Method= 1
Unsteady Friction Slope Method= 2
Unsteady Bridges Friction Slope Method= 1
Parabolic Critical Depth
Global Vel Dist=  1 , 1 , 1
Global Log Level= 0
CheckData=True
Encroach Param= -1, 0, 0, 0
BEGIN DESCRIPTION:
Multiple Run
END DESCRIPTION:

--- Stream0618.f01 (steady flow) ---

Flow Title=Multiple
Number of Profiles=7
Profile Names=10-year,25-year,50-year,1pct_min,100-year,1pct_plu,500-year
River Rch & RM= Stream0618,Reach-1,2476
     177     266     340     212     422     842     643
Boundary for River Rch & Prof#=Stream0618,Reach-1,1
Up Type=0
Dn Type=3
Dn Slope=0.005
Boundary for River Rch & Prof#=Stream0618,Reach-1,2
Up Type=0
Dn Type=3
Dn Slope=0.005
Boundary for River Rch & Prof#=Stream0618,Reach-1,3
Up Type=0
Dn Type=3
Dn Slope=0.005
Boundary for River Rch & Prof#=Stream0618,Reach-1,4
Up Type=0
Dn Type=3
Dn Slope=0.005
Boundary for River Rch & Prof#=Stream0618,Reach-1,5
Up Type=0
Dn Type=3
Dn Slope=0.005
Boundary for River Rch & Prof#=Stream0618,Reach-1,6
Up Type=0
Dn Type=3
Dn Slope=0.005
Boundary for River Rch & Prof#=Stream0618,Reach-1,7
Up Type=0
Dn Type=3
Dn Slope=0.005

--- Stream0618.g01 (geometry) ---

Geom Title=Existing Conditions
Program Version=4.10

River Reach=Stream0618      ,Reach-1
Reach XY= 30
        2370475.       13598375.      2370326.54     13598378.72
      2370277.17     13598418.86      2370218.95     13598433.16
      2370127.42     13598519.47      2370030.89     13598527.55
      2369978.22     13598566.71      2369918.33      13598534.3
      2369684.68     13598764.24        2369511.     13598838.62
      2369482.89     13598871.41      2369517.19     13598924.89
      2369477.54     13598980.89      2369471.18     13599073.41
      2369431.12     13599122.82      2369420.84     13599173.28
      2369381.08      13599222.8      2369370.84     13599273.28
      2369331.08      13599322.8      2369318.88     13599377.18
      2369278.83     13599426.59      2369264.61      13599535.1
      2369227.57     13599569.26      2369168.98     13599583.19
      2369077.29     13599669.15      2369026.73     13599679.19
      2368977.19      13599718.9      2368918.95     13599733.14
      2368827.51     13599819.67        2368775.       13599825.

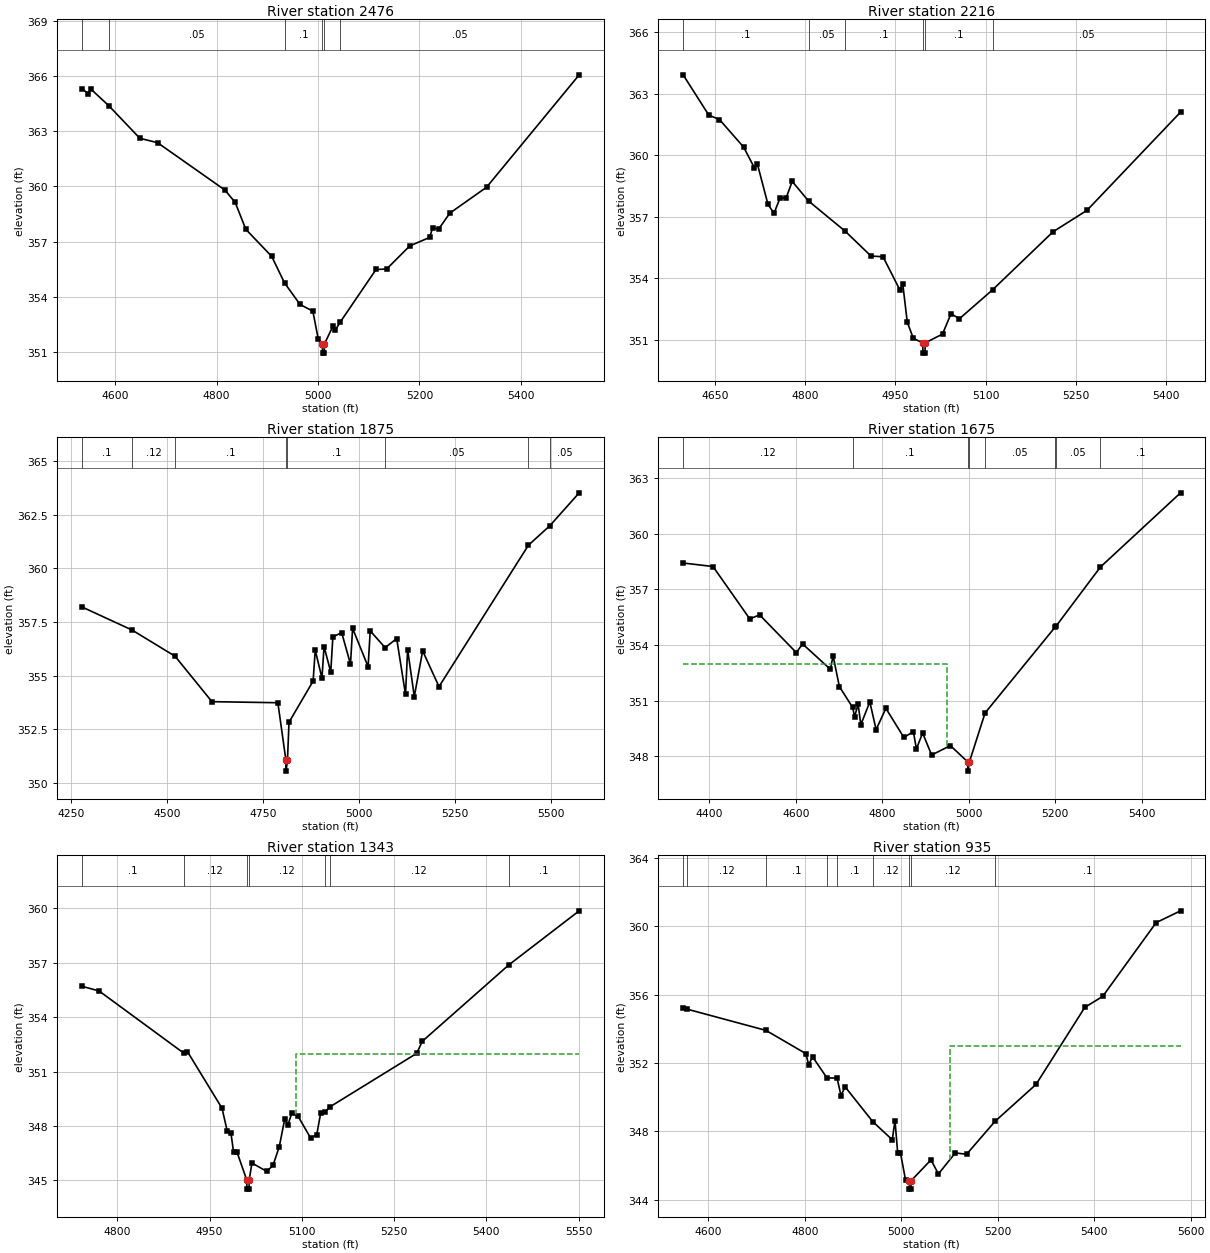
Type RM Length L Ch R = 1 ,2476    ,260,260,260
BEGIN DESCRIPTION:
XS7278
END DESCRIPTION:
XS GIS Cut Line= 4
       2370307.4     13597918.39      2370391.91     13598340.94
      2370463.08     13598594.49      2370605.44     13598843.62
#Sta/Elev= 30
    4534  365.32  4546.6  365.05  4551.7   365.3  4587.7  364.38  4648.5  362.62
  4683.5  362.38  4816.1  359.81  4836.5  359.14  4857.6  357.67  4908.6   356.2
  4933.9  354.76  4964.4  353.59  4989.8  353.22  5000.3  351.73  5008.7  351.44
  5008.9  350.94  5012.4  350.94  5012.7  351.44  5029.1  352.39  5034.3   352.2
  5043.4  352.61  5114.5  355.49  5135.3  355.51    5181  356.77  5220.2  357.23
  5225.9  357.74  5238.4   357.7    5260  358.55  5332.5  359.96  5515.2  366.07
#Mann= 6 ,-1 , 0
    4534      .1       0  4587.7     .05       0  4933.9      .1       0
  5008.7     .05       0  5012.7      .1       0  5043.4     .05       0
Bank Sta=5008.7,5012.7
XS Rating Curve= 0 ,0
Exp/Cntr=0.3,0.1

Type RM Length L Ch R = 1 ,2216    ,341,341,341
BEGIN DESCRIPTION:
Stream0618 5.0
END DESCRIPTION:
XS GIS Cut Line= 3
        2370125.     13598075.04        2370175.       13598475.
      2370474.97     13598774.97
#Sta/Elev= 30
  4596.9  363.92  4639.7  361.95  4657.3  361.74  4697.6  360.39  4715.3  359.39
  4720.3  359.58    4738   357.6    4748  357.16  4758.1  357.91  4768.2  357.91
  4778.3  358.72  4805.6  357.76  4866.4  356.29  4909.3  355.08  4929.4  355.04
  4957.1  353.44  4962.2  353.71  4969.7  351.85  4979.8  351.06  4995.5  350.84
  4995.7  350.34  4999.2  350.34  4999.5  350.84  5028.3  351.27  5042.4  352.26
  5056.5  352.02  5111.6  353.43  5212.1  356.26  5268.7  357.31  5424.2   362.1
#Mann= 6 ,-1 , 0
  4596.9      .1       0  4805.6     .05       0  4866.4      .1       0
  4995.5     .05       0  4999.5      .1       0  5111.6     .05       0
Bank Sta=4995.5,4999.5
XS Rating Curve= 0 ,0
Exp/Cntr=0.3,0.1

Type RM Length L Ch R = 1 ,1875    ,200,200,200
BEGIN DESCRIPTION:
Stream0618 4.0
END DESCRIPTION:
XS GIS Cut Line= 3
      2369586.79     13597905.02      2369955.99     13598705.69
      2370261.43     13598984.57
#Sta/Elev= 30
  4278.4   358.2  4409.4  357.12  4521.2   355.9  4617.3  353.78    4789  353.73
    4810  351.04  4810.2  350.54    4814  351.04    4818  352.82  4880.8  354.74
  4886.3  356.18  4903.8  354.88  4909.3  356.35  4926.7  355.16  4932.2   356.8
  4955.2     357  4978.1  355.53  4983.6   357.2    5024  355.41  5029.5  357.08
  5068.3   356.3  5098.4  356.72  5121.4  354.12  5126.9  356.21  5144.3  354.02
    5166  356.15  5208.6  354.48  5441.6  361.08  5496.9  361.98  5573.7  363.52
#Mann= 8 ,-1 , 0
  4278.4      .1       0  4409.4     .12       0  4521.2      .1       0
    4810     .05       0    4814      .1       0  5068.3     .05       0
  5441.6      .1       0  5496.9     .05       0
Bank Sta=4810,4814
XS Rating Curve= 0 ,0
Exp/Cntr=0.3,0.1

Type RM Length L Ch R = 1 ,1675    ,332,332,332
BEGIN DESCRIPTION:
XS7280
END DESCRIPTION:
XS GIS Cut Line= 3
      2369337.67     13598185.23      2369733.58     13598692.35
      2370156.15     13598972.58
#Sta/Elev= 30
  4339.2  358.43  4408.3  358.24  4493.4  355.41    4516  355.63    4601  353.59
  4615.4  354.06  4679.7  352.69    4686  353.42  4700.5  351.76  4731.2  350.63
  4735.8  350.13  4743.9  350.81  4750.2   349.7    4771  350.93  4785.5  349.43
  4808.1  350.58  4849.7  349.01  4871.7  349.32  4878.7  348.39  4893.1  349.25
  4913.9  348.06  4957.3  348.57  4997.3  347.69  4997.6  347.19  5001.3  347.69
  5037.5  350.33  5199.6  354.97    5202  355.03  5304.2  358.21  5489.6  362.22
#Mann= 8 ,-1 , 0
  4339.2     .12       0  4731.2      .1       0  4997.3     .05       0
  5001.3      .1       0  5037.5     .05       0  5199.6      .1       0
    5202     .05       0  5304.2      .1       0
#XS Ineff= 2 , 0
       0    4950     353               0
Permanent Ineff=
       F       F
Bank Sta=4997.3,5001.3
XS Rating Curve= 0 ,0
Exp/Cntr=0.3,0.1

Type RM Length L Ch R = 1 ,1343    ,408,408,408
BEGIN DESCRIPTION:
Stream0618 3.0
END DESCRIPTION:
XS GIS Cut Line= 3
      2369274.99     13598724.99        2369475.       13598875.
      2370024.97     13598974.99
#Sta/Elev= 30
  4742.1  355.71  4770.2  355.45  4907.6  352.03    4914   352.1  4970.2  348.98
  4978.6  347.73  4984.8  347.59    4989  346.55  4994.7  346.55  5010.4  345.02
  5010.7  344.52  5014.2  344.52  5014.4  345.02  5018.8  345.96  5042.9   345.5
  5053.1  345.83  5063.3  346.86  5072.2  348.39  5077.2  348.05  5083.6   348.7
  5093.8  348.54  5114.1  347.35  5124.2  347.52  5130.6  348.71  5138.3  348.79
  5145.3  349.05  5286.9  352.01  5295.8  352.67  5436.7  356.89  5551.1  359.87
#Mann= 7 ,-1 , 0
  4742.1      .1       0  4907.6     .12       0  5010.4     .05       0
  5014.4     .12       0  5138.3      .1       0  5145.3     .12       0
  5436.7      .1       0
#XS Ineff= 2 , 0
       0                    5090       0     352
Permanent Ineff=
       F       F
Bank Sta=5010.4,5014.4
XS Rating Curve= 0 ,0
Exp/Cntr=0.3,0.1

Type RM Length L Ch R = 1 ,935     ,376,376,376
BEGIN DESCRIPTION:
Stream0618 2.0
END DESCRIPTION:
XS GIS Cut Line= 3
      2369175.01     13598825.01        2369375.       13599225.
        2369875.       13599525.
#Sta/Elev= 30
  4548.2  355.21  4557.1  355.15  4719.9  353.91  4802.5  352.55  4808.1  351.91
  4816.5  352.36  4846.1  351.13  4867.1  351.12  4875.2  350.09  4883.6  350.61
    4941  348.57  4981.4  347.51    4987  348.63  4992.6  346.76  4998.3  346.76
    5009  345.13  5016.7  345.12    5017  344.62  5020.5  344.62  5020.7  345.12
  5061.5  346.33    5077  345.51    5112  346.74  5135.3  346.66    5194  348.58
  5279.2  350.75  5380.2  355.26  5417.2   355.9    5528  360.22  5578.5  360.91
#Mann= 9 ,-1 , 0
  4548.2      .1       0  4557.1     .12       0  4719.9      .1       0
  4846.1     .12       0  4867.1      .1       0    4941     .12       0
  5016.7     .05       0  5020.7     .12       0    5194      .1       0
#XS Ineff= 2 , 0
       0                    5100       0     353
Permanent Ineff=
       F       F
Bank Sta=5016.7,5020.7
XS Rating Curve= 0 ,0
Exp/Cntr=0.3,0.1

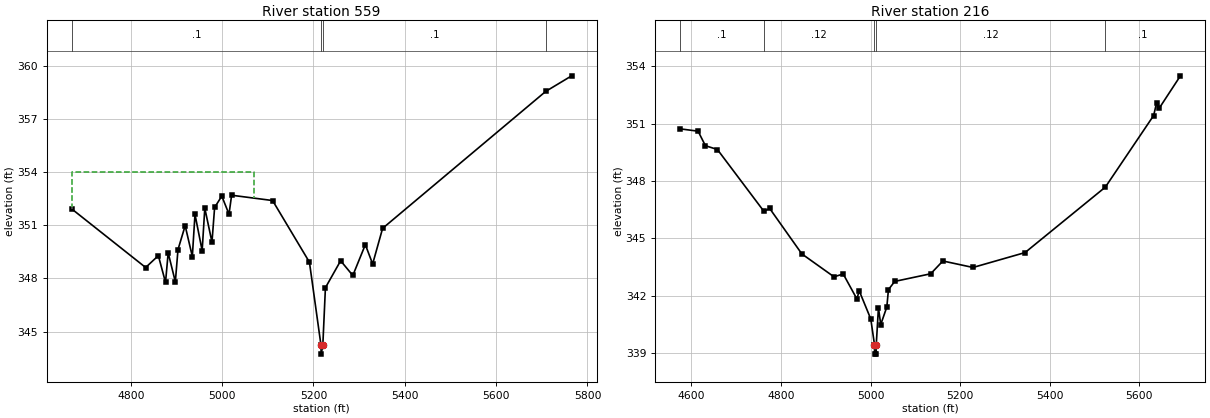
Type RM Length L Ch R = 1 ,559     ,343,343,343
BEGIN DESCRIPTION:
Stream0618 1.0
END DESCRIPTION:
XS GIS Cut Line= 3
      2369075.01     13599275.01      2369373.28      13599786.6
      2369812.55     13600030.64
#Sta/Elev= 30
  4670.6  351.93  4832.6  348.62  4860.4  349.29  4876.1  347.78  4881.9  349.45
  4897.6  347.81  4903.4  349.63  4919.1  350.98  4934.8  349.24  4940.6  351.62
  4956.3  349.57  4962.1  351.97  4977.8  350.05  4983.6  352.01  4999.3  352.65
  5015.1  351.63  5020.8   352.7  5110.5   352.4  5191.2  348.92  5216.5  344.23
  5216.8  343.73  5220.5  344.23  5226.2  347.48  5259.5     349  5286.2  348.17
  5313.6  349.91  5329.6  348.82  5351.4  350.83  5708.5  358.56  5765.3  359.44
#Mann= 4 ,-1 , 0
  4670.6      .1       0  5216.5     .05       0  5220.5      .1       0
  5708.5     .05       0
#XS Ineff= 2 , 0
       0    5070     354               0
Permanent Ineff=
       F       F
Bank Sta=5216.5,5220.5
XS Rating Curve= 0 ,0
Exp/Cntr=0.3,0.1

Type RM Length L Ch R = 1 ,216     ,0,0,0
BEGIN DESCRIPTION:
XS7279
END DESCRIPTION:
XS GIS Cut Line= 4
      2369048.56     13599310.65      2368946.25     13599759.91
       2369070.8     13599960.08       2369448.9     13600142.45
#Sta/Elev= 30
  4575.5  350.73  4614.9  350.61  4631.2  349.85    4658  349.65  4761.9  346.41
  4774.8  346.56  4846.6  344.18  4918.4  342.98  4938.9  343.13  4969.5  341.82
  4974.6  342.25  5000.5  340.77  5008.7  339.43    5009  338.93  5012.5  338.93
  5012.7  339.43  5017.6  341.36  5022.7  340.48  5036.3   341.4  5039.9  342.31
    5054  342.74  5134.3  343.14  5161.4  343.81  5228.7  343.47  5344.9  344.25
  5524.2  347.68    5632  351.43  5638.8  352.11  5644.4  351.81  5691.8  353.51
#Mann= 5 ,-1 , 0
  4575.5      .1       0  4761.9     .12       0  5008.7     .05       0
  5012.7     .12       0  5524.2      .1       0
Bank Sta=5008.7,5012.7
XS Rating Curve= 0 ,0
Exp/Cntr=0.3,0.1

Chan Stop Cuts=-1
Use User Specified Reach Order=0
Composite Channel Slope=5