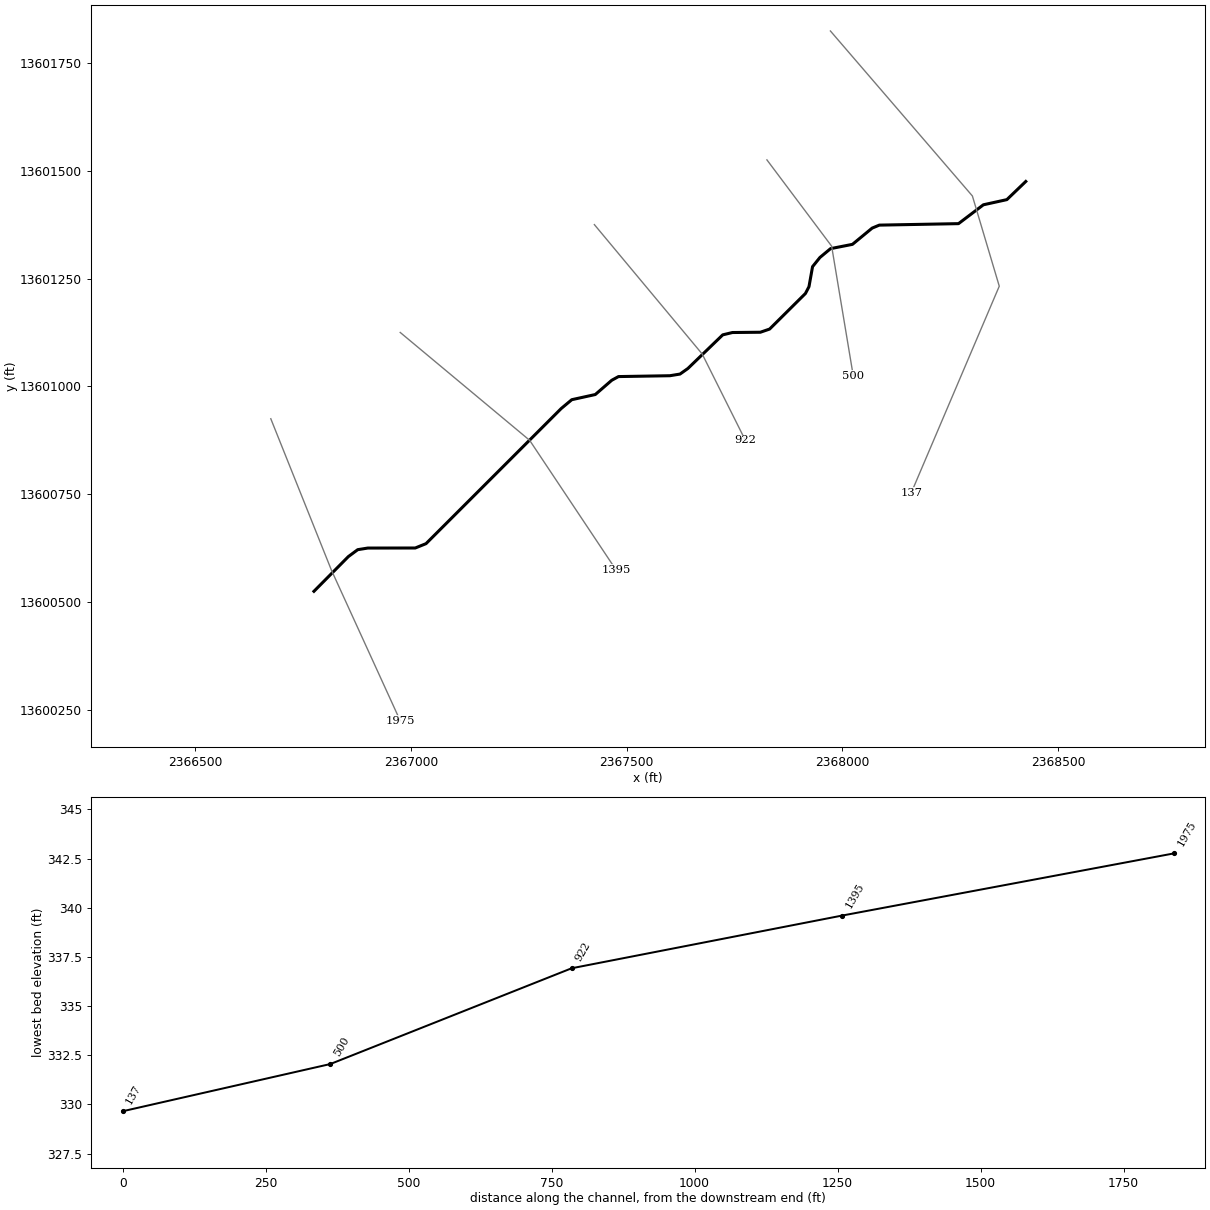
--- Stream0619.prj (project) ---

Proj Title=Stream0619 Base Level Engineering
Current Plan=p01
Default Exp/Contr=0.3,0.1
English Units
Geom File=g01
Flow File=f01
Plan File=p01
BEGIN DESCRIPTION:
Stream0619
END DESCRIPTION:

--- Stream0619.p01 (plan) ---

Plan Title=Multiple Run
Short Identifier=Multiple
Geom File=g01
Flow File=f01
Subcritical Flow
K Sum by GR= 0
Std Step Tol= 0.01
Critical Tol= 0.01
Num of Std Step Trials= 20
Max Error Tol= 0.3
Flow Tol Ratio= 0.001
Split Flow NTrial= 30
Split Flow Tol= 0.02
Split Flow Ratio= 0.02
Log Output Level= 0
Friction Slope Method= 1
Unsteady Friction Slope Method= 2
Unsteady Bridges Friction Slope Method= 1
Parabolic Critical Depth
Global Vel Dist=  1 , 1 , 1
Global Log Level= 0
CheckData=True
Encroach Param= -1, 0, 0, 0
BEGIN DESCRIPTION:
Multiple Run
END DESCRIPTION:

--- Stream0619.f01 (steady flow) ---

Flow Title=Multiple
Number of Profiles=7
Profile Names=10-year,25-year,50-year,1pct_min,100-year,1pct_plu,500-year
River Rch & RM= Stream0619,Reach-1,1975
     302     466     608     385     767    1531    1211
River Rch & RM= Stream0619,Reach-1,137
     741    1207    1629    1064    2122    4234    3573
Boundary for River Rch & Prof#=Stream0619,Reach-1,1
Up Type=0
Dn Type=3
Dn Slope=0.005
Boundary for River Rch & Prof#=Stream0619,Reach-1,2
Up Type=0
Dn Type=3
Dn Slope=0.005
Boundary for River Rch & Prof#=Stream0619,Reach-1,3
Up Type=0
Dn Type=3
Dn Slope=0.005
Boundary for River Rch & Prof#=Stream0619,Reach-1,4
Up Type=0
Dn Type=3
Dn Slope=0.005
Boundary for River Rch & Prof#=Stream0619,Reach-1,5
Up Type=0
Dn Type=3
Dn Slope=0.005
Boundary for River Rch & Prof#=Stream0619,Reach-1,6
Up Type=0
Dn Type=3
Dn Slope=0.005
Boundary for River Rch & Prof#=Stream0619,Reach-1,7
Up Type=0
Dn Type=3
Dn Slope=0.005

--- Stream0619.g01 (geometry) ---

Geom Title=Existing Conditions

River Reach=Stream0619,Reach-1
Reach XY= 30
      2366775.00     13600525.00      2366854.79     13600605.50
      2366876.45     13600621.51      2366899.89     13600625.27
      2367009.84     13600625.40      2367034.80     13600635.48
      2367348.18     13600948.71      2367372.70     13600969.17
      2367427.17     13600981.14      2367465.33     13601014.20
      2367480.93     13601022.75      2367600.11     13601024.73
      2367623.53     13601028.56      2367641.75     13601041.47
      2367722.58     13601119.46      2367745.06     13601124.86
      2367809.79     13601125.52      2367831.19     13601132.86
      2367914.22     13601215.31      2367922.45     13601231.08
      2367930.75     13601277.54      2367947.86     13601298.84
      2367972.45     13601319.27      2368023.22     13601329.23
      2368068.92     13601366.91      2368085.50     13601373.80
      2368269.08     13601377.23      2368326.69     13601420.92
      2368381.15     13601432.91      2368425.00     13601475.00

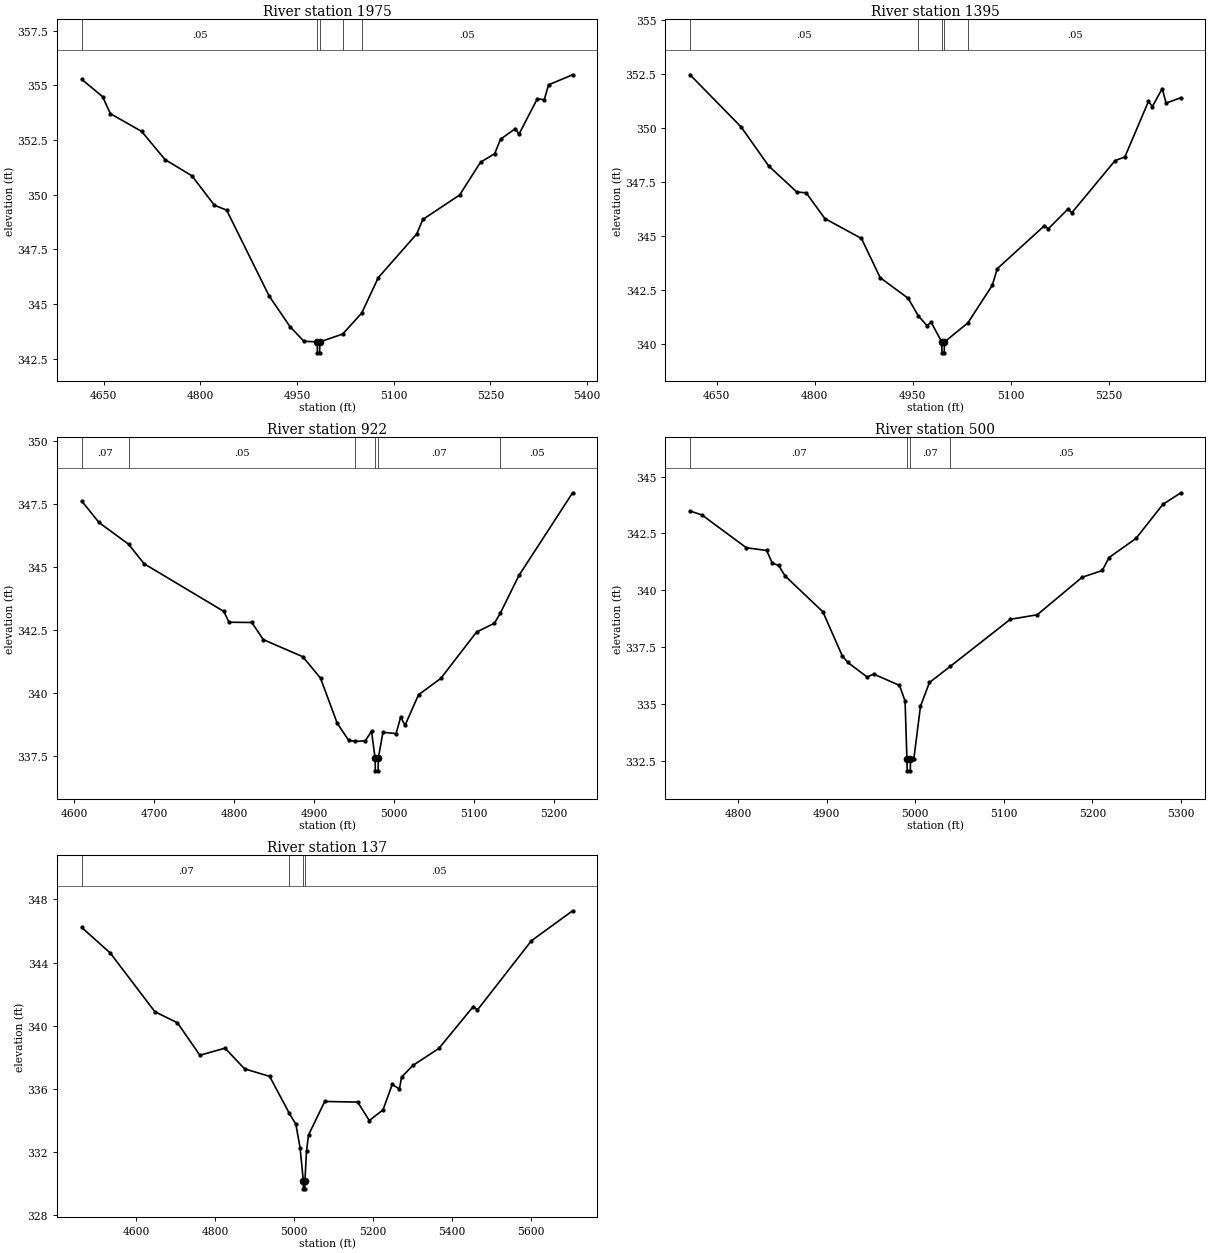
Type RM Length L Ch R = 1,1975,580,580,580
BEGIN DESCRIPTION:
Stream0619 4.0
END DESCRIPTION:
XS GIS Cut Line= 3
      2366675.00     13600925.01      2366815.58     13600573.92
      2366975.00     13600225.00
#Sta/Elev= 30
  4615.8  355.27  4648.1  354.48  4660.2  353.70  4708.7  352.89  4745.1  351.60
  4786.7  350.86  4821.7  349.51  4840.6  349.29  4906.6  345.36  4939.0  343.96
  4960.5  343.29  4981.2  343.26  4981.5  342.76  4985.0  342.76  4985.2  343.26
  5020.8  343.62  5050.3  344.58  5076.0  346.20  5135.7  348.20  5145.1  348.86
  5202.2  349.98  5234.7  351.48  5256.7  351.87  5265.7  352.53  5288.8  353.02
  5294.3  352.76  5322.8  354.38  5333.6  354.34  5340.3  355.02  5377.6  355.48
#Mann=5,-1,0
  4615.8    0.05       0  4981.2    0.05       0  4985.2    0.05       0
  5020.8    0.07       0  5050.3    0.05       0
Bank Sta=4981.2,4985.2
Exp/Cntr=0.3,0.1

Type RM Length L Ch R = 1,1395,473,473,473
BEGIN DESCRIPTION:
Stream0619 3.0
END DESCRIPTION:
XS GIS Cut Line= 3
      2366974.99     13601125.01      2367275.00     13600875.00
      2367475.01     13600574.98
#Sta/Elev= 30
  4609.5  352.46  4687.6  350.05  4729.9  348.24  4772.9  347.04  4787.2  347.00
  4815.8  345.81  4871.8  344.89  4900.4  343.08  4943.4  342.12  4958.6  341.32
  4972.0  340.86  4978.5  341.01  4994.8  340.10  4995.0  339.60  4998.5  339.60
  4998.8  340.10  5034.8  340.99  5072.1  342.73  5079.6  343.49  5151.8  345.48
  5157.8  345.34  5187.8  346.25  5193.8  346.08  5259.9  348.49  5274.9  348.66
  5311.0  351.23  5317.0  350.99  5332.0  351.82  5338.0  351.15  5360.6  351.40
#Mann=5,-1,0
  4609.5    0.05       0  4958.6    0.07       0  4994.8    0.05       0
  4998.8    0.07       0  5034.8    0.05       0
Bank Sta=4994.8,4998.8
Exp/Cntr=0.3,0.1

Type RM Length L Ch R = 1,922,422,422,422
BEGIN DESCRIPTION:
Stream0619 2.0
END DESCRIPTION:
XS GIS Cut Line= 3
      2367425.00     13601375.00      2367675.00     13601075.00
      2367774.99     13600875.01
#Sta/Elev= 30
  4609.5  347.63  4631.0  346.78  4668.0  345.92  4687.6  345.14  4787.2  343.25
  4793.7  342.82  4822.3  342.81  4836.6  342.13  4886.1  341.45  4908.2  340.60
  4929.1  338.81  4943.4  338.13  4951.4  338.09  4964.2  338.11  4972.0  338.49
  4976.5  337.42  4976.8  336.92  4980.3  336.92  4980.5  337.42  4986.3  338.45
  5002.8  338.40  5008.4  339.05  5014.0  338.73  5030.8  339.94  5058.7  340.59
  5103.4  342.43  5125.8  342.78  5133.0  343.17  5156.5  344.68  5223.6  347.96
#Mann=6,-1,0
  4609.5    0.07       0  4668.0    0.05       0  4951.4    0.07       0
  4976.5    0.05       0  4980.5    0.07       0  5133.0    0.05       0
Bank Sta=4976.5,4980.5
Exp/Cntr=0.3,0.1

Type RM Length L Ch R = 1,500,363,363,363
BEGIN DESCRIPTION:
Stream0619 1.0
END DESCRIPTION:
XS GIS Cut Line= 3
      2367824.97     13601525.04      2367975.00     13601325.00
      2368025.00     13601024.98
#Sta/Elev= 30
  4745.7  343.49  4759.3  343.31  4809.3  341.87  4832.2  341.75  4838.5  341.20
  4845.7  341.09  4853.0  340.63  4895.7  339.05  4917.6  337.11  4923.9  336.82
  4945.7  336.18  4953.0  336.31  4982.2  335.81  4988.5  335.12  4990.6  332.55
  4990.9  332.05  4994.4  332.05  4994.6  332.55  4998.3  332.55  5005.9  334.89
  5016.0  335.94  5039.6  336.65  5107.3  338.72  5137.7  338.92  5188.4  340.57
  5211.2  340.87  5218.8  341.44  5249.2  342.28  5279.6  343.78  5299.9  344.29
#Mann=4,-1,0
  4745.7    0.07       0  4990.6    0.05       0  4994.6    0.07       0
  5039.6    0.05       0
Bank Sta=4990.6,4994.6
Exp/Cntr=0.3,0.1

Type RM Length L Ch R = 1,137,0,0,0
BEGIN DESCRIPTION:
XS7281
END DESCRIPTION:
XS GIS Cut Line= 4
      2367972.12     13601823.83      2368301.27     13601441.32
      2368363.54     13601232.25      2368159.45     13600753.08
#Sta/Elev= 30
  4462.5  346.22  4534.7  344.60  4647.7  340.88  4704.8  340.18  4761.8  338.12
  4825.5  338.57  4874.9  337.26  4938.5  336.78  4988.5  334.43  5005.0  333.74
  5015.5  332.27  5023.9  330.15  5024.1  329.65  5027.6  329.65  5027.9  330.15
  5031.9  332.04  5037.1  333.07  5078.1  335.19  5161.5  335.15  5191.0  333.98
  5225.8  334.66  5249.1  336.27  5267.3  335.98  5272.8  336.74  5301.8  337.48
  5367.1  338.55  5454.5  341.21  5464.9  340.99  5601.7  345.38  5706.1  347.28
#Mann=4,-1,0
  4462.5    0.07       0  4988.5    0.05       0  5023.9    0.05       0
  5027.9    0.05       0
Bank Sta=5023.9,5027.9
Exp/Cntr=0.3,0.1

Chan Stop Cuts=-1