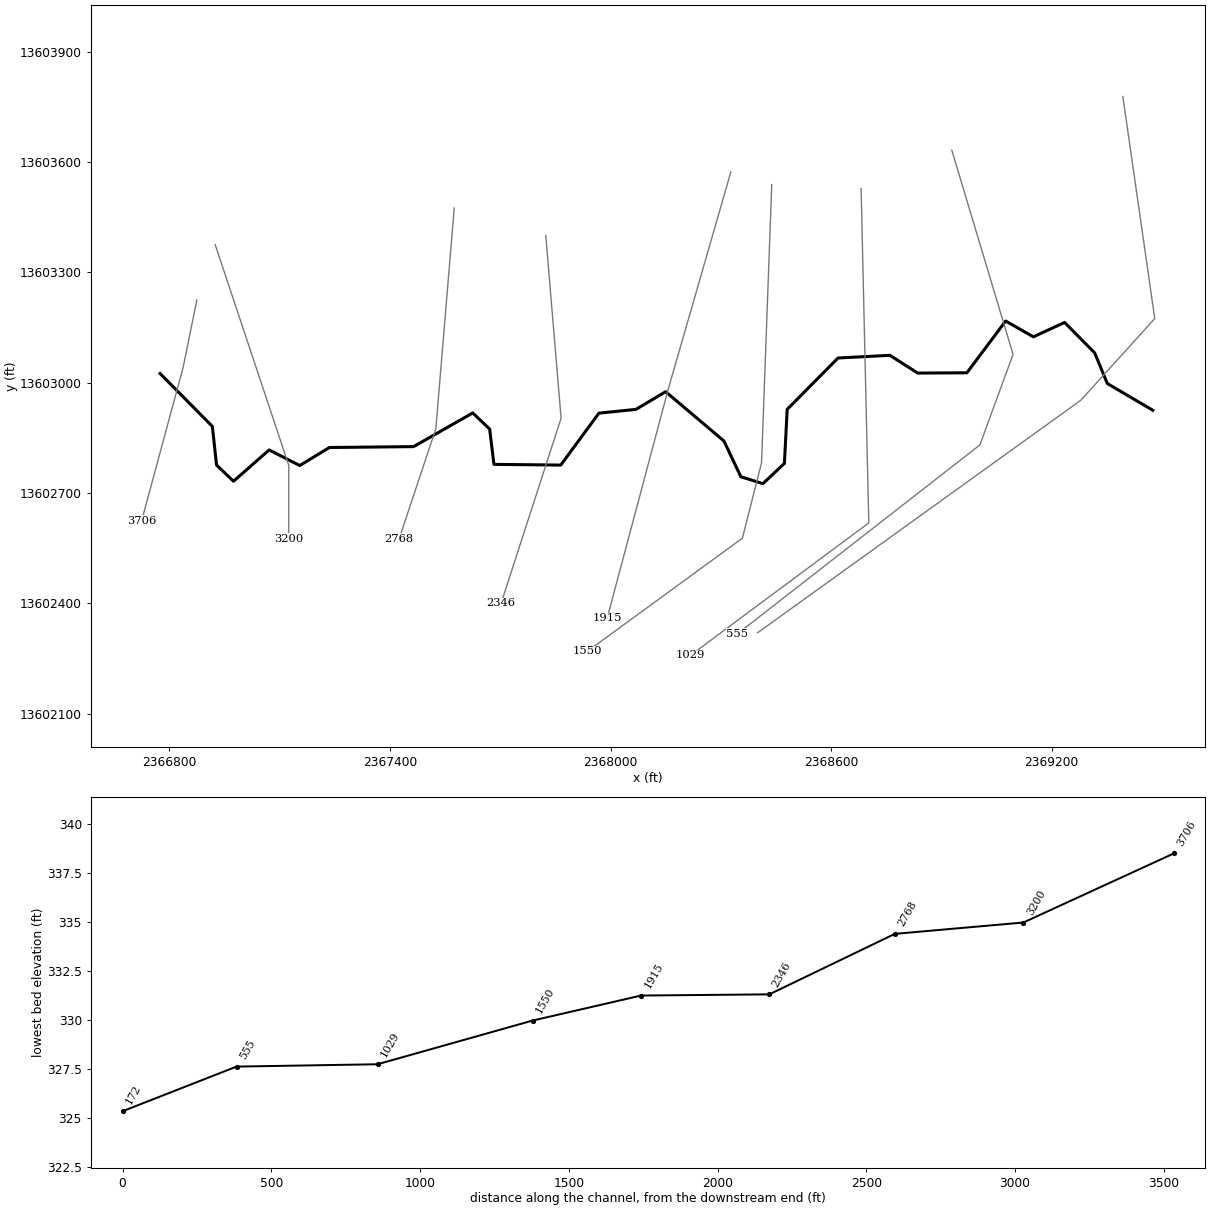
--- Stream0620.prj (project) ---

Proj Title=Stream0620 Base Level Engineering
Current Plan=p01
Default Exp/Contr=0.3,0.1
English Units
Geom File=g01
Flow File=f01
Plan File=p01
BEGIN DESCRIPTION:
Stream0620
END DESCRIPTION:

--- Stream0620.p01 (plan) ---

Plan Title=Multiple Run
Short Identifier=Multiple
Geom File=g01
Flow File=f01
Subcritical Flow
K Sum by GR= 0
Std Step Tol= 0.01
Critical Tol= 0.01
Num of Std Step Trials= 20
Max Error Tol= 0.3
Flow Tol Ratio= 0.001
Split Flow NTrial= 30
Split Flow Tol= 0.02
Split Flow Ratio= 0.02
Log Output Level= 0
Friction Slope Method= 1
Unsteady Friction Slope Method= 2
Unsteady Bridges Friction Slope Method= 1
Parabolic Critical Depth
Global Vel Dist=  1 , 1 , 1
Global Log Level= 0
CheckData=True
Encroach Param= -1, 0, 0, 0
BEGIN DESCRIPTION:
Multiple Run
END DESCRIPTION:

--- Stream0620.f01 (steady flow) ---

Flow Title=Multiple
Number of Profiles=7
Profile Names=10-year,25-year,50-year,1pct_min,100-year,1pct_plu,500-year
River Rch & RM= Stream0620,Reach-1,3706
     367     574     755     481     960    1915    1537
Boundary for River Rch & Prof#=Stream0620,Reach-1,1
Up Type=0
Dn Type=3
Dn Slope=0.005
Boundary for River Rch & Prof#=Stream0620,Reach-1,2
Up Type=0
Dn Type=3
Dn Slope=0.005
Boundary for River Rch & Prof#=Stream0620,Reach-1,3
Up Type=0
Dn Type=3
Dn Slope=0.005
Boundary for River Rch & Prof#=Stream0620,Reach-1,4
Up Type=0
Dn Type=3
Dn Slope=0.005
Boundary for River Rch & Prof#=Stream0620,Reach-1,5
Up Type=0
Dn Type=3
Dn Slope=0.005
Boundary for River Rch & Prof#=Stream0620,Reach-1,6
Up Type=0
Dn Type=3
Dn Slope=0.005
Boundary for River Rch & Prof#=Stream0620,Reach-1,7
Up Type=0
Dn Type=3
Dn Slope=0.005

--- Stream0620.g01 (geometry) ---

Geom Title=Existing Conditions

River Reach=Stream0620,Reach-1
Reach XY= 30
      2366775.00     13603025.00      2366917.14     13602881.17
      2366928.61     13602776.01      2366974.76     13602731.99
      2367071.59     13602817.15      2367154.79     13602774.79
      2367235.50     13602823.76      2367464.50     13602826.20
      2367625.33     13602917.81      2367671.36     13602873.90
      2367682.97     13602777.94      2367864.72     13602775.98
      2367968.55     13602917.25      2368069.03     13602927.39
      2368150.04     13602975.50      2368308.35     13602841.66
      2368354.54     13602744.25      2368414.48     13602725.46
      2368473.01     13602780.62      2368480.47     13602927.45
      2368618.81     13603067.19      2368759.78     13603074.49
      2368835.51     13603026.21      2368969.32     13603026.97
      2369074.70     13603167.74      2369150.00     13603124.79
      2369235.08     13603163.90      2369316.83     13603081.07
      2369351.14     13602997.83      2369475.00     13602925.00

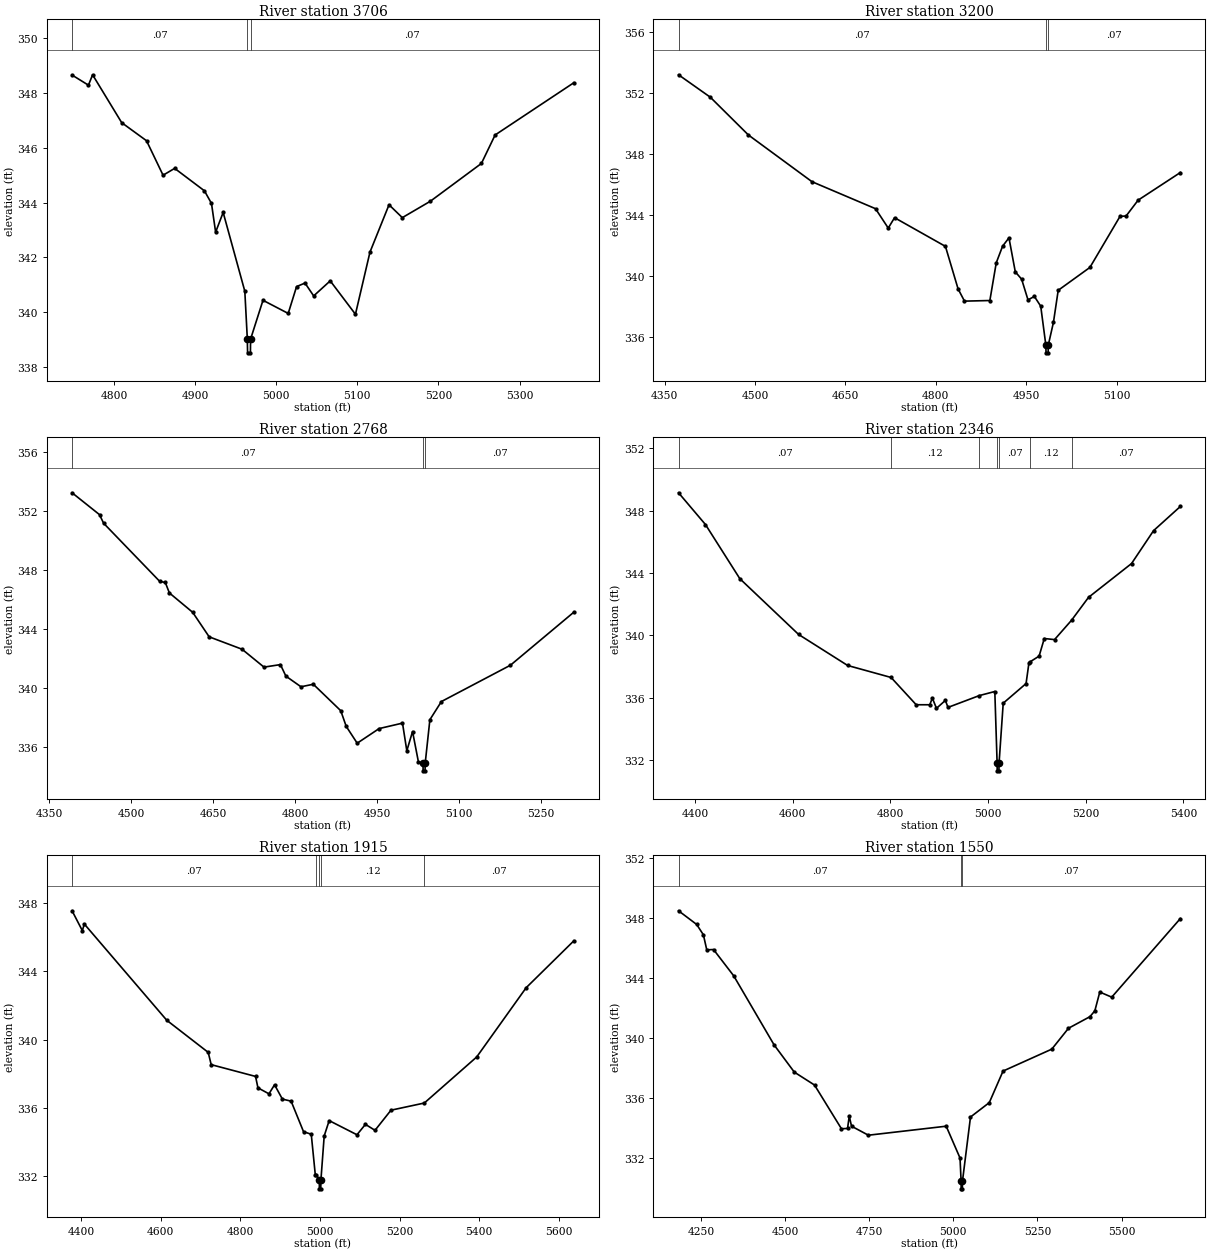
Type RM Length L Ch R = 1,3706,506,506,506
BEGIN DESCRIPTION:
Stream0620 5.0
END DESCRIPTION:
XS GIS Cut Line= 3
      2366874.99     13603224.97      2366837.85     13603042.36
      2366725.00     13602625.00
#Sta/Elev= 30
  4748.3  348.66  4768.5  348.29  4773.6  348.67  4809.5  346.92  4840.1  346.26
  4860.5  345.00  4874.8  345.25  4911.5  344.43  4920.2  343.97  4925.3  342.92
  4934.6  343.64  4961.3  340.76  4964.4  339.01  4964.7  338.51  4968.2  338.51
  4968.4  339.01  4983.7  340.43  5014.8  339.95  5025.1  340.93  5035.5  341.06
  5046.2  340.59  5066.6  341.14  5097.7  339.92  5115.6  342.19  5139.1  343.92
  5155.5  343.45  5190.1  344.05  5253.0  345.43  5269.9  346.47  5367.0  348.38
#Mann=3,-1,0
  4748.3    0.07       0  4964.4    0.05       0  4968.4    0.07       0
Bank Sta=4964.4,4968.4
Exp/Cntr=0.3,0.1

Type RM Length L Ch R = 1,3200,432,432,432
BEGIN DESCRIPTION:
Stream0620 4.0
END DESCRIPTION:
XS GIS Cut Line= 3
      2366924.99     13603375.04      2367125.00     13602775.00
      2367125.00     13602575.00
#Sta/Elev= 30
  4373.2  353.21  4425.9  351.74  4489.2  349.26  4594.6  346.20  4700.0  344.43
  4721.1  343.16  4731.6  343.84  4816.0  341.96  4837.0  339.17  4847.6  338.37
  4889.7  338.41  4900.3  340.88  4910.8  341.97  4921.4  342.52  4931.9  340.29
  4942.4  339.81  4953.0  338.45  4963.5  338.68  4974.1  338.04  4982.6  335.48
  4982.9  334.98  4986.4  334.98  4986.6  335.48  4995.2  336.98  5003.1  339.08
  5055.7  340.58  5105.7  343.93  5115.7  343.95  5135.7  344.99  5205.7  346.80
#Mann=3,-1,0
  4373.2    0.07       0  4982.6    0.05       0  4986.6    0.07       0
Bank Sta=4982.6,4986.6
Exp/Cntr=0.3,0.1

Type RM Length L Ch R = 1,2768,422,422,422
BEGIN DESCRIPTION:
Stream0620 3.0
END DESCRIPTION:
XS GIS Cut Line= 3
      2367575.00     13603474.99      2367525.00     13602875.00
      2367425.00     13602574.99
#Sta/Elev= 30
  4391.6  353.22  4441.8  351.74  4449.3  351.16  4552.1  347.22  4562.2  347.15
  4569.7  346.44  4612.3  345.13  4642.5  343.47  4702.7  342.63  4742.8  341.42
  4772.9  341.59  4782.9  340.81  4810.5  340.09  4833.1  340.26  4883.3  338.47
  4893.3  337.41  4913.4  336.27  4953.5  337.26  4996.3  337.63  5004.2  335.76
  5014.7  337.06  5025.3  335.03  5033.8  334.90  5034.1  334.40  5037.6  334.40
  5037.8  334.90  5046.4  337.86  5067.5  339.09  5193.9  341.55  5309.9  345.14
#Mann=3,-1,0
  4391.6    0.07       0  5033.8    0.05       0  5037.8    0.07       0
Bank Sta=5033.8,5037.8
Exp/Cntr=0.3,0.1

Type RM Length L Ch R = 1,2346,431,431,431
BEGIN DESCRIPTION:
Stream0620 2.0
END DESCRIPTION:
XS GIS Cut Line= 3
      2367823.95     13603400.04      2367865.63     13602903.47
      2367702.42     13602399.98
#Sta/Elev= 30
  4366.2  349.15  4421.4  347.11  4491.7  343.64  4612.1  340.06  4712.5  338.07
  4801.5  337.30  4852.9  335.55  4880.7  335.55  4886.0  335.98  4894.4  335.32
  4912.7  335.83  4918.0  335.38  4982.3  336.14  5013.9  336.40  5018.6  331.81
  5018.8  331.31  5022.3  331.31  5022.6  331.81  5031.1  335.65  5077.9  336.91
  5083.7  338.22  5086.9  338.32  5104.6  338.67  5115.2  339.80  5136.2  339.73
  5171.0  340.97  5205.8  342.44  5293.9  344.61  5339.0  346.72  5393.8  348.27
#Mann=7,-1,0
  4366.2    0.07       0  4801.5    0.12       0  4982.3    0.07       0
  5018.6    0.05       0  5022.6    0.07       0  5086.9    0.12       0
  5171.0    0.07       0
Bank Sta=5018.6,5022.6
Exp/Cntr=0.3,0.1

Type RM Length L Ch R = 1,1915,365,365,365
BEGIN DESCRIPTION:
XS7282
END DESCRIPTION:
XS GIS Cut Line= 3
      2368327.42     13603573.57      2368157.29     13602983.33
      2367990.86     13602359.21
#Sta/Elev= 30
  4377.5  347.55  4403.2  346.39  4408.4  346.77  4615.4  341.13  4719.4  339.25
  4726.9  338.53  4838.3  337.84  4844.3  337.17  4872.0  336.82  4886.0  337.35
  4905.7  336.51  4927.6  336.39  4958.8  334.60  4978.2  334.45  4988.3  332.08
  4991.3  332.08  4998.4  331.75  4998.6  331.25  5002.1  331.25  5002.4  331.75
  5010.7  334.35  5023.2  335.25  5093.0  334.42  5114.2  335.03  5138.3  334.68
  5178.4  335.86  5262.1  336.28  5393.7  338.98  5517.9  343.04  5637.7  345.79
#Mann=5,-1,0
  4377.5    0.07       0  4991.3    0.12       0  4998.4    0.05       0
  5002.4    0.12       0  5262.1    0.07       0
Bank Sta=4998.4,5002.4
Exp/Cntr=0.3,0.1

Type RM Length L Ch R = 1,1550,521,521,521
BEGIN DESCRIPTION:
XS7283
END DESCRIPTION:
XS GIS Cut Line= 4
      2368438.54     13603538.89      2368410.76     13602781.94
      2368358.68     13602577.08      2367936.43     13602269.05
#Sta/Elev= 30
  4183.2  348.48  4237.1  347.57  4257.1  346.88  4267.1  345.88  4287.2  345.90
  4347.2  344.15  4467.3  339.55  4527.3  337.74  4587.4  336.88  4667.4  333.97
  4685.6  333.99  4690.6  334.81  4697.4  334.14  4747.5  333.54  4978.8  334.14
  5019.9  332.02  5023.1  330.47  5023.3  329.97  5026.8  329.97  5027.1  330.47
  5051.0  334.75  5106.9  335.71  5147.8  337.81  5292.7  339.27  5342.3  340.66
  5406.0  341.43  5420.6  341.82  5435.3  343.07  5470.8  342.73  5674.7  347.96
#Mann=3,-1,0
  4183.2    0.07       0  5023.1    0.05       0  5027.1    0.07       0
Bank Sta=5023.1,5027.1
Exp/Cntr=0.3,0.1

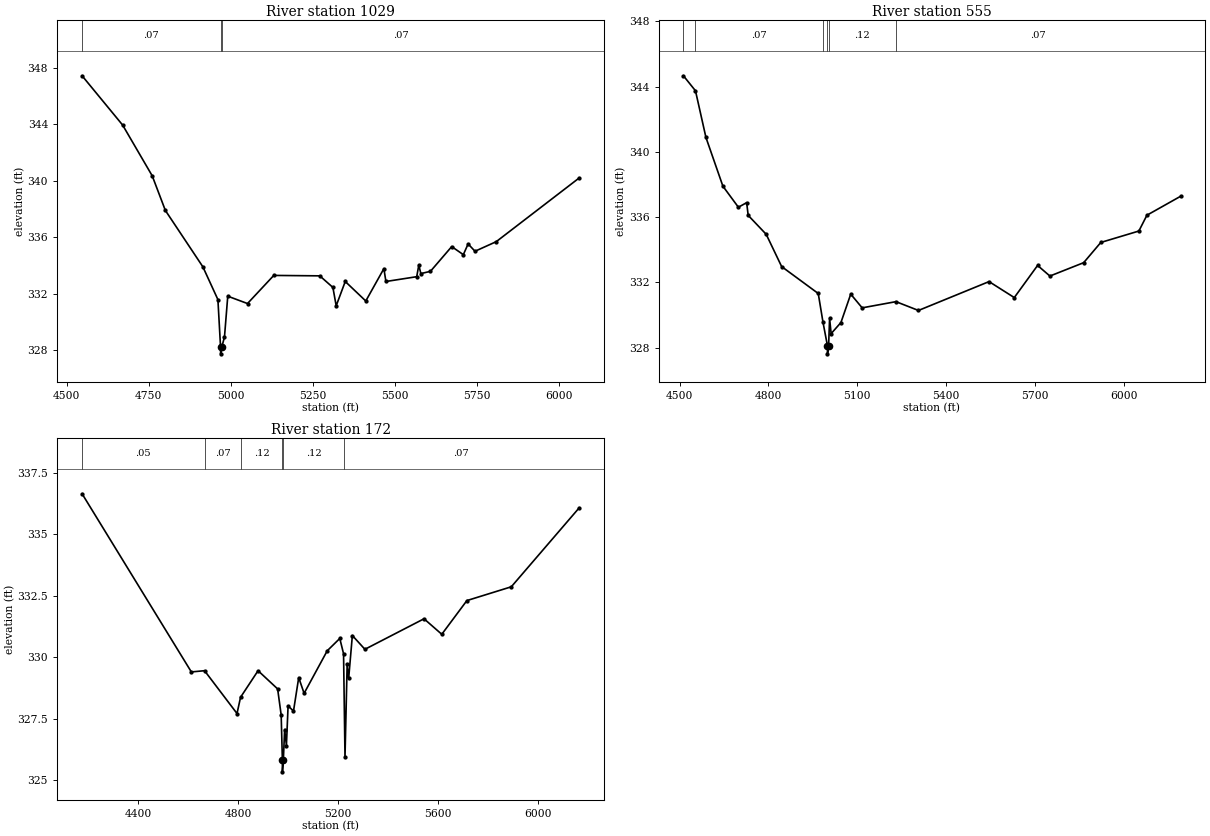
Type RM Length L Ch R = 1,1029,474,474,474
BEGIN DESCRIPTION:
XS7284
END DESCRIPTION:
XS GIS Cut Line= 3
      2368681.60     13603528.42      2368702.43     13602618.75
      2368217.91     13602258.82
#Sta/Elev= 30
  4546.9  347.42  4670.4  343.93  4760.4  340.34  4800.4  337.89  4914.6  333.90
  4960.4  331.58  4968.4  328.24  4968.7  327.74  4972.4  328.24  4980.4  328.93
  4990.4  331.82  5050.5  331.30  5130.5  333.29  5270.5  333.26  5310.5  332.44
  5320.5  331.14  5348.1  332.86  5410.6  331.48  5465.7  333.77  5471.9  332.86
  5565.7  333.20  5572.0  334.02  5578.3  333.42  5607.5  333.58  5672.2  335.33
  5707.6  334.76  5722.2  335.52  5743.1  335.00  5807.8  335.68  6060.4  340.19
#Mann=3,-1,0
  4546.9    0.07       0  4968.4    0.05       0  4972.4    0.07       0
Bank Sta=4968.4,4972.4
Exp/Cntr=0.3,0.1

Type RM Length L Ch R = 1,555,383,383,383
BEGIN DESCRIPTION:
XS7285
END DESCRIPTION:
XS GIS Cut Line= 4
      2368928.12     13603632.67      2369094.79     13603077.08
      2369004.51     13602830.56      2368344.82     13602316.69
#Sta/Elev= 30
  4512.8  344.67  4553.5  343.75  4588.8  340.89  4646.1  337.90  4698.4  336.61
  4726.3  336.89  4731.5  336.11  4792.3  334.95  4844.5  332.97  4968.1  331.32
  4984.1  329.56  4999.1  328.12  4999.3  327.62  5003.1  328.12  5006.4  329.79
  5011.6  328.86  5044.7  329.54  5077.8  331.28  5116.4  330.44  5230.5  330.82
  5306.5  330.28  5544.9  332.05  5630.1  331.07  5708.8  333.04  5750.4  332.39
  5864.4  333.21  5922.3  334.45  6050.8  335.15  6078.0  336.12  6191.6  337.28
#Mann=6,-1,0
  4512.8    0.05       0  4553.5    0.07       0  4984.1    0.12       0
  4999.1    0.05       0  5003.1    0.12       0  5230.5    0.07       0
Bank Sta=4999.1,5003.1
Exp/Cntr=0.3,0.1

Type RM Length L Ch R = 1,172,0,0,0
BEGIN DESCRIPTION:
XS7286
END DESCRIPTION:
XS GIS Cut Line= 4
      2369393.41     13603778.45      2369480.21     13603174.31
      2369278.82     13602952.08      2368400.35     13602320.14
#Sta/Elev= 30
  4174.5  336.64  4612.4  329.40  4665.3  329.45  4795.4  327.71  4809.6  328.37
  4879.8  329.45  4958.2  328.71  4972.4  327.65  4977.2  325.84  4977.4  325.34
  4981.2  325.84  4986.3  327.06  4993.4  326.41  5000.1  328.02  5021.8  327.81
  5042.7  329.17  5064.3  328.53  5157.0  330.26  5207.3  330.76  5222.4  330.14
  5228.2  325.94  5236.8  329.71  5242.9  329.14  5257.7  330.88  5308.0  330.32
  5544.9  331.56  5616.1  330.93  5716.7  332.30  5894.7  332.86  6166.9  336.07
#Mann=6,-1,0
  4174.5    0.05       0  4665.3    0.07       0  4809.6    0.12       0
  4977.2    0.05       0  4981.2    0.12       0  5222.4    0.07       0
Bank Sta=4977.2,4981.2
Exp/Cntr=0.3,0.1

Chan Stop Cuts=-1