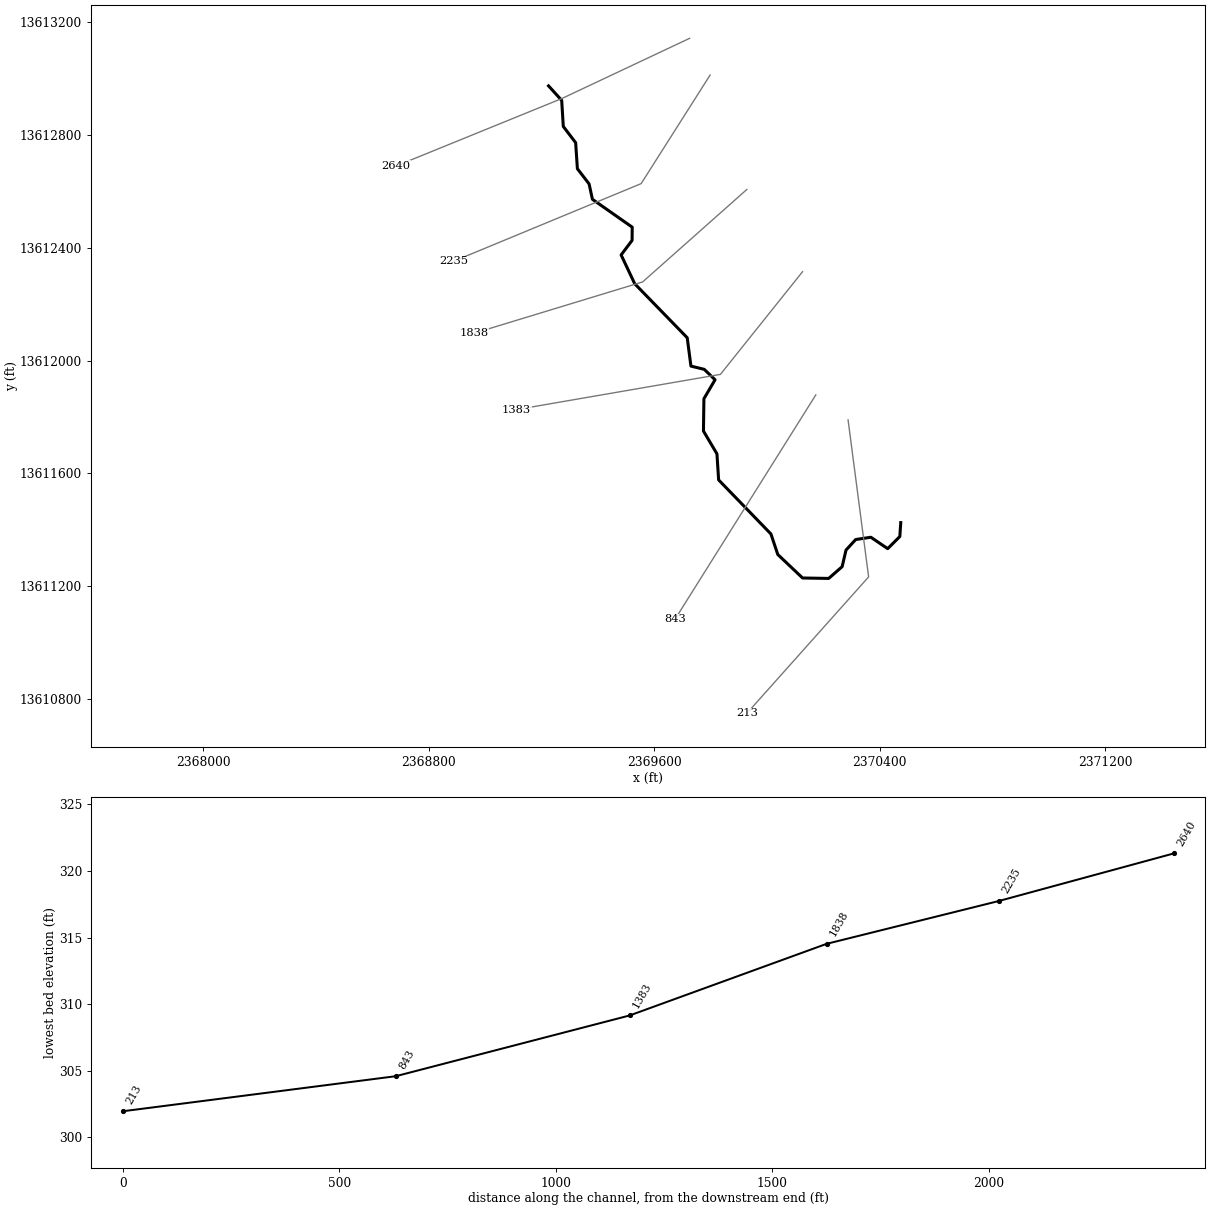
--- Stream0623.prj (project) ---

Proj Title=Stream0623 Base Level Engineering
Current Plan=p01
Default Exp/Contr=0.3,0.1
English Units
Geom File=g01
Flow File=f01
Plan File=p01
BEGIN DESCRIPTION:
Stream0623
END DESCRIPTION:

--- Stream0623.p01 (plan) ---

Plan Title=Multiple Run
Short Identifier=Multiple
Geom File=g01
Flow File=f01
Subcritical Flow
K Sum by GR= 0
Std Step Tol= 0.01
Critical Tol= 0.01
Num of Std Step Trials= 20
Max Error Tol= 0.3
Flow Tol Ratio= 0.001
Split Flow NTrial= 30
Split Flow Tol= 0.02
Split Flow Ratio= 0.02
Log Output Level= 0
Friction Slope Method= 1
Unsteady Friction Slope Method= 2
Unsteady Bridges Friction Slope Method= 1
Parabolic Critical Depth
Global Vel Dist=  1 , 1 , 1
Global Log Level= 0
CheckData=True
Encroach Param= -1, 0, 0, 0
BEGIN DESCRIPTION:
Multiple Run
END DESCRIPTION:

--- Stream0623.f01 (steady flow) ---

Flow Title=Multiple
Number of Profiles=7
Profile Names=10-year,25-year,50-year,1pct_min,100-year,1pct_plu,500-year
River Rch & RM= Stream0623,Reach-1,2640
     420     667     886     571    1139    2273    1865
Boundary for River Rch & Prof#=Stream0623,Reach-1,1
Up Type=0
Dn Type=3
Dn Slope=0.005
Boundary for River Rch & Prof#=Stream0623,Reach-1,2
Up Type=0
Dn Type=3
Dn Slope=0.005
Boundary for River Rch & Prof#=Stream0623,Reach-1,3
Up Type=0
Dn Type=3
Dn Slope=0.005
Boundary for River Rch & Prof#=Stream0623,Reach-1,4
Up Type=0
Dn Type=3
Dn Slope=0.005
Boundary for River Rch & Prof#=Stream0623,Reach-1,5
Up Type=0
Dn Type=3
Dn Slope=0.005
Boundary for River Rch & Prof#=Stream0623,Reach-1,6
Up Type=0
Dn Type=3
Dn Slope=0.005
Boundary for River Rch & Prof#=Stream0623,Reach-1,7
Up Type=0
Dn Type=3
Dn Slope=0.005

--- Stream0623.g01 (geometry) ---

Geom Title=Existing Conditions

River Reach=Stream0623,Reach-1
Reach XY= 30
      2369225.00     13612975.00      2369271.61     13612923.60
      2369277.32     13612830.96      2369321.15     13612773.40
      2369327.33     13612680.96      2369368.85     13612627.15
      2369380.73     13612572.45      2369521.93     13612473.57
      2369521.44     13612426.68      2369482.56     13612375.00
      2369530.81     13612272.71      2369717.12     13612081.12
      2369730.32     13611980.47      2369777.46     13611968.99
      2369815.94     13611932.00      2369776.38     13611864.57
      2369774.77     13611749.93      2369822.64     13611669.02
      2369828.61     13611576.50      2370014.22     13611384.68
      2370038.62     13611311.76      2370126.49     13611228.45
      2370219.29     13611226.88      2370266.97     13611268.64
      2370280.76     13611327.59      2370315.01     13611364.93
      2370368.92     13611373.04      2370428.61     13611332.53
      2370471.73     13611375.63      2370475.00     13611425.00

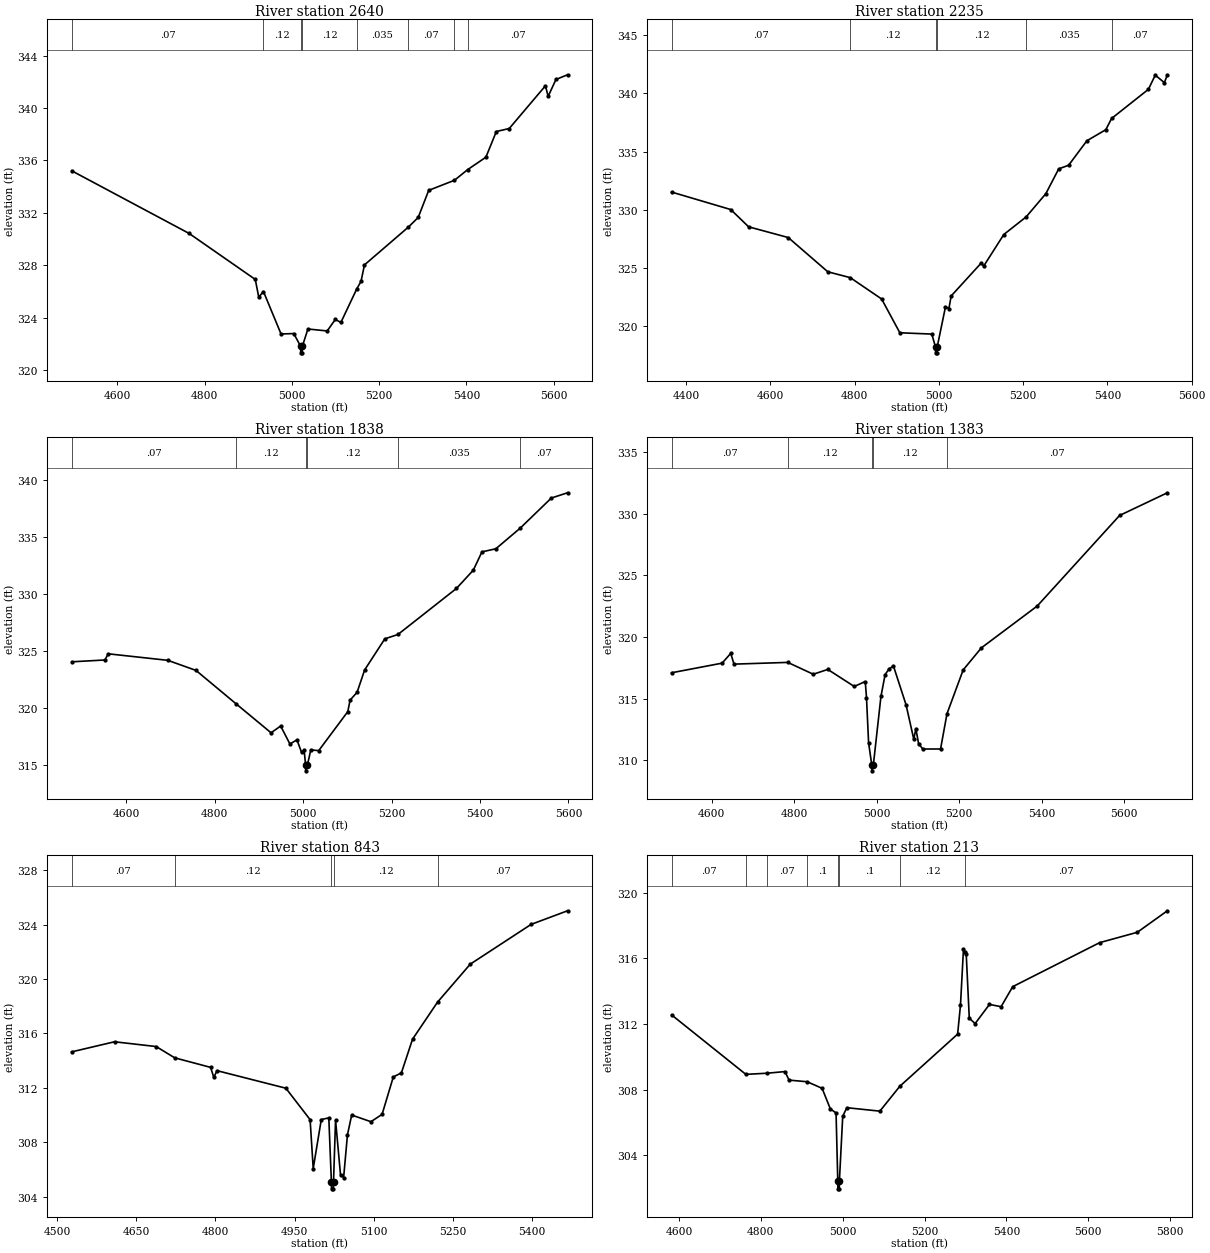
Type RM Length L Ch R = 1,2640,405,405,405
BEGIN DESCRIPTION:
XS7292
END DESCRIPTION:
XS GIS Cut Line= 3
      2369725.54     13613143.76      2369272.40     13612930.21
      2368683.83     13612690.62
#Sta/Elev= 30
  4495.4  335.21  4764.5  330.43  4916.1  326.92  4924.0  325.57  4934.8  326.00
  4975.1  322.76  5004.3  322.79  5020.0  321.82  5020.2  321.32  5023.7  321.32
  5024.0  321.82  5036.7  323.14  5080.9  322.99  5099.5  323.87  5112.3  323.64
  5148.4  326.18  5158.5  326.78  5166.3  328.03  5266.8  330.91  5289.5  331.65
  5313.6  333.72  5372.7  334.49  5402.8  335.30  5444.7  336.25  5468.6  338.21
  5498.2  338.44  5581.2  341.70  5587.4  340.89  5605.2  342.18  5631.8  342.54
#Mann=8,-1,0
  4495.4    0.07       0  4934.8    0.12       0  5020.0    0.05       0
  5024.0    0.12       0  5148.4   0.035       0  5266.8    0.07       0
  5372.7   0.035       0  5402.8    0.07       0
Bank Sta=5020,5024
Exp/Cntr=0.3,0.1

Type RM Length L Ch R = 1,2235,397,397,397
BEGIN DESCRIPTION:
XS7291
END DESCRIPTION:
XS GIS Cut Line= 3
      2369798.45     13613013.56      2369553.65     13612628.13
      2368888.51     13612352.72
#Sta/Elev= 30
  4365.8  331.53  4506.2  330.03  4548.6  328.55  4642.6  327.63  4736.6  324.69
  4789.8  324.19  4864.2  322.36  4907.5  319.46  4983.3  319.35  4992.1  318.24
  4992.4  317.74  4995.9  317.74  4996.1  318.24  5015.8  321.69  5023.9  321.54
  5029.3  322.62  5101.0  325.46  5106.4  325.18  5154.2  327.89  5207.2  329.40
  5253.9  331.39  5284.5  333.52  5308.0  333.83  5351.3  335.93  5396.3  336.88
  5409.9  337.84  5497.3  340.34  5513.6  341.56  5535.3  340.91  5542.3  341.59
#Mann=6,-1,0
  4365.8    0.07       0  4789.8    0.12       0  4992.1    0.05       0
  4996.1    0.12       0  5207.2   0.035       0  5409.9    0.07       0
Bank Sta=4992.1,4996.1
Exp/Cntr=0.3,0.1

Type RM Length L Ch R = 1,1838,455,455,455
BEGIN DESCRIPTION:
XS7290
END DESCRIPTION:
XS GIS Cut Line= 3
      2369928.67     13612607.31      2369558.85     13612279.17
      2368959.98     13612096.90
#Sta/Elev= 30
  4477.4  324.07  4552.3  324.23  4559.8  324.77  4694.4  324.20  4758.0  323.32
  4849.2  320.38  4927.8  317.86  4949.5  318.45  4970.4  316.88  4986.3  317.24
  4996.7  316.15  5002.6  316.32  5005.9  315.03  5006.1  314.53  5009.9  315.03
  5017.6  316.36  5035.5  316.30  5101.2  319.71  5106.4  320.72  5122.2  321.40
  5139.3  323.36  5184.9  326.08  5214.5  326.46  5346.8  330.49  5384.9  332.09
  5404.4  333.69  5435.8  333.96  5490.7  335.76  5561.2  338.40  5597.8  338.86
#Mann=6,-1,0
  4477.4    0.07       0  4849.2    0.12       0  5005.9    0.05       0
  5009.9    0.12       0  5214.5   0.035       0  5490.7    0.07       0
Bank Sta=5005.9,5009.9
Exp/Cntr=0.3,0.1

Type RM Length L Ch R = 1,1383,540,540,540
BEGIN DESCRIPTION:
XS7289
END DESCRIPTION:
XS GIS Cut Line= 3
      2370126.57     13612315.63      2369834.90     13611951.04
      2369110.91     13611826.04
#Sta/Elev= 30
  4503.0  317.10  4625.5  317.88  4646.3  318.67  4654.3  317.80  4784.6  317.94
  4846.4  316.98  4881.6  317.37  4945.7  315.99  4972.4  316.39  4975.4  315.08
  4980.5  311.41  4988.1  309.65  4988.3  309.15  4992.1  309.65  5010.4  315.18
  5020.5  316.95  5030.2  317.42  5040.8  317.64  5071.3  314.50  5090.0  311.71
  5095.1  312.57  5101.7  311.34  5111.9  310.92  5154.9  310.92  5170.5  313.78
  5209.7  317.33  5253.9  319.12  5389.2  322.51  5588.8  329.85  5704.6  331.69
#Mann=5,-1,0
  4503.0    0.07       0  4784.6    0.12       0  4988.1    0.05       0
  4992.1    0.12       0  5170.5    0.07       0
Bank Sta=4988.1,4992.1
Exp/Cntr=0.3,0.1

Type RM Length L Ch R = 1,843,630,630,630
BEGIN DESCRIPTION:
XS7288
END DESCRIPTION:
XS GIS Cut Line= 2
      2370173.46     13611878.16      2369673.43     13611081.24
#Sta/Elev= 30
  4527.3  314.65  4608.4  315.39  4687.4  315.04  4722.7  314.21  4790.8  313.51
  4796.9  312.77  4802.8  313.27  4933.6  311.98  4979.6  309.67  4985.5  306.08
  5000.8  309.68  5015.1  309.80  5020.0  305.09  5020.2  304.59  5023.7  304.59
  5024.0  305.09  5027.9  309.63  5037.3  305.62  5043.2  305.42  5050.5  308.56
  5058.5  310.01  5095.0  309.52  5116.2  310.06  5137.5  312.81  5152.8  313.10
  5174.0  315.58  5221.4  318.30  5283.5  321.09  5399.0  324.01  5468.1  325.01
#Mann=5,-1,0
  4527.3    0.07       0  4722.7    0.12       0  5020.0    0.05       0
  5024.0    0.12       0  5221.4    0.07       0
Bank Sta=5020,5024
Exp/Cntr=0.3,0.1

Type RM Length L Ch R = 1,213,0,0,0
BEGIN DESCRIPTION:
XS7287
END DESCRIPTION:
XS GIS Cut Line= 3
      2370288.03     13611789.55      2370360.94     13611232.29
      2369928.67     13610747.94
#Sta/Elev= 30
  4582.1  312.55  4763.5  308.93  4815.6  309.00  4859.0  309.10  4869.1  308.58
  4913.4  308.48  4949.8  308.08  4969.9  306.83  4983.9  306.58  4988.1  302.46
  4988.3  301.96  4991.8  301.96  4992.1  302.46  5000.2  306.38  5010.3  306.90
  5090.9  306.69  5139.9  308.21  5280.9  311.38  5287.9  313.15  5295.2  316.56
  5299.1  316.39  5301.9  316.27  5309.4  312.35  5323.6  312.02  5358.7  313.19
  5387.1  313.05  5415.5  314.27  5627.9  316.95  5719.9  317.58  5793.3  318.89
#Mann=8,-1,0
  4582.1    0.07       0  4763.5    0.12       0  4815.6    0.07       0
  4913.4     0.1       0  4988.1    0.05       0  4992.1     0.1       0
  5139.9    0.12       0  5299.1    0.07       0
Bank Sta=4988.1,4992.1
Exp/Cntr=0.3,0.1

Chan Stop Cuts=-1