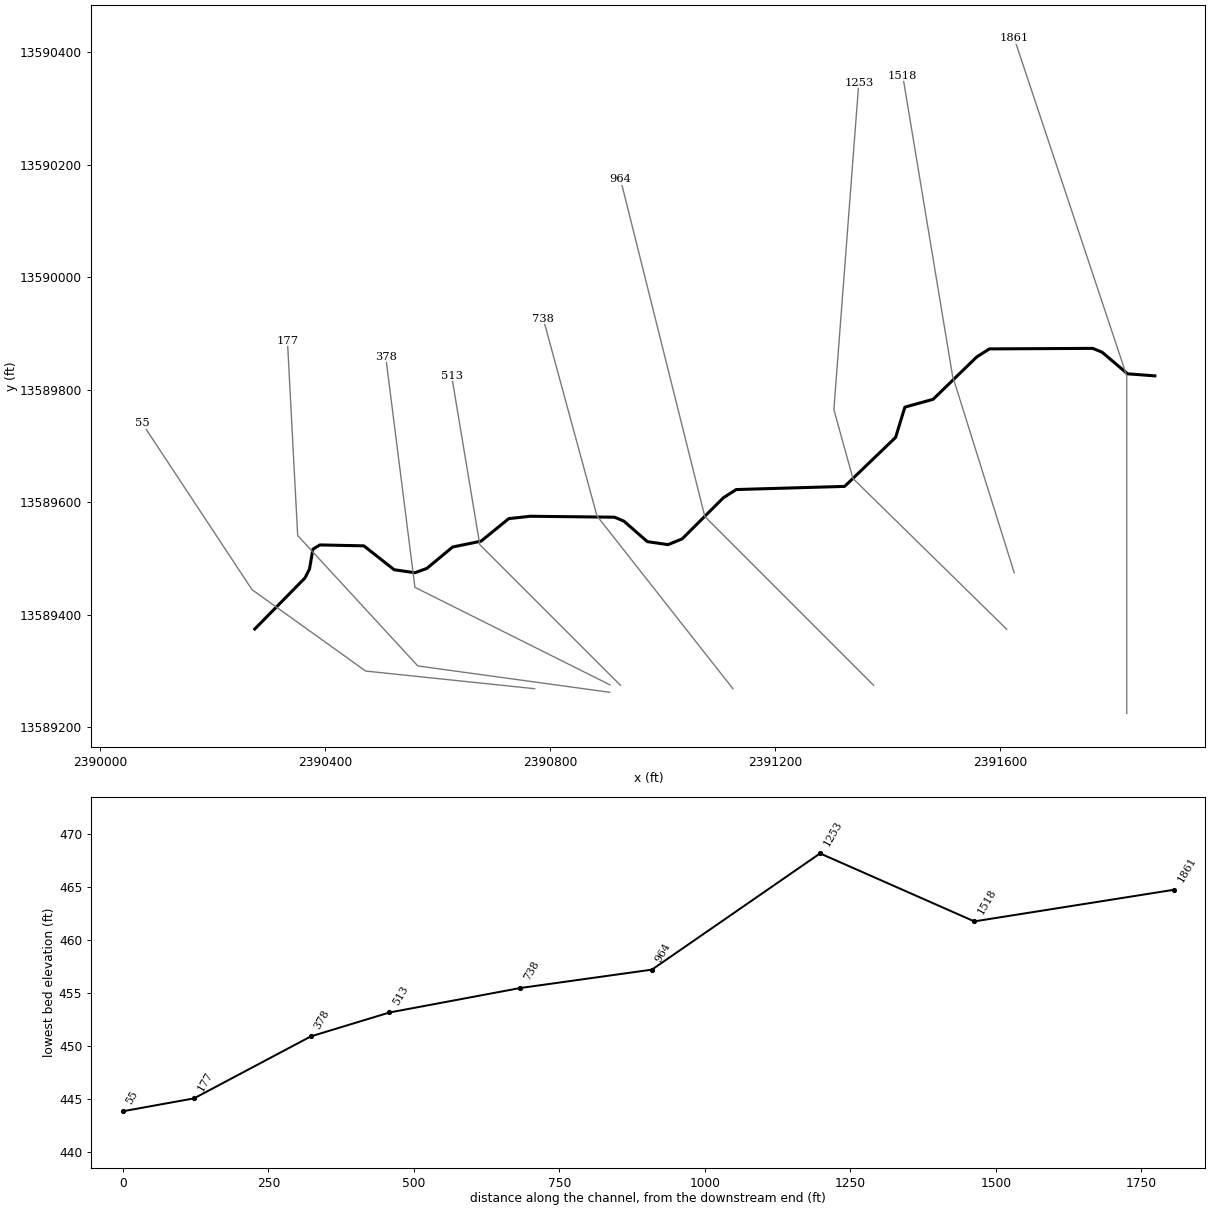
--- Stream0625.prj (project) ---

Proj Title=Stream0625 Base Level Engineering
Current Plan=p01
Default Exp/Contr=0.3,0.1
English Units
Geom File=g01
Flow File=f01
Plan File=p01
BEGIN DESCRIPTION:
Stream0625
END DESCRIPTION:

--- Stream0625.p01 (plan) ---

Plan Title=Multiple Run
Short Identifier=Multiple
Geom File=g01
Flow File=f01
Subcritical Flow
K Sum by GR= 0
Std Step Tol= 0.01
Critical Tol= 0.01
Num of Std Step Trials= 20
Max Error Tol= 0.3
Flow Tol Ratio= 0.001
Split Flow NTrial= 30
Split Flow Tol= 0.02
Split Flow Ratio= 0.02
Log Output Level= 0
Friction Slope Method= 1
Unsteady Friction Slope Method= 2
Unsteady Bridges Friction Slope Method= 1
Parabolic Critical Depth
Global Vel Dist=  1 , 1 , 1
Global Log Level= 0
CheckData=True
Encroach Param= -1, 0, 0, 0
BEGIN DESCRIPTION:
Multiple Run
END DESCRIPTION:

--- Stream0625.f01 (steady flow) ---

Flow Title=Multiple
Number of Profiles=7
Profile Names=10-year,25-year,50-year,1pct_min,100-year,1pct_plu,500-year
River Rch & RM= Stream0625,Reach-1,1861
     250     385     502     318     635    1267    1004
Boundary for River Rch & Prof#=Stream0625,Reach-1,1
Up Type=0
Dn Type=3
Dn Slope=0.005
Boundary for River Rch & Prof#=Stream0625,Reach-1,2
Up Type=0
Dn Type=3
Dn Slope=0.005
Boundary for River Rch & Prof#=Stream0625,Reach-1,3
Up Type=0
Dn Type=3
Dn Slope=0.005
Boundary for River Rch & Prof#=Stream0625,Reach-1,4
Up Type=0
Dn Type=3
Dn Slope=0.005
Boundary for River Rch & Prof#=Stream0625,Reach-1,5
Up Type=0
Dn Type=3
Dn Slope=0.005
Boundary for River Rch & Prof#=Stream0625,Reach-1,6
Up Type=0
Dn Type=3
Dn Slope=0.005
Boundary for River Rch & Prof#=Stream0625,Reach-1,7
Up Type=0
Dn Type=3
Dn Slope=0.005

--- Stream0625.g01 (geometry) ---

Geom Title=Existing Conditions

River Reach=Stream0625,Reach-1
Reach XY= 30
      2391875.00     13589825.00      2391826.51     13589828.65
      2391781.16     13589867.11      2391764.54     13589873.88
      2391580.85     13589872.94      2391558.25     13589858.54
      2391480.74     13589783.30      2391430.62     13589769.38
      2391414.12     13589715.56      2391323.55     13589628.53
      2391130.86     13589622.93      2391108.25     13589608.53
      2391034.67     13589535.21      2391009.66     13589524.96
      2390972.83     13589530.35      2390931.08     13589566.81
      2390914.50     13589573.76      2390764.81     13589575.46
      2390726.55     13589571.25      2390677.18     13589531.11
      2390626.72     13589520.78      2390580.94     13589482.77
      2390559.61     13589475.08      2390522.82     13589480.38
      2390468.95     13589522.85      2390390.89     13589524.48
      2390378.39     13589516.97      2390372.28     13589481.56
      2390364.15     13589465.63      2390275.00     13589375.00

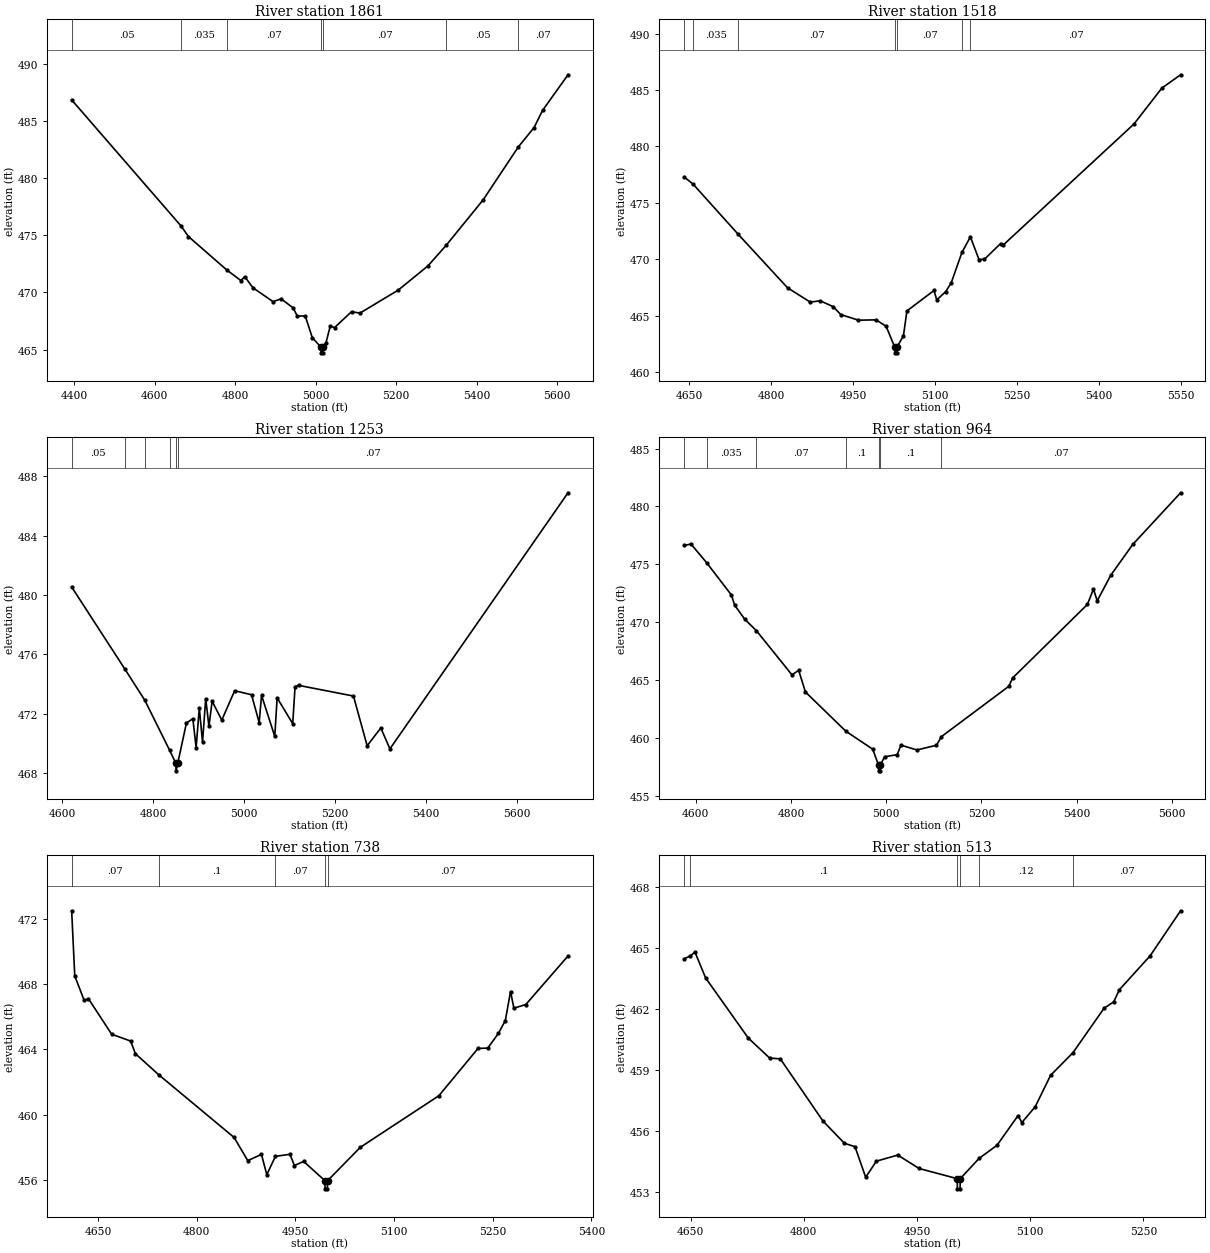
Type RM Length L Ch R = 1,1861,343,343,343
BEGIN DESCRIPTION:
Stream0625 4.0
END DESCRIPTION:
XS GIS Cut Line= 3
      2391825.00     13589225.05      2391825.00     13589825.00
      2391625.00     13590424.99
#Sta/Elev= 30
  4394.3  486.85  4666.0  475.81  4684.3  474.89  4778.9  471.98  4814.3  471.04
  4824.3  471.37  4844.3  470.41  4894.3  469.19  4914.3  469.44  4944.3  468.64
  4954.3  467.94  4974.3  467.93  4991.8  466.03  5013.3  465.21  5013.6  464.71
  5017.1  464.71  5017.3  465.21  5025.9  465.61  5036.4  467.07  5047.0  466.92
  5089.1  468.31  5110.2  468.19  5205.1  470.20  5278.9  472.32  5324.8  474.15
  5415.9  478.10  5503.4  482.74  5542.4  484.43  5563.5  485.93  5626.7  489.05
#Mann=7,-1,0
  4394.3    0.05       0  4666.0   0.035       0  4778.9    0.07       0
  5013.3    0.05       0  5017.3    0.07       0  5324.8    0.05       0
  5503.4    0.07       0
Bank Sta=5013.3,5017.3
Exp/Cntr=0.3,0.1

Type RM Length L Ch R = 1,1518,265,265,265
BEGIN DESCRIPTION:
Stream0625 3.0
END DESCRIPTION:
XS GIS Cut Line= 3
      2391625.00     13589475.01      2391515.36     13589825.00
      2391426.82     13590358.85
#Sta/Elev= 30
  4641.0  477.30  4657.5  476.65  4739.8  472.22  4829.9  467.49  4871.5  466.22
  4889.6  466.34  4913.4  465.82  4927.3  465.12  4959.7  464.62  4992.1  464.65
  5010.3  464.08  5026.0  462.23  5026.3  461.73  5029.8  461.73  5030.0  462.23
  5041.9  463.23  5048.3  465.44  5097.8  467.25  5102.9  466.42  5119.3  467.15
  5129.4  467.94  5149.0  470.63  5164.4  472.00  5180.1  469.99  5190.2  470.02
  5219.7  471.41  5224.8  471.29  5463.6  481.99  5514.6  485.17  5548.9  486.35
#Mann=7,-1,0
  4641.0    0.05       0  4657.5   0.035       0  4739.8    0.07       0
  5026.0    0.05       0  5030.0    0.07       0  5149.0    0.05       0
  5164.4    0.07       0
Bank Sta=5026,5030
Exp/Cntr=0.3,0.1

Type RM Length L Ch R = 1,1253,289,289,289
BEGIN DESCRIPTION:
XS7294
END DESCRIPTION:
XS GIS Cut Line= 4
      2391611.70     13589374.50      2391338.28     13589642.71
      2391304.43     13589765.10      2391348.70     13590345.82
#Sta/Elev= 30
  4620.3  480.53  4736.7  475.03  4781.2  472.90  4835.7  469.54  4849.7  468.64
  4850.0  468.14  4853.7  468.64  4872.9  471.37  4887.0  471.65  4894.2  469.71
  4901.2  472.37  4908.3  470.07  4915.3  473.01  4922.4  471.14  4929.4  472.83
  4950.7  471.56  4979.0  473.54  5016.1  473.27  5033.0  471.39  5038.2  473.23
  5067.3  470.46  5072.5  473.06  5106.8  471.32  5112.0  473.82  5119.8  473.90
  5240.5  473.18  5270.6  469.83  5300.7  471.03  5320.7  469.62  5712.7  486.88
#Mann=6,-1,0
  4620.3    0.05       0  4736.7    0.07       0  4781.2   0.035       0
  4835.7    0.07       0  4849.7    0.05       0  4853.7    0.07       0
Bank Sta=4849.7,4853.7
Exp/Cntr=0.3,0.1

Type RM Length L Ch R = 1,964,226,226,226
BEGIN DESCRIPTION:
Stream0625 2.0
END DESCRIPTION:
XS GIS Cut Line= 3
      2391374.98     13589275.02      2391075.00     13589575.00
      2390925.00     13590175.00
#Sta/Elev= 30
  4575.8  476.63  4589.9  476.76  4622.9  475.14  4674.8  472.36  4681.8  471.47
  4703.0  470.26  4727.1  469.29  4802.0  465.47  4816.2  465.85  4830.3  463.99
  4915.2  460.60  4971.7  459.05  4983.9  457.68  4984.1  457.18  4987.6  457.18
  4987.9  457.68  4996.5  458.39  5023.2  458.58  5031.0  459.40  5064.5  458.98
  5105.7  459.39  5116.0  460.13  5257.7  464.48  5265.5  465.19  5422.7  471.54
  5435.5  472.87  5443.3  471.85  5471.6  474.05  5518.0  476.72  5618.5  481.18
#Mann=7,-1,0
  4575.8    0.07       0  4622.9   0.035       0  4727.1    0.07       0
  4915.2     0.1       0  4983.9    0.05       0  4987.9     0.1       0
  5116.0    0.07       0
Bank Sta=4983.9,4987.9
Exp/Cntr=0.3,0.1

Type RM Length L Ch R = 1,738,225,225,225
BEGIN DESCRIPTION:
E21183
END DESCRIPTION:
XS GIS Cut Line= 3
      2391124.94     13589268.91      2390883.30     13589576.09
      2390787.73     13589926.97
#Sta/Elev= 30
  4610.0  472.50  4614.7  468.50  4629.1  467.00  4635.5  467.11  4670.8  464.93
  4699.7  464.51  4706.8  463.74  4742.5  462.44  4856.9  458.60  4877.7  457.18
  4898.5  457.56  4906.6  456.32  4919.7  457.44  4941.8  457.57  4948.6  456.88
  4962.6  457.13  4995.0  455.95  4995.2  455.45  4998.7  455.45  4999.0  455.95
  5048.9  458.00  5168.2  461.16  5227.7  464.06  5242.5  464.08  5258.8  464.99
  5269.2  465.77  5277.1  467.55  5282.2  466.53  5300.3  466.75  5364.5  469.73
#Mann=5,-1,0
  4610.0    0.07       0  4742.5     0.1       0  4919.7    0.07       0
  4995.0    0.05       0  4999.0    0.07       0
Bank Sta=4995,4999
Exp/Cntr=0.3,0.1

Type RM Length L Ch R = 1,513,135,135,135
BEGIN DESCRIPTION:
Stream0625 1.0
END DESCRIPTION:
XS GIS Cut Line= 3
      2390925.02     13589274.98      2390675.00     13589525.00
      2390625.00     13589824.99
#Sta/Elev= 30
  4641.7  464.45  4649.7  464.59  4655.9  464.78  4670.0  463.51  4726.6  460.55
  4754.9  459.57  4769.0  459.53  4825.6  456.47  4853.9  455.38  4868.0  455.21
  4882.1  453.71  4896.3  454.50  4924.6  454.80  4952.9  454.14  5003.4  453.64
  5003.7  453.14  5007.2  453.14  5007.4  453.64  5032.5  454.64  5056.1  455.28
  5084.0  456.74  5089.1  456.40  5106.8  457.18  5127.1  458.72  5156.7  459.83
  5198.0  462.02  5210.7  462.33  5218.3  462.93  5258.9  464.59  5299.4  466.81
#Mann=6,-1,0
  4641.7    0.07       0  4649.7     0.1       0  5003.4    0.05       0
  5007.4     0.1       0  5032.5    0.12       0  5156.7    0.07       0
Bank Sta=5003.4,5007.4
Exp/Cntr=0.3,0.1

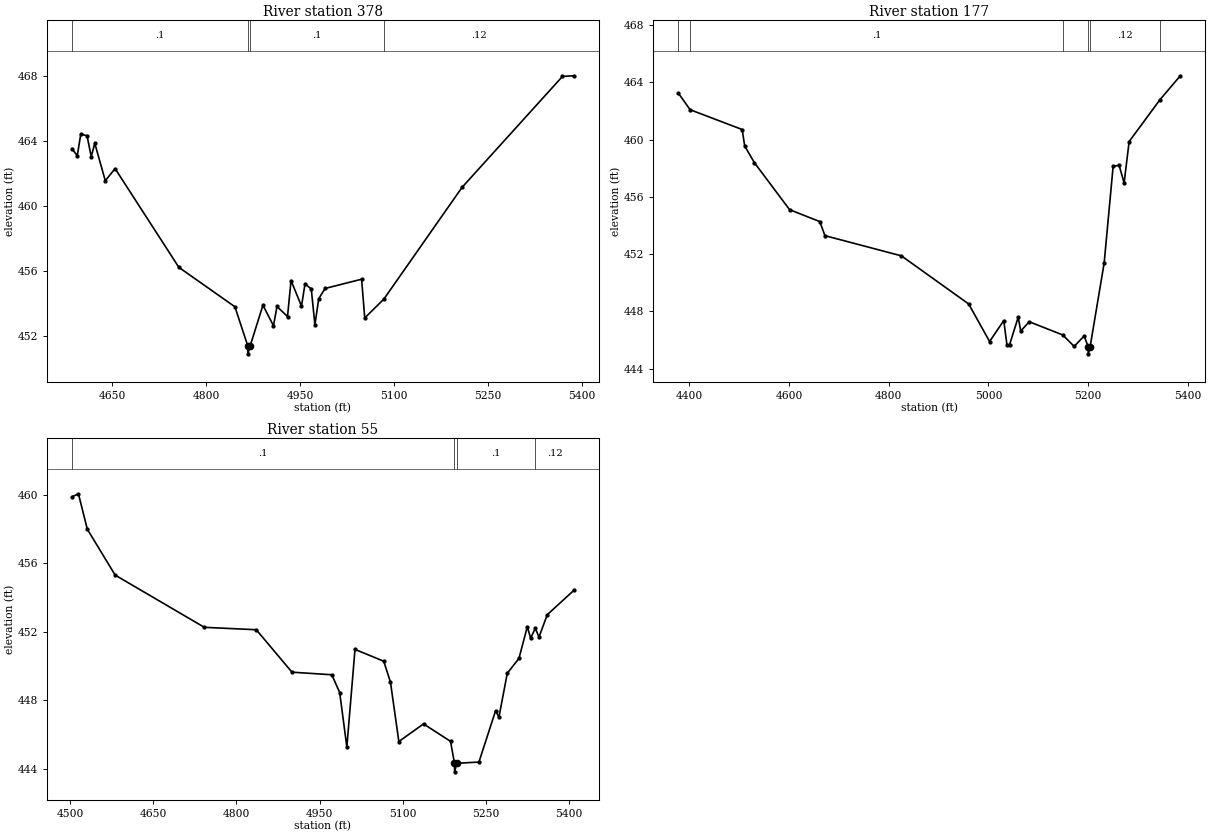
Type RM Length L Ch R = 1,378,201,201,201
BEGIN DESCRIPTION:
E21182
END DESCRIPTION:
XS GIS Cut Line= 3
      2390906.53     13589275.69      2390559.70     13589449.11
      2390507.81     13589858.76
#Sta/Elev= 30
  4586.3  463.54  4594.8  463.10  4600.4  464.44  4610.4  464.33  4617.1  463.04
  4622.7  463.87  4639.5  461.56  4655.1  462.31  4756.9  456.22  4846.3  453.79
  4866.7  451.39  4866.9  450.89  4870.7  451.39  4891.0  453.89  4907.8  452.62
  4913.4  453.81  4930.2  453.19  4935.8  455.41  4952.5  453.83  4958.1  455.20
  4968.1  454.89  4973.9  452.68  4980.0  454.29  4990.1  454.92  5048.4  455.49
  5053.4  453.10  5084.0  454.27  5208.6  461.15  5368.8  467.99  5387.0  468.03
#Mann=4,-1,0
  4586.3     0.1       0  4866.7    0.05       0  4870.7     0.1       0
  5084.0    0.12       0
Bank Sta=4866.7,4870.7
Exp/Cntr=0.3,0.1

Type RM Length L Ch R = 1,177,122,122,122
BEGIN DESCRIPTION:
XS7293
END DESCRIPTION:
XS GIS Cut Line= 4
      2390905.96     13589262.50      2390564.84     13589309.38
      2390351.30     13589541.15      2390333.07     13589887.50
#Sta/Elev= 30
  4378.4  463.23  4401.9  462.08  4506.2  460.70  4511.3  459.55  4530.8  458.38
  4601.4  455.10  4662.0  454.27  4672.1  453.29  4825.5  451.88  4960.4  448.52
  5002.3  445.90  5030.7  447.36  5037.1  445.67  5042.3  445.67  5059.7  447.60
  5064.7  446.63  5081.8  447.28  5148.9  446.36  5171.9  445.56  5191.9  446.29
  5199.9  445.54  5200.2  445.04  5203.9  445.54  5232.0  451.38  5250.0  458.13
  5262.0  458.20  5272.0  456.97  5282.1  459.86  5343.9  462.78  5384.7  464.45
#Mann=6,-1,0
  4378.4    0.07       0  4401.9     0.1       0  5148.9    0.12       0
  5199.9    0.05       0  5203.9    0.12       0  5343.9    0.07       0
Bank Sta=5199.9,5203.9
Exp/Cntr=0.3,0.1

Type RM Length L Ch R = 1,55,0,0,0
BEGIN DESCRIPTION:
E21181
END DESCRIPTION:
XS GIS Cut Line= 4
      2390772.57     13589268.88      2390472.18     13589300.28
      2390270.10     13589445.01      2390074.52     13589741.29
#Sta/Elev= 30
  4503.3  459.89  4515.0  460.07  4531.0  458.00  4581.3  455.32  4742.2  452.27
  4835.9  452.13  4900.3  449.65  4972.2  449.50  4986.4  448.46  4999.3  445.28
  5014.0  450.98  5065.9  450.29  5078.0  449.07  5093.1  445.60  5137.7  446.63
  5186.4  445.61  5193.5  444.33  5193.7  443.83  5197.5  444.33  5237.6  444.40
  5267.7  447.40  5273.7  447.02  5288.8  449.59  5309.8  450.45  5324.9  452.30
  5330.9  451.64  5339.4  452.21  5346.0  451.70  5361.0  453.01  5408.9  454.43
#Mann=4,-1,0
  4503.3     0.1       0  5193.5    0.05       0  5197.5     0.1       0
  5339.4    0.12       0
Bank Sta=5193.5,5197.5
Exp/Cntr=0.3,0.1

Chan Stop Cuts=-1