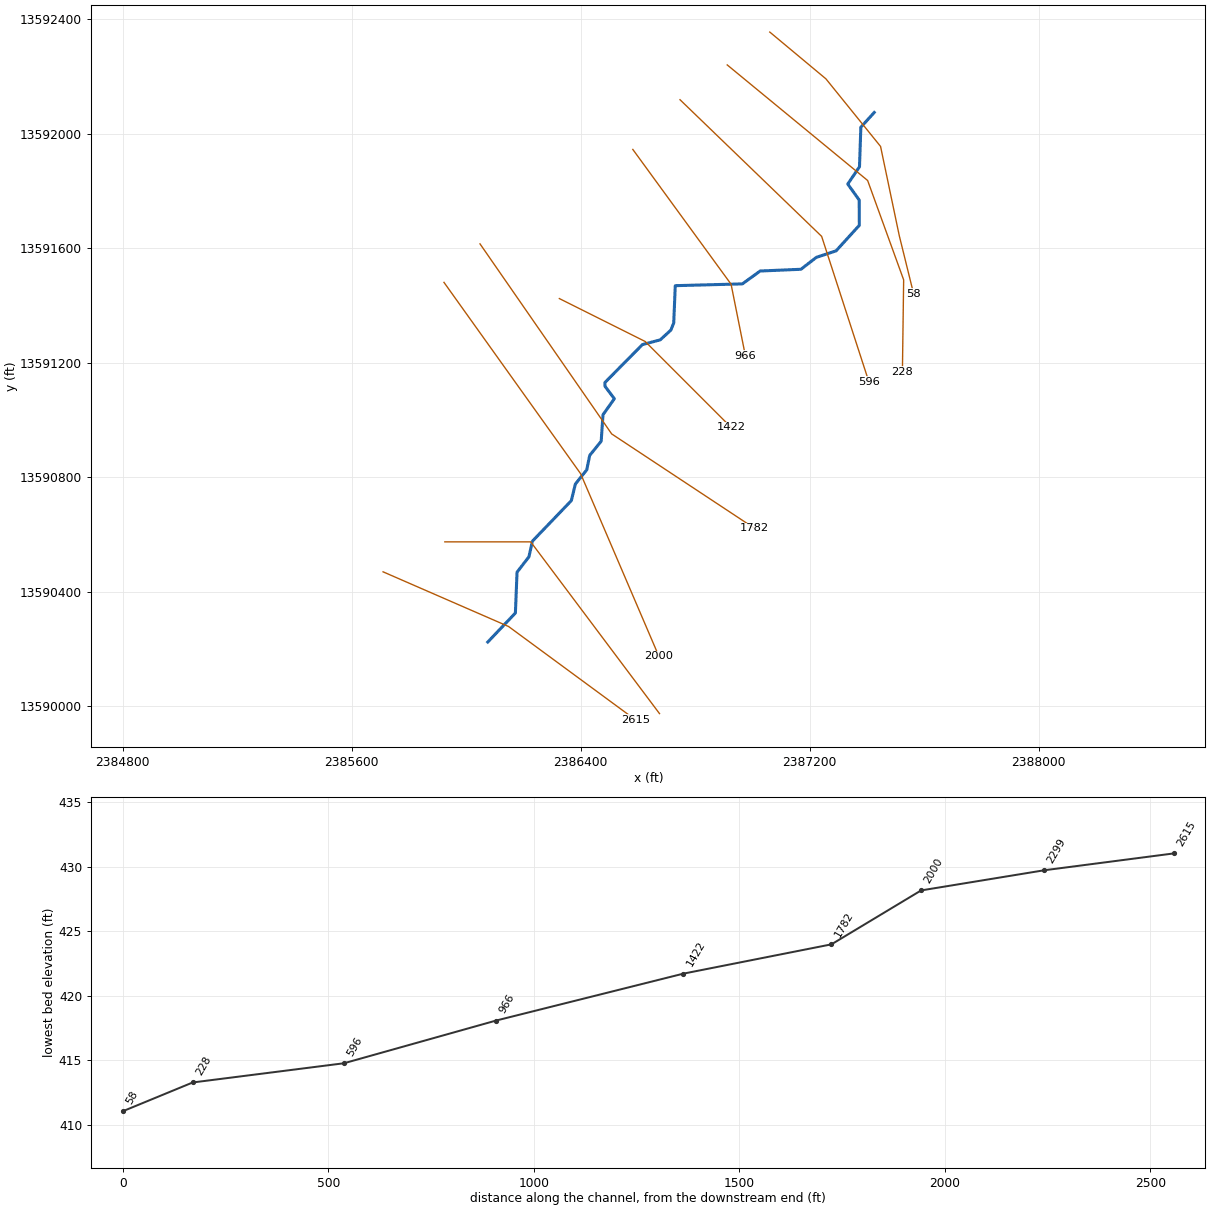
--- Stream0626.prj (project) ---

Proj Title=Stream0626 Base Level Engineering
Current Plan=p01
Default Exp/Contr=0.3,0.1
English Units
Geom File=g01
Flow File=f01
Plan File=p01
BEGIN DESCRIPTION:
Stream0626
END DESCRIPTION:

--- Stream0626.p01 (plan) ---

Plan Title=Multiple Run
Short Identifier=Multiple
Geom File=g01
Flow File=f01
Subcritical Flow
K Sum by GR= 0
Std Step Tol= 0.01
Critical Tol= 0.01
Num of Std Step Trials= 20
Max Error Tol= 0.3
Flow Tol Ratio= 0.001
Split Flow NTrial= 30
Split Flow Tol= 0.02
Split Flow Ratio= 0.02
Log Output Level= 0
Friction Slope Method= 1
Unsteady Friction Slope Method= 2
Unsteady Bridges Friction Slope Method= 1
Parabolic Critical Depth
Global Vel Dist=  1 , 1 , 1
Global Log Level= 0
CheckData=True
Encroach Param= -1, 0, 0, 0
BEGIN DESCRIPTION:
Multiple Run
END DESCRIPTION:

--- Stream0626.f01 (steady flow) ---

Flow Title=Multiple
Number of Profiles=7
Profile Names=10-year,25-year,50-year,1pct_min,100-year,1pct_plu,500-year
River Rch & RM= Stream0626,Reach-1,2615
     325     507     666     425     847    1691    1358
Boundary for River Rch & Prof#=Stream0626,Reach-1,1
Up Type=0
Dn Type=3
Dn Slope=0.005
Boundary for River Rch & Prof#=Stream0626,Reach-1,2
Up Type=0
Dn Type=3
Dn Slope=0.005
Boundary for River Rch & Prof#=Stream0626,Reach-1,3
Up Type=0
Dn Type=3
Dn Slope=0.005
Boundary for River Rch & Prof#=Stream0626,Reach-1,4
Up Type=0
Dn Type=3
Dn Slope=0.005
Boundary for River Rch & Prof#=Stream0626,Reach-1,5
Up Type=0
Dn Type=3
Dn Slope=0.005
Boundary for River Rch & Prof#=Stream0626,Reach-1,6
Up Type=0
Dn Type=3
Dn Slope=0.005
Boundary for River Rch & Prof#=Stream0626,Reach-1,7
Up Type=0
Dn Type=3
Dn Slope=0.005

--- Stream0626.g01 (geometry) ---

Geom Title=Existing Conditions

River Reach=Stream0626,Reach-1
Reach XY= 30
      2386075.00     13590225.00      2386171.51     13590326.45
      2386177.25     13590469.07      2386218.86     13590522.83
      2386230.83     13590577.30      2386366.86     13590718.94
      2386381.10     13590777.19      2386420.84     13590826.72
      2386431.12     13590877.18      2386471.18     13590926.59
      2386477.54     13591019.11      2386517.20     13591075.10
      2386484.60     13591118.34      2386484.30     13591131.67
      2386615.34     13591264.21      2386677.57     13591280.74
      2386714.65     13591314.88      2386724.65     13591340.06
      2386730.01     13591470.00      2386964.50     13591476.22
      2387026.57     13591521.21      2387169.07     13591527.25
      2387222.83     13591568.86      2387291.71     13591591.63
      2387373.04     13591680.88      2387372.64     13591769.10
      2387332.56     13591825.00      2387373.61     13591885.44
      2387378.30     13592023.63      2387425.00     13592075.00

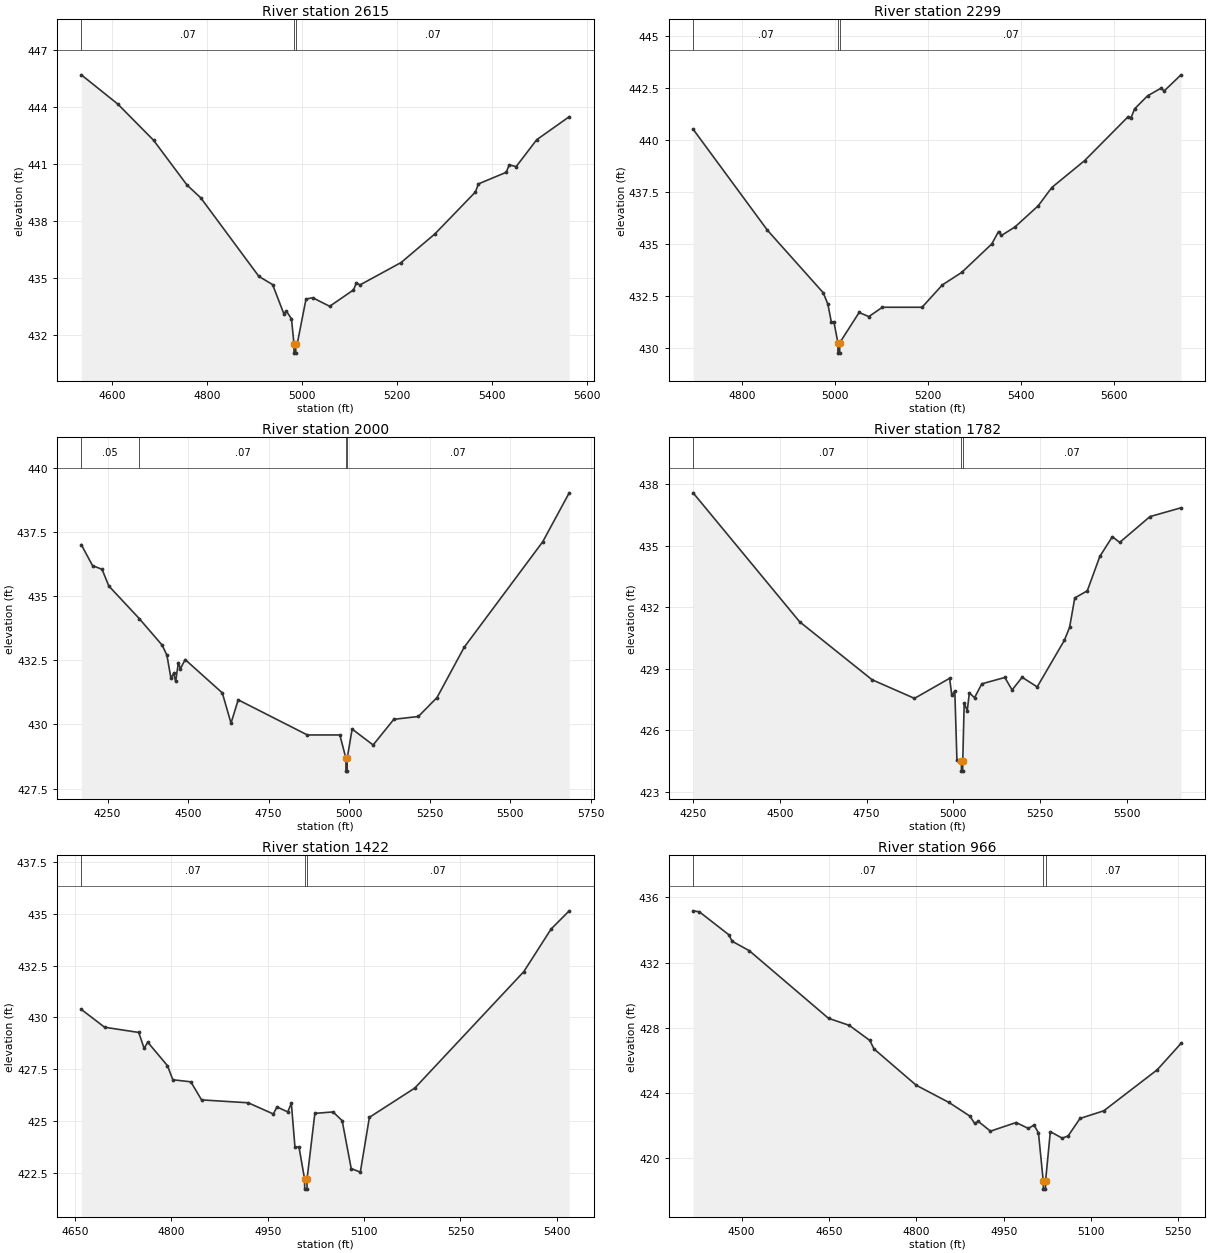
Type RM Length L Ch R = 1,2615,316,316,316
BEGIN DESCRIPTION:
XS7296
END DESCRIPTION:
XS GIS Cut Line= 3
      2385709.25     13590470.33      2386147.66     13590279.34
      2386590.20     13589953.94
#Sta/Elev= 30
  4535.2  445.67  4611.8  444.14  4687.5  442.23  4757.8  439.88  4786.7  439.21
  4909.2  435.08  4938.1  434.65  4961.5  433.13  4967.0  433.26  4977.8  432.85
  4983.0  431.55  4983.2  431.05  4986.7  431.05  4987.0  431.55  4990.4  431.60
  5008.4  433.89  5022.5  433.96  5058.2  433.51  5108.4  434.37  5114.6  434.75
  5121.8  434.63  5208.7  435.81  5279.7  437.31  5365.3  439.52  5371.5  439.94
  5430.1  440.55  5436.3  440.94  5451.0  440.85  5494.2  442.26  5562.7  443.47
#Mann=3,-1,0
  4535.2    0.07       0  4983.0    0.05       0  4987.0    0.07       0
Bank Sta=4983,4987
Exp/Cntr=0.3,0.1

Type RM Length L Ch R = 1,2299,299,299,299
BEGIN DESCRIPTION:
Stream0626 5.0
END DESCRIPTION:
XS GIS Cut Line= 3
      2385924.99     13590575.00      2386225.00     13590575.00
      2386674.99     13589975.01
#Sta/Elev= 30
  4694.8  440.53  4854.8  435.66  4974.8  432.65  4984.8  432.10  4992.3  431.23
  4997.9  431.23  5006.4  430.24  5006.6  429.74  5010.1  429.74  5010.4  430.24
  5052.1  431.70  5072.9  431.50  5102.1  431.95  5187.5  431.95  5231.3  433.03
  5272.9  433.63  5337.5  435.00  5352.1  435.60  5358.4  435.41  5387.5  435.82
  5437.5  436.84  5466.7  437.72  5537.5  439.02  5631.3  441.14  5637.5  441.09
  5644.8  441.51  5672.9  442.14  5702.1  442.51  5708.4  442.37  5744.8  443.15
#Mann=3,-1,0
  4694.8    0.07       0  5006.4    0.05       0  5010.4    0.07       0
Bank Sta=5006.4,5010.4
Exp/Cntr=0.3,0.1

Type RM Length L Ch R = 1,2000,218,218,218
BEGIN DESCRIPTION:
XS7297
END DESCRIPTION:
XS GIS Cut Line= 3
      2385921.98     13591481.57      2386399.39     13590813.19
      2386672.83     13590175.18
#Sta/Elev= 30
  4168.3  437.01  4203.2  436.19  4232.7  436.05  4253.6  435.40  4348.1  434.13
  4419.5  433.09  4434.2  432.70  4446.7  431.80  4455.1  431.99  4461.3  431.68
  4469.9  432.41  4476.0  432.17  4490.8  432.53  4606.3  431.23  4633.3  430.05
  4655.6  430.96  4870.5  429.59  4971.3  429.59  4990.2  428.68  4990.4  428.18
  4993.9  428.18  4994.2  428.68  5009.5  429.82  5074.7  429.20  5139.0  430.20
  5215.2  430.31  5273.2  431.05  5357.6  433.01  5601.4  437.12  5683.8  439.03
#Mann=4,-1,0
  4168.3    0.05       0  4348.1    0.07       0  4990.2    0.05       0
  4994.2    0.07       0
Bank Sta=4990.2,4994.2
Exp/Cntr=0.3,0.1

Type RM Length L Ch R = 1,1782,360,360,360
BEGIN DESCRIPTION:
Stream0626 4.0
END DESCRIPTION:
XS GIS Cut Line= 3
      2386047.85     13591616.12      2386507.90     13590952.08
      2387007.02     13590622.23
#Sta/Elev= 30
  4249.8  437.58  4556.7  431.29  4765.5  428.46  4887.8  427.55  4989.1  428.53
  4995.2  427.71  5004.0  427.91  5010.1  424.54  5022.9  424.50  5023.2  424.00
  5026.7  424.00  5026.9  424.50  5031.0  427.33  5039.8  426.94  5045.9  427.82
  5060.8  427.58  5081.8  428.26  5148.1  428.57  5169.1  427.96  5198.0  428.58
  5241.4  428.11  5319.6  430.38  5334.7  431.01  5349.7  432.45  5385.8  432.80
  5422.0  434.48  5458.1  435.44  5479.1  435.16  5566.4  436.42  5655.9  436.85
#Mann=3,-1,0
  4249.8    0.07       0  5022.9    0.05       0  5026.9    0.07       0
Bank Sta=5022.9,5026.9
Exp/Cntr=0.3,0.1

Type RM Length L Ch R = 1,1422,456,456,456
BEGIN DESCRIPTION:
Stream0626 3.0
END DESCRIPTION:
XS GIS Cut Line= 3
      2386325.04     13591424.98      2386625.00     13591275.00
      2386924.98     13590975.02
#Sta/Elev= 30
  4659.8  430.39  4696.1  429.53  4749.2  429.28  4757.6  428.51  4763.2  428.81
  4793.9  427.68  4802.3  427.00  4830.3  426.90  4847.0  426.03  4919.7  425.89
  4958.8  425.35  4964.4  425.69  4981.2  425.45  4986.8  425.87  4992.4  423.76
  4998.7  423.76  5007.3  422.23  5007.6  421.73  5011.1  421.73  5011.3  422.23
  5023.4  425.38  5051.7  425.45  5065.9  425.03  5080.0  422.72  5094.2  422.55
  5108.3  425.19  5179.0  426.60  5348.7  432.21  5391.1  434.26  5419.4  435.14
#Mann=3,-1,0
  4659.8    0.07       0  5007.3    0.05       0  5011.3    0.07       0
Bank Sta=5007.3,5011.3
Exp/Cntr=0.3,0.1

Type RM Length L Ch R = 1,966,370,370,370
BEGIN DESCRIPTION:
Stream0626 2.0
END DESCRIPTION:
XS GIS Cut Line= 3
      2386581.71     13591945.98      2386925.00     13591475.00
      2386975.01     13591224.96
#Sta/Elev= 30
  4416.8  435.18  4427.5  435.12  4477.8  433.72  4483.9  433.31  4513.3  432.73
  4649.3  428.58  4684.8  428.15  4720.3  427.22  4727.4  426.70  4799.9  424.47
  4856.3  423.41  4891.8  422.58  4900.3  422.13  4906.5  422.25  4927.4  421.65
  4971.4  422.18  4992.3  421.82  5002.2  422.02  5009.8  421.55  5018.0  418.59
  5018.3  418.09  5021.8  418.09  5022.0  418.59  5030.2  421.62  5050.6  421.22
  5060.8  421.36  5081.2  422.43  5122.0  422.90  5213.8  425.42  5254.6  427.04
#Mann=3,-1,0
  4416.8    0.07       0  5018.0    0.05       0  5022.0    0.07       0
Bank Sta=5018,5022
Exp/Cntr=0.3,0.1

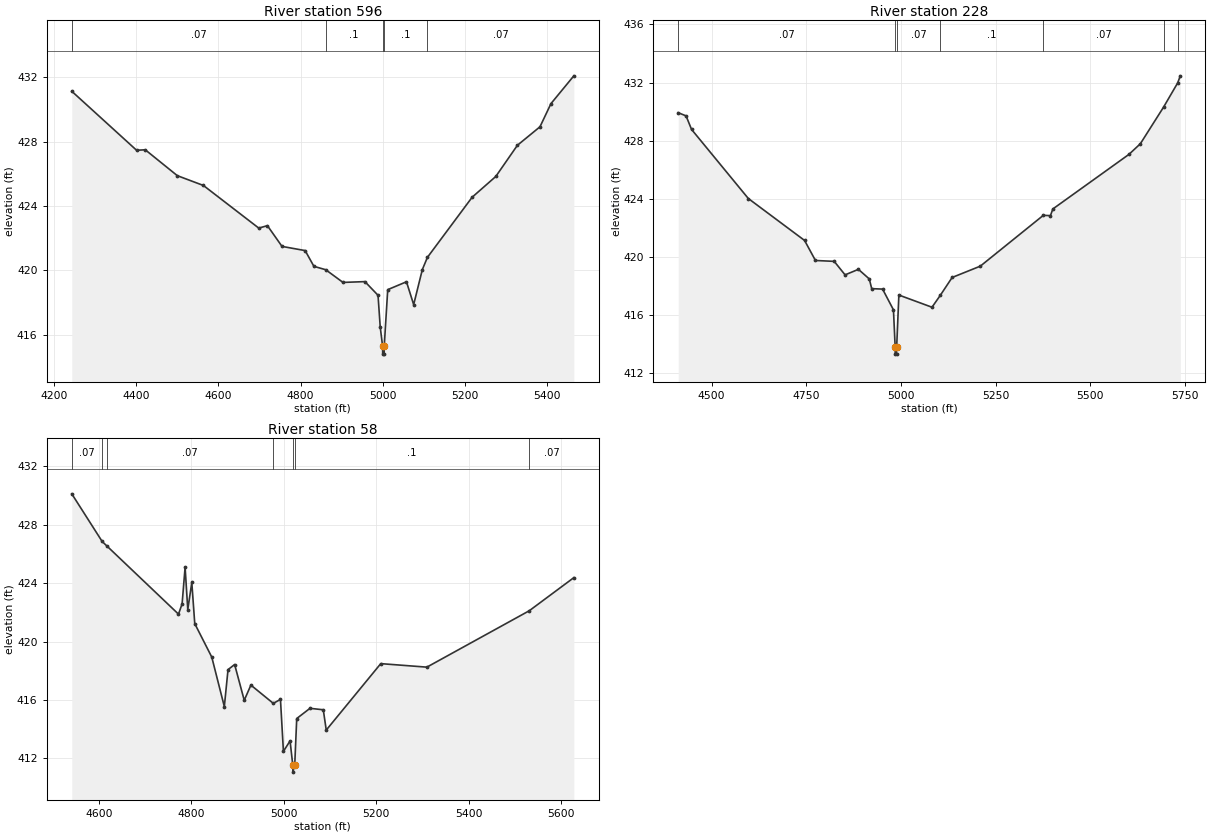
Type RM Length L Ch R = 1,596,368,368,368
BEGIN DESCRIPTION:
Stream0626 1.0
END DESCRIPTION:
XS GIS Cut Line= 3
      2386746.60     13592119.63      2387241.41     13591642.19
      2387406.33     13591134.39
#Sta/Elev= 30
  4243.1  431.13  4400.8  427.46  4421.9  427.49  4499.9  425.88  4563.4  425.27
  4698.0  422.62  4719.1  422.77  4754.6  421.48  4810.9  421.22  4832.2  420.24
  4860.9  420.03  4903.0  419.24  4956.3  419.29  4988.2  418.44  4993.5  416.48
  4999.3  415.28  4999.6  414.78  5003.1  414.78  5003.3  415.28  5011.8  418.79
  5057.4  419.28  5074.9  417.86  5096.0  420.04  5108.4  420.80  5217.2  424.54
  5274.7  425.83  5327.3  427.77  5382.2  428.92  5408.9  430.36  5464.6  432.09
#Mann=5,-1,0
  4243.1    0.07       0  4860.9     0.1       0  4999.3    0.05       0
  5003.3     0.1       0  5108.4    0.07       0
Bank Sta=4999.3,5003.3
Exp/Cntr=0.3,0.1

Type RM Length L Ch R = 1,228,170,170,170
BEGIN DESCRIPTION:
XS7295
END DESCRIPTION:
XS GIS Cut Line= 4
      2386911.53     13592241.16      2387402.00     13591837.50
      2387527.86     13591490.28      2387523.53     13591169.55
#Sta/Elev= 30
  4412.0  429.92  4432.7  429.70  4447.1  428.77  4597.0  424.01  4745.5  421.12
  4774.2  419.74  4823.7  419.68  4852.4  418.75  4887.6  419.13  4916.3  418.47
  4922.7  417.80  4951.4  417.77  4980.1  416.34  4984.6  413.79  4984.8  413.29
  4988.3  413.29  4988.6  413.79  4994.4  417.36  5081.8  416.52  5103.5  417.33
  5135.0  418.57  5209.4  419.35  5375.7  422.85  5394.5  422.83  5400.9  423.29
  5601.8  427.05  5631.8  427.78  5693.0  430.30  5730.3  431.97  5737.3  432.46
#Mann=7,-1,0
  4412.0    0.07       0  4984.6    0.05       0  4988.6    0.07       0
  5103.5     0.1       0  5375.7    0.07       0  5693.0    0.12       0
  5730.3    0.07       0
Bank Sta=4984.6,4988.6
Exp/Cntr=0.3,0.1

Type RM Length L Ch R = 1,58,0,0,0
BEGIN DESCRIPTION:
E21184
END DESCRIPTION:
XS GIS Cut Line= 5
      2387060.24     13592355.95      2387256.24     13592192.62
      2387447.18     13591956.46      2387512.50     13591644.93
      2387562.73     13591441.47
#Sta/Elev= 30
  4541.0  430.12  4606.7  426.86  4617.9  426.52  4772.0  421.88  4779.8  422.58
  4786.3  425.09  4792.1  422.19  4800.8  424.05  4807.2  421.23  4844.0  418.94
  4871.2  415.55  4879.2  418.08  4893.5  418.43  4914.3  415.98  4928.7  417.02
  4977.2  415.77  4992.7  416.04  4999.1  412.48  5013.5  413.20  5019.3  411.56
  5019.6  411.06  5023.6  411.56  5027.9  414.73  5056.6  415.43  5085.4  415.33
  5091.8  413.94  5209.8  418.49  5309.6  418.25  5531.1  422.11  5627.7  424.38
#Mann=7,-1,0
  4541.0    0.07       0  4606.7    0.12       0  4617.9    0.07       0
  4977.2     0.1       0  5019.3    0.05       0  5023.6     0.1       0
  5531.1    0.07       0
Bank Sta=5019.3,5023.6
Exp/Cntr=0.3,0.1

Chan Stop Cuts=-1