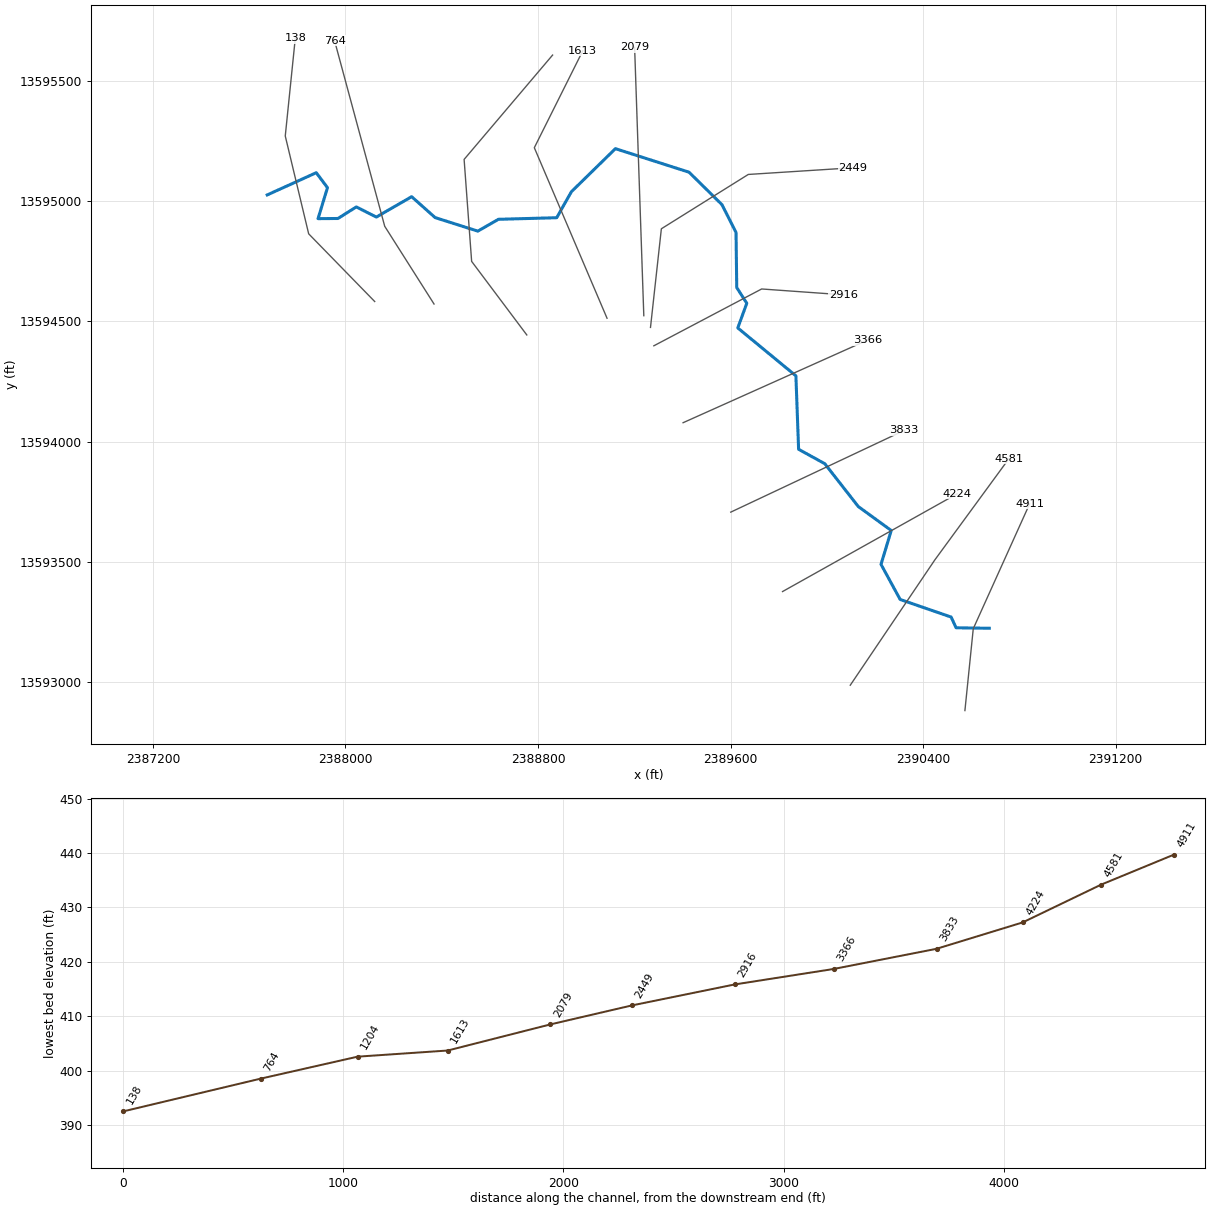
--- Stream0627.prj (project) ---

Proj Title=Stream0627 Base Level Engineering
Current Plan=p01
Default Exp/Contr=0.3,0.1
English Units
Geom File=g01
Flow File=f01
Plan File=p01
Y Axis Title=Elevation
X Axis Title(PF)=Main Channel Distance
X Axis Title(XS)=Station
BEGIN DESCRIPTION:
Stream0627
END DESCRIPTION:
DSS Export Rating Curves= 0
DSS Export Rating Curve Sorted= 0
DSS Export Volume Flow Curves= 0
DXF OffsetX= 0
DXF OffsetY= 0
DXF ScaleX= 1
DXF ScaleY= 10

--- Stream0627.p01 (plan) ---

Plan Title=Multiple Run
Short Identifier=Multiple
Geom File=g01
Flow File=f01
Subcritical Flow
K Sum by GR= 0
Std Step Tol= 0.01
Critical Tol= 0.01
Num of Std Step Trials= 20
Max Error Tol= 0.3
Flow Tol Ratio= 0.001
Split Flow NTrial= 30
Split Flow Tol= 0.02
Split Flow Ratio= 0.02
Log Output Level= 0
Friction Slope Method= 1
Unsteady Friction Slope Method= 2
Unsteady Bridges Friction Slope Method= 1
Parabolic Critical Depth
Global Vel Dist=  1 , 1 , 1
Global Log Level= 0
CheckData=True
Encroach Param= -1, 0, 0, 0
BEGIN DESCRIPTION:
Multiple Run
END DESCRIPTION:

--- Stream0627.f01 (steady flow) ---

Flow Title=Multiple
Number of Profiles=7
Profile Names=10-year,25-year,50-year,1pct_min,100-year,1pct_plu,500-year
River Rch & RM= Stream0627,Reach-1,4911
     511     826    1112     726    1449    2890    2435
Boundary for River Rch & Prof#=Stream0627,Reach-1,1
Up Type=0
Dn Type=3
Dn Slope=0.005
Boundary for River Rch & Prof#=Stream0627,Reach-1,2
Up Type=0
Dn Type=3
Dn Slope=0.005
Boundary for River Rch & Prof#=Stream0627,Reach-1,3
Up Type=0
Dn Type=3
Dn Slope=0.005
Boundary for River Rch & Prof#=Stream0627,Reach-1,4
Up Type=0
Dn Type=3
Dn Slope=0.005
Boundary for River Rch & Prof#=Stream0627,Reach-1,5
Up Type=0
Dn Type=3
Dn Slope=0.005
Boundary for River Rch & Prof#=Stream0627,Reach-1,6
Up Type=0
Dn Type=3
Dn Slope=0.005
Boundary for River Rch & Prof#=Stream0627,Reach-1,7
Up Type=0
Dn Type=3
Dn Slope=0.005

--- Stream0627.g01 (geometry) ---

Geom Title=Existing Conditions

River Reach=Stream0627,Reach-1
Reach XY= 30
      2390675.00     13593225.00      2390536.91     13593226.90
      2390516.51     13593271.45      2390304.52     13593344.62
      2390225.08     13593490.39      2390267.52     13593631.07
      2390130.62     13593730.62      2389991.66     13593908.34
      2389882.69     13593968.52      2389871.46     13594273.54
      2389630.01     13594472.46      2389667.41     13594574.99
      2389625.66     13594640.16      2389622.76     13594869.07
      2389564.24     13594984.68      2389427.43     13595119.48
      2389121.58     13595217.21      2388938.64     13595038.20
      2388877.70     13594930.36      2388635.50     13594923.78
      2388550.00     13594874.60      2388372.70     13594930.86
      2388275.08     13595017.70      2388128.31     13594933.07
      2388045.21     13594975.21      2387968.93     13594927.15
      2387886.21     13594926.50      2387925.39     13595055.09
      2387878.73     13595117.34      2387675.00     13595025.00

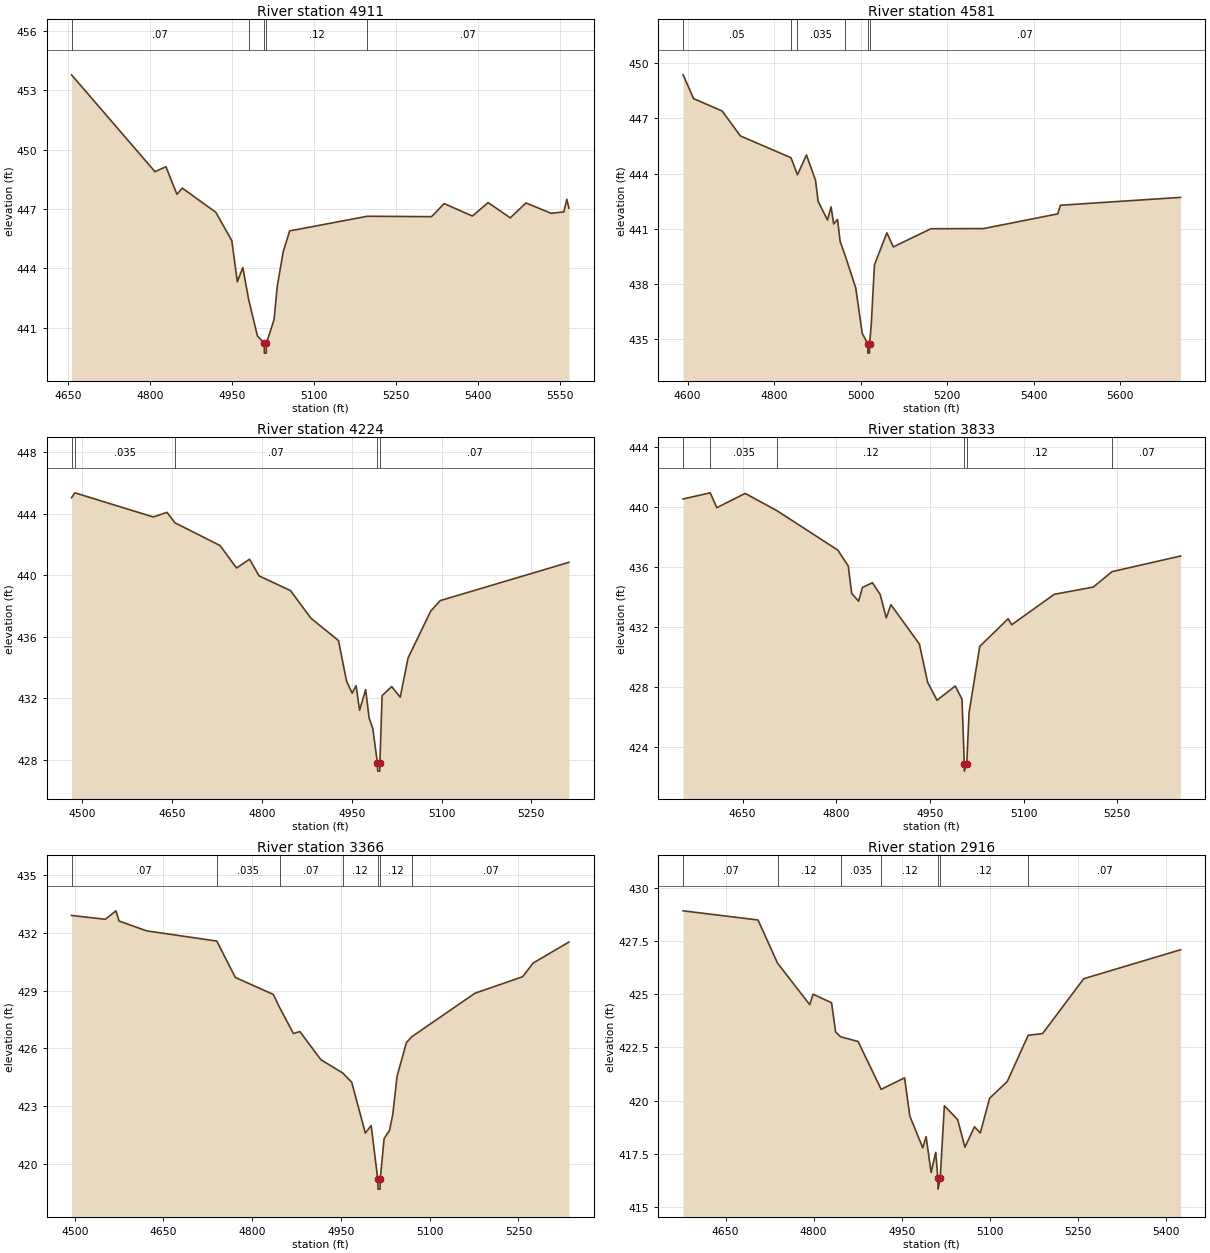
Type RM Length L Ch R = 1,4911,330,330,330
BEGIN DESCRIPTION:
XS7308
END DESCRIPTION:
XS GIS Cut Line= 3
      2390573.61     13592883.01      2390608.33     13593223.26
      2390842.45     13593741.74
#Sta/Elev= 30
  4656.4  453.77  4809.2  448.88  4829.3  449.13  4849.4  447.74  4859.4  448.05
  4920.6  446.83  4949.9  445.40  4960.0  443.32  4970.0  444.04  4980.9  442.41
  4996.8  440.59  5009.3  440.22  5009.5  439.72  5013.0  439.72  5013.3  440.22
  5027.3  441.41  5033.2  443.11  5044.2  444.86  5055.9  445.89  5198.2  446.63
  5315.7  446.61  5338.8  447.27  5390.5  446.64  5419.2  447.32  5459.9  446.55
  5488.5  447.30  5534.8  446.78  5557.9  446.85  5563.4  447.49  5567.3  447.04
#Mann=5,-1,0
  4656.4    0.07       0  4980.9    0.12       0  5009.3    0.05       0
  5013.3    0.12       0  5198.2    0.07       0
Bank Sta=5009.3,5013.3
Exp/Cntr=0.3,0.1

Type RM Length L Ch R = 1,4581,357,357,357
BEGIN DESCRIPTION:
E21185
END DESCRIPTION:
XS GIS Cut Line= 3
      2390097.33     13592988.43      2390448.87     13593509.23
      2390756.92     13593930.09
#Sta/Elev= 30
  4589.5  449.38  4613.8  448.08  4679.7  447.41  4721.8  446.05  4838.9  444.86
  4853.8  443.93  4874.6  445.01  4895.6  443.63  4901.6  442.48  4923.2  441.47
  4931.5  442.18  4937.6  441.25  4946.5  441.50  4952.5  440.29  4964.2  439.52
  4988.5  437.77  5003.5  435.29  5016.5  434.71  5016.7  434.21  5020.2  434.21
  5020.5  434.71  5024.5  435.79  5031.8  439.02  5060.5  440.77  5075.4  440.00
  5162.3  440.99  5284.1  441.00  5455.5  441.80  5461.7  442.27  5739.4  442.70
#Mann=6,-1,0
  4589.5    0.05       0  4838.9    0.07       0  4853.8   0.035       0
  4964.2    0.07       0  5016.5    0.05       0  5020.5    0.07       0
Bank Sta=5016.5,5020.5
Exp/Cntr=0.3,0.1

Type RM Length L Ch R = 1,4224,391,391,391
BEGIN DESCRIPTION:
XS7307
END DESCRIPTION:
XS GIS Cut Line= 2
      2389815.93     13593377.41      2390540.87     13593783.23
#Sta/Elev= 30
  4482.0  445.03  4487.6  445.35  4618.5  443.78  4641.4  444.08  4654.8  443.40
  4730.1  441.92  4757.6  440.46  4779.3  441.03  4795.2  439.95  4847.7  438.99
  4882.0  437.19  4927.9  435.74  4941.4  433.09  4950.8  432.32  4957.3  432.81
  4963.1  431.21  4973.3  432.55  4979.0  430.71  4985.2  430.02  4993.0  427.75
  4993.3  427.25  4996.8  427.25  4997.0  427.75  5000.7  432.16  5016.7  432.75
  5031.0  432.06  5044.1  434.61  5081.8  437.65  5097.8  438.34  5312.8  440.83
#Mann=5,-1,0
  4482.0    0.07       0  4487.6   0.035       0  4654.8    0.07       0
  4993.0    0.05       0  4997.0    0.07       0
Bank Sta=4993,4997
Exp/Cntr=0.3,0.1

Type RM Length L Ch R = 1,3833,467,467,467
BEGIN DESCRIPTION:
XS7306
END DESCRIPTION:
XS GIS Cut Line= 2
      2389600.72     13593707.31      2390321.43     13594046.87
#Sta/Elev= 30
  4554.8  440.53  4598.2  440.94  4608.7  439.95  4654.2  440.90  4705.5  439.74
  4802.7  437.12  4819.3  436.06  4824.8  434.24  4835.9  433.72  4842.0  434.64
  4858.0  434.95  4870.4  434.17  4880.1  432.61  4887.6  433.49  4933.2  430.87
  4946.4  428.32  4961.5  427.12  4990.6  428.07  5001.5  427.19  5005.1  422.90
  5005.3  422.40  5009.1  422.90  5012.8  426.30  5029.9  430.71  5075.4  432.55
  5081.0  432.15  5149.3  434.18  5211.7  434.66  5241.9  435.69  5351.5  436.73
#Mann=6,-1,0
  4554.8    0.12       0  4598.2   0.035       0  4705.5    0.12       0
  5005.1    0.05       0  5009.1    0.12       0  5241.9    0.07       0
Bank Sta=5005.1,5009.1
Exp/Cntr=0.3,0.1

Type RM Length L Ch R = 1,3366,450,450,450
BEGIN DESCRIPTION:
XS7305
END DESCRIPTION:
XS GIS Cut Line= 2
      2389402.77     13594078.82      2390170.10     13594422.55
#Sta/Elev= 30
  4494.6  432.90  4551.9  432.70  4569.6  433.14  4575.1  432.61  4621.4  432.10
  4740.1  431.57  4771.5  429.68  4835.6  428.80  4846.5  428.11  4869.7  426.77
  4880.6  426.87  4916.1  425.41  4953.0  424.72  4968.2  424.24  4991.2  421.60
  5001.1  421.99  5012.3  419.19  5012.6  418.69  5016.1  418.69  5016.3  419.19
  5023.0  421.32  5032.1  421.74  5037.5  422.55  5044.9  424.56  5060.7  426.30
  5069.7  426.60  5176.4  428.86  5257.2  429.72  5274.9  430.43  5335.4  431.52
#Mann=7,-1,0
  4494.6    0.07       0  4740.1   0.035       0  4846.5    0.07       0
  4953.0    0.12       0  5012.3    0.05       0  5016.3    0.12       0
  5069.7    0.07       0
Bank Sta=5012.3,5016.3
Exp/Cntr=0.3,0.1

Type RM Length L Ch R = 1,2916,467,467,467
BEGIN DESCRIPTION:
XS7304
END DESCRIPTION:
XS GIS Cut Line= 3
      2389281.27     13594398.28      2389729.17     13594634.38
      2390069.49     13594610.07
#Sta/Elev= 30
  4577.7  428.92  4705.3  428.49  4738.6  426.46  4793.4  424.51  4799.1  425.00
  4830.6  424.60  4837.5  423.23  4845.9  423.00  4875.8  422.78  4915.1  420.53
  4955.0  421.07  4964.0  419.27  4986.0  417.78  4991.7  418.31  5000.2  416.62
  5008.1  417.57  5011.7  416.34  5012.0  415.84  5015.7  416.34  5022.8  419.76
  5045.4  419.11  5057.8  417.81  5074.1  418.77  5084.0  418.48  5099.9  420.11
  5130.0  420.90  5165.6  423.07  5190.1  423.15  5260.3  425.73  5425.2  427.09
#Mann=7,-1,0
  4577.7    0.07       0  4738.6    0.12       0  4845.9   0.035       0
  4915.1    0.12       0  5011.7    0.05       0  5015.7    0.12       0
  5165.6    0.07       0
Bank Sta=5011.7,5015.7
Exp/Cntr=0.3,0.1

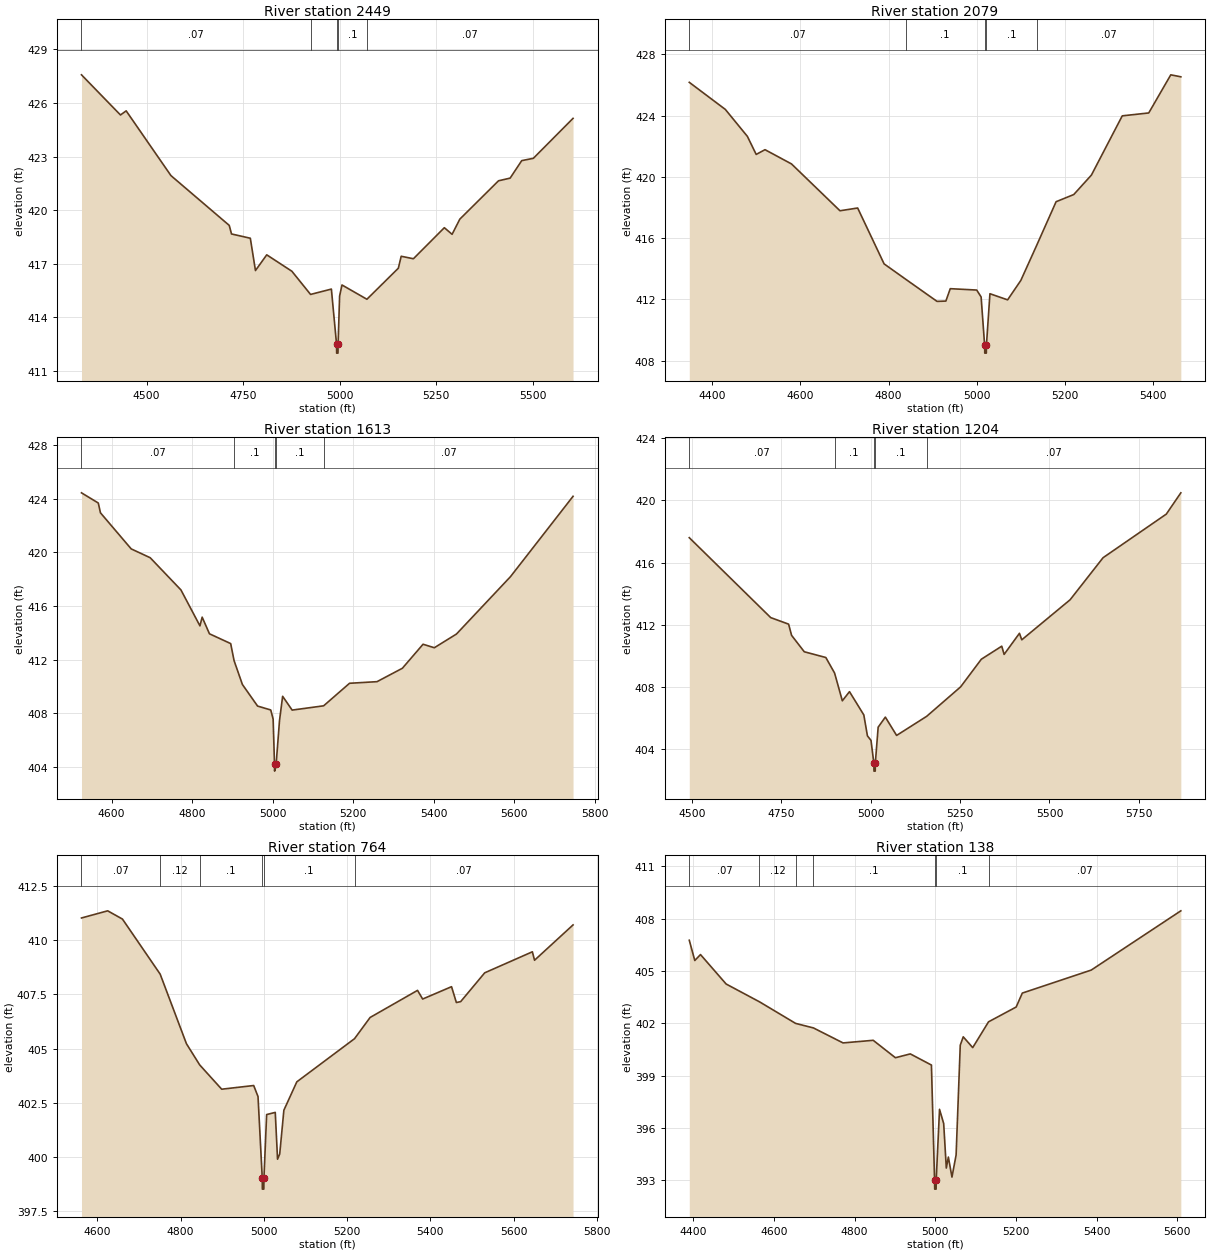
Type RM Length L Ch R = 1,2449,370,370,370
BEGIN DESCRIPTION:
XS7303
END DESCRIPTION:
XS GIS Cut Line= 4
      2389267.36     13594474.67      2389312.50     13594884.38
      2389673.61     13595110.07      2390107.60     13595137.84
#Sta/Elev= 30
  4331.3  427.58  4432.2  425.33  4447.0  425.56  4563.0  421.93  4713.9  419.14
  4719.8  418.66  4768.5  418.42  4781.8  416.61  4811.0  417.49  4876.1  416.57
  4924.5  415.27  4978.4  415.57  4991.8  412.48  4992.0  411.98  4995.5  411.98
  4995.8  412.48  4999.7  415.18  5005.9  415.80  5070.4  415.00  5151.8  416.74
  5159.2  417.41  5190.8  417.27  5270.9  419.01  5291.0  418.64  5311.0  419.49
  5411.2  421.64  5441.3  421.79  5471.3  422.77  5501.4  422.90  5604.2  425.14
#Mann=5,-1,0
  4331.3    0.07       0  4924.5     0.1       0  4991.8    0.05       0
  4995.8     0.1       0  5070.4    0.07       0
Bank Sta=4991.8,4995.8
Exp/Cntr=0.3,0.1

Type RM Length L Ch R = 1,2079,466,466,466
BEGIN DESCRIPTION:
XS7302
END DESCRIPTION:
XS GIS Cut Line= 2
      2389239.58     13594523.26      2389201.39     13595637.80
#Sta/Elev= 30
  4347.9  426.18  4429.7  424.41  4479.7  422.65  4499.7  421.47  4519.7  421.78
  4579.8  420.85  4689.8  417.79  4729.9  417.97  4789.9  414.32  4838.7  413.32
  4910.0  411.87  4930.0  411.89  4940.0  412.70  5000.0  412.61  5010.0  412.16
  5018.0  408.99  5018.3  408.49  5021.8  408.49  5022.0  408.99  5030.0  412.37
  5070.1  411.97  5100.1  413.24  5135.9  415.52  5180.1  418.38  5220.2  418.85
  5260.2  420.12  5330.2  423.99  5390.3  424.18  5440.3  426.67  5463.1  426.54
#Mann=5,-1,0
  4347.9    0.07       0  4838.7     0.1       0  5018.0    0.05       0
  5022.0     0.1       0  5135.9    0.07       0
Bank Sta=5018,5022
Exp/Cntr=0.3,0.1

Type RM Length L Ch R = 1,1613,409,409,409
BEGIN DESCRIPTION:
XS7301
END DESCRIPTION:
XS GIS Cut Line= 3
      2389086.82     13594512.81      2388784.72     13595221.18
      2388986.10     13595623.94
#Sta/Elev= 30
  4525.3  424.44  4567.0  423.68  4572.4  422.95  4648.7  420.26  4695.9  419.60
  4772.2  417.20  4819.4  414.52  4824.9  415.17  4843.0  413.93  4895.7  413.20
  4904.1  411.93  4924.8  410.15  4962.5  408.54  4995.2  408.25  5001.1  407.57
  5004.5  404.19  5004.7  403.69  5008.5  404.19  5016.9  407.45  5024.7  409.27
  5048.3  408.24  5126.5  408.56  5190.8  410.24  5259.0  410.36  5322.0  411.36
  5373.3  413.15  5401.3  412.89  5456.2  413.91  5590.4  418.19  5745.7  424.18
#Mann=5,-1,0
  4525.3    0.07       0  4904.1     0.1       0  5004.5    0.05       0
  5008.5     0.1       0  5126.5    0.07       0
Bank Sta=5004.5,5008.5
Exp/Cntr=0.3,0.1

Type RM Length L Ch R = 1,1204,440,440,440
BEGIN DESCRIPTION:
XS7300
END DESCRIPTION:
XS GIS Cut Line= 4
      2388753.44     13594443.44      2388524.31     13594748.96
      2388493.06     13595172.57      2388860.57     13595605.96
#Sta/Elev= 30
  4492.5  417.60  4720.3  412.45  4770.3  412.03  4778.6  411.31  4814.1  410.25
  4874.4  409.88  4898.9  408.88  4920.6  407.09  4940.6  407.68  4980.7  406.18
  4990.8  404.83  5000.8  404.54  5008.8  403.06  5009.1  402.56  5012.6  402.56
  5012.8  403.06  5020.8  405.39  5040.9  406.04  5072.4  404.86  5156.5  406.09
  5251.5  407.99  5309.4  409.77  5366.5  410.61  5373.1  410.08  5416.0  411.44
  5422.5  411.02  5557.7  413.60  5649.9  416.31  5826.8  419.12  5867.4  420.49
#Mann=5,-1,0
  4492.5    0.07       0  4898.9     0.1       0  5008.8    0.05       0
  5012.8     0.1       0  5156.5    0.07       0
Bank Sta=5008.8,5012.8
Exp/Cntr=0.3,0.1

Type RM Length L Ch R = 1,764,626,626,626
BEGIN DESCRIPTION:
XS7299
END DESCRIPTION:
XS GIS Cut Line= 3
      2388368.05     13594571.88      2388163.19     13594894.79
      2387954.86     13595665.63
#Sta/Elev= 30
  4562.1  411.03  4625.0  411.36  4660.5  410.98  4751.1  408.44  4814.2  405.23
  4846.1  404.25  4898.9  403.13  4975.8  403.30  4986.2  402.79  4996.4  399.02
  4996.6  398.52  5000.1  398.52  5000.4  399.02  5006.9  401.96  5027.6  402.06
  5033.1  399.90  5038.3  400.14  5048.3  402.16  5079.4  403.47  5218.0  405.46
  5255.5  406.44  5369.4  407.69  5381.7  407.29  5451.1  407.86  5462.7  407.13
  5473.0  407.17  5530.8  408.50  5645.3  409.47  5650.5  409.08  5743.0  410.71
#Mann=6,-1,0
  4562.1    0.07       0  4751.1    0.12       0  4846.1     0.1       0
  4996.4    0.05       0  5000.4     0.1       0  5218.0    0.07       0
Bank Sta=4996.4,5000.4
Exp/Cntr=0.3,0.1

Type RM Length L Ch R = 1,138,0,0,0
BEGIN DESCRIPTION:
XS7298
END DESCRIPTION:
XS GIS Cut Line= 4
      2388121.54     13594582.28      2387847.22     13594863.54
      2387750.00     13595269.79      2387791.67     13595676.06
#Sta/Elev= 30
  4389.9  406.76  4403.6  405.60  4417.7  405.94  4481.3  404.25  4563.9  403.23
  4653.6  401.99  4697.8  401.73  4771.2  400.87  4846.0  401.02  4901.1  400.02
  4938.0  400.24  4990.4  399.60  4998.2  392.98  4998.5  392.48  5002.0  392.48
  5002.2  392.98  5010.5  397.06  5020.8  396.24  5027.3  393.69  5032.4  394.32
  5041.3  393.17  5051.6  394.44  5061.9  400.74  5069.3  401.22  5092.8  400.60
  5132.0  402.08  5200.5  402.93  5215.8  403.73  5386.7  405.05  5608.9  408.45
#Mann=7,-1,0
  4389.9    0.07       0  4563.9    0.12       0  4653.6    0.07       0
  4697.8     0.1       0  4998.2    0.05       0  5002.2     0.1       0
  5132.0    0.07       0
Bank Sta=4998.2,5002.2
Exp/Cntr=0.3,0.1

Chan Stop Cuts=-1