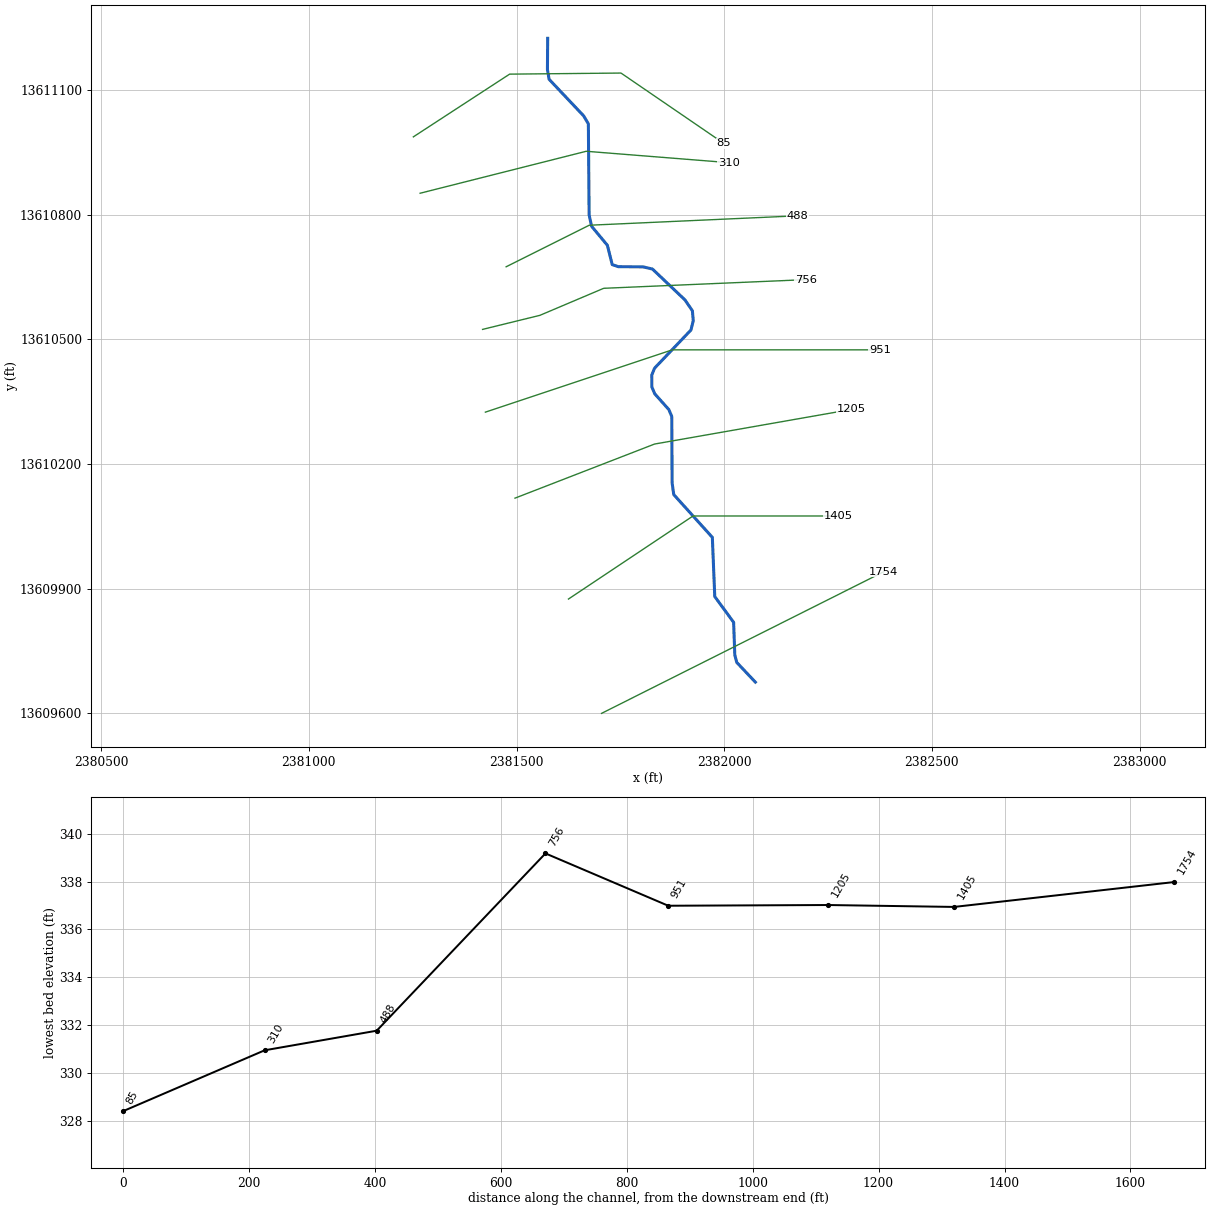
--- Stream0633.prj (project) ---

Proj Title=Stream0633 Base Level Engineering
Current Plan=p01
Default Exp/Contr=0.3,0.1
English Units
Geom File=g01
Flow File=f01
Plan File=p01
BEGIN DESCRIPTION:
Stream0633
END DESCRIPTION:

--- Stream0633.p01 (plan) ---

Plan Title=Multiple Run
Short Identifier=Multiple
Geom File=g01
Flow File=f01
Subcritical Flow
K Sum by GR= 0
Std Step Tol= 0.01
Critical Tol= 0.01
Num of Std Step Trials= 20
Max Error Tol= 0.3
Flow Tol Ratio= 0.001
Split Flow NTrial= 30
Split Flow Tol= 0.02
Split Flow Ratio= 0.02
Log Output Level= 0
Friction Slope Method= 1
Unsteady Friction Slope Method= 2
Unsteady Bridges Friction Slope Method= 1
Parabolic Critical Depth
Global Vel Dist=  1 , 1 , 1
Global Log Level= 0
CheckData=True
Encroach Param= -1, 0, 0, 0
BEGIN DESCRIPTION:
Multiple Run
END DESCRIPTION:

--- Stream0633.f01 (steady flow) ---

Flow Title=Multiple
Number of Profiles=7
Profile Names=10-year,25-year,50-year,1pct_min,100-year,1pct_plu,500-year
River Rch & RM= Stream0633,Reach-1,1754
     228     346     446     280     558    1114     865
Boundary for River Rch & Prof#=Stream0633,Reach-1,1
Up Type=0
Dn Type=3
Dn Slope=0.005
Boundary for River Rch & Prof#=Stream0633,Reach-1,2
Up Type=0
Dn Type=3
Dn Slope=0.005
Boundary for River Rch & Prof#=Stream0633,Reach-1,3
Up Type=0
Dn Type=3
Dn Slope=0.005
Boundary for River Rch & Prof#=Stream0633,Reach-1,4
Up Type=0
Dn Type=3
Dn Slope=0.005
Boundary for River Rch & Prof#=Stream0633,Reach-1,5
Up Type=0
Dn Type=3
Dn Slope=0.005
Boundary for River Rch & Prof#=Stream0633,Reach-1,6
Up Type=0
Dn Type=3
Dn Slope=0.005
Boundary for River Rch & Prof#=Stream0633,Reach-1,7
Up Type=0
Dn Type=3
Dn Slope=0.005

--- Stream0633.g01 (geometry) ---

Geom Title=Existing Conditions

River Reach=Stream0633,Reach-1
Reach XY= 30
      2382075.00     13609675.00      2382030.22     13609722.45
      2382025.53     13609740.22      2382022.68     13609819.04
      2381977.27     13609880.94      2381971.44     13610023.53
      2381878.55     13610126.47      2381874.57     13610154.82
      2381873.76     13610314.50      2381866.81     13610331.08
      2381832.79     13610369.09      2381825.72     13610385.71
      2381825.61     13610414.38      2381832.50     13610431.05
      2381919.92     13610522.72      2381925.47     13610545.17
      2381923.43     13610568.96      2381905.60     13610595.13
      2381827.38     13610669.46      2381804.79     13610674.80
      2381745.25     13610675.21      2381730.44     13610680.25
      2381718.70     13610726.78      2381680.69     13610772.61
      2381674.78     13610799.90      2381672.94     13611019.14
      2381661.60     13611038.31      2381578.39     13611126.41
      2381574.41     13611149.76      2381575.00     13611225.00

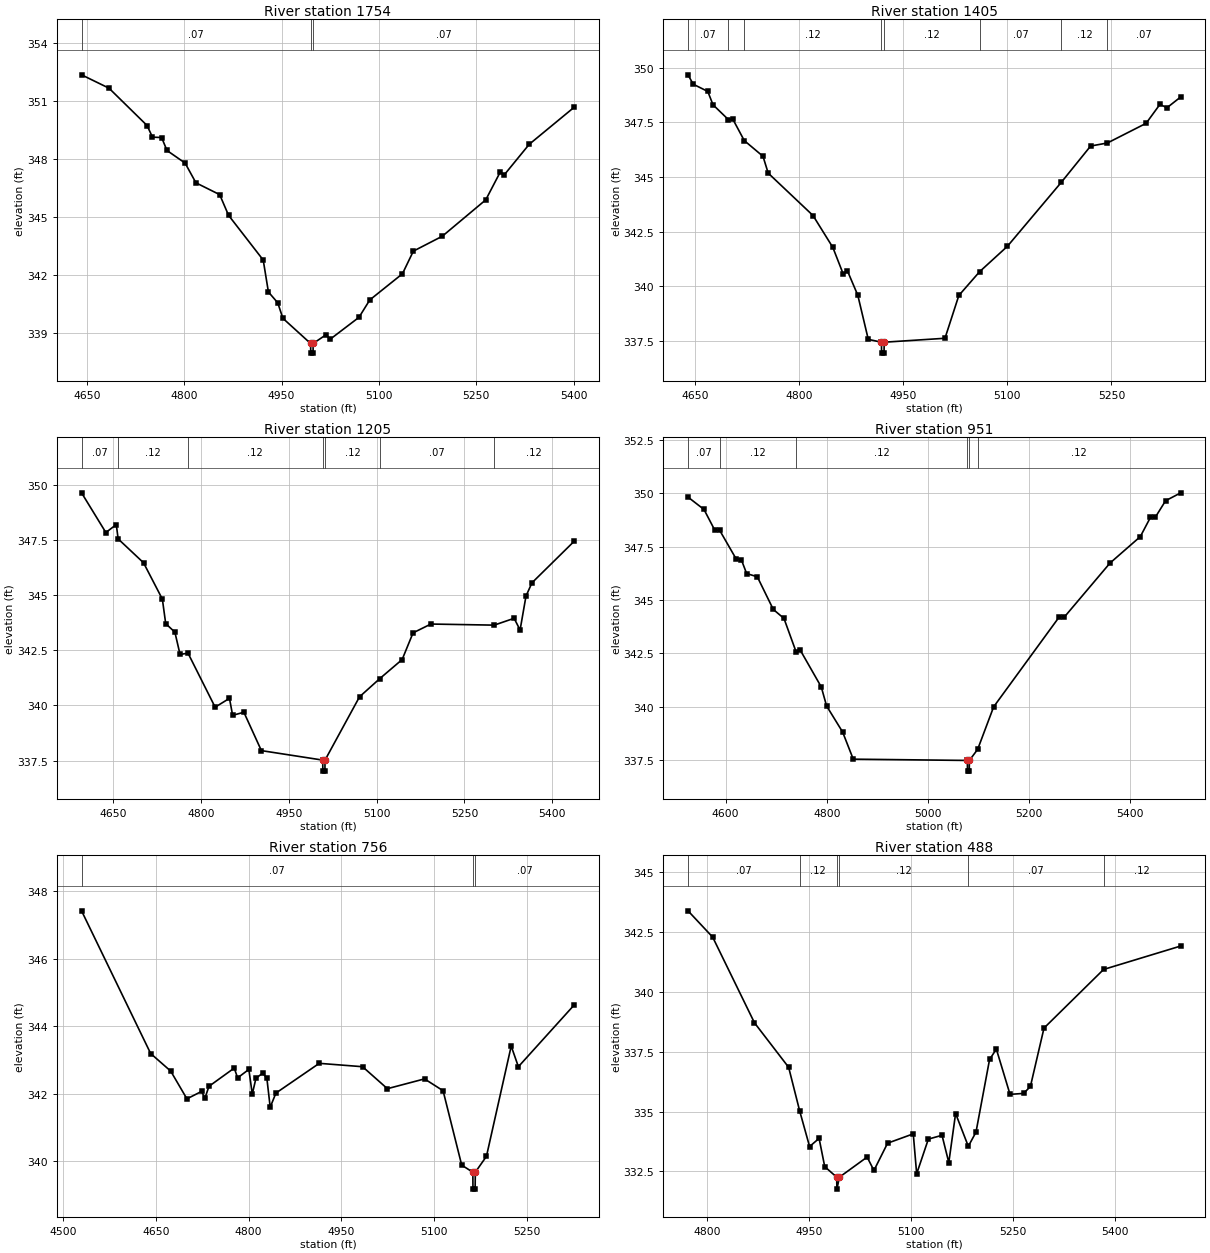
Type RM Length L Ch R = 1,1754,349,349,349
BEGIN DESCRIPTION:
XS7344
END DESCRIPTION:
XS GIS Cut Line= 2
      2381704.71     13609599.75      2382383.51     13609940.45
#Sta/Elev= 30
  4641.7  352.36  4684.0  351.67  4742.7  349.74  4751.0  349.14  4765.1  349.12
  4773.4  348.45  4801.3  347.80  4818.0  346.78  4854.6  346.17  4868.3  345.10
  4921.7  342.79  4929.7  341.14  4944.1  340.58  4952.0  339.78  4994.7  338.48
  4995.0  337.98  4998.5  337.98  4998.7  338.48  5019.0  338.94  5024.6  338.69
  5069.3  339.83  5086.0  340.73  5136.3  342.08  5153.1  343.25  5197.7  344.02
  5264.7  345.90  5287.1  347.34  5292.7  347.17  5331.7  348.77  5401.2  350.69
#Mann=3,-1,0
  4641.7    0.07       0  4994.7    0.05       0  4998.7    0.07       0
Bank Sta=4994.7,4998.7
Exp/Cntr=0.3,0.1

Type RM Length L Ch R = 1,1405,200,200,200
BEGIN DESCRIPTION:
Stream0633 3.0
END DESCRIPTION:
XS GIS Cut Line= 3
      2381625.04     13609875.02      2381925.00     13610075.00
      2382274.99     13610075.00
#Sta/Elev= 30
  4639.5  349.68  4647.0  349.25  4668.0  348.92  4675.5  348.31  4697.7  347.63
  4704.1  347.65  4720.6  346.67  4747.6  345.95  4755.1  345.18  4819.7  343.24
  4848.3  341.78  4863.3  340.56  4869.3  340.71  4884.3  339.59  4899.4  337.57
  4918.4  337.44  4918.6  336.94  4922.1  336.94  4922.4  337.44  5010.0  337.62
  5030.0  339.58  5060.0  340.67  5100.0  341.83  5178.0  344.77  5220.0  346.42
  5244.2  346.56  5300.0  347.46  5320.0  348.33  5330.0  348.17  5350.0  348.67
#Mann=8,-1,0
  4639.5    0.07       0  4697.7    0.12       0  4720.6    0.12       0
  4918.4    0.05       0  4922.4    0.12       0  5060.0    0.07       0
  5178.0    0.12       0  5244.2    0.07       0
Bank Sta=4918.4,4922.4
Exp/Cntr=0.3,0.1

Type RM Length L Ch R = 1,1205,254,254,254
BEGIN DESCRIPTION:
XS7345
END DESCRIPTION:
XS GIS Cut Line= 3
      2381496.35     13610117.97      2381832.29     13610248.18
      2382306.23     13610331.51
#Sta/Elev= 30
  4596.1  349.64  4637.6  347.84  4655.4  348.20  4658.6  347.55  4701.9  346.47
  4734.1  344.82  4739.8  343.71  4755.5  343.32  4764.3  342.31  4777.9  342.37
  4824.2  339.92  4848.7  340.32  4854.1  339.55  4873.3  339.69  4903.2  337.95
  5007.9  337.52  5008.2  337.02  5011.7  337.02  5011.9  337.52  5070.8  340.39
  5105.6  341.22  5143.6  342.08  5162.2  343.29  5192.7  343.69  5300.8  343.64
  5334.8  343.95  5345.0  343.42  5355.1  344.96  5365.3  345.56  5437.6  347.45
#Mann=7,-1,0
  4596.1    0.07       0  4658.6    0.12       0  4777.9    0.12       0
  5007.9    0.05       0  5011.9    0.12       0  5105.6    0.07       0
  5300.8    0.12       0
Bank Sta=5007.9,5011.9
Exp/Cntr=0.3,0.1

Type RM Length L Ch R = 1,951,195,195,195
BEGIN DESCRIPTION:
Stream0633 2.0
END DESCRIPTION:
XS GIS Cut Line= 3
      2381425.02     13610325.01      2381875.00     13610475.00
      2382374.98     13610475.00
#Sta/Elev= 30
  4525.7  349.82  4557.3  349.24  4578.4  348.28  4588.4  348.26  4620.5  346.94
  4631.1  346.89  4641.6  346.24  4662.7  346.09  4694.3  344.56  4715.4  344.14
  4739.3  342.58  4747.0  342.68  4789.2  340.93  4799.7  340.04  4831.4  338.82
  4852.4  337.55  5078.0  337.49  5078.3  336.99  5081.8  336.99  5082.0  337.49
  5098.4  338.01  5130.0  340.00  5260.0  344.22  5270.0  344.21  5360.0  346.73
  5420.0  347.97  5440.0  348.87  5450.0  348.89  5470.0  349.65  5500.0  350.02
#Mann=6,-1,0
  4525.7    0.07       0  4588.4    0.12       0  4739.3    0.12       0
  5078.0    0.05       0  5082.0    0.12       0  5098.4    0.12       0
Bank Sta=5078,5082
Exp/Cntr=0.3,0.1

Type RM Length L Ch R = 1,756,268,268,268
BEGIN DESCRIPTION:
XS7343
END DESCRIPTION:
XS GIS Cut Line= 4
      2381418.23     13610524.22      2381556.25     13610558.07
      2381709.90     13610623.18      2382196.87     13610644.01
#Sta/Elev= 30
  4530.1  347.41  4641.8  343.19  4674.2  342.67  4700.4  341.85  4724.1  342.07
  4729.5  341.87  4736.0  342.22  4776.9  342.76  4782.3  342.47  4800.5  342.72
  4806.0  341.99  4812.0  342.46  4822.9  342.61  4829.6  342.46  4835.0  341.60
  4844.2  342.02  4914.3  342.90  4984.3  342.80  5024.4  342.15  5084.4  342.44
  5114.4  342.09  5144.5  339.89  5162.5  339.68  5162.7  339.18  5166.2  339.18
  5166.5  339.68  5184.5  340.15  5224.5  343.41  5236.1  342.80  5326.5  344.63
#Mann=3,-1,0
  4530.1    0.07       0  5162.5    0.05       0  5166.5    0.07       0
Bank Sta=5162.5,5166.5
Exp/Cntr=0.3,0.1

Type RM Length L Ch R = 1,488,178,178,178
BEGIN DESCRIPTION:
Stream0633 1.0
END DESCRIPTION:
XS GIS Cut Line= 3
      2381475.01     13610675.00      2381675.00     13610775.00
      2382176.09     13610797.66
#Sta/Elev= 30
  4772.0  343.39  4808.3  342.29  4869.8  338.71  4920.1  336.85  4936.3  335.03
  4950.9  333.54  4964.9  333.88  4973.2  332.70  4990.8  332.26  4991.1  331.76
  4994.8  332.26  5035.6  333.10  5045.6  332.54  5065.7  333.68  5103.5  334.07
  5108.5  332.40  5125.7  333.85  5145.8  334.01  5155.8  332.87  5165.8  334.92
  5184.5  333.55  5195.8  334.14  5215.8  337.18  5225.8  337.61  5245.9  335.72
  5265.9  335.76  5275.9  336.05  5295.9  338.49  5383.6  340.94  5497.2  341.92
#Mann=6,-1,0
  4772.0    0.07       0  4936.3    0.12       0  4990.8    0.05       0
  4994.8    0.12       0  5184.5    0.07       0  5383.6    0.12       0
Bank Sta=4990.8,4994.8
Exp/Cntr=0.3,0.1

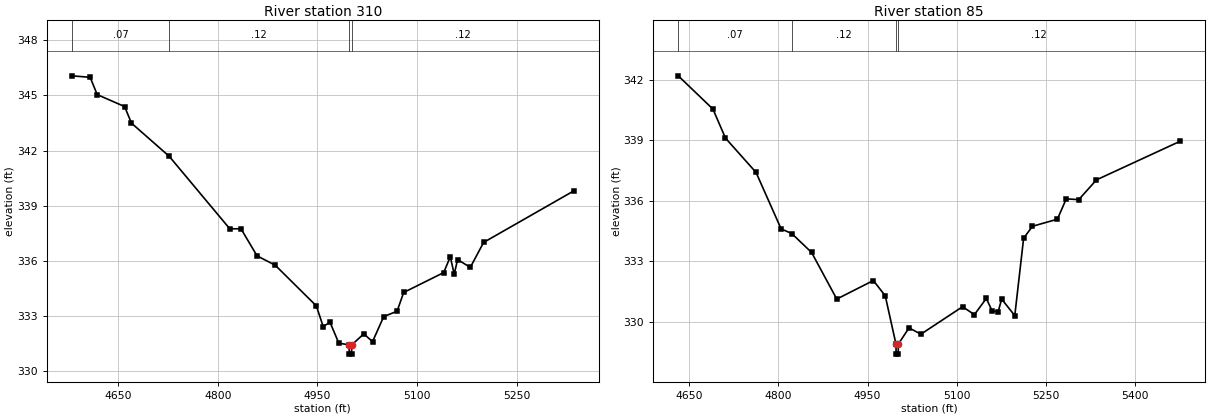
Type RM Length L Ch R = 1,310,225,225,225
BEGIN DESCRIPTION:
E21193
END DESCRIPTION:
XS GIS Cut Line= 3
      2381267.84     13610852.04      2381667.79     13610953.08
      2382010.49     13610925.75
#Sta/Elev= 30
  4580.0  346.06  4607.7  345.98  4618.3  345.04  4659.6  344.39  4669.9  343.49
  4726.7  341.69  4818.0  337.75  4834.9  337.75  4859.1  336.28  4886.5  335.77
  4948.4  333.56  4958.7  332.44  4969.0  332.67  4982.2  331.54  4997.7  331.44
  4998.0  330.94  5001.5  330.94  5001.7  331.44  5019.8  332.04  5033.1  331.62
  5049.9  332.98  5070.0  333.27  5080.0  334.29  5140.2  335.37  5150.2  336.23
  5156.1  335.28  5161.2  336.08  5180.3  335.65  5200.4  337.01  5336.3  339.81
#Mann=4,-1,0
  4580.0    0.07       0  4726.7    0.12       0  4997.7    0.05       0
  5001.7    0.12       0
Bank Sta=4997.7,5001.7
Exp/Cntr=0.3,0.1

Type RM Length L Ch R = 1,85,0,0,0
BEGIN DESCRIPTION:
XS7342
END DESCRIPTION:
XS GIS Cut Line= 4
      2381251.56     13610987.76      2381483.33     13611138.80
      2381751.56     13611141.41      2381999.00     13610972.11
#Sta/Elev= 30
  4631.5  342.19  4689.9  340.54  4711.0  339.10  4762.4  337.40  4804.6  334.60
  4822.5  334.37  4855.9  333.43  4898.2  331.12  4959.8  332.04  4979.8  331.28
  4997.8  328.89  4998.1  328.39  5001.6  328.39  5001.8  328.89  5019.8  329.69
  5039.8  329.38  5109.8  330.74  5129.8  330.35  5149.8  331.15  5159.8  330.52
  5169.8  330.50  5175.6  331.12  5197.7  330.30  5212.6  334.14  5227.5  334.73
  5269.4  335.08  5284.3  336.09  5305.3  336.05  5335.1  337.03  5476.2  338.95
#Mann=4,-1,0
  4631.5    0.07       0  4822.5    0.12       0  4997.8    0.05       0
  5001.8    0.12       0
Bank Sta=4997.8,5001.8
Exp/Cntr=0.3,0.1

Chan Stop Cuts=-1