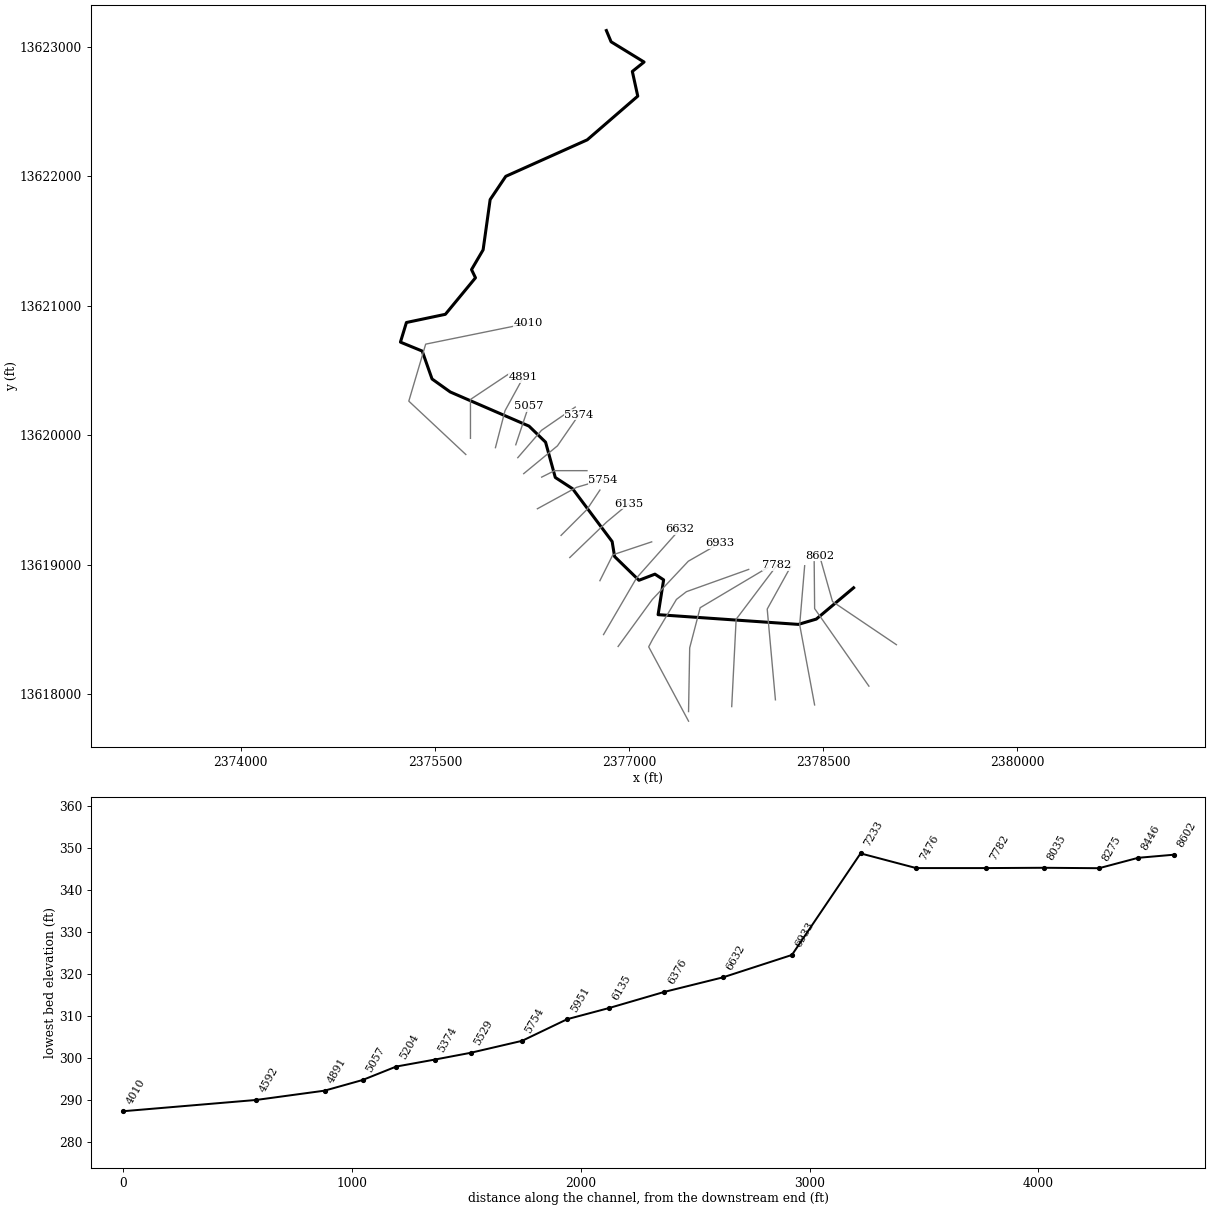
--- Stream0637.prj (project) ---

Proj Title=Stream0637 Base Level Engineering
Current Plan=p01
Default Exp/Contr=0.3,0.1
English Units
Geom File=g01
Flow File=f01
Plan File=p01
Y Axis Title=Elevation
X Axis Title(PF)=Main Channel Distance
X Axis Title(XS)=Station
BEGIN DESCRIPTION:
Stream0637
END DESCRIPTION:
DSS Export Rating Curves= 0
DSS Export Rating Curve Sorted= 0
DSS Export Volume Flow Curves= 0
DXF OffsetX= 0
DXF OffsetY= 0
DXF ScaleX= 1
DXF ScaleY= 10

--- Stream0637.p01 (plan) ---

Plan Title=Multiple Run
Short Identifier=Multiple
Geom File=g01
Flow File=f01
Subcritical Flow
K Sum by GR= 0
Std Step Tol= 0.01
Critical Tol= 0.01
Num of Std Step Trials= 20
Max Error Tol= 0.3
Flow Tol Ratio= 0.001
Split Flow NTrial= 30
Split Flow Tol= 0.02
Split Flow Ratio= 0.02
Log Output Level= 0
Friction Slope Method= 1
Unsteady Friction Slope Method= 2
Unsteady Bridges Friction Slope Method= 1
Parabolic Critical Depth
Global Vel Dist=  1 , 1 , 1
Global Log Level= 0
CheckData=True
Encroach Param= -1, 0, 0, 0
BEGIN DESCRIPTION:
Multiple Run
END DESCRIPTION:

--- Stream0637.f01 (steady flow) ---

Flow Title=Multiple
Number of Profiles=7
Profile Names=10-year,25-year,50-year,1pct_min,100-year,1pct_plu,500-year
River Rch & RM= Stream0637,Reach-1,8602
     184     275     351     219     436     871     664
Boundary for River Rch & Prof#=Stream0637,Reach-1,1
Up Type=0
Dn Type=3
Dn Slope=0.005
Boundary for River Rch & Prof#=Stream0637,Reach-1,2
Up Type=0
Dn Type=3
Dn Slope=0.005
Boundary for River Rch & Prof#=Stream0637,Reach-1,3
Up Type=0
Dn Type=3
Dn Slope=0.005
Boundary for River Rch & Prof#=Stream0637,Reach-1,4
Up Type=0
Dn Type=3
Dn Slope=0.005
Boundary for River Rch & Prof#=Stream0637,Reach-1,5
Up Type=0
Dn Type=3
Dn Slope=0.005
Boundary for River Rch & Prof#=Stream0637,Reach-1,6
Up Type=0
Dn Type=3
Dn Slope=0.005
Boundary for River Rch & Prof#=Stream0637,Reach-1,7
Up Type=0
Dn Type=3
Dn Slope=0.005

--- Stream0637.g01 (geometry) ---

Geom Title=Existing Conditions
Program Version=4.10

River Reach=Stream0637      ,Reach-1
Reach XY= 30
      2378734.94     13618820.16      2378447.03     13618578.52
      2378308.21     13618537.39      2377224.55     13618612.54
      2377267.31     13618881.57      2377200.13     13618925.53
      2377076.63     13618878.13       2376888.4      13619061.7
      2376869.48     13619177.43      2376564.35     13619584.99
      2376430.36      13619672.3      2376355.22     13619945.09
       2376227.3     13620069.17      2375618.83     13620332.88
      2375478.16     13620433.34      2375402.19     13620648.95
      2375233.99     13620717.94      2375280.26     13620869.59
      2375581.17     13620932.86      2375813.74     13621215.01
      2375783.25     13621278.23      2375872.75     13621430.93
      2375927.07     13621819.14      2376047.86     13621998.84
      2376677.29     13622280.84      2377067.41     13622618.37
      2377025.53     13622809.15       2377116.2      13622881.8
      2376861.39     13623038.14        2376825.       13623125.

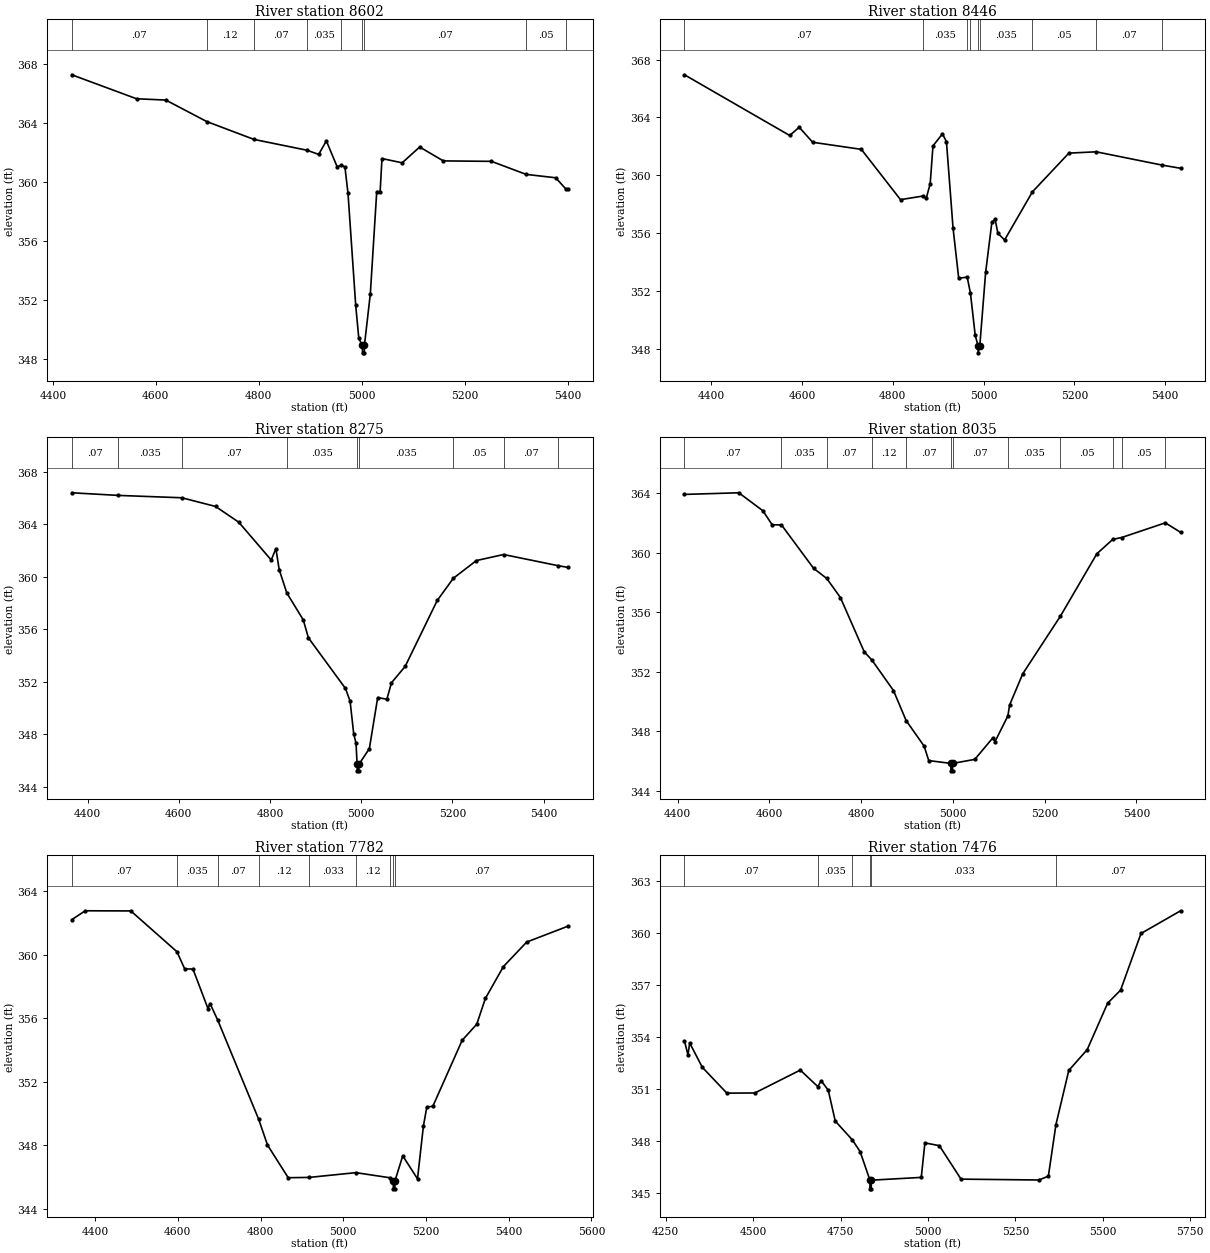
Type RM Length L Ch R = 1 ,8602    ,156,156,156
BEGIN DESCRIPTION:
XS7353
END DESCRIPTION:
XS GIS Cut Line= 3
      2379065.51     13618380.52      2378571.95     13618713.71
      2378472.07      13619067.9
#Sta/Elev= 30
  4436.7  367.24  4562.4  365.62  4619.4  365.53  4698.7  364.08  4790.7  362.87
  4893.6  362.14  4916.1  361.86  4931.1  362.77  4952.1  361.02  4959.5  361.12
  4967.1  361.02  4973.1  359.24  4988.1  351.65  4994.1  349.42    5001  348.95
  5001.3  348.45  5004.8  348.45    5005  348.95  5016.5  352.45  5028.9  359.34
  5035.5  359.34  5039.1  361.58  5078.3  361.29  5112.3  362.36  5158.2  361.42
  5251.7  361.39  5318.9  360.51  5376.4  360.28  5396.8   359.5  5400.2   359.5
#Mann= 9 ,-1 , 0
  4436.7     .07       0  4698.7     .12       0  4790.7     .07       0
  4893.6    .035       0  4959.5     .07       0    5001     .05       0
    5005     .07       0  5318.9     .05       0  5396.8     .07       0
Bank Sta=5001,5005
XS Rating Curve= 0 ,0
Exp/Cntr=0.3,0.1

Type RM Length L Ch R = 1 ,8446    ,171,171,171
BEGIN DESCRIPTION:
E21209
END DESCRIPTION:
XS GIS Cut Line= 3
      2378853.08     13618060.34      2378433.86     13618659.22
      2378430.34     13619021.07
#Sta/Elev= 30
  4341.2  366.95    4573  362.75  4593.9  363.32  4623.6  362.28  4730.8  361.79
  4817.1  358.31  4866.8  358.56  4873.8   358.4  4882.5  359.42  4888.6  362.03
  4909.5  362.86  4918.3  362.32  4932.8  356.35  4945.3  352.87    4964  352.95
  4971.2  351.83  4981.6  348.93  4987.8  348.21    4988  347.71  4991.8  348.21
  5004.6  353.28  5018.3  356.73  5025.5  356.95  5031.6  355.98  5046.4  355.52
  5107.7  358.85    5188  361.53  5248.1  361.62  5393.3   360.7  5434.1  360.48
#Mann= 9 ,-1 , 0
  4341.2     .07       0  4866.8    .035       0    4964     .07       0
  4971.2    .035       0  4987.8    .035       0  4991.8    .035       0
  5107.7     .05       0  5248.1     .07       0  5393.3     .05       0
Bank Sta=4987.8,4991.8
XS Rating Curve= 0 ,0
Exp/Cntr=0.3,0.1

Type RM Length L Ch R = 1 ,8275    ,240,240,240
BEGIN DESCRIPTION:
XS7352
END DESCRIPTION:
XS GIS Cut Line= 3
      2378433.66     13617915.18      2378318.39     13618534.23
      2378356.77     13618990.52
#Sta/Elev= 30
  4365.5   366.4  4467.8   366.2  4606.7  366.02  4680.6  365.36  4731.5  364.16
  4802.7  361.28  4812.9  362.15  4820.2  360.54  4836.9  358.77    4873  356.72
  4884.1  355.36  4965.5   351.5  4975.6  350.53  4983.5  348.05  4988.6  347.32
    4991  345.73  4991.3  345.23  4994.8  345.23    4995  345.73  5017.8  346.92
  5036.1  350.81  5056.2  350.68  5066.2  351.93  5096.3  353.18  5166.6   358.2
  5201.9  359.89  5252.5  361.24  5312.1   361.7  5431.5  360.85  5453.1  360.72
#Mann= 9 ,-1 , 0
  4365.5     .07       0  4467.8    .035       0  4606.7     .07       0
  4836.9    .035       0    4991    .035       0    4995    .035       0
  5201.9     .05       0  5312.1     .07       0  5431.5     .05       0
Bank Sta=4991,4995
XS Rating Curve= 0 ,0
Exp/Cntr=0.3,0.1

Type RM Length L Ch R = 1 ,8035    ,253,253,253
BEGIN DESCRIPTION:
E21208
END DESCRIPTION:
XS GIS Cut Line= 3
      2378130.91     13617954.67       2378067.5      13618655.7
      2378250.33     13618986.21
#Sta/Elev= 30
  4414.9  363.91  4533.3  364.02  4585.9  362.81    4606  361.87  4626.4  361.86
  4696.4  358.94  4725.1  358.26  4754.8  356.98  4806.8  353.33  4823.7  352.77
  4870.5  350.73  4898.1  348.71  4937.4  346.99  4947.4  346.02  4995.6  345.83
  4995.8  345.33  4999.3  345.33  4999.6  345.83  5047.8   346.1    5087  347.54
    5092   347.3  5119.9  349.02  5123.8  349.76  5152.3  351.85  5234.3  355.72
  5313.9  359.92  5348.7  360.89  5367.8  361.01  5463.2     362  5496.5  361.36
#Mann= 12 ,-1 , 0
  4414.9     .07       0  4626.4    .035       0  4725.1     .07       0
  4823.7     .12       0  4898.1     .07       0  4995.6     .05       0
  4999.6     .07       0  5119.9    .035       0  5234.3     .05       0
  5348.7     .07       0  5367.8     .05       0  5463.2     .07       0
Bank Sta=4995.6,4999.6
XS Rating Curve= 0 ,0
Exp/Cntr=0.3,0.1

Type RM Length L Ch R = 1 ,7782    ,306,306,306
BEGIN DESCRIPTION:
XS7351
END DESCRIPTION:
XS GIS Cut Line= 3
      2377793.28      13617902.4      2377827.44     13618576.92
      2378143.33     13618995.26
#Sta/Elev= 30
  4343.6  362.21  4376.2  362.77  4486.4  362.76  4597.9  360.19  4616.6  359.11
  4636.6   359.1  4672.9  356.61  4677.9  356.93  4696.7  355.87  4795.5  349.64
  4816.8  348.02  4866.9  345.96  4917.6  345.98  5030.6  346.28  5112.2  345.96
    5121  345.76  5121.2  345.26  5124.7  345.26    5125  345.76  5143.8  347.34
  5179.5  345.89  5193.7   349.2    5202  350.41  5216.6  350.46  5287.4  354.61
  5322.8  355.63  5343.6  357.25  5387.3  359.26  5443.5   360.8  5543.2   361.8
#Mann= 9 ,-1 , 0
  4343.6     .07       0  4597.9    .035       0  4696.7     .07       0
  4795.5     .12       0  4917.6    .033       0  5030.6     .12       0
  5112.2     .07       0    5121    .033       0    5125     .07       0
Bank Sta=5121,5125
XS Rating Curve= 0 ,0
Exp/Cntr=0.3,0.1

Type RM Length L Ch R = 1 ,7476    ,243,243,243
BEGIN DESCRIPTION:
E21207
END DESCRIPTION:
XS GIS Cut Line= 4
      2377459.75     13617863.87      2377468.64     13618356.27
      2377549.66     13618666.26      2378070.55     13618975.98
#Sta/Elev= 30
  4303.6  353.78  4313.6  352.99  4318.6  353.67  4354.7  352.27  4424.8  350.78
  4504.8  350.79  4634.8  352.11  4684.9  351.16  4694.8  351.49  4714.8  350.95
  4734.8  349.17  4783.5  348.09  4805.9  347.41    4834  345.76  4834.2  345.26
  4837.7  345.26    4838  345.76  4980.8  345.92  4991.2  347.91  5032.5  347.75
  5094.5  345.82  5317.1  345.77  5344.3  345.99    5366  348.97  5402.7  352.09
  5455.4  353.29  5513.8  355.97  5550.8  356.72  5609.2  359.99  5722.5   361.3
#Mann= 6 ,-1 , 0
  4303.6     .07       0  4684.9    .035       0  4783.5    .033       0
    4834    .033       0    4838    .033       0    5366     .07       0
Bank Sta=4834,4838
XS Rating Curve= 0 ,0
Exp/Cntr=0.3,0.1

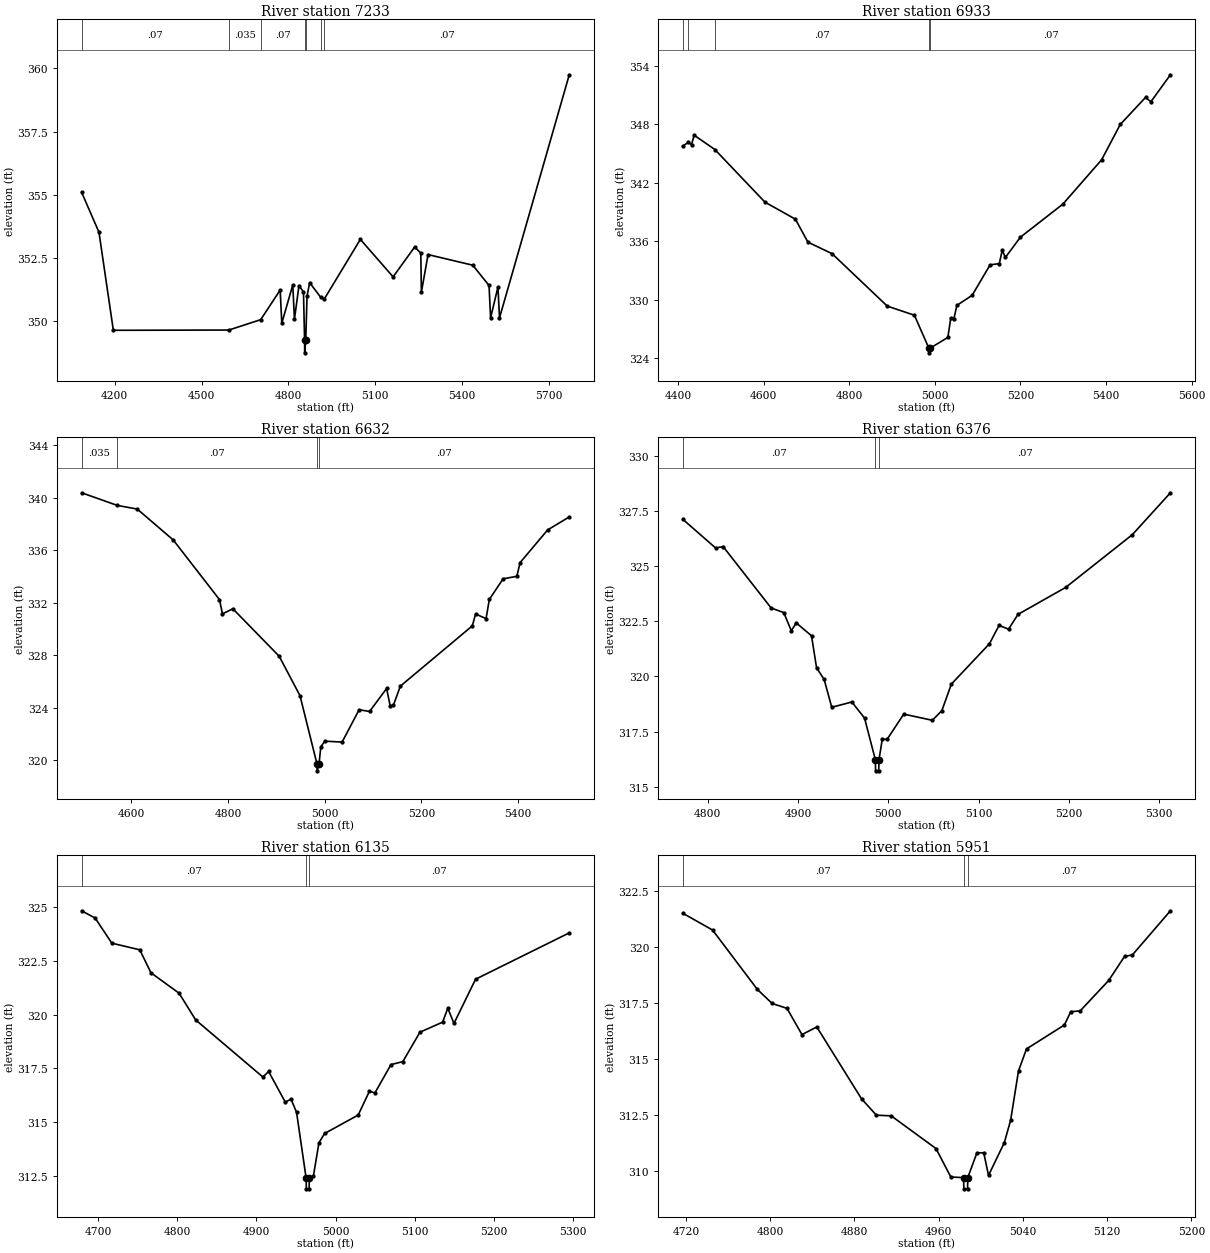
Type RM Length L Ch R = 1 ,7233    ,300,300,300
BEGIN DESCRIPTION:
XS7350
END DESCRIPTION:
XS GIS Cut Line= 6
      2377459.84     13617789.81       2377151.8     13618364.05
       2377182.8     13618423.24      2377366.25     13618730.43
      2377443.47     13618790.17      2377924.27     13618962.09
#Sta/Elev= 30
  4085.6   355.1  4145.6  353.52  4195.2  349.65  4594.1  349.66  4704.2  350.07
  4771.5  351.24  4777.1  349.93    4815  351.44  4820.8  350.09  4836.4  351.41
    4852  351.17  4855.8  349.26  4856.1  348.76  4859.8  349.26  4864.3     351
  4873.4  351.53  4911.7  350.95  4924.1  350.89  5048.5  353.24  5161.6  351.76
  5236.1  352.94  5257.2   352.7  5259.3  351.16  5282.4  352.64  5436.8  352.22
    5493  351.42  5498.3  350.14  5523.8  351.36  5529.1  350.14  5770.1  359.74
#Mann= 7 ,-1 , 0
  4085.6     .07       0  4594.1    .035       0  4704.2     .07       0
  4855.8     .05       0  4859.8     .07       0  4911.7    .033       0
  4924.1     .07       0
Bank Sta=4855.8,4859.8
XS Rating Curve= 0 ,0
Exp/Cntr=0.3,0.1

Type RM Length L Ch R = 1 ,6933    ,301,301,301
BEGIN DESCRIPTION:
E21206
END DESCRIPTION:
XS GIS Cut Line= 4
       2376915.6     13618366.86      2377179.78     13618729.67
      2377458.07     13619025.58      2377704.64     13619166.48
#Sta/Elev= 30
  4411.4  345.75  4424.7  346.15  4431.8  345.89  4437.9  346.87  4486.3   345.4
  4603.3     340  4674.4  338.25  4703.7  335.89  4760.1  334.71  4888.9  329.33
  4952.4  328.39    4986  325.03  4986.3  324.53    4990  325.03  5030.5  326.11
  5037.4  328.12  5044.7  328.03  5051.6   329.4  5087.2  330.43  5129.2  333.56
  5150.7  333.69  5157.6  335.06  5164.9  334.32    5200   336.4  5299.3   339.8
  5389.6  344.34  5433.2  347.97  5492.3  350.75  5504.7   350.3  5550.4  353.07
#Mann= 5 ,-1 , 0
  4411.4     .07       0  4424.7    .035       0  4486.3     .07       0
    4986     .05       0    4990     .07       0
Bank Sta=4986,4990
XS Rating Curve= 0 ,0
Exp/Cntr=0.3,0.1

Type RM Length L Ch R = 1 ,6632    ,256,256,256
BEGIN DESCRIPTION:
Stream0637 6.0
END DESCRIPTION:
XS GIS Cut Line= 3
      2376803.11     13618458.83      2377058.33     13618896.35
      2377391.69     13619271.39
#Sta/Elev= 30
  4497.3  340.36  4570.9   339.4  4612.3  339.12  4686.7  336.77  4782.3  332.23
  4788.5  331.14    4810  331.53  4905.9  327.91  4948.9  324.91  4984.1  319.69
  4984.3  319.19  4988.1  319.69  4991.9  321.01  5000.1  321.45  5035.9  321.38
  5071.1  323.84  5092.8  323.71  5127.9  325.46  5135.5  324.11  5142.1   324.2
  5156.4  325.64  5305.2  330.23  5311.9  331.13  5333.6  330.78  5340.3  332.24
  5368.8  333.81  5397.2     334  5403.9  335.04  5460.8  337.53  5505.6  338.52
#Mann= 4 ,-1 , 0
  4497.3    .035       0  4570.9     .07       0  4984.1     .05       0
  4988.1     .07       0
Bank Sta=4984.1,4988.1
XS Rating Curve= 0 ,0
Exp/Cntr=0.3,0.1

Type RM Length L Ch R = 1 ,6376    ,241,241,241
BEGIN DESCRIPTION:
Stream0637 5.0
END DESCRIPTION:
XS GIS Cut Line= 3
      2376775.02     13618875.04        2376875.       13619075.
      2377175.01       13619175.
#Sta/Elev= 30
  4772.5  327.12  4808.8  325.82  4817.2  325.88  4870.3   323.1  4884.3  322.89
  4892.6  322.07  4898.2  322.42    4915  321.84  4920.6  320.39    4929  319.86
  4937.4   318.6  4959.7  318.84  4973.7  318.11  4985.7  316.22  4985.9  315.72
  4989.4  315.72  4989.7  316.22  4993.3  317.15  4998.7  317.15  5017.1  318.29
  5048.8  318.01  5059.3  318.45  5069.8  319.65    5112  321.48  5122.6  322.31
  5133.1  322.14  5143.6  322.81  5196.3  324.03  5270.1  326.42  5312.3  328.32
#Mann= 3 ,-1 , 0
  4772.5     .07       0  4985.7     .05       0  4989.7     .07       0
Bank Sta=4985.7,4989.7
XS Rating Curve= 0 ,0
Exp/Cntr=0.3,0.1

Type RM Length L Ch R = 1 ,6135    ,184,184,184
BEGIN DESCRIPTION:
E21205
END DESCRIPTION:
XS GIS Cut Line= 3
      2376542.18     13619053.76      2376827.51     13619328.53
      2376996.58     13619469.42
#Sta/Elev= 30
  4679.1  324.84  4696.2   324.5  4717.3  323.33  4752.6  323.02  4766.7  321.95
  4802.2     321  4823.3  319.75  4908.2  317.09  4915.4  317.35  4936.5  315.92
  4943.7  316.06  4950.7  315.45  4962.8  312.38  4963.1  311.88  4966.6  311.88
  4966.8  312.38    4972  312.48    4979  314.03  4986.2  314.46  5028.6  315.32
  5042.8  316.43  5049.7  316.35    5070  317.67    5085  317.81  5106.6  319.18
  5135.3  319.65  5141.8   320.3  5149.6  319.59  5176.9  321.65  5295.3  323.81
#Mann= 3 ,-1 , 0
  4679.1     .07       0  4962.8     .05       0  4966.8     .07       0
Bank Sta=4962.8,4966.8
XS Rating Curve= 0 ,0
Exp/Cntr=0.3,0.1

Type RM Length L Ch R = 1 ,5951    ,197,197,197
BEGIN DESCRIPTION:
Stream0637 4.0
END DESCRIPTION:
XS GIS Cut Line= 3
      2376474.97     13619224.97        2376675.       13619425.
      2376775.02     13619575.03
#Sta/Elev= 30
  4716.9  321.51  4745.2  320.76  4787.7  318.11  4801.8  317.48  4815.9  317.26
  4830.1  316.09  4844.2  316.43  4886.7  313.22  4900.8  312.49  4914.9  312.46
  4957.4     311  4971.5  309.73  4983.6   309.7  4983.9   309.2  4987.4   309.2
  4987.6   309.7  4996.3  310.81  5002.8  310.81  5007.3   309.8  5022.3  311.26
  5028.3  312.26  5035.8  314.47  5043.4  315.45  5079.4  316.52  5085.4  317.11
  5094.4  317.15  5121.5  318.51  5136.5  319.58    5144  319.65  5180.1  321.62
#Mann= 3 ,-1 , 0
  4716.9     .07       0  4983.6     .05       0  4987.6     .07       0
Bank Sta=4983.6,4987.6
XS Rating Curve= 0 ,0
Exp/Cntr=0.3,0.1

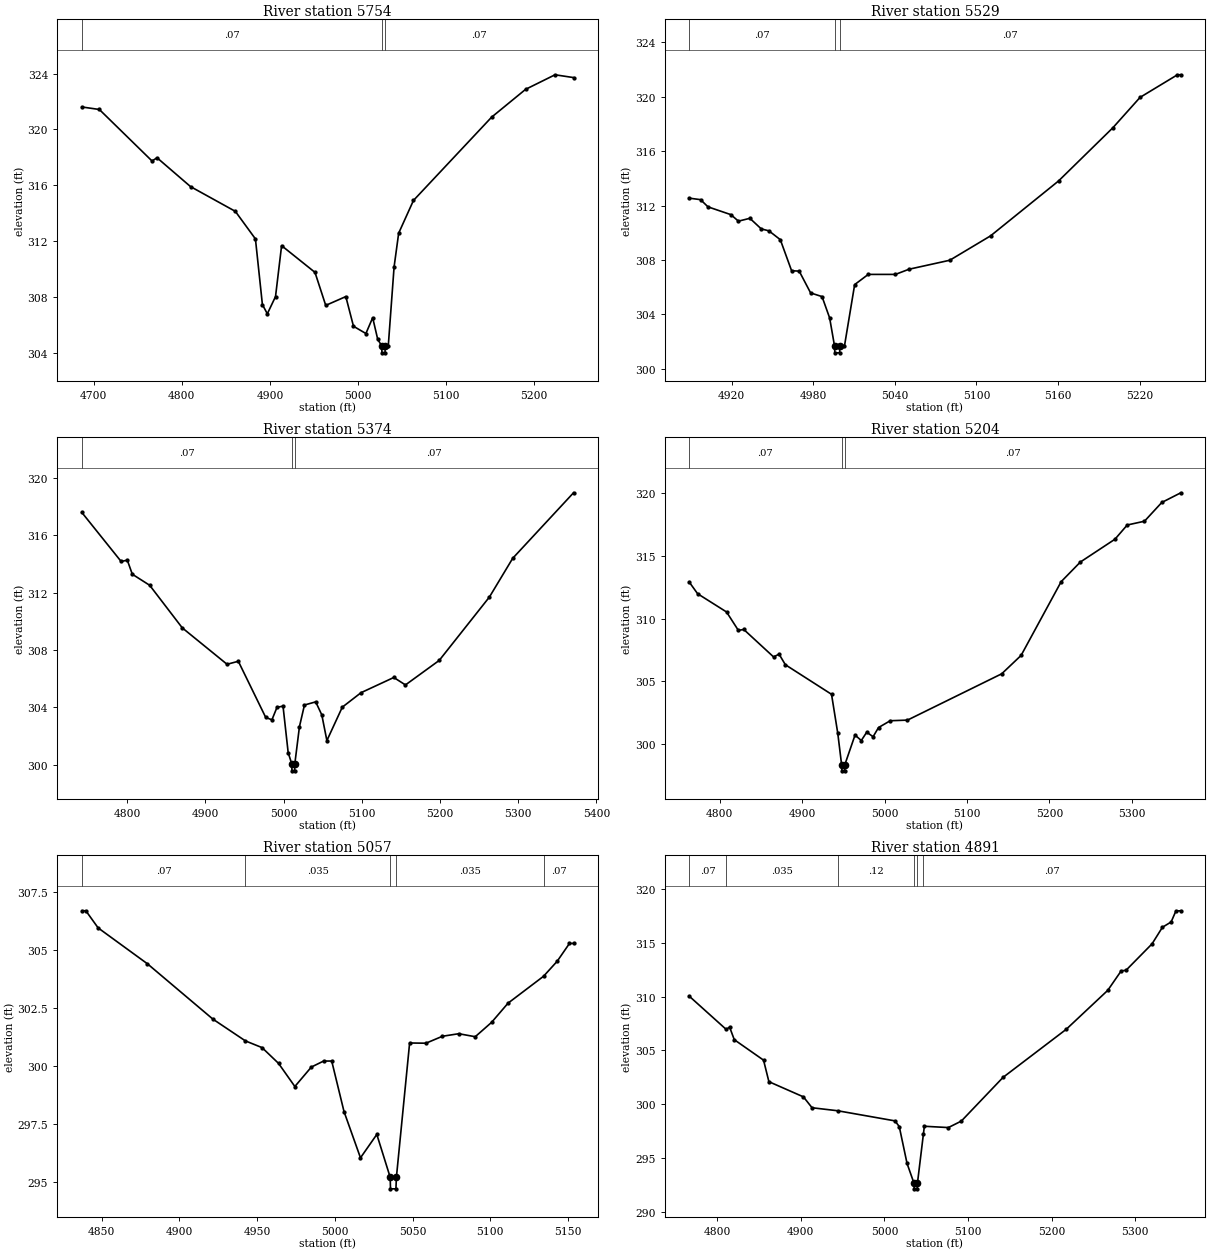
Type RM Length L Ch R = 1 ,5754    ,225,225,225
BEGIN DESCRIPTION:
E21204
END DESCRIPTION:
XS GIS Cut Line= 3
      2376292.04     13619430.68      2376595.01     13619596.25
      2376799.35     13619656.15
#Sta/Elev= 30
  4686.5  321.61  4706.4  321.43  4766.2  317.75  4771.9  317.98  4809.9  315.92
  4860.8  314.15  4883.6  312.18  4891.5  307.49  4897.1  306.83  4906.4  308.06
  4913.3   311.7  4951.2  309.79  4963.4  307.43  4986.2  308.06  4994.9  305.94
    5009  305.42  5016.7  306.55  5022.4  305.01  5026.9  304.54  5027.2  304.04
  5030.7  304.04  5030.9  304.54  5034.4  304.54    5041  310.18  5046.2  312.59
    5063  314.93  5151.7  320.88  5190.3  322.87  5223.7  323.91  5244.7  323.71
#Mann= 3 ,-1 , 0
  4686.5     .07       0  5026.9     .05       0  5030.9     .07       0
Bank Sta=5026.9,5030.9
XS Rating Curve= 0 ,0
Exp/Cntr=0.3,0.1

Type RM Length L Ch R = 1 ,5529    ,155,155,155
BEGIN DESCRIPTION:
Stream0637 3.0
END DESCRIPTION:
XS GIS Cut Line= 3
      2376325.03     13619675.01        2376425.       13619725.
      2376675.02       13619725.
#Sta/Elev= 30
  4888.6  312.54    4897  312.43  4902.5   311.9  4919.3  311.33  4924.9  310.85
  4933.3  311.06  4941.7  310.28  4947.3  310.14  4955.7  309.49    4964  307.21
  4969.6  307.18    4978  305.58  4986.4  305.31    4992  303.74  4995.6  301.68
  4995.8  301.18  4999.3  301.18  4999.6  301.68  5002.9  301.68  5010.4  306.19
  5020.4  306.94  5040.4  306.94  5050.4  307.32  5080.4  307.98  5110.4  309.77
  5160.4   313.8  5200.4  317.71  5220.4  319.94  5247.9   321.6  5250.4   321.6
#Mann= 3 ,-1 , 0
  4888.6     .07       0  4995.6     .05       0  4999.6     .07       0
Bank Sta=4995.6,4999.6
XS Rating Curve= 0 ,0
Exp/Cntr=0.3,0.1

Type RM Length L Ch R = 1 ,5374    ,170,170,170
BEGIN DESCRIPTION:
E21203
END DESCRIPTION:
XS GIS Cut Line= 3
       2376186.4     13619701.95      2376447.06     13619916.82
      2376612.63     13620156.37
#Sta/Elev= 30
  4741.8   317.6  4792.1  314.18    4800  314.27  4806.4  313.29  4828.6  312.52
  4870.3  309.55  4927.6  307.01    4942  307.22  4977.1   303.3    4985  303.14
  4991.5  304.01  4999.2  304.09  5005.8  300.84  5010.3  300.08  5010.6  299.58
  5014.1  299.58  5014.3  300.08  5020.2  302.66  5026.6  304.17    5041  304.39
  5048.8  303.48  5055.3  301.69    5075  304.02    5099  305.03  5140.9  306.09
  5155.8  305.57    5199  307.28  5263.2   311.7    5293   314.4  5370.8  318.97
#Mann= 3 ,-1 , 0
  4741.8     .07       0  5010.3     .05       0  5014.3     .07       0
Bank Sta=5010.3,5014.3
XS Rating Curve= 0 ,0
Exp/Cntr=0.3,0.1

Type RM Length L Ch R = 1 ,5204    ,147,147,147
BEGIN DESCRIPTION:
E21202
END DESCRIPTION:
XS GIS Cut Line= 3
       2376140.6     13619825.25      2376323.76     13620036.59
      2376584.48     13620216.27
#Sta/Elev= 30
    4763  312.91  4773.3  311.97  4808.4  310.52  4822.7  309.06  4829.3  309.13
  4865.4  306.95  4872.1  307.17  4879.7  306.33  4935.7  303.98  4943.3  300.87
  4947.9   298.4  4948.2   297.9  4951.7   297.9  4951.9   298.4  4964.2  300.74
  4971.8  300.31  4978.4  300.97  4986.1  300.61  4992.7  301.34  5006.9  301.88
  5027.8  301.93  5142.1  305.61  5165.6  307.07  5214.2  312.93  5237.5  314.49
  5279.4   316.3  5294.3  317.43  5315.2  317.73  5336.2  319.22  5359.3  319.99
#Mann= 3 ,-1 , 0
    4763     .07       0  4947.9     .05       0  4951.9     .07       0
Bank Sta=4947.9,4951.9
XS Rating Curve= 0 ,0
Exp/Cntr=0.3,0.1

Type RM Length L Ch R = 1 ,5057    ,166,166,166
BEGIN DESCRIPTION:
Stream0637 2.0
END DESCRIPTION:
XS GIS Cut Line= 3
        2376125.     13619925.01        2376175.       13620075.
      2376224.99     13620224.98
#Sta/Elev= 30
  4837.3   306.7  4839.9   306.7  4847.8  305.96  4879.5  304.41  4921.6  302.02
  4942.5  301.08  4953.2  300.79  4963.8  300.11  4974.3  299.11  4984.9  299.95
  4992.8  300.21    4998  300.21  5005.9  298.03  5016.5  296.03    5027  297.04
  5035.6  295.19  5035.8  294.69  5039.3  294.69  5039.6  295.19  5048.1  300.99
  5058.6  300.98  5069.2  301.28  5079.7  301.39  5090.3  301.26  5100.8  301.88
  5111.4  302.71  5134.2  303.87    5143  304.52  5150.9  305.29  5153.5  305.29
#Mann= 5 ,-1 , 0
  4837.3     .07       0  4942.5    .035       0  5035.6    .035       0
  5039.6    .035       0  5134.2     .07       0
Bank Sta=5035.6,5039.6
XS Rating Curve= 0 ,0
Exp/Cntr=0.3,0.1

Type RM Length L Ch R = 1 ,4891    ,299,299,299
BEGIN DESCRIPTION:
E21201
END DESCRIPTION:
XS GIS Cut Line= 3
      2375967.97      13619902.7      2376041.95     13620188.07
      2376182.84     13620445.19
#Sta/Elev= 30
  4766.4  310.05  4810.8  306.95  4814.8  307.17  4820.4     306  4855.4   304.1
  4861.8   302.1  4903.1  300.69  4913.4  299.68  4944.1   299.4  5012.6  298.46
  5017.7  297.93    5027  294.51  5035.4  292.65  5035.6  292.15  5039.1  292.15
  5039.4  292.65  5046.6  297.26  5047.7  297.96  5076.4  297.84  5091.9  298.44
  5141.8   302.5  5217.3  306.96    5267  310.58  5283.1  312.39  5288.8  312.44
    5320   314.9  5332.4  316.44  5342.8  316.93  5348.5  317.95  5354.4  317.97
#Mann= 6 ,-1 , 0
  4766.4     .07       0  4810.8    .035       0  4944.1     .12       0
  5035.4     .05       0  5039.4     .12       0  5046.6     .07       0
Bank Sta=5035.4,5039.4
XS Rating Curve= 0 ,0
Exp/Cntr=0.3,0.1

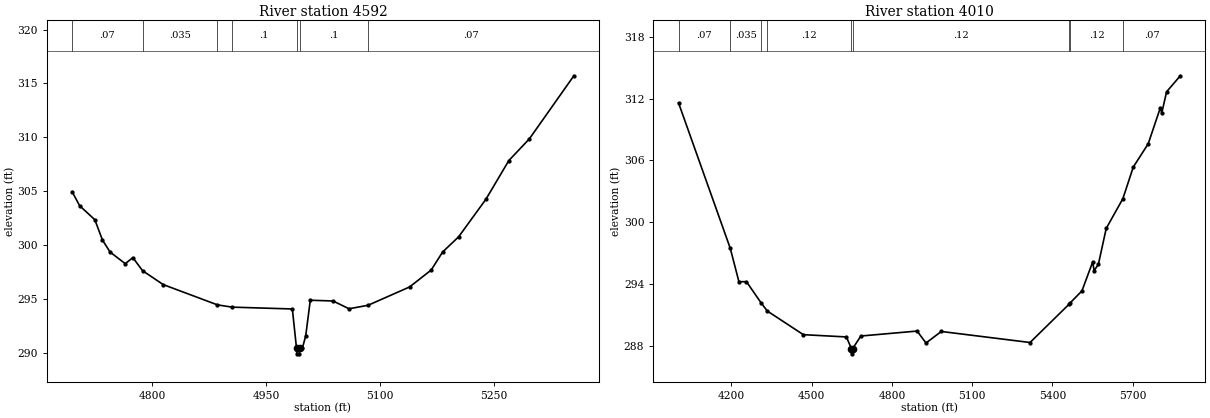
Type RM Length L Ch R = 1 ,4592    ,582,582,582
BEGIN DESCRIPTION:
Stream0637 1.0
END DESCRIPTION:
XS GIS Cut Line= 3
        2375775.     13619974.95        2375775.       13620275.
        2376075.       13620475.
#Sta/Elev= 30
  4694.2  304.97  4704.2  303.66  4724.2  302.36  4734.2  300.48  4744.2  299.37
  4764.2  298.29  4774.2  298.85    4787  297.64  4814.2  296.35  4885.6  294.47
  4904.7  294.26  4984.2  294.09  4989.7  290.43    4990  289.93  4993.5  289.93
  4993.7  290.43  4997.3  290.43  5001.8   291.6  5007.8   294.9  5037.8  294.83
  5058.8  294.11  5083.8  294.43  5138.5  296.13    5167   297.7    5182  299.37
  5203.1  300.78  5239.1  304.27  5269.2  307.85  5296.2  309.86  5354.8  315.71
#Mann= 7 ,-1 , 0
  4694.2     .07       0    4787    .035       0  4885.6     .07       0
  4904.7      .1       0  4989.7     .07       0  4993.7      .1       0
  5083.8     .07       0
Bank Sta=4989.7,4993.7
XS Rating Curve= 0 ,0
Exp/Cntr=0.3,0.1

Type RM Length L Ch R = 1 ,4010    ,0,0,0
BEGIN DESCRIPTION:
E21200
END DESCRIPTION:
XS GIS Cut Line= 4
      2375739.03     13619849.86      2375298.66     13620262.04
        2375429.     13620702.38      2376225.18     13620864.43
#Sta/Elev= 30
  4002.8  311.59  4196.2  297.47  4228.4  294.24  4256.7  294.24  4310.6  292.21
  4334.7  291.39  4469.2   289.1  4629.9  288.88    4649  287.74  4649.2  287.24
    4653  287.74  4684.2  288.97  4894.2  289.45  4927.5  288.29  4984.5  289.41
  5316.2  288.34    5463  292.08  5466.4  292.19  5510.1  293.35  5550.3  296.16
  5555.4  295.32  5571.4  295.91  5600.8  299.41  5663.1   302.3    5702  305.37
  5757.7  307.62  5803.2  311.13  5808.3  310.61  5826.5  312.67  5877.7  314.22
#Mann= 9 ,-1 , 0
  4002.8     .07       0  4196.2    .035       0  4310.6     .07       0
  4334.7     .12       0    4649     .05       0    4653     .12       0
    5463     .07       0  5466.4     .12       0  5663.1     .07       0
Bank Sta=4649,4653
XS Rating Curve= 0 ,0
Exp/Cntr=0.3,0.1

Chan Stop Cuts=-1
Use User Specified Reach Order=0
Composite Channel Slope=5