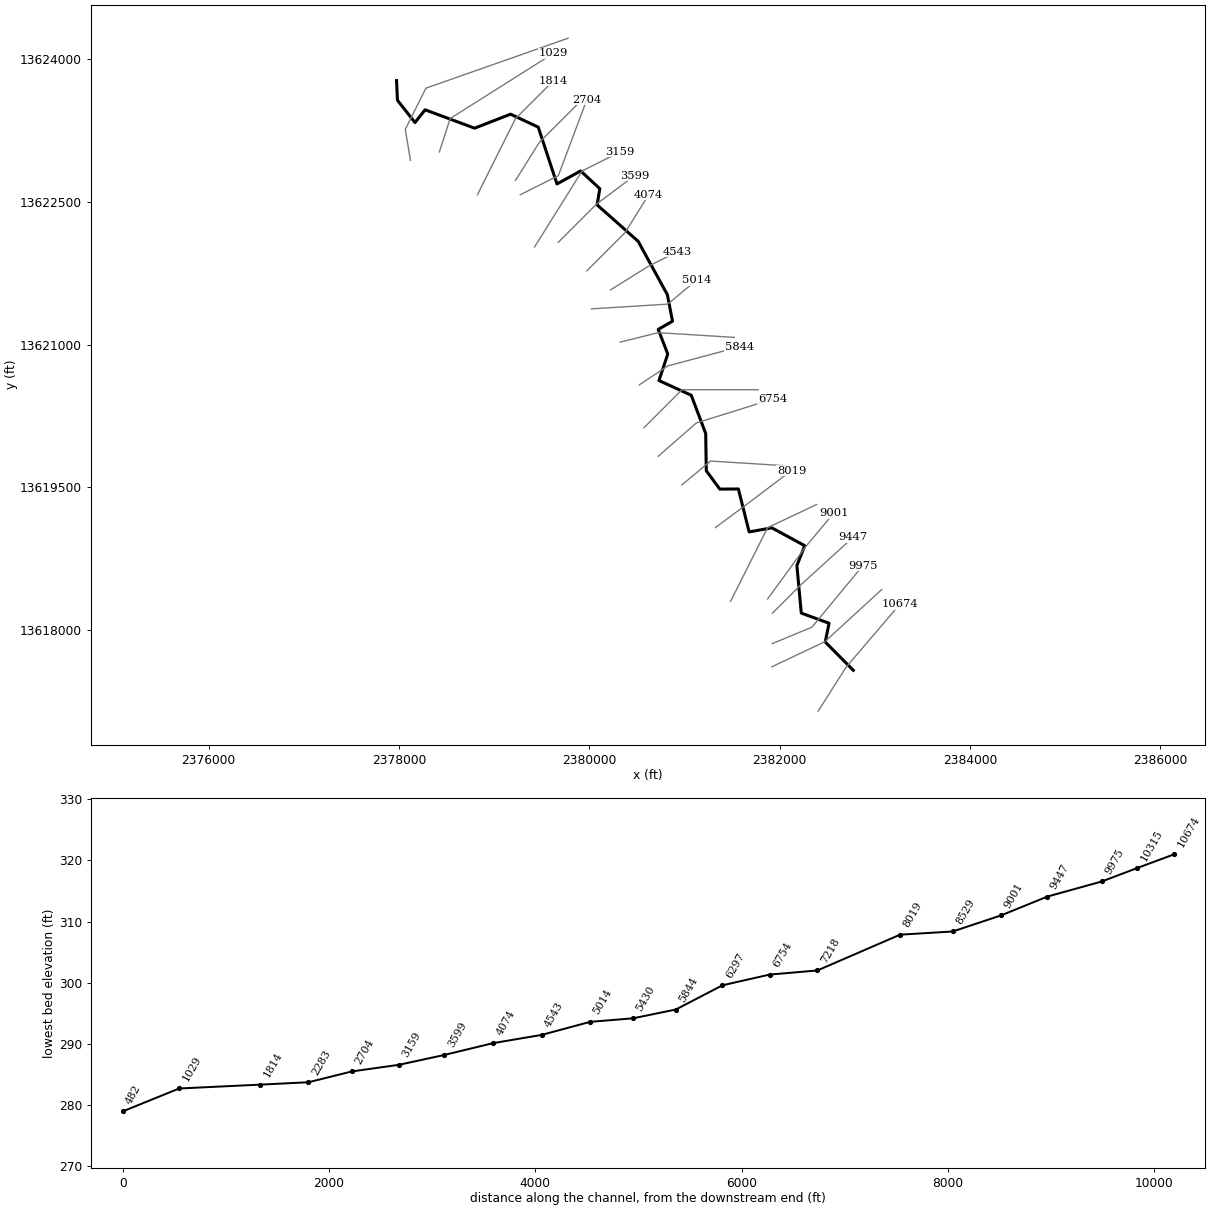
--- Stream0639.prj (project) ---

Proj Title=Stream0639 Base Level Engineering
Current Plan=p01
Default Exp/Contr=0.3,0.1
English Units
Geom File=g01
Flow File=f01
Plan File=p01
BEGIN DESCRIPTION:
Stream0639
END DESCRIPTION:

--- Stream0639.p01 (plan) ---

Plan Title=Multiple Run
Short Identifier=Multiple
Geom File=g01
Flow File=f01
Subcritical Flow
K Sum by GR= 0
Std Step Tol= 0.01
Critical Tol= 0.01
Num of Std Step Trials= 20
Max Error Tol= 0.3
Flow Tol Ratio= 0.001
Split Flow NTrial= 30
Split Flow Tol= 0.02
Split Flow Ratio= 0.02
Log Output Level= 0
Friction Slope Method= 1
Unsteady Friction Slope Method= 2
Unsteady Bridges Friction Slope Method= 1
Parabolic Critical Depth
Global Vel Dist=  1 , 1 , 1
Global Log Level= 0
CheckData=True
Encroach Param= -1, 0, 0, 0
BEGIN DESCRIPTION:
Multiple Run
END DESCRIPTION:

--- Stream0639.f01 (steady flow) ---

Flow Title=Multiple
Number of Profiles=7
Profile Names=10-year,25-year,50-year,1pct_min,100-year,1pct_plu,500-year
River Rch & RM= Stream0639,Reach-1,10674
     569     915    1226     795    1587    3167    2637
River Rch & RM= Stream0639,Reach-1,7218
     733    1191    1608    1049    2094    4177    3521
Boundary for River Rch & Prof#=Stream0639,Reach-1,1
Up Type=0
Dn Type=3
Dn Slope=0.005
Boundary for River Rch & Prof#=Stream0639,Reach-1,2
Up Type=0
Dn Type=3
Dn Slope=0.005
Boundary for River Rch & Prof#=Stream0639,Reach-1,3
Up Type=0
Dn Type=3
Dn Slope=0.005
Boundary for River Rch & Prof#=Stream0639,Reach-1,4
Up Type=0
Dn Type=3
Dn Slope=0.005
Boundary for River Rch & Prof#=Stream0639,Reach-1,5
Up Type=0
Dn Type=3
Dn Slope=0.005
Boundary for River Rch & Prof#=Stream0639,Reach-1,6
Up Type=0
Dn Type=3
Dn Slope=0.005
Boundary for River Rch & Prof#=Stream0639,Reach-1,7
Up Type=0
Dn Type=3
Dn Slope=0.005

--- Stream0639.g01 (geometry) ---

Geom Title=Existing Conditions

River Reach=Stream0639,Reach-1
Reach XY= 30
      2382775.00     13617575.00      2382480.40     13617872.57
      2382520.38     13618069.76      2382228.54     13618176.44
      2382182.33     13618675.10      2382264.70     13618885.10
      2381919.06     13619072.75      2381680.61     13619029.77
      2381567.31     13619481.57      2381372.45     13619479.99
      2381230.13     13619672.72      2381223.95     13620064.57
      2381071.85     13620466.69      2380732.76     13620621.58
      2380825.32     13620899.96      2380725.23     13621159.00
      2380875.13     13621245.25      2380821.24     13621523.44
      2380514.49     13622084.81      2380082.63     13622468.50
      2380111.47     13622638.38      2379909.58     13622825.13
      2379660.91     13622688.33      2379464.04     13623285.43
      2379173.36     13623421.86      2378795.18     13623274.71
      2378274.69     13623467.77      2378168.49     13623333.89
      2377984.43     13623568.39      2377975.00     13623775.00

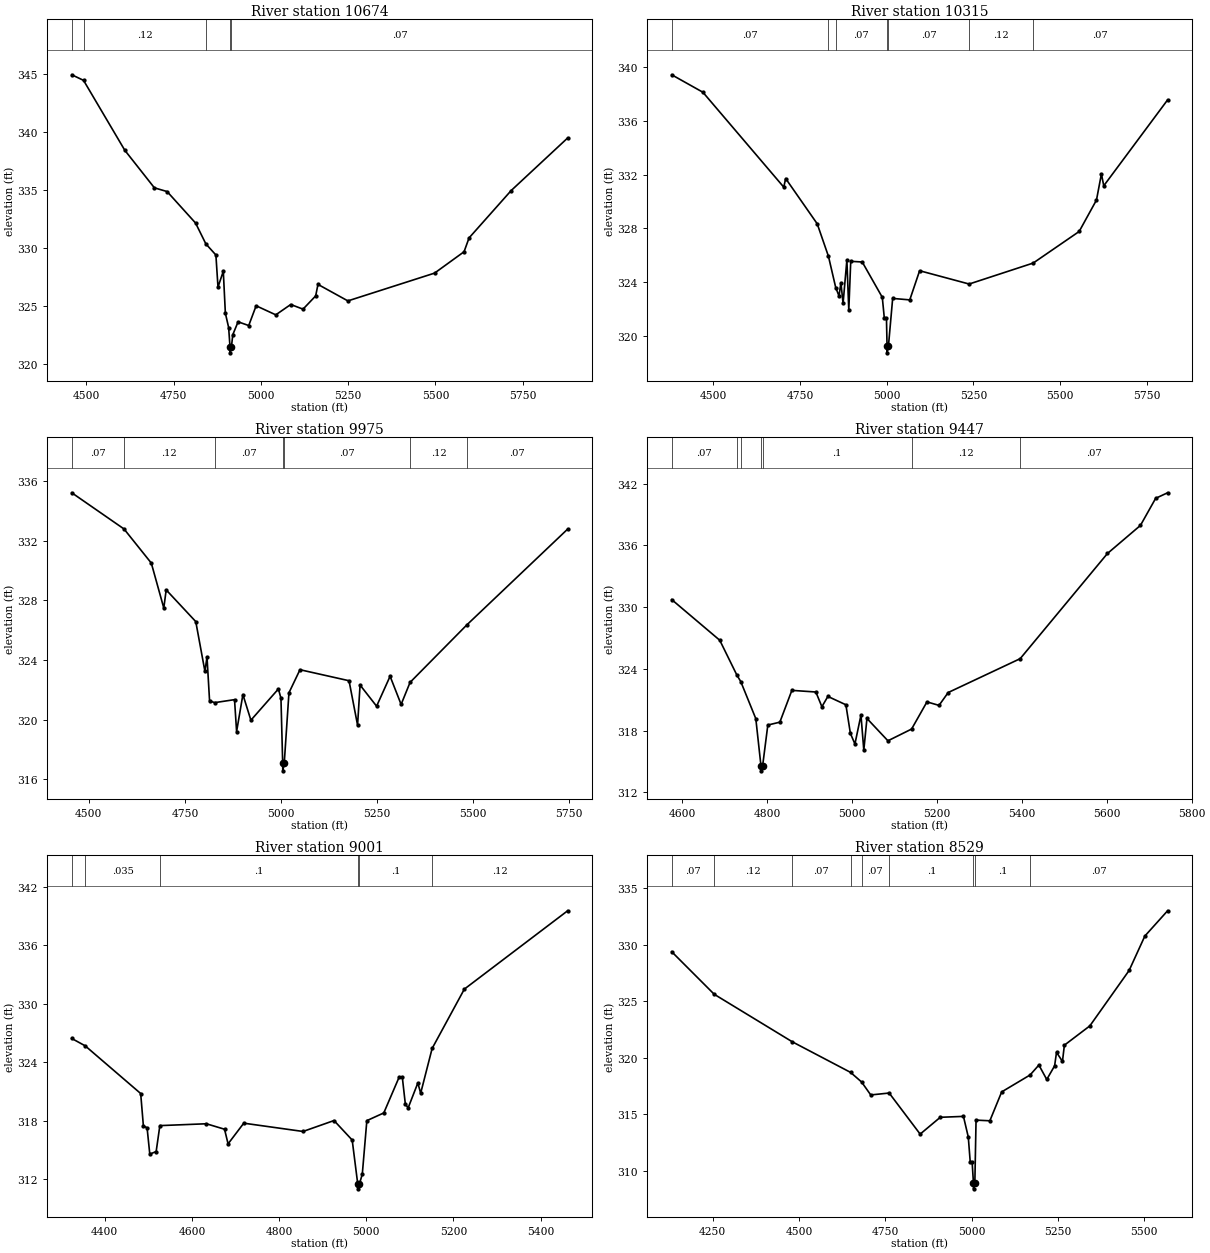
Type RM Length L Ch R = 1,10674,359,359,359
BEGIN DESCRIPTION:
XS7361
END DESCRIPTION:
XS GIS Cut Line= 3
      2382406.02     13617145.81      2382698.54     13617606.26
      2383266.25     13618271.29
#Sta/Elev= 30
  4458.7  344.92  4492.4  344.44  4610.6  338.42  4695.3  335.19  4731.7  334.87
  4813.2  332.16  4842.6  330.37  4871.4  329.41  4877.4  326.65  4892.6  328.01
  4898.5  324.40  4907.9  323.17  4911.8  321.49  4912.0  320.99  4915.8  321.49
  4919.8  322.55  4934.9  323.66  4965.4  323.34  4986.6  325.04  5042.9  324.26
  5085.7  325.15  5120.9  324.75  5157.1  325.89  5163.7  326.88  5249.3  325.46
  5497.5  327.85  5582.0  329.69  5596.3  330.88  5717.0  334.96  5878.6  339.48
#Mann=5,-1,0
  4458.7    0.07       0  4492.4    0.12       0  4842.6    0.07       0
  4911.8    0.05       0  4915.8    0.07       0
Bank Sta=4911.8,4915.8
Exp/Cntr=0.3,0.1

Type RM Length L Ch R = 1,10315,340,340,340
BEGIN DESCRIPTION:
Stream0639 21.0
END DESCRIPTION:
XS GIS Cut Line= 3
      2381918.46     13617611.67      2382475.00     13617875.00
      2383074.97     13618424.97
#Sta/Elev= 30
  4380.2  339.43  4470.1  338.13  4703.2  331.07  4708.7  331.71  4799.7  328.34
  4832.1  325.92  4853.0  323.60  4862.5  322.97  4868.0  323.96  4874.2  322.42
  4885.2  325.65  4890.7  321.91  4896.3  325.55  4929.5  325.50  4987.3  322.87
  4993.1  321.33  4999.3  321.33  5001.0  319.24  5001.2  318.74  5005.0  319.24
  5017.2  322.79  5066.5  322.68  5094.9  324.85  5237.7  323.86  5422.3  325.42
  5554.9  327.77  5604.8  330.11  5619.0  332.05  5625.8  331.17  5809.8  337.56
#Mann=7,-1,0
  4380.2    0.07       0  4832.1    0.12       0  4853.0    0.07       0
  5001.0    0.05       0  5005.0    0.07       0  5237.7    0.12       0
  5422.3    0.07       0
Bank Sta=5001,5005
Exp/Cntr=0.3,0.1

Type RM Length L Ch R = 1,9975,528,528,528
BEGIN DESCRIPTION:
Stream0639 20.0
END DESCRIPTION:
XS GIS Cut Line= 3
      2381923.91     13617855.47      2382341.01     13618028.80
      2382875.02     13618675.03
#Sta/Elev= 30
  4455.7  335.23  4591.6  332.80  4662.6  330.51  4695.1  327.49  4701.3  328.71
  4778.3  326.58  4802.1  323.24  4807.5  324.21  4814.2  321.25  4827.8  321.14
  4879.1  321.34  4884.5  319.20  4900.9  321.68  4921.7  319.96  4993.3  322.06
  4999.9  321.43  5004.4  317.06  5004.6  316.56  5008.4  317.06  5020.7  321.80
  5049.4  323.35  5177.0  322.61  5199.2  319.63  5205.7  322.32  5248.7  320.90
  5283.8  322.91  5312.5  321.02  5335.8  322.50  5483.9  326.37  5745.7  332.79
#Mann=7,-1,0
  4455.7    0.07       0  4591.6    0.12       0  4827.8    0.07       0
  5004.4    0.05       0  5008.4    0.07       0  5335.8    0.12       0
  5483.9    0.07       0
Bank Sta=5004.4,5008.4
Exp/Cntr=0.3,0.1

Type RM Length L Ch R = 1,9447,446,446,446
BEGIN DESCRIPTION:
Stream0639 19.0
END DESCRIPTION:
XS GIS Cut Line= 3
      2381924.99     13618174.99      2382225.00     13618475.00
      2382775.02     13618975.02
#Sta/Elev= 30
  4575.7  330.73  4688.8  326.78  4729.3  323.38  4738.2  322.77  4773.7  319.16
  4785.8  314.59  4786.1  314.09  4789.8  314.59  4802.0  318.54  4830.3  318.82
  4858.6  321.91  4915.1  321.75  4929.3  320.32  4943.4  321.32  4985.8  320.51
  4996.4  317.73  5007.1  316.70  5021.3  319.51  5028.0  316.10  5035.4  319.18
  5084.8  317.01  5140.5  318.15  5176.7  320.79  5205.1  320.45  5226.7  321.70
  5396.2  324.99  5601.7  335.21  5679.4  337.94  5715.2  340.57  5743.3  341.11
#Mann=7,-1,0
  4575.7    0.07       0  4729.3   0.035       0  4738.2     0.1       0
  4785.8    0.05       0  4789.8     0.1       0  5140.5    0.12       0
  5396.2    0.07       0
Bank Sta=4785.8,4789.8
Exp/Cntr=0.3,0.1

Type RM Length L Ch R = 1,9001,472,472,472
BEGIN DESCRIPTION:
Stream0639 18.0
END DESCRIPTION:
XS GIS Cut Line= 3
      2381874.97     13618324.96      2382275.00     13618875.00
      2382568.53     13619226.02
#Sta/Elev= 30
  4324.3  326.44  4355.0  325.69  4482.4  320.80  4488.6  317.48  4497.1  317.29
  4503.3  314.59  4517.9  314.85  4526.4  317.51  4633.1  317.70  4674.8  317.14
  4682.9  315.64  4718.9  317.76  4854.9  316.91  4926.0  318.03  4967.7  316.03
  4980.4  311.53  4980.6  311.03  4984.4  311.53  4990.9  312.55  5001.3  318.02
  5040.2  318.81  5075.3  322.47  5082.6  322.50  5089.7  319.69  5096.2  319.34
  5118.3  321.88  5124.8  320.83  5151.1  325.42  5225.0  331.50  5462.0  339.53
#Mann=6,-1,0
  4324.3    0.07       0  4355.0   0.035       0  4526.4     0.1       0
  4980.4    0.05       0  4984.4     0.1       0  5151.1    0.12       0
Bank Sta=4980.4,4984.4
Exp/Cntr=0.3,0.1

Type RM Length L Ch R = 1,8529,510,510,510
BEGIN DESCRIPTION:
Stream0639 17.0
END DESCRIPTION:
XS GIS Cut Line= 3
      2381485.08     13618299.67      2381875.00     13619075.00
      2382389.73     13619318.09
#Sta/Elev= 30
  4131.1  329.39  4254.3  325.62  4480.5  321.41  4649.4  318.70  4681.3  317.85
  4707.9  316.70  4761.3  316.87  4851.1  313.23  4909.4  314.72  4976.6  314.80
  4990.6  312.97  4996.2  310.77  5001.7  310.77  5005.6  308.88  5005.8  308.38
  5009.6  308.88  5013.1  314.47  5053.1  314.41  5087.4  316.97  5169.7  318.47
  5195.2  319.35  5218.0  318.07  5240.8  319.28  5246.3  320.48  5263.5  319.67
  5269.1  321.11  5342.9  322.82  5456.7  327.73  5502.3  330.78  5568.2  333.02
#Mann=9,-1,0
  4131.1    0.07       0  4254.3    0.12       0  4480.5    0.07       0
  4649.4   0.035       0  4681.3    0.07       0  4761.3     0.1       0
  5005.6    0.05       0  5009.6     0.1       0  5169.7    0.07       0
Bank Sta=5005.6,5009.6
Exp/Cntr=0.3,0.1

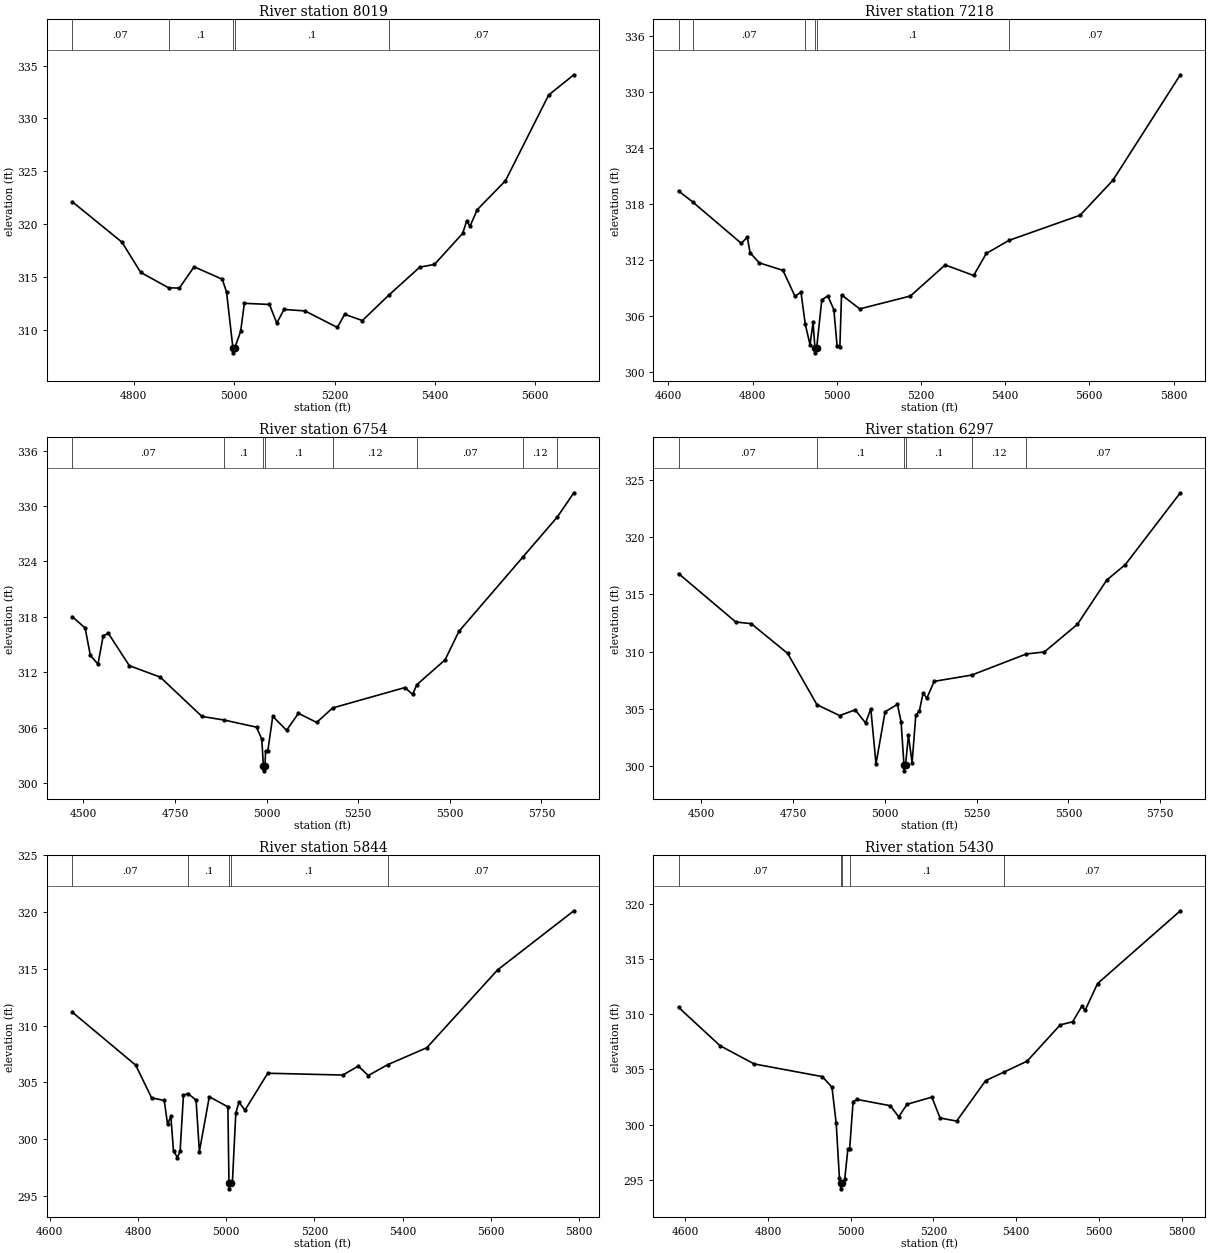
Type RM Length L Ch R = 1,8019,801,801,801
BEGIN DESCRIPTION:
Stream0639 16.0
END DESCRIPTION:
XS GIS Cut Line= 3
      2381324.96     13619074.97      2381631.35     13619301.86
      2382125.03     13619675.03
#Sta/Elev= 30
  4676.9  322.15  4776.5  318.31  4813.7  315.46  4869.4  314.00  4890.8  313.98
  4920.1  315.99  4976.4  314.81  4984.8  313.59  4997.4  308.36  4997.7  307.86
  5001.4  308.36  5012.9  309.89  5020.3  312.54  5070.3  312.43  5084.9  310.67
  5099.4  311.96  5141.1  311.82  5205.6  310.26  5220.2  311.50  5255.5  310.91
  5308.4  313.32  5370.0  315.96  5399.1  316.21  5455.3  319.14  5463.6  320.34
  5469.9  319.81  5484.5  321.39  5540.7  324.12  5626.8  332.22  5677.0  334.13
#Mann=5,-1,0
  4676.9    0.07       0  4869.4     0.1       0  4997.4    0.05       0
  5001.4     0.1       0  5308.4    0.07       0
Bank Sta=4997.4,5001.4
Exp/Cntr=0.3,0.1

Type RM Length L Ch R = 1,7218,464,464,464
BEGIN DESCRIPTION:
Stream0639 15.0
END DESCRIPTION:
XS GIS Cut Line= 3
      2380975.01     13619525.01      2381275.00     13619775.00
      2382075.04     13619725.00
#Sta/Elev= 30
  4624.0  319.36  4658.7  318.14  4773.0  313.75  4787.4  314.40  4793.9  312.74
  4816.0  311.65  4872.0  310.85  4900.6  308.08  4914.9  308.50  4925.1  305.08
  4936.4  302.87  4943.6  305.29  4948.1  302.51  4948.3  302.01  4952.1  302.51
  4964.4  307.70  4978.7  308.11  4993.0  306.64  5000.8  302.70  5007.3  302.63
  5011.2  308.22  5054.6  306.72  5174.8  308.10  5257.5  311.43  5325.1  310.30
  5355.2  312.66  5408.8  314.06  5578.1  316.76  5655.7  320.49  5816.1  331.81
#Mann=6,-1,0
  4624.0    0.12       0  4658.7    0.07       0  4925.1     0.1       0
  4948.1    0.05       0  4952.1     0.1       0  5408.8    0.07       0
Bank Sta=4948.1,4952.1
Exp/Cntr=0.3,0.1

Type RM Length L Ch R = 1,6754,457,457,457
BEGIN DESCRIPTION:
Stream0639 14.0
END DESCRIPTION:
XS GIS Cut Line= 3
      2380724.97     13619824.97      2381125.00     13620175.00
      2381925.00     13620425.00
#Sta/Elev= 30
  4468.8  318.04  4504.4  316.80  4518.7  313.83  4539.5  312.88  4553.8  315.96
  4568.0  316.21  4625.0  312.72  4709.4  311.48  4823.3  307.22  4882.7  306.84
  4972.3  306.06  4986.6  304.77  4991.2  301.83  4991.4  301.33  4995.3  301.83
  4997.0  303.46  5003.0  303.46  5016.6  307.23  5054.3  305.72  5086.8  307.56
  5136.5  306.57  5180.0  308.14  5377.5  310.35  5398.5  309.60  5409.6  310.65
  5487.0  313.35  5524.7  316.43  5699.8  324.50  5793.5  328.83  5838.5  331.44
#Mann=8,-1,0
  4468.8    0.07       0  4882.7     0.1       0  4991.2    0.05       0
  4995.3     0.1       0  5180.0    0.12       0  5409.6    0.07       0
  5699.8    0.12       0  5793.5    0.07       0
Bank Sta=4991.2,4995.3
Exp/Cntr=0.3,0.1

Type RM Length L Ch R = 1,6297,453,453,453
BEGIN DESCRIPTION:
Stream0639 13.0
END DESCRIPTION:
XS GIS Cut Line= 3
      2380575.00     13620125.00      2380975.00     13620525.00
      2381775.01     13620525.00
#Sta/Elev= 30
  4438.8  316.82  4594.4  312.59  4636.8  312.44  4735.8  309.84  4815.6  305.36
  4877.2  304.41  4919.6  304.91  4947.9  303.76  4962.1  305.01  4976.2  300.19
  5001.0  304.74  5034.5  305.39  5044.5  303.87  5052.4  300.08  5052.7  299.58
  5056.6  300.08  5064.5  302.68  5074.5  300.29  5084.5  304.42  5094.5  304.85
  5104.5  306.39  5114.5  305.92  5134.5  307.40  5236.8  307.95  5385.1  309.79
  5434.5  309.97  5524.5  312.39  5604.5  316.26  5654.5  317.59  5804.5  323.88
#Mann=6,-1,0
  4438.8    0.07       0  4815.6     0.1       0  5052.4    0.05       0
  5056.6     0.1       0  5236.8    0.12       0  5385.1    0.07       0
Bank Sta=5052.4,5056.6
Exp/Cntr=0.3,0.1

Type RM Length L Ch R = 1,5844,414,414,414
BEGIN DESCRIPTION:
Stream0639 12.0
END DESCRIPTION:
XS GIS Cut Line= 3
      2380525.04     13620575.03      2380825.00     13620775.00
      2381574.99     13620975.00
#Sta/Elev= 30
  4650.9  311.20  4795.1  306.51  4831.1  303.63  4859.7  303.40  4867.2  301.32
  4874.7  301.99  4880.7  298.94  4889.7  298.37  4895.7  298.96  4903.2  303.86
  4913.6  304.01  4931.8  303.43  4939.3  298.90  4961.8  303.73  5003.9  302.84
  5006.3  296.11  5006.6  295.61  5010.6  296.11  5014.0  296.11  5021.8  302.28
  5028.9  303.26  5042.5  302.54  5094.2  305.80  5264.3  305.64  5299.3  306.43
  5321.9  305.60  5365.7  306.55  5454.5  308.05  5614.9  314.91  5787.6  320.12
#Mann=5,-1,0
  4650.9    0.07       0  4913.6     0.1       0  5006.3    0.05       0
  5010.6     0.1       0  5365.7    0.07       0
Bank Sta=5006.3,5010.6
Exp/Cntr=0.3,0.1

Type RM Length L Ch R = 1,5430,416,416,416
BEGIN DESCRIPTION:
Stream0639 11.0
END DESCRIPTION:
XS GIS Cut Line= 3
      2380325.03     13621025.01      2380725.00     13621125.00
      2381524.96     13621075.00
#Sta/Elev= 30
  4583.3  310.63  4683.8  307.15  4766.2  305.50  4931.2  304.35  4954.4  303.39
  4964.7  300.11  4972.4  295.20  4975.4  294.68  4975.7  294.18  4979.7  294.68
  4985.3  295.04  4993.0  297.81  4997.2  297.81  5005.6  302.09  5015.6  302.28
  5095.8  301.71  5115.8  300.70  5135.9  301.84  5196.0  302.49  5216.0  300.60
  5256.1  300.32  5326.2  303.99  5371.7  304.78  5426.4  305.75  5506.6  309.04
  5536.6  309.32  5559.2  310.75  5566.7  310.35  5596.8  312.78  5797.1  319.38
#Mann=5,-1,0
  4583.3    0.07       0  4975.4    0.05       0  4979.7    0.07       0
  4997.2     0.1       0  5371.7    0.07       0
Bank Sta=4975.4,4979.7
Exp/Cntr=0.3,0.1

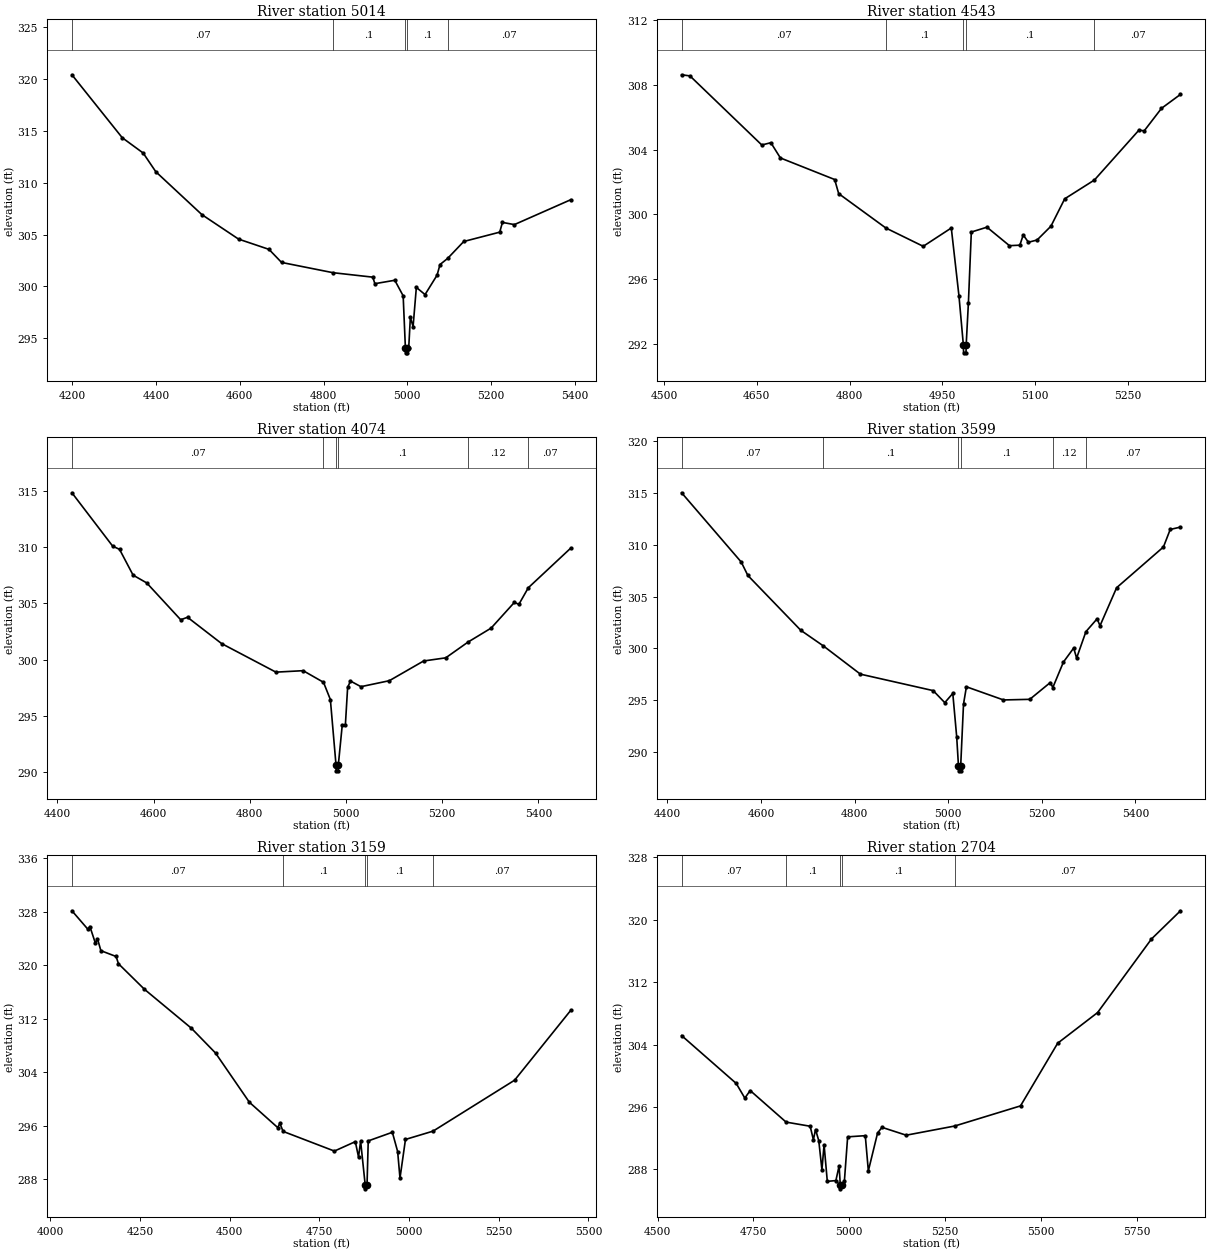
Type RM Length L Ch R = 1,5014,471,471,471
BEGIN DESCRIPTION:
Stream0639 10.0
END DESCRIPTION:
XS GIS Cut Line= 3
      2380025.03     13621375.00      2380825.00     13621425.00
      2381124.97     13621674.97
#Sta/Elev= 30
  4198.8  320.42  4319.0  314.35  4369.1  312.87  4399.2  311.07  4509.4  306.93
  4597.0  304.57  4669.7  303.58  4699.7  302.32  4822.7  301.33  4917.7  300.90
  4922.7  300.27  4970.3  300.60  4990.3  299.10  4995.6  294.10  4995.9  293.60
  4999.8  293.60  5000.1  294.10  5003.6  294.10  5007.5  297.02  5014.0  296.13
  5021.8  299.91  5042.6  299.22  5071.3  301.09  5078.4  302.12  5096.4  302.70
  5135.1  304.34  5221.0  305.24  5227.5  306.18  5256.1  305.97  5390.8  308.37
#Mann=5,-1,0
  4198.8    0.07       0  4822.7     0.1       0  4995.6    0.05       0
  5000.1     0.1       0  5096.4    0.07       0
Bank Sta=4995.6,5000.1
Exp/Cntr=0.3,0.1

Type RM Length L Ch R = 1,4543,469,469,469
BEGIN DESCRIPTION:
Stream0639 9.0
END DESCRIPTION:
XS GIS Cut Line= 3
      2380225.01     13621575.01      2380625.00     13621825.00
      2380925.00     13621975.00
#Sta/Elev= 30
  4528.3  308.61  4541.8  308.54  4658.0  304.28  4672.7  304.42  4688.1  303.48
  4775.9  302.15  4782.4  301.28  4858.7  299.16  4919.2  298.03  4964.6  299.16
  4977.0  294.98  4984.1  291.96  4984.5  291.46  4988.4  291.46  4988.7  291.96
  4992.3  294.55  4997.0  298.91  5022.3  299.21  5058.7  298.07  5075.5  298.10
  5081.0  298.73  5089.4  298.28  5103.4  298.42  5125.8  299.27  5148.1  300.96
  5196.2  302.12  5268.3  305.20  5276.7  305.15  5304.7  306.54  5335.4  307.40
#Mann=5,-1,0
  4528.3    0.07       0  4858.7     0.1       0  4984.1    0.05       0
  4988.7     0.1       0  5196.2    0.07       0
Bank Sta=4984.1,4988.7
Exp/Cntr=0.3,0.1

Type RM Length L Ch R = 1,4074,475,475,475
BEGIN DESCRIPTION:
Stream0639 8.0
END DESCRIPTION:
XS GIS Cut Line= 3
      2379975.03     13621775.03      2380375.00     13622175.00
      2380624.97     13622574.96
#Sta/Elev= 30
  4430.1  314.80  4514.9  310.06  4529.1  309.78  4557.3  307.49  4585.6  306.80
  4656.3  303.53  4670.5  303.75  4741.2  301.42  4854.3  298.88  4910.9  299.01
  4953.2  297.98  4967.5  296.45  4979.3  290.62  4979.6  290.12  4983.6  290.12
  4984.0  290.62  4992.2  294.18  4998.7  294.18  5003.4  297.52  5009.3  298.09
  5031.1  297.59  5090.1  298.12  5161.4  299.87  5207.4  300.15  5253.8  301.55
  5301.8  302.79  5350.1  305.07  5359.5  304.90  5379.1  306.37  5467.4  309.89
#Mann=6,-1,0
  4430.1    0.07       0  4953.2     0.1       0  4979.3    0.05       0
  4984.0     0.1       0  5253.8    0.12       0  5379.1    0.07       0
Bank Sta=4979.3,4984
Exp/Cntr=0.3,0.1

Type RM Length L Ch R = 1,3599,440,440,440
BEGIN DESCRIPTION:
Stream0639 7.0
END DESCRIPTION:
XS GIS Cut Line= 3
      2379674.98     13622074.98      2380075.00     13622475.00
      2380474.98     13622774.99
#Sta/Elev= 30
  4430.5  315.01  4557.8  308.33  4572.0  307.03  4685.1  301.74  4733.4  300.23
  4812.4  297.51  4967.9  295.92  4992.7  294.76  5009.8  295.65  5018.1  291.48
  5021.9  288.68  5022.3  288.18  5026.4  288.18  5026.7  288.68  5032.7  294.62
  5038.9  296.29  5118.1  295.02  5174.3  295.08  5218.1  296.70  5223.5  296.22
  5246.2  298.68  5268.1  300.03  5274.3  299.06  5294.2  301.61  5318.1  302.85
  5324.3  302.18  5359.8  305.85  5459.8  309.78  5474.3  311.47  5496.2  311.70
#Mann=6,-1,0
  4430.5    0.07       0  4733.4     0.1       0  5021.9    0.05       0
  5026.7     0.1       0  5223.5    0.12       0  5294.2    0.07       0
Bank Sta=5021.9,5026.7
Exp/Cntr=0.3,0.1

Type RM Length L Ch R = 1,3159,455,455,455
BEGIN DESCRIPTION:
Stream0639 6.0
END DESCRIPTION:
XS GIS Cut Line= 3
      2379425.02     13622025.04      2379925.00     13622825.00
      2380325.03     13623025.02
#Sta/Elev= 30
  4060.2  328.11  4104.4  325.37  4110.3  325.76  4125.6  323.27  4131.5  323.93
  4140.9  322.15  4183.4  321.28  4189.9  320.20  4262.4  316.38  4393.3  310.56
  4460.5  306.86  4554.8  299.51  4633.9  295.72  4639.8  296.36  4648.9  295.15
  4791.9  292.21  4850.2  293.62  4859.1  291.33  4865.0  293.68  4877.9  287.07
  4878.2  286.57  4882.8  287.07  4886.2  293.73  4953.4  295.02  4968.2  292.14
  4974.7  288.17  4990.0  293.95  5066.9  295.19  5294.2  302.80  5450.8  313.24
#Mann=5,-1,0
  4060.2    0.07       0  4648.9     0.1       0  4877.9    0.05       0
  4882.8     0.1       0  5066.9    0.07       0
Bank Sta=4877.9,4882.8
Exp/Cntr=0.3,0.1

Type RM Length L Ch R = 1,2704,421,421,421
BEGIN DESCRIPTION:
Stream0639 5.0
END DESCRIPTION:
XS GIS Cut Line= 3
      2379275.02     13622575.01      2379675.00     13622775.00
      2379975.00     13623575.01
#Sta/Elev= 30
  4562.6  305.15  4705.1  299.01  4727.5  297.13  4741.5  298.10  4835.2  294.05
  4898.0  293.52  4906.4  291.79  4912.0  293.10  4920.4  291.68  4928.7  287.94
  4934.3  291.15  4942.7  286.45  4965.1  286.55  4973.5  288.44  4976.6  285.99
  4976.9  285.49  4981.5  285.99  4987.4  286.55  4995.8  292.16  5041.8  292.31
  5049.8  287.80  5073.9  292.65  5085.4  293.38  5148.6  292.37  5275.3  293.55
  5446.8  296.13  5543.8  304.17  5647.9  308.10  5788.5  317.54  5864.2  321.16
#Mann=5,-1,0
  4562.6    0.07       0  4835.2     0.1       0  4976.6    0.05       0
  4981.5     0.1       0  5275.3    0.07       0
Bank Sta=4976.6,4981.5
Exp/Cntr=0.3,0.1

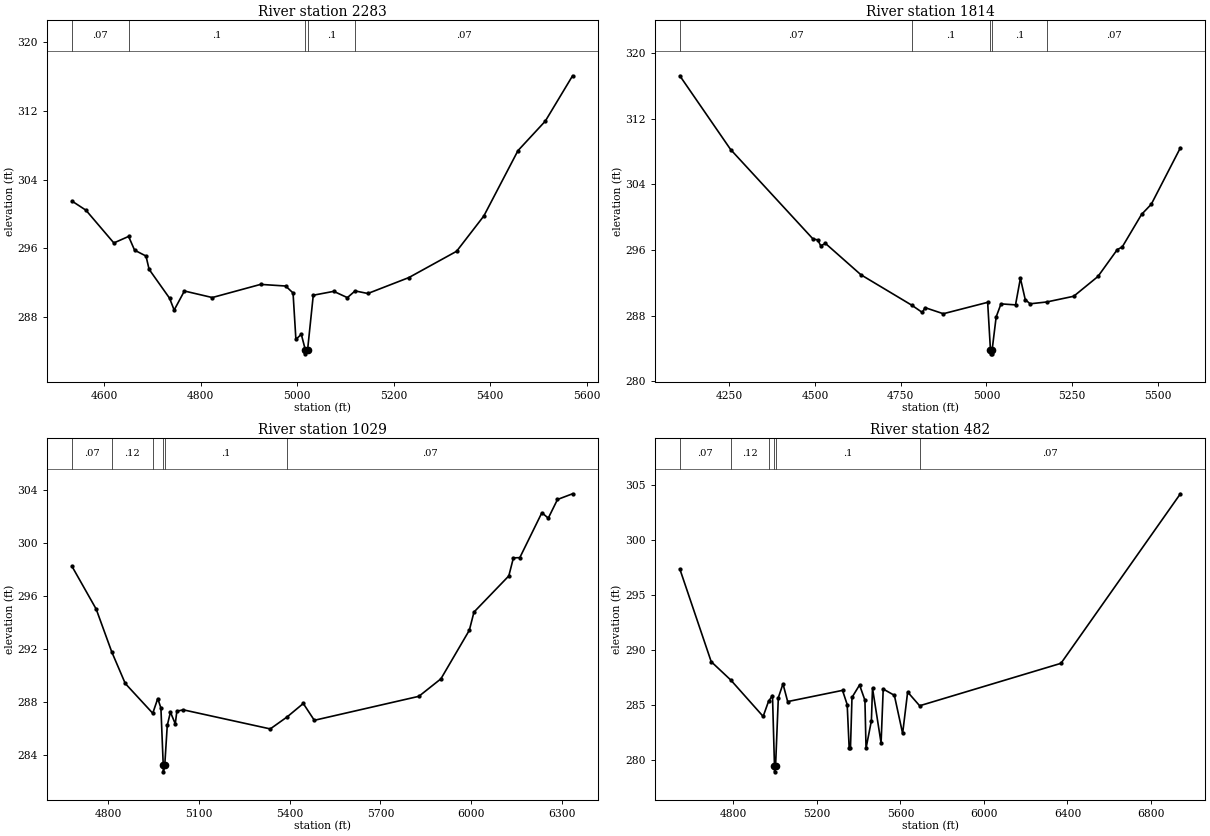
Type RM Length L Ch R = 1,2283,469,469,469
BEGIN DESCRIPTION:
Stream0639 4.0
END DESCRIPTION:
XS GIS Cut Line= 3
      2379225.00     13622725.00      2379475.00     13623125.00
      2379875.01     13623525.01
#Sta/Elev= 30
  4533.7  301.49  4562.6  300.43  4620.4  296.62  4651.0  297.38  4663.4  295.78
  4687.0  295.10  4693.5  293.55  4735.9  290.19  4745.4  288.81  4766.6  291.03
  4824.4  290.27  4924.6  291.80  4976.5  291.61  4991.8  290.80  4997.7  285.40
  5008.9  285.99  5017.1  284.22  5017.4  283.72  5022.0  284.22  5033.7  290.54
  5076.1  290.99  5104.4  290.26  5120.4  291.04  5146.8  290.74  5231.7  292.59
  5330.7  295.65  5387.2  299.76  5457.9  307.36  5514.5  310.79  5571.1  316.07
#Mann=5,-1,0
  4533.7    0.07       0  4651.0     0.1       0  5017.1    0.05       0
  5022.0     0.1       0  5120.4    0.07       0
Bank Sta=5017.1,5022
Exp/Cntr=0.3,0.1

Type RM Length L Ch R = 1,1814,785,785,785
BEGIN DESCRIPTION:
Stream0639 3.0
END DESCRIPTION:
XS GIS Cut Line= 3
      2378824.98     13622574.96      2379225.00     13623375.00
      2379625.03     13623775.03
#Sta/Elev= 30
  4105.5  317.23  4253.7  308.24  4494.1  297.33  4508.0  297.22  4516.4  296.51
  4530.4  296.79  4633.8  292.97  4782.1  289.26  4812.7  288.38  4821.1  288.96
  4874.2  288.22  5003.5  289.61  5011.6  283.83  5012.0  283.33  5016.2  283.33
  5016.6  283.83  5028.3  287.83  5042.4  289.42  5084.8  289.30  5099.0  292.54
  5113.1  289.95  5127.2  289.43  5175.4  289.65  5254.5  290.35  5325.2  292.76
  5381.8  296.05  5395.9  296.35  5452.5  300.33  5480.8  301.57  5565.7  308.45
#Mann=5,-1,0
  4105.5    0.07       0  4782.1     0.1       0  5011.6    0.05       0
  5016.6     0.1       0  5175.4    0.07       0
Bank Sta=5011.6,5016.6
Exp/Cntr=0.3,0.1

Type RM Length L Ch R = 1,1029,547,547,547
BEGIN DESCRIPTION:
Stream0639 2.0
END DESCRIPTION:
XS GIS Cut Line= 3
      2378425.01     13623025.03      2378538.10     13623375.63
      2379626.98     13624063.62
#Sta/Elev= 30
  4679.5  298.21  4759.6  294.98  4810.9  291.76  4855.7  289.37  4946.7  287.12
  4963.2  288.23  4973.7  287.52  4981.4  283.20  4981.8  282.70  4986.4  283.20
  4994.7  286.20  5005.2  287.21  5021.2  286.32  5026.5  287.28  5047.9  287.38
  5335.5  285.94  5391.0  286.84  5444.8  287.86  5481.3  286.59  5827.2  288.40
  5900.2  289.72  5994.3  293.39  6009.6  294.76  6124.9  297.49  6140.1  298.85
  6161.3  298.87  6234.3  302.26  6255.5  301.85  6286.0  303.26  6335.9  303.69
#Mann=6,-1,0
  4679.5    0.07       0  4810.9    0.12       0  4946.7     0.1       0
  4981.4    0.05       0  4986.4     0.1       0  5391.0    0.07       0
Bank Sta=4981.4,4986.4
Exp/Cntr=0.3,0.1

Type RM Length L Ch R = 1,482,0,0,0
BEGIN DESCRIPTION:
Stream0639 1.0
END DESCRIPTION:
XS GIS Cut Line= 4
      2378120.98     13622936.79      2378066.80     13623261.87
      2378283.49     13623695.24      2379777.60     13624220.35
#Sta/Elev= 30
  4543.1  297.40  4693.4  288.97  4787.7  287.29  4942.3  283.99  4968.0  285.36
  4987.0  285.89  4996.6  279.45  4997.0  278.95  5001.7  279.45  5015.0  285.70
  5037.3  286.95  5059.7  285.34  5322.4  286.36  5344.8  285.07  5354.3  281.11
  5360.6  281.11  5367.8  285.72  5404.1  286.85  5429.8  285.46  5435.1  281.09
  5460.8  283.60  5466.1  286.56  5507.2  281.57  5517.4  286.48  5570.8  285.91
  5610.4  282.44  5634.4  286.21  5691.9  284.96  6368.9  288.82  6940.9  304.24
#Mann=6,-1,0
  4543.1    0.07       0  4787.7    0.12       0  4968.0     0.1       0
  4996.6    0.05       0  5001.7     0.1       0  5691.9    0.07       0
Bank Sta=4996.6,5001.7
Exp/Cntr=0.3,0.1

Chan Stop Cuts=-1