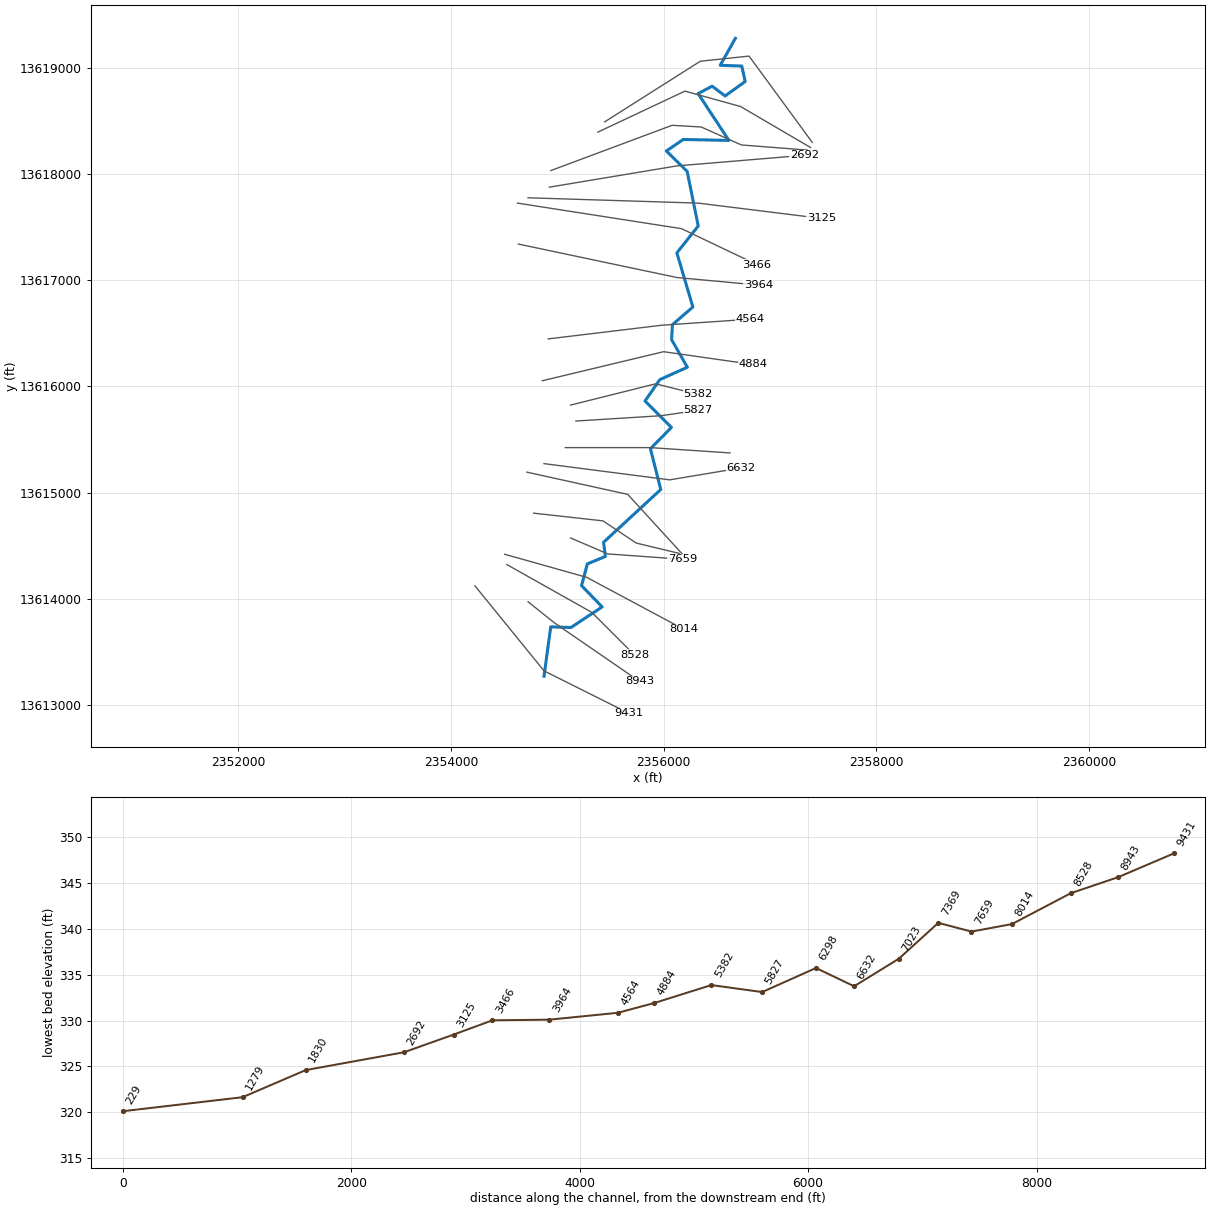
--- Stream0645.prj (project) ---

Proj Title=Stream0645 Base Level Engineering
Current Plan=p01
Default Exp/Contr=0.3,0.1
English Units
Geom File=g01
Flow File=f01
Plan File=p01
BEGIN DESCRIPTION:
Stream0645
END DESCRIPTION:

--- Stream0645.p01 (plan) ---

Plan Title=Multiple Run
Short Identifier=Multiple
Geom File=g01
Flow File=f01
Subcritical Flow
K Sum by GR= 0
Std Step Tol= 0.01
Critical Tol= 0.01
Num of Std Step Trials= 20
Max Error Tol= 0.3
Flow Tol Ratio= 0.001
Split Flow NTrial= 30
Split Flow Tol= 0.02
Split Flow Ratio= 0.02
Log Output Level= 0
Friction Slope Method= 1
Unsteady Friction Slope Method= 2
Unsteady Bridges Friction Slope Method= 1
Parabolic Critical Depth
Global Vel Dist=  1 , 1 , 1
Global Log Level= 0
CheckData=True
Encroach Param= -1, 0, 0, 0
BEGIN DESCRIPTION:
Multiple Run
END DESCRIPTION:

--- Stream0645.f01 (steady flow) ---

Flow Title=Multiple
Number of Profiles=7
Profile Names=10-year,25-year,50-year,1pct_min,100-year,1pct_plu,500-year
River Rch & RM= Stream0645,Reach-1,9431
     669    1087    1466     956    1908    3807    3207
River Rch & RM= Stream0645,Reach-1,4564
     987    1630    2220    1461    2915    5816    4987
Boundary for River Rch & Prof#=Stream0645,Reach-1,1
Up Type=0
Dn Type=3
Dn Slope=0.005
Boundary for River Rch & Prof#=Stream0645,Reach-1,2
Up Type=0
Dn Type=3
Dn Slope=0.005
Boundary for River Rch & Prof#=Stream0645,Reach-1,3
Up Type=0
Dn Type=3
Dn Slope=0.005
Boundary for River Rch & Prof#=Stream0645,Reach-1,4
Up Type=0
Dn Type=3
Dn Slope=0.005
Boundary for River Rch & Prof#=Stream0645,Reach-1,5
Up Type=0
Dn Type=3
Dn Slope=0.005
Boundary for River Rch & Prof#=Stream0645,Reach-1,6
Up Type=0
Dn Type=3
Dn Slope=0.005
Boundary for River Rch & Prof#=Stream0645,Reach-1,7
Up Type=0
Dn Type=3
Dn Slope=0.005

--- Stream0645.g01 (geometry) ---

Geom Title=Existing Conditions

River Reach=Stream0645,Reach-1
Reach XY= 30
      2354875.00     13613275.00      2354938.20     13613738.75
      2355128.41     13613732.81      2355422.01     13613926.46
      2355228.12     13614126.62      2355282.73     13614331.50
      2355452.74     13614401.16      2355435.20     13614534.68
      2355973.35     13615031.05      2355875.96     13615414.73
      2356073.91     13615615.36      2355825.35     13615863.87
      2355964.88     13616064.65      2356223.39     13616181.03
      2356075.37     13616440.17      2356082.80     13616581.21
      2356275.26     13616747.56      2356124.94     13617256.71
      2356325.77     13617509.91      2356221.48     13618023.72
      2356025.64     13618215.36      2356185.50     13618323.80
      2356614.20     13618314.62      2356324.73     13618755.05
      2356456.71     13618825.07      2356578.23     13618732.84
      2356767.25     13618868.82      2356735.44     13619014.06
      2356532.65     13619021.30      2356675.00     13619275.00

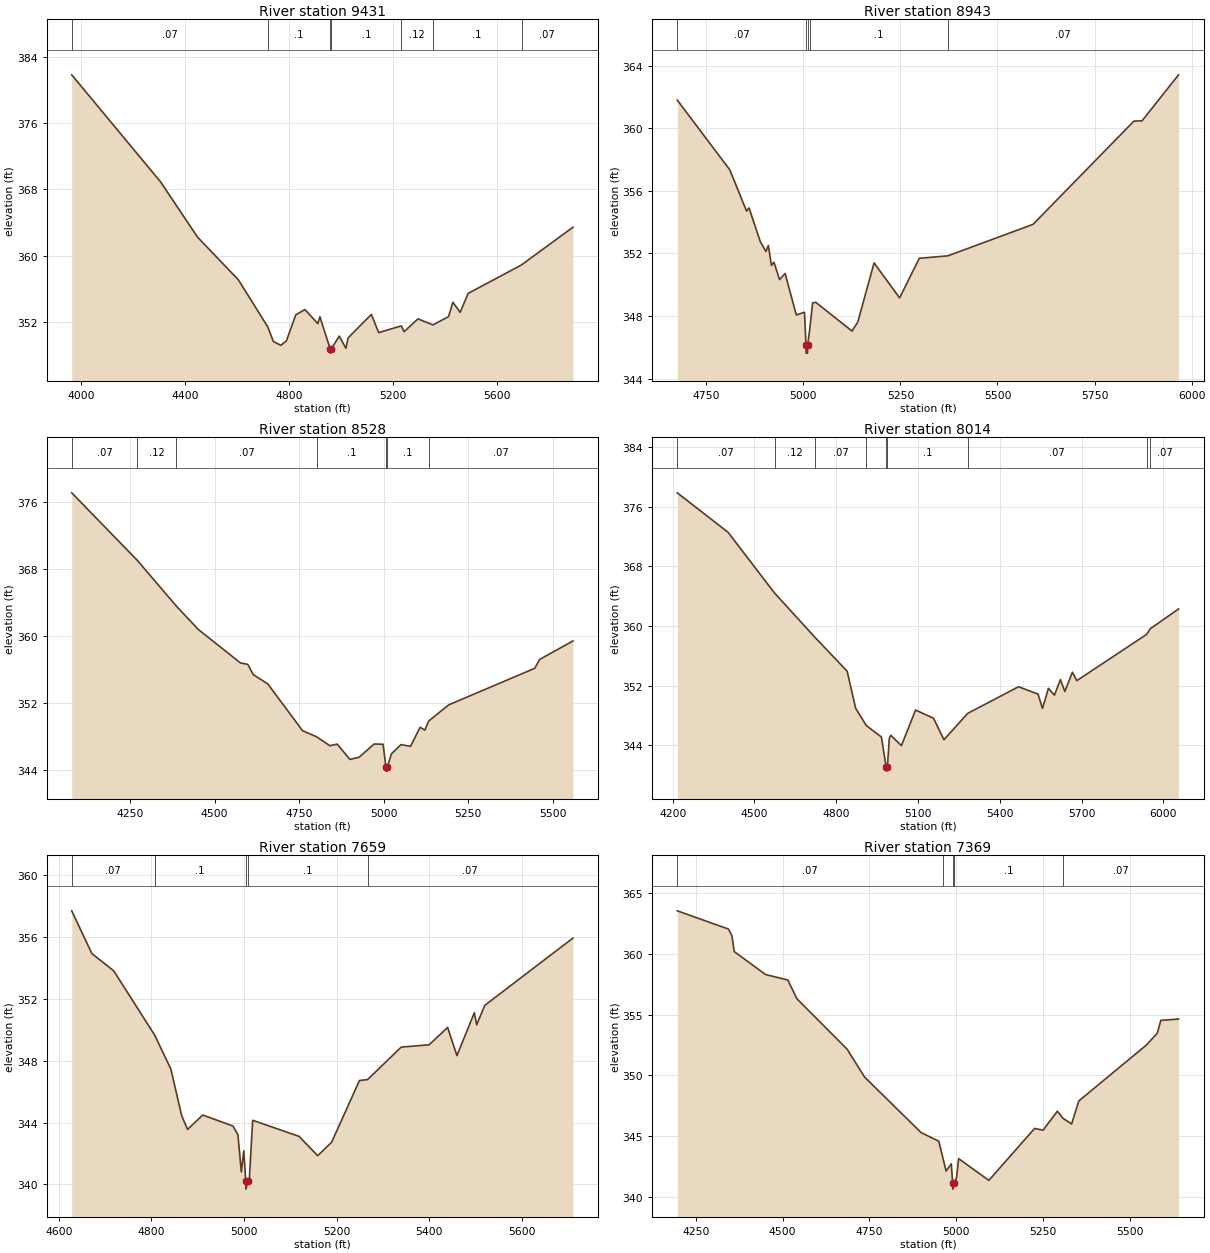
Type RM Length L Ch R = 1,9431,488,488,488
BEGIN DESCRIPTION:
Stream0645 16.0
END DESCRIPTION:
XS GIS Cut Line= 3
      2354225.03     13614124.96      2354875.00     13613325.00
      2355675.04     13612924.98
#Sta/Elev= 30
  3965.3  381.85  4306.4  368.92  4448.7  362.23  4605.3  357.08  4718.1  351.40
  4739.6  349.64  4768.3  349.16  4789.9  349.71  4825.8  352.85  4861.0  353.49
  4910.5  351.79  4918.5  352.62  4958.0  348.72  4958.3  348.22  4962.1  348.72
  4992.8  350.28  5018.4  348.80  5026.8  350.06  5116.2  352.90  5144.2  350.70
  5231.0  351.51  5242.0  350.81  5295.1  352.36  5352.6  351.63  5412.5  352.63
  5429.3  354.37  5457.2  353.15  5488.0  355.44  5692.8  358.88  5890.5  363.44
#Mann=7,-1,0
  3965.3    0.07       0  4718.1     0.1       0  4958.0    0.05       0
  4962.1     0.1       0  5231.0    0.12       0  5352.6     0.1       0
  5692.8    0.07       0
Bank Sta=4958,4962.1
Exp/Cntr=0.3,0.1

Type RM Length L Ch R = 1,8943,415,415,415
BEGIN DESCRIPTION:
Stream0645 15.0
END DESCRIPTION:
XS GIS Cut Line= 3
      2354725.04     13613974.97      2354975.00     13613775.00
      2355774.97     13613225.02
#Sta/Elev= 30
  4675.4  361.80  4810.6  357.35  4853.8  354.71  4860.2  354.91  4889.1  352.76
  4903.5  352.13  4909.9  352.51  4917.9  351.24  4924.3  351.44  4938.7  350.33
  4953.1  350.72  4981.9  348.07  5003.0  348.24  5006.9  346.13  5007.2  345.63
  5010.8  345.63  5011.1  346.13  5017.2  347.30  5023.9  348.84  5031.9  348.88
  5125.4  347.04  5140.3  347.62  5182.2  351.40  5247.9  349.16  5298.6  351.69
  5372.2  351.85  5591.5  353.86  5851.3  360.46  5872.3  360.48  5966.3  363.42
#Mann=5,-1,0
  4675.4    0.07       0  5006.9    0.05       0  5011.1    0.07       0
  5017.2     0.1       0  5372.2    0.07       0
Bank Sta=5006.9,5011.1
Exp/Cntr=0.3,0.1

Type RM Length L Ch R = 1,8528,514,514,514
BEGIN DESCRIPTION:
Stream0645 14.0
END DESCRIPTION:
XS GIS Cut Line= 3
      2354524.96     13614325.02      2355325.00     13613875.00
      2355725.00     13613475.00
#Sta/Elev= 30
  4077.0  377.14  4270.4  369.10  4386.6  363.61  4452.2  360.79  4576.5  356.81
  4598.1  356.64  4614.1  355.42  4657.4  354.30  4760.0  348.72  4801.9  347.98
  4841.0  346.92  4862.7  347.11  4900.3  345.28  4927.7  345.54  4972.0  347.12
  4998.5  347.09  5007.0  344.38  5007.3  343.88  5010.9  343.88  5011.2  344.38
  5023.2  345.94  5051.5  347.05  5079.8  346.84  5108.1  349.12  5122.2  348.78
  5133.6  349.87  5192.9  351.80  5447.5  356.17  5461.6  357.22  5560.6  359.44
#Mann=7,-1,0
  4077.0    0.07       0  4270.4    0.12       0  4386.6    0.07       0
  4801.9     0.1       0  5007.0    0.05       0  5011.2     0.1       0
  5133.6    0.07       0
Bank Sta=5007,5011.2
Exp/Cntr=0.3,0.1

Type RM Length L Ch R = 1,8014,355,355,355
BEGIN DESCRIPTION:
Stream0645 13.0
END DESCRIPTION:
XS GIS Cut Line= 3
      2354505.16     13614421.69      2355276.72     13614204.69
      2356191.50     13613715.20
#Sta/Elev= 30
  4216.8  377.88  4403.1  372.58  4573.6  364.43  4723.2  358.43  4839.9  353.94
  4871.1  348.97  4910.6  346.62  4965.7  345.10  4983.2  341.02  4983.5  340.52
  4987.5  341.02  4994.6  344.91  4999.8  345.34  5039.0  343.94  5090.9  348.72
  5156.8  347.62  5195.0  344.73  5282.1  348.27  5468.8  351.85  5540.3  350.86
  5556.6  348.94  5578.5  351.63  5600.5  350.72  5622.4  352.81  5638.7  351.21
  5666.3  353.80  5682.6  352.67  5938.8  358.88  5951.9  359.63  6055.8  362.29
#Mann=9,-1,0
  4216.8    0.07       0  4573.6    0.12       0  4723.2    0.07       0
  4910.6     0.1       0  4983.2    0.05       0  4987.5     0.1       0
  5282.1    0.07       0  5938.8   0.035       0  5951.9    0.07       0
Bank Sta=4983.2,4987.5
Exp/Cntr=0.3,0.1

Type RM Length L Ch R = 1,7659,290,290,290
BEGIN DESCRIPTION:
Stream0645 12.0
END DESCRIPTION:
XS GIS Cut Line= 3
      2355124.99     13614575.01      2355475.00     13614425.00
      2356175.01     13614375.00
#Sta/Elev= 30
  4627.9  357.69  4671.4  354.93  4718.6  353.81  4807.0  349.66  4841.9  347.47
  4865.5  344.44  4878.1  343.56  4910.8  344.49  4976.1  343.78  4986.9  343.21
  4994.2  340.81  4999.6  342.18  5003.8  340.20  5004.1  339.70  5008.1  340.20
  5011.2  340.20  5018.7  344.15  5119.0  343.11  5159.1  341.86  5189.2  342.73
  5249.3  346.72  5266.8  346.78  5339.5  348.88  5399.7  349.03  5439.8  350.15
  5459.9  348.33  5497.4  351.10  5502.5  350.32  5520.0  351.58  5710.5  355.93
#Mann=5,-1,0
  4627.9    0.07       0  4807.0     0.1       0  5003.8    0.05       0
  5008.1     0.1       0  5266.8    0.07       0
Bank Sta=5003.8,5008.1
Exp/Cntr=0.3,0.1

Type RM Length L Ch R = 1,7369,346,346,346
BEGIN DESCRIPTION:
XS7369
END DESCRIPTION:
XS GIS Cut Line= 4
      2354778.39     13614808.26      2355429.42     13614735.92
      2355742.85     13614526.96      2356144.70     13614430.52
#Sta/Elev= 30
  4196.3  363.54  4343.8  362.04  4353.9  361.48  4360.3  360.19  4450.8  358.30
  4514.9  357.85  4541.4  356.30  4685.9  352.16  4736.2  349.87  4899.1  345.30
  4950.2  344.59  4961.6  343.25  4971.2  342.14  4986.2  342.73  4990.1  341.15
  4990.4  340.65  4994.4  341.15  5001.2  341.57  5007.3  343.16  5094.4  341.37
  5226.3  345.64  5250.8  345.50  5292.0  347.06  5308.4  346.47  5333.1  346.01
  5353.7  347.90  5549.0  352.51  5579.9  353.47  5590.2  354.53  5641.3  354.64
#Mann=5,-1,0
  4196.3    0.07       0  4961.6     0.1       0  4990.1    0.05       0
  4994.4     0.1       0  5308.4    0.07       0
Bank Sta=4990.1,4994.4
Exp/Cntr=0.3,0.1

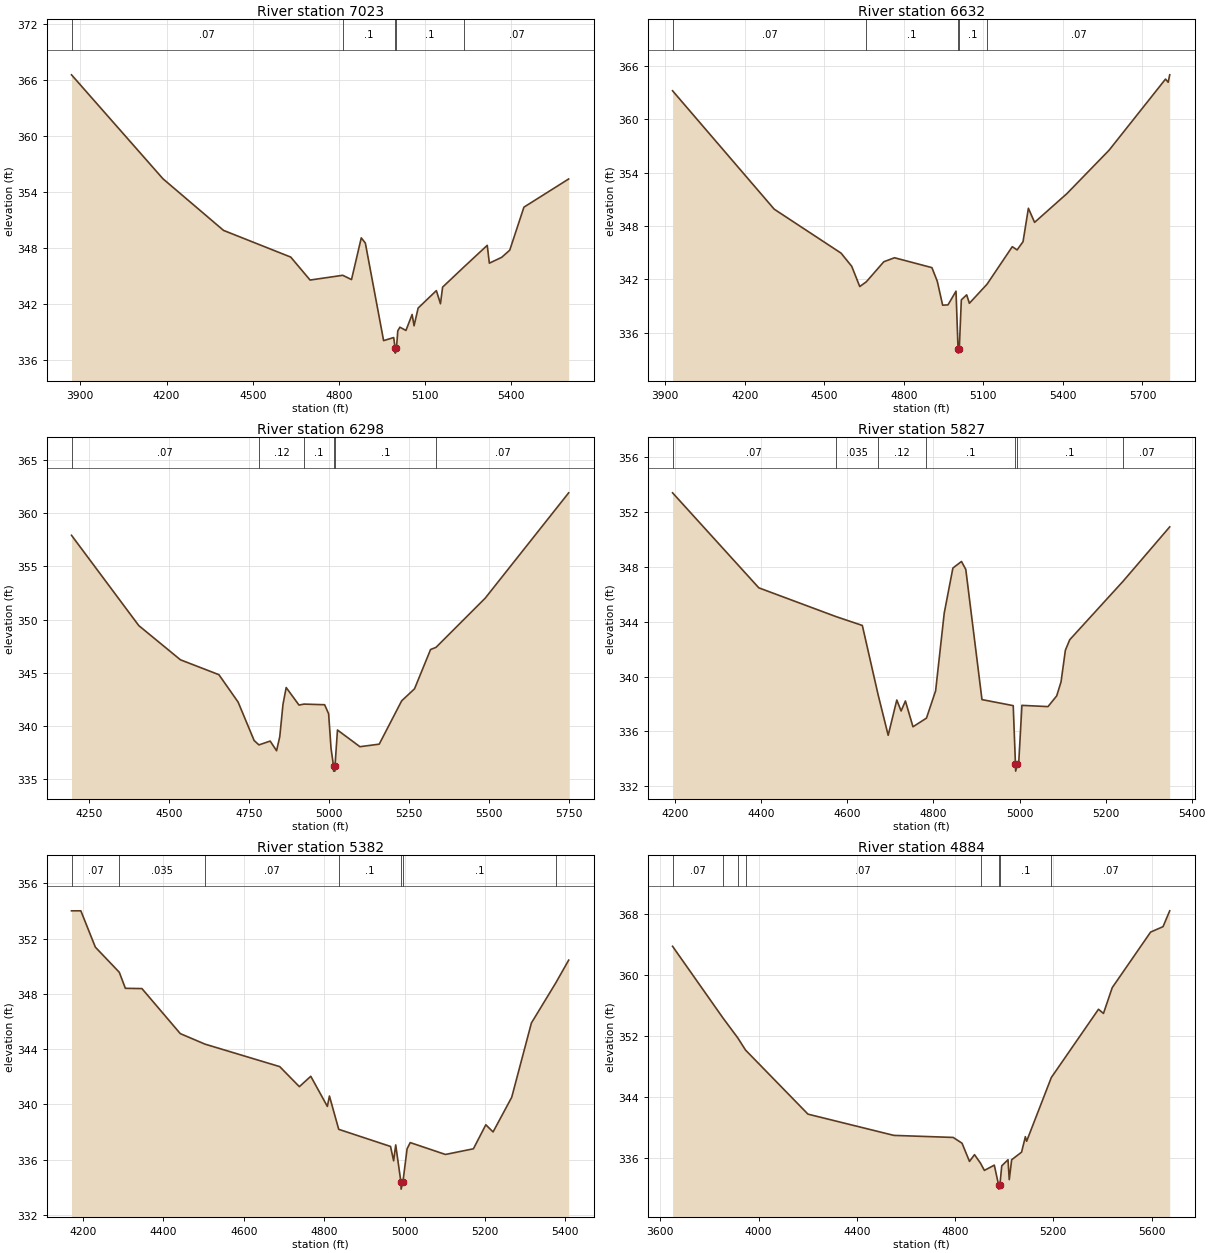
Type RM Length L Ch R = 1,7023,391,391,391
BEGIN DESCRIPTION:
Stream0645 11.0
END DESCRIPTION:
XS GIS Cut Line= 3
      2354714.13     13615194.02      2355662.48     13614985.06
      2356175.01     13614424.98
#Sta/Elev= 30
  3869.3  366.56  4187.6  355.42  4398.4  349.89  4632.3  347.03  4699.6  344.57
  4813.3  345.08  4843.8  344.62  4877.8  349.09  4892.0  348.53  4955.5  338.08
  4990.6  338.41  4995.8  337.24  4996.1  336.74  5000.2  337.24  5004.8  339.12
  5012.2  339.52  5033.2  339.17  5054.8  340.88  5061.5  339.67  5075.7  341.57
  5139.2  343.44  5153.4  342.03  5160.8  343.81  5235.4  345.98  5316.2  348.29
  5323.6  346.38  5366.2  347.00  5394.5  347.77  5443.9  352.38  5599.6  355.40
#Mann=5,-1,0
  3869.3    0.07       0  4813.3     0.1       0  4995.8    0.05       0
  5000.2     0.1       0  5235.4    0.07       0
Bank Sta=4995.8,5000.2
Exp/Cntr=0.3,0.1

Type RM Length L Ch R = 1,6632,334,334,334
BEGIN DESCRIPTION:
Stream0645 10.0
END DESCRIPTION:
XS GIS Cut Line= 3
      2354874.84     13615274.39      2356056.29     13615121.69
      2356730.71     13615234.09
#Sta/Elev= 30
  3927.7  363.17  4311.0  349.89  4563.1  344.96  4603.4  343.48  4633.7  341.21
  4658.4  341.74  4724.4  343.99  4764.8  344.44  4905.9  343.33  4926.1  341.80
  4946.3  339.12  4966.4  339.15  4996.7  340.69  5004.4  334.24  5004.8  333.74
  5009.1  334.24  5016.8  339.72  5037.0  340.28  5047.1  339.33  5113.7  341.47
  5208.9  345.68  5227.2  345.32  5249.5  346.24  5269.7  349.99  5293.1  348.41
  5414.8  351.63  5573.9  356.50  5786.8  364.48  5796.9  364.13  5802.7  364.96
#Mann=5,-1,0
  3927.7    0.07       0  4658.4     0.1       0  5004.4    0.05       0
  5009.1     0.1       0  5113.7    0.07       0
Bank Sta=5004.4,5009.1
Exp/Cntr=0.3,0.1

Type RM Length L Ch R = 1,6298,471,471,471
BEGIN DESCRIPTION:
Stream0645 9.0
END DESCRIPTION:
XS GIS Cut Line= 3
      2355075.00     13615425.00      2355875.00     13615425.00
      2356625.04     13615375.00
#Sta/Elev= 30
  4196.1  357.93  4406.1  349.43  4536.1  346.21  4656.1  344.81  4716.1  342.23
  4766.1  338.61  4781.1  338.20  4816.1  338.56  4836.1  337.65  4846.1  338.98
  4856.1  342.01  4866.1  343.60  4906.1  341.95  4921.9  342.04  4986.1  341.98
  4998.6  341.13  5006.1  337.87  5013.8  336.23  5014.1  335.73  5018.1  335.73
  5018.5  336.23  5026.2  339.60  5096.3  338.03  5156.5  338.27  5226.6  342.35
  5266.7  343.48  5316.8  347.18  5333.6  347.38  5487.2  352.01  5747.8  361.93
#Mann=6,-1,0
  4196.1    0.07       0  4781.1    0.12       0  4921.9     0.1       0
  5013.8    0.05       0  5018.5     0.1       0  5333.6    0.07       0
Bank Sta=5013.8,5018.5
Exp/Cntr=0.3,0.1

Type RM Length L Ch R = 1,5827,445,445,445
BEGIN DESCRIPTION:
Stream0645 8.0
END DESCRIPTION:
XS GIS Cut Line= 3
      2355175.00     13615675.00      2355975.00     13615725.00
      2356324.99     13615775.00
#Sta/Elev= 30
  4193.9  353.38  4394.3  346.46  4573.2  344.37  4634.8  343.72  4671.6  338.66
  4694.9  335.72  4714.9  338.29  4724.9  337.49  4734.9  338.22  4752.5  336.34
  4783.8  336.97  4805.1  338.96  4825.1  344.62  4845.2  347.90  4865.2  348.38
  4875.2  347.80  4912.8  338.32  4985.4  337.88  4990.6  333.61  4991.0  333.11
  4995.3  333.61  4998.0  333.61  5005.6  337.90  5066.2  337.81  5086.4  338.59
  5096.5  339.61  5106.6  341.92  5116.7  342.68  5240.4  346.93  5349.0  350.90
#Mann=7,-1,0
  4193.9    0.07       0  4573.2   0.035       0  4671.6    0.12       0
  4783.8     0.1       0  4990.6    0.05       0  4995.3     0.1       0
  5240.4    0.07       0
Bank Sta=4990.6,4995.3
Exp/Cntr=0.3,0.1

Type RM Length L Ch R = 1,5382,498,498,498
BEGIN DESCRIPTION:
Stream0645 7.0
END DESCRIPTION:
XS GIS Cut Line= 3
      2355125.00     13615825.00      2355925.00     13616025.00
      2356324.97     13615925.01
#Sta/Elev= 30
  4171.2  354.02  4194.4  354.02  4230.5  351.39  4290.1  349.57  4305.2  348.41
  4346.4  348.39  4441.8  345.13  4503.1  344.37  4689.2  342.74  4738.1  341.29
  4766.5  342.04  4807.7  339.86  4812.9  340.61  4836.0  338.20  4964.9  336.96
  4972.6  335.92  4977.8  337.07  4990.8  334.37  4991.2  333.87  4995.6  334.37
  5006.1  336.79  5013.9  337.24  5101.5  336.38  5171.1  336.79  5202.0  338.53
  5220.0  338.01  5266.4  340.52  5315.4  345.90  5376.0  348.80  5408.1  350.45
#Mann=7,-1,0
  4171.2    0.07       0  4290.1   0.035       0  4503.1    0.07       0
  4836.0     0.1       0  4990.8    0.05       0  4995.6     0.1       0
  5376.0    0.07       0
Bank Sta=4990.8,4995.6
Exp/Cntr=0.3,0.1

Type RM Length L Ch R = 1,4884,320,320,320
BEGIN DESCRIPTION:
XS7370
END DESCRIPTION:
XS GIS Cut Line= 3
      2354858.85     13616053.98      2356000.03     13616327.22
      2356841.94     13616206.94
#Sta/Elev= 30
  3649.9  363.82  3855.2  354.40  3915.8  351.77  3946.9  350.19  4201.2  341.77
  4550.8  338.98  4792.4  338.71  4828.4  337.95  4858.7  335.56  4879.1  336.45
  4903.7  335.32  4919.3  334.38  4959.7  335.07  4977.5  332.42  4977.8  331.92
  4982.3  332.42  4990.0  334.98  5015.5  335.78  5020.6  333.17  5030.4  335.78
  5070.8  336.78  5086.2  338.81  5091.3  338.21  5191.8  346.58  5383.9  355.55
  5404.1  355.00  5439.8  358.39  5596.1  365.69  5646.6  366.40  5673.8  368.48
#Mann=8,-1,0
  3649.9    0.07       0  3855.2   0.035       0  3915.8    0.12       0
  3946.9    0.07       0  4903.7     0.1       0  4977.5    0.05       0
  4982.3     0.1       0  5191.8    0.07       0
Bank Sta=4977.5,4982.3
Exp/Cntr=0.3,0.1

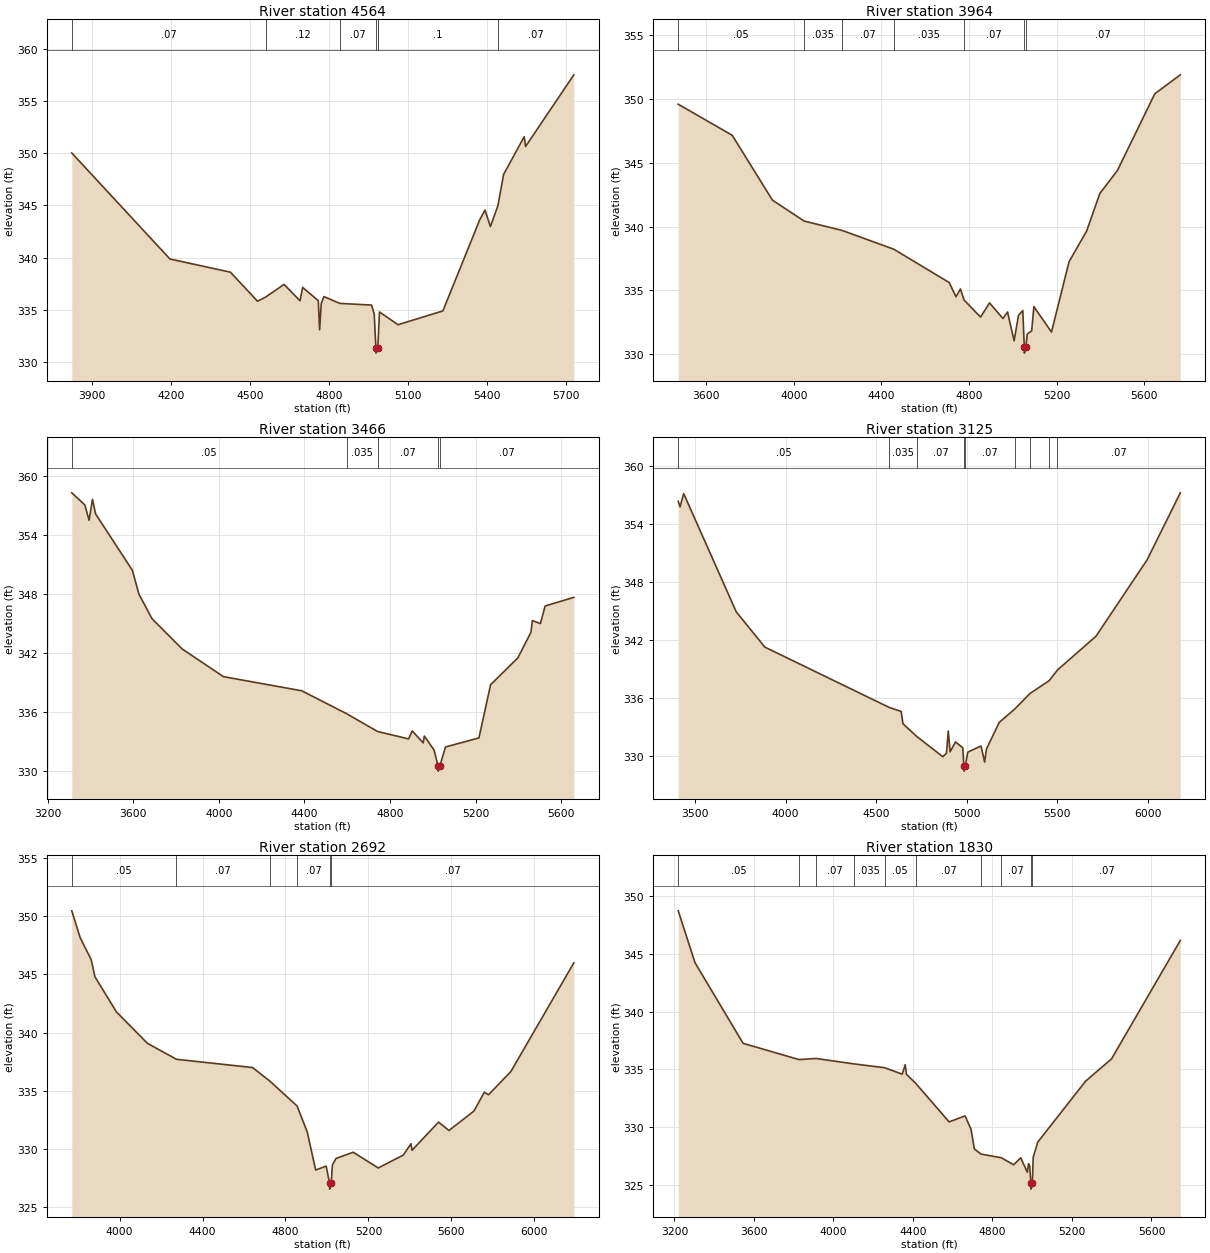
Type RM Length L Ch R = 1,4564,600,600,600
BEGIN DESCRIPTION:
Stream0645 6.0
END DESCRIPTION:
XS GIS Cut Line= 3
      2354915.09     13616447.77      2355983.96     13616576.36
      2356810.87     13616632.56
#Sta/Elev= 30
  3822.9  350.01  4195.5  339.86  4424.9  338.60  4527.9  335.82  4559.6  336.23
  4628.6  337.43  4689.0  335.86  4699.1  337.14  4758.5  335.87  4763.5  333.08
  4769.6  335.58  4779.7  336.26  4840.3  335.61  4960.7  335.45  4970.7  334.59
  4977.1  331.35  4977.6  330.85  4984.3  331.35  4986.4  332.48  4990.7  334.79
  5060.9  333.57  5231.3  334.89  5371.6  343.64  5391.1  344.54  5411.7  342.97
  5440.0  344.95  5461.8  347.96  5540.0  351.57  5545.1  350.63  5728.3  357.49
#Mann=7,-1,0
  3822.9    0.07       0  4559.6    0.12       0  4840.3    0.07       0
  4977.1    0.05       0  4984.3    0.07       0  4986.4     0.1       0
  5440.0    0.07       0
Bank Sta=4977.1,4984.3
Exp/Cntr=0.3,0.1

Type RM Length L Ch R = 1,3964,498,498,498
BEGIN DESCRIPTION:
Stream0645 5.0
END DESCRIPTION:
XS GIS Cut Line= 3
      2354633.76     13617339.86      2356125.00     13617025.00
      2356891.02     13616954.19
#Sta/Elev= 30
  3471.7  349.57  3718.3  347.14  3901.9  342.07  4046.8  340.43  4220.1  339.70
  4456.1  338.23  4709.6  335.62  4740.3  334.51  4760.7  335.12  4777.1  334.26
  4852.7  332.92  4893.6  334.03  4954.9  332.81  4976.0  333.32  5005.9  331.06
  5025.9  333.05  5045.6  333.43  5052.4  330.60  5052.9  330.10  5059.7  330.60
  5066.1  331.60  5086.2  331.84  5096.2  333.74  5176.6  331.75  5256.9  337.25
  5337.3  339.65  5397.5  342.59  5477.9  344.39  5648.6  350.39  5765.1  351.87
#Mann=7,-1,0
  3471.7    0.05       0  4046.8   0.035       0  4220.1    0.07       0
  4456.1   0.035       0  4777.1    0.07       0  5052.4    0.05       0
  5059.7    0.07       0
Bank Sta=5052.4,5059.7
Exp/Cntr=0.3,0.1

Type RM Length L Ch R = 1,3466,341,341,341
BEGIN DESCRIPTION:
Stream0645 4.0
END DESCRIPTION:
XS GIS Cut Line= 3
      2354624.97     13617725.00      2356168.81     13617484.52
      2356876.03     13617146.98
#Sta/Elev= 30
  3312.9  358.27  3373.7  357.05  3393.9  355.49  3409.7  357.61  3424.3  356.13
  3596.3  350.40  3626.7  347.99  3687.4  345.51  3829.1  342.42  4021.4  339.62
  4387.9  338.18  4597.1  335.86  4742.1  334.05  4886.8  333.30  4904.0  334.11
  4954.9  332.90  4960.4  333.59  5005.8  332.17  5024.8  330.53  5025.3  330.03
  5032.1  330.53  5059.5  332.48  5215.5  333.40  5270.0  338.80  5397.0  341.51
  5458.4  344.11  5465.1  345.31  5502.7  345.00  5524.9  346.79  5659.0  347.66
#Mann=5,-1,0
  3312.9    0.05       0  4597.1   0.035       0  4742.1    0.07       0
  5024.8    0.05       0  5032.1    0.07       0
Bank Sta=5024.8,5032.1
Exp/Cntr=0.3,0.1

Type RM Length L Ch R = 1,3125,433,433,433
BEGIN DESCRIPTION:
Stream0645 3.0
END DESCRIPTION:
XS GIS Cut Line= 3
      2354725.05     13617775.00      2356325.00     13617725.00
      2357486.87     13617580.96
#Sta/Elev= 30
  3406.9  356.38  3416.9  355.80  3436.9  357.17  3727.0  344.95  3884.6  341.30
  4570.1  335.07  4637.5  334.64  4647.5  333.37  4723.4  332.06  4867.6  329.96
  4887.6  330.33  4897.6  332.62  4907.6  330.47  4937.6  331.49  4977.6  330.88
  4983.9  328.97  4984.4  328.47  4991.3  328.97  5005.1  330.43  5078.2  331.07
  5098.3  329.41  5108.4  330.76  5178.9  333.51  5263.9  334.88  5349.2  336.51
  5454.3  337.82  5500.4  338.93  5713.0  342.42  5995.1  350.32  6178.4  357.25
#Mann=9,-1,0
  3406.9    0.05       0  4570.1   0.035       0  4723.4    0.07       0
  4983.9    0.05       0  4991.3    0.07       0  5263.9    0.05       0
  5349.2    0.07       0  5454.3    0.05       0  5500.4    0.07       0
Bank Sta=4983.9,4991.3
Exp/Cntr=0.3,0.1

Type RM Length L Ch R = 1,2692,862,862,862
BEGIN DESCRIPTION:
Stream0645 2.0
END DESCRIPTION:
XS GIS Cut Line= 3
      2354924.99     13617875.00      2356125.00     13618075.00
      2357324.97     13618175.00
#Sta/Elev= 30
  3769.7  350.47  3810.3  348.16  3863.5  346.27  3881.2  344.81  3985.1  341.78
  4134.7  339.08  4274.2  337.71  4641.6  337.00  4725.7  335.82  4856.3  333.69
  4905.2  331.45  4945.7  328.19  4996.3  328.53  5012.6  327.05  5013.1  326.55
  5020.1  327.05  5026.4  328.63  5044.0  329.19  5126.8  329.72  5247.2  328.37
  5367.6  329.47  5405.2  330.45  5410.2  329.89  5538.2  332.31  5588.3  331.59
  5708.8  333.26  5758.9  334.88  5779.0  334.66  5886.9  336.66  6190.4  346.00
#Mann=6,-1,0
  3769.7    0.05       0  4274.2    0.07       0  4725.7    0.05       0
  4856.3    0.07       0  5012.6    0.05       0  5020.1    0.07       0
Bank Sta=5012.6,5020.1
Exp/Cntr=0.3,0.1

Type RM Length L Ch R = 1,1830,551,551,551
BEGIN DESCRIPTION:
XS7368
END DESCRIPTION:
XS GIS Cut Line= 5
      2354939.19     13618031.04      2356080.40     13618456.98
      2356353.65     13618440.91      2356731.39     13618272.13
      2357350.15     13618223.92
#Sta/Elev= 30
  3218.9  348.73  3303.4  344.23  3545.3  337.24  3827.3  335.83  3911.2  335.93
  4101.8  335.46  4256.8  335.13  4345.9  334.57  4360.9  335.38  4367.2  334.56
  4413.4  333.78  4581.9  330.43  4662.0  330.95  4692.0  329.79  4708.9  328.08
  4742.4  327.64  4844.6  327.32  4906.5  326.71  4942.2  327.32  4975.1  326.07
  4981.6  326.80  4987.1  326.64  4993.2  325.10  4993.7  324.60  5000.8  325.10
  5004.8  327.36  5028.0  328.68  5268.5  333.96  5398.9  335.89  5745.1  346.16
#Mann=10,-1,0
  3218.9    0.05       0  3827.3   0.035       0  3911.2    0.07       0
  4101.8   0.035       0  4256.8    0.05       0  4413.4    0.07       0
  4742.4    0.12       0  4844.6    0.07       0  4993.2    0.05       0
  5000.8    0.07       0
Bank Sta=4993.2,5000.8
Exp/Cntr=0.3,0.1

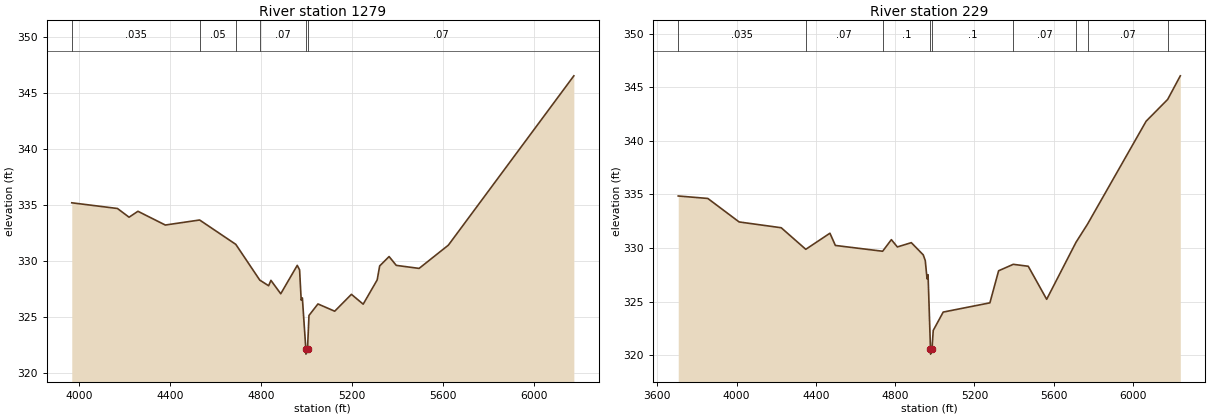
Type RM Length L Ch R = 1,1279,1050,1050,1050
BEGIN DESCRIPTION:
XS7367
END DESCRIPTION:
XS GIS Cut Line= 4
      2355381.24     13618392.71      2356200.95     13618778.46
      2356723.35     13618633.79      2357382.35     13618248.04
#Sta/Elev= 30
  3966.1  335.19  4167.4  334.68  4218.5  333.90  4257.6  334.43  4378.1  333.20
  4529.3  333.65  4688.7  331.47  4794.4  328.27  4833.3  327.77  4843.4  328.25
  4886.6  327.05  4959.3  329.59  4969.6  329.19  4976.7  326.48  4981.9  326.68
  4997.0  322.15  4997.5  321.65  5004.6  322.15  5011.0  325.11  5050.5  326.14
  5124.3  325.49  5197.9  327.00  5249.8  326.12  5311.4  328.29  5322.4  329.54
  5363.9  330.38  5395.5  329.59  5496.1  329.32  5625.0  331.40  6177.7  346.55
#Mann=6,-1,0
  3966.1   0.035       0  4529.3    0.05       0  4688.7   0.035       0
  4794.4    0.07       0  4997.0    0.05       0  5004.6    0.07       0
Bank Sta=4997,5004.6
Exp/Cntr=0.3,0.1

Type RM Length L Ch R = 1,229,0,0,0
BEGIN DESCRIPTION:
Stream0645 1.0
END DESCRIPTION:
XS GIS Cut Line= 4
      2355445.53     13618489.15      2356345.62     13619059.75
      2356803.72     13619107.97      2357398.43     13618296.26
#Sta/Elev= 30
  3706.0  334.86  3855.2  334.63  4013.2  332.44  4225.5  331.90  4349.4  329.89
  4471.2  331.39  4498.7  330.25  4737.0  329.71  4781.1  330.79  4811.3  330.11
  4881.7  330.51  4942.0  329.37  4952.1  328.84  4961.1  327.14  4966.2  327.52
  4978.4  320.62  4978.9  320.12  4986.1  320.62  4992.3  322.33  5042.6  324.04
  5278.1  324.90  5322.1  327.89  5396.1  328.49  5471.6  328.31  5564.5  325.23
  5712.3  330.54  5770.7  332.24  6066.2  341.83  6174.8  343.86  6238.6  346.06
#Mann=9,-1,0
  3706.0   0.035       0  4349.4    0.07       0  4737.0     0.1       0
  4978.4    0.05       0  4986.1     0.1       0  5396.1    0.07       0
  5712.3    0.05       0  5770.7    0.07       0  6174.8    0.05       0
Bank Sta=4978.4,4986.1
Exp/Cntr=0.3,0.1

Chan Stop Cuts=-1