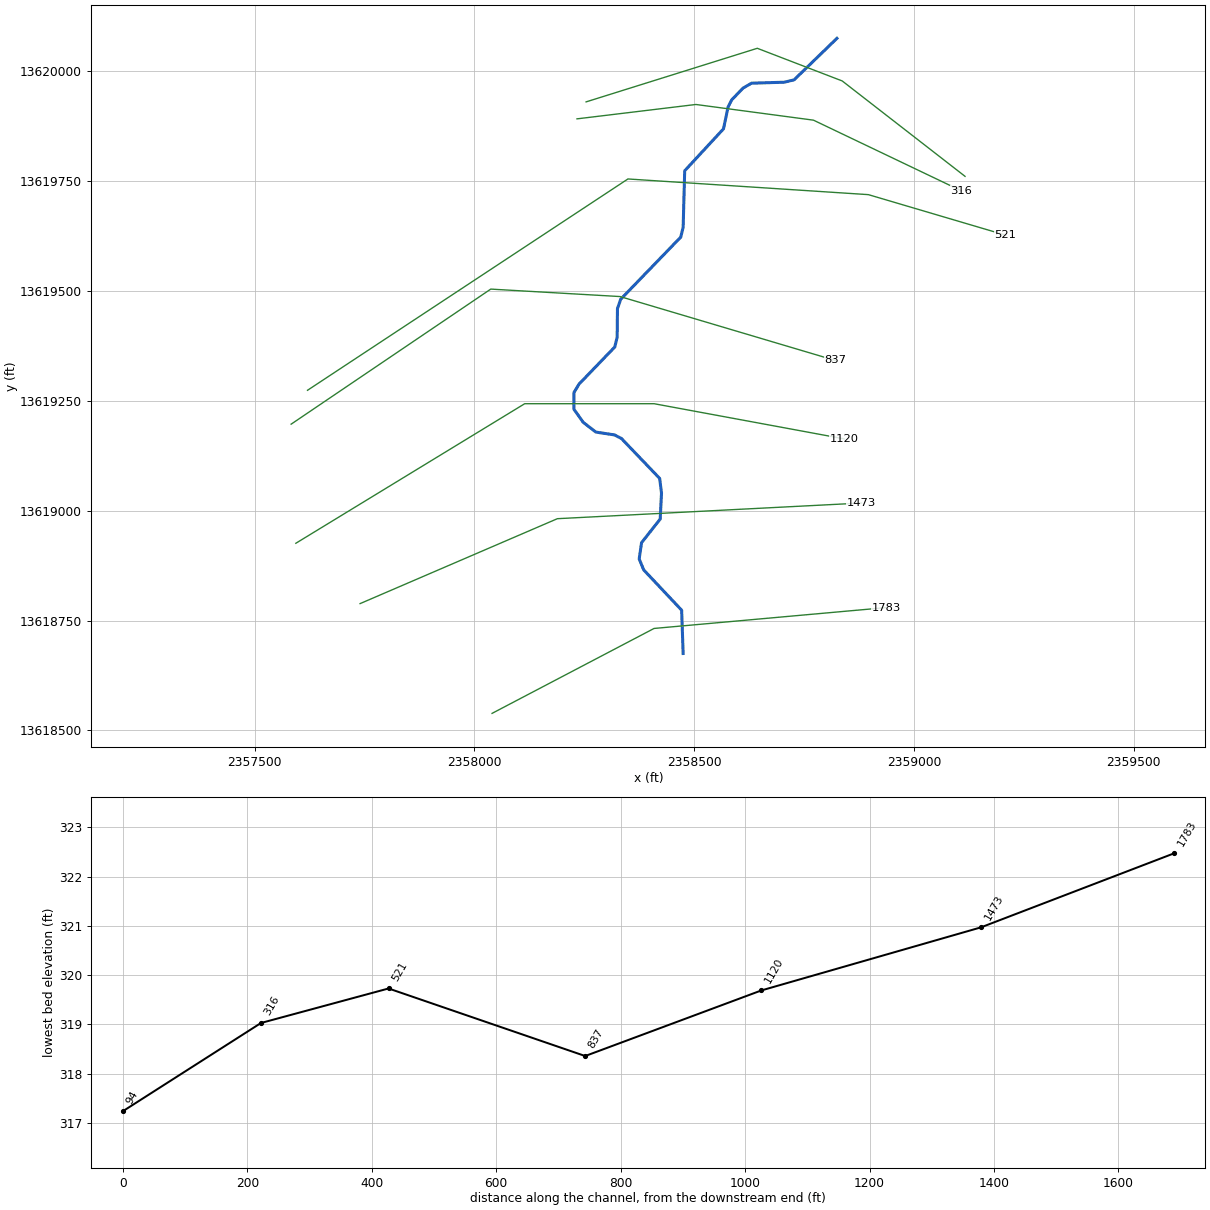
--- Stream0646.prj (project) ---

Proj Title=Stream0646 Base Level Engineering
Current Plan=p01
Default Exp/Contr=0.3,0.1
English Units
Geom File=g01
Flow File=f01
Plan File=p01
BEGIN DESCRIPTION:
Stream0646
END DESCRIPTION:

--- Stream0646.p01 (plan) ---

Plan Title=Multiple Run
Short Identifier=Multiple
Geom File=g01
Flow File=f01
Subcritical Flow
K Sum by GR= 0
Std Step Tol= 0.01
Critical Tol= 0.01
Num of Std Step Trials= 20
Max Error Tol= 0.3
Flow Tol Ratio= 0.001
Split Flow NTrial= 30
Split Flow Tol= 0.02
Split Flow Ratio= 0.02
Log Output Level= 0
Friction Slope Method= 1
Unsteady Friction Slope Method= 2
Unsteady Bridges Friction Slope Method= 1
Parabolic Critical Depth
Global Vel Dist=  1 , 1 , 1
Global Log Level= 0
CheckData=True
Encroach Param= -1, 0, 0, 0
BEGIN DESCRIPTION:
Multiple Run
END DESCRIPTION:

--- Stream0646.f01 (steady flow) ---

Flow Title=Multiple
Number of Profiles=7
Profile Names=10-year,25-year,50-year,1pct_min,100-year,1pct_plu,500-year
River Rch & RM= Stream0646,Reach-1,1783
     610     987    1326     864    1723    3438    2882
Boundary for River Rch & Prof#=Stream0646,Reach-1,1
Up Type=0
Dn Type=3
Dn Slope=0.005
Boundary for River Rch & Prof#=Stream0646,Reach-1,2
Up Type=0
Dn Type=3
Dn Slope=0.005
Boundary for River Rch & Prof#=Stream0646,Reach-1,3
Up Type=0
Dn Type=3
Dn Slope=0.005
Boundary for River Rch & Prof#=Stream0646,Reach-1,4
Up Type=0
Dn Type=3
Dn Slope=0.005
Boundary for River Rch & Prof#=Stream0646,Reach-1,5
Up Type=0
Dn Type=3
Dn Slope=0.005
Boundary for River Rch & Prof#=Stream0646,Reach-1,6
Up Type=0
Dn Type=3
Dn Slope=0.005
Boundary for River Rch & Prof#=Stream0646,Reach-1,7
Up Type=0
Dn Type=3
Dn Slope=0.005

--- Stream0646.g01 (geometry) ---

Geom Title=Existing Conditions

River Reach=Stream0646,Reach-1
Reach XY= 30
      2358475.00     13618675.00      2358471.60     13618773.59
      2358385.21     13618865.32      2358374.96     13618890.34
      2358380.36     13618927.17      2358422.81     13618980.97
      2358425.77     13619040.09      2358421.54     13619073.52
      2358334.68     13619164.22      2358318.92     13619172.45
      2358276.37     13619178.89      2358247.55     13619201.16
      2358226.50     13619230.87      2358226.57     13619268.91
      2358238.13     13619288.19      2358319.46     13619372.58
      2358324.86     13619395.06      2358325.53     13619459.78
      2358332.86     13619481.17      2358469.53     13619622.55
      2358475.02     13619644.99      2358478.55     13619773.53
      2358566.81     13619868.98      2358577.45     13619919.15
      2358585.63     13619935.05      2358611.35     13619961.74
      2358630.71     13619972.92      2358704.94     13619975.13
      2358727.45     13619980.46      2358825.00     13620075.00

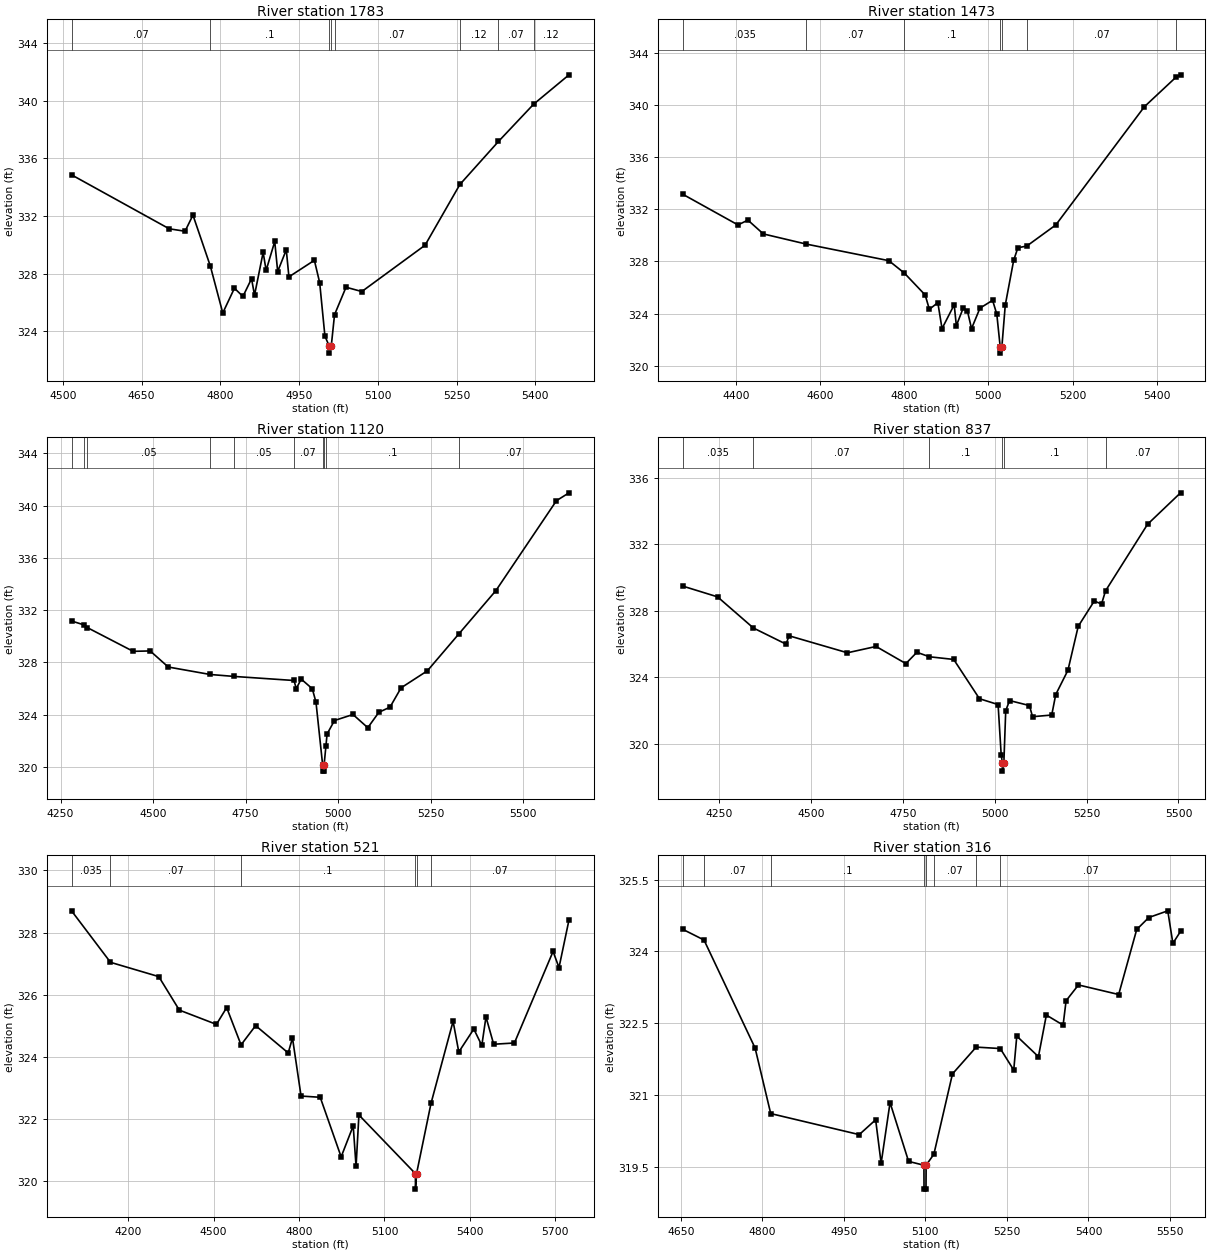
Type RM Length L Ch R = 1,1783,310,310,310
BEGIN DESCRIPTION:
XS7377
END DESCRIPTION:
XS GIS Cut Line= 3
      2358040.14     13618538.74      2358408.85     13618732.02
      2358938.12     13618779.59
#Sta/Elev= 30
  4516.5  334.86  4702.6  331.11  4732.7  330.94  4747.8  332.06  4781.0  328.51
  4804.6  325.26  4826.8  326.98  4843.0  326.41  4859.4  327.64  4865.1  326.50
  4881.5  329.47  4887.2  328.22  4903.6  330.23  4909.2  328.14  4925.6  329.65
  4930.6  327.77  4979.1  328.92  4989.2  327.37  4999.2  323.65  5007.3  322.97
  5007.5  322.47  5011.3  322.97  5017.5  325.14  5039.4  327.05  5069.5  326.75
  5190.0  329.97  5256.3  334.19  5329.8  337.18  5396.8  339.77  5464.2  341.81
#Mann=8,-1,0
  4516.5    0.07       0  4781.0     0.1       0  5007.3    0.05       0
  5011.3     0.1       0  5017.5    0.07       0  5256.3    0.12       0
  5329.8    0.07       0  5396.8    0.12       0
Bank Sta=5007.3,5011.3
Exp/Cntr=0.3,0.1

Type RM Length L Ch R = 1,1473,353,353,353
BEGIN DESCRIPTION:
XS7376
END DESCRIPTION:
XS GIS Cut Line= 3
      2357739.82     13618788.54      2358188.80     13618981.81
      2358880.87     13619017.45
#Sta/Elev= 30
  4274.7  333.14  4405.2  330.80  4428.7  331.17  4465.4  330.11  4567.5  329.33
  4763.5  328.06  4800.3  327.11  4849.8  325.43  4859.8  324.33  4879.9  324.84
  4889.9  322.85  4918.8  324.68  4923.9  323.08  4939.9  324.40  4950.0  324.23
  4960.0  322.85  4980.0  324.42  5010.0  325.02  5020.0  323.96  5028.0  321.47
  5028.3  320.97  5032.1  321.47  5040.1  324.65  5060.1  328.09  5070.1  329.05
  5091.2  329.18  5160.2  330.80  5370.5  339.86  5446.7  342.16  5456.5  342.31
#Mann=7,-1,0
  4274.7   0.035       0  4567.5    0.07       0  4800.3     0.1       0
  5028.0    0.05       0  5032.1     0.1       0  5091.2    0.07       0
  5446.7    0.12       0
Bank Sta=5028,5032.1
Exp/Cntr=0.3,0.1

Type RM Length L Ch R = 1,1120,283,283,283
BEGIN DESCRIPTION:
XS7375
END DESCRIPTION:
XS GIS Cut Line= 4
      2357593.60     13618925.88      2358114.46     13619243.49
      2358408.85     13619243.49      2358841.46     13619163.49
#Sta/Elev= 30
  4279.8  331.17  4314.8  330.86  4322.1  330.67  4446.3  328.85  4492.3  328.88
  4541.2  327.65  4654.4  327.08  4719.6  326.93  4880.9  326.62  4887.2  326.00
  4900.4  326.73  4930.4  325.99  4940.4  324.96  4958.3  320.19  4958.6  319.69
  4962.1  319.69  4962.4  320.19  4967.3  321.62  4970.4  322.53  4990.4  323.56
  5040.4  324.02  5080.4  323.01  5110.4  324.19  5140.4  324.58  5170.4  326.06
  5241.4  327.36  5326.1  330.17  5426.5  333.49  5590.3  340.37  5624.2  340.97
#Mann=10,-1,0
  4279.8    0.05       0  4314.8   0.035       0  4322.1    0.05       0
  4654.4    0.07       0  4719.6    0.05       0  4880.9    0.07       0
  4958.3    0.05       0  4962.4    0.07       0  4967.3     0.1       0
  5326.1    0.07       0
Bank Sta=4958.3,4962.4
Exp/Cntr=0.3,0.1

Type RM Length L Ch R = 1,837,316,316,316
BEGIN DESCRIPTION:
XS7374
END DESCRIPTION:
XS GIS Cut Line= 4
      2357582.93     13619196.95      2358037.20     13619504.31
      2358331.54     13619487.33      2358821.10     13619341.95
#Sta/Elev= 30
  4151.6  329.47  4245.5  328.83  4342.9  326.96  4431.8  325.99  4440.2  326.49
  4599.0  325.47  4676.9  325.85  4758.0  324.82  4788.0  325.50  4822.2  325.23
  4888.2  325.07  4958.3  322.71  5009.0  322.36  5017.4  319.35  5020.6  318.86
  5020.8  318.36  5024.7  318.86  5029.8  321.99  5040.2  322.60  5094.3  322.30
  5102.8  321.63  5155.0  321.73  5165.9  322.96  5199.1  324.42  5227.1  327.06
  5270.8  328.58  5290.6  328.40  5301.4  329.19  5415.8  333.19  5505.6  335.08
#Mann=6,-1,0
  4151.6   0.035       0  4342.9    0.07       0  4822.2     0.1       0
  5020.6    0.05       0  5024.7     0.1       0  5301.4    0.07       0
Bank Sta=5020.6,5024.7
Exp/Cntr=0.3,0.1

Type RM Length L Ch R = 1,521,205,205,205
BEGIN DESCRIPTION:
XS7373
END DESCRIPTION:
XS GIS Cut Line= 4
      2357620.15     13619274.03      2358349.38     13619754.96
      2358896.53     13619719.28      2359208.75     13619627.10
#Sta/Elev= 30
  4000.9  328.70  4137.7  327.04  4307.3  326.58  4379.5  325.50  4509.8  325.04
  4545.8  325.58  4596.3  324.38  4647.5  325.00  4761.9  324.12  4777.0  324.60
  4807.1  322.73  4874.4  322.69  4947.9  320.77  4990.3  321.77  5000.3  320.46
  5010.3  322.12  5208.7  320.23  5209.0  319.73  5212.8  320.23  5263.7  322.50
  5341.1  325.14  5361.1  324.15  5413.9  324.89  5442.0  324.36  5456.6  325.28
  5483.7  324.40  5556.5  324.44  5692.3  327.39  5713.1  326.87  5748.3  328.41
#Mann=6,-1,0
  4000.9   0.035       0  4137.7    0.07       0  4596.3     0.1       0
  5208.7    0.05       0  5212.8     0.1       0  5263.7    0.07       0
Bank Sta=5208.7,5212.8
Exp/Cntr=0.3,0.1

Type RM Length L Ch R = 1,316,222,222,222
BEGIN DESCRIPTION:
XS7372
END DESCRIPTION:
XS GIS Cut Line= 4
      2358233.44     13619891.76      2358504.01     13619924.46
      2358771.64     13619888.78      2359107.70     13619728.18
#Sta/Elev= 30
  4654.3  324.46  4692.8  324.24  4786.8  321.98  4815.5  320.61  4978.3  320.17
  5008.5  320.48  5018.6  319.57  5035.0  320.84  5069.1  319.61  5097.3  319.53
  5097.5  319.03  5101.1  319.03  5101.4  319.53  5115.6  319.76  5149.8  321.44
  5193.4  322.00  5237.7  321.97  5262.5  321.52  5268.1  322.23  5307.9  321.80
  5322.5  322.67  5353.3  322.46  5358.8  322.97  5381.5  323.30  5455.5  323.10
  5488.7  324.46  5510.9  324.71  5545.8  324.85  5555.2  324.17  5569.3  324.42
#Mann=8,-1,0
  4654.3     0.1       0  4692.8    0.07       0  4815.5     0.1       0
  5097.3    0.05       0  5101.4     0.1       0  5115.6    0.07       0
  5193.4     0.1       0  5237.7    0.07       0
Bank Sta=5097.3,5101.4
Exp/Cntr=0.3,0.1

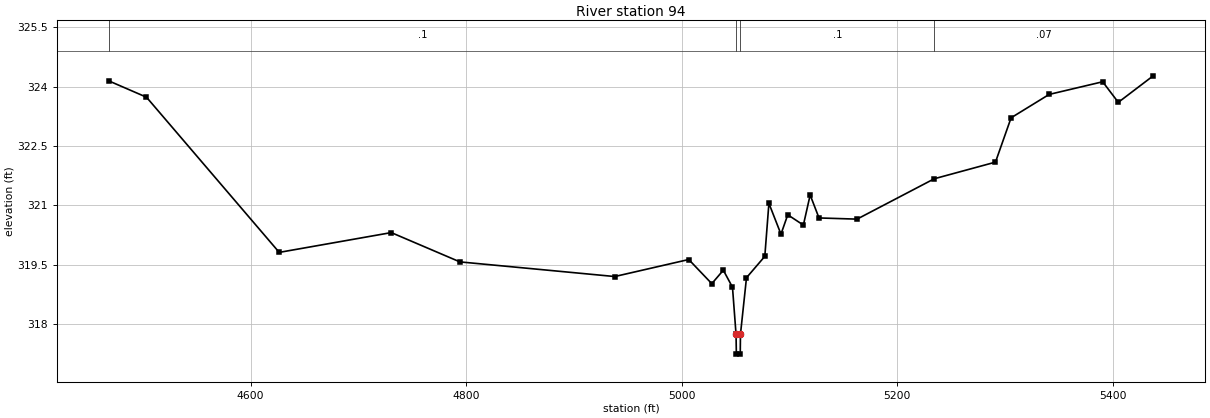
Type RM Length L Ch R = 1,94,0,0,0
BEGIN DESCRIPTION:
XS7371
END DESCRIPTION:
XS GIS Cut Line= 4
      2358254.21     13619930.40      2358643.77     13620052.33
      2358837.06     13619977.99      2359116.58     13619760.91
#Sta/Elev= 30
  4468.5  324.14  4503.3  323.73  4626.5  319.81  4730.5  320.31  4794.2  319.57
  4937.9  319.20  5006.6  319.63  5028.0  319.02  5038.7  319.36  5047.2  318.93
  5050.5  317.74  5050.8  317.24  5054.4  317.24  5054.6  317.74  5060.2  319.17
  5077.2  319.71  5081.0  321.05  5092.2  320.27  5098.5  320.76  5113.0  320.50
  5119.3  321.26  5127.5  320.68  5162.8  320.65  5234.5  321.67  5291.3  322.09
  5305.8  323.21  5341.1  323.80  5390.8  324.12  5405.3  323.60  5437.7  324.27
#Mann=4,-1,0
  4468.5     0.1       0  5050.5    0.05       0  5054.6     0.1       0
  5234.5    0.07       0
Bank Sta=5050.5,5054.6
Exp/Cntr=0.3,0.1

Chan Stop Cuts=-1