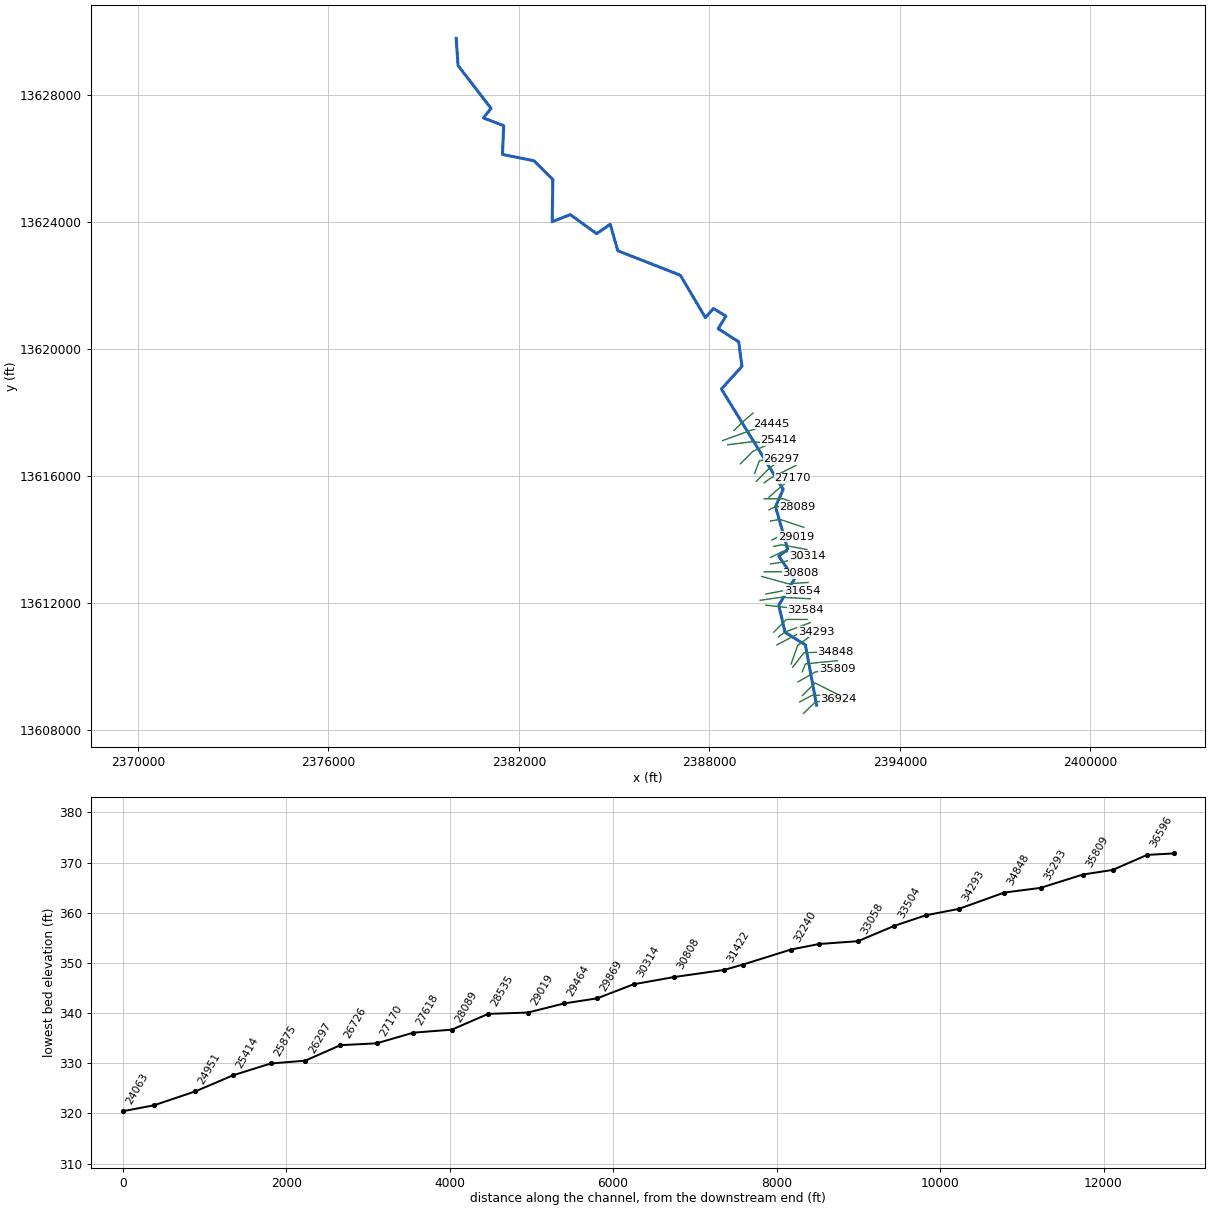
--- Stream0648.prj (project) ---

Proj Title=Stream0648 Base Level Engineering
Current Plan=p01
Default Exp/Contr=0.3,0.1
English Units
Geom File=g01
Flow File=f01
Plan File=p01
Y Axis Title=Elevation
X Axis Title(PF)=Main Channel Distance
X Axis Title(XS)=Station
BEGIN DESCRIPTION:
Stream0648
END DESCRIPTION:
DSS Export Rating Curves= 0
DSS Export Rating Curve Sorted= 0
DSS Export Volume Flow Curves= 0
DXF OffsetX= 0
DXF OffsetY= 0
DXF ScaleX= 1
DXF ScaleY= 10

--- Stream0648.p01 (plan) ---

Plan Title=Multiple Run
Short Identifier=Multiple
Geom File=g01
Flow File=f01
Subcritical Flow
K Sum by GR= 0
Std Step Tol= 0.01
Critical Tol= 0.01
Num of Std Step Trials= 20
Max Error Tol= 0.3
Flow Tol Ratio= 0.001
Split Flow NTrial= 30
Split Flow Tol= 0.02
Split Flow Ratio= 0.02
Log Output Level= 0
Friction Slope Method= 1
Unsteady Friction Slope Method= 2
Unsteady Bridges Friction Slope Method= 1
Parabolic Critical Depth
Global Vel Dist=  1 , 1 , 1
Global Log Level= 0
CheckData=True
Encroach Param= -1, 0, 0, 0
BEGIN DESCRIPTION:
Multiple Run
END DESCRIPTION:

--- Stream0648.f01 (steady flow) ---

Flow Title=Multiple
Number of Profiles=7
Profile Names=10-year,25-year,50-year,1pct_min,100-year,1pct_plu,500-year
River Rch & RM= Stream0648,Reach-1,36924
     527     839    1117     720    1436    2865    2352
River Rch & RM= Stream0648,Reach-1,35809
     867    1421    1927    1263    2520    5028    4277
River Rch & RM= Stream0648,Reach-1,25414
    1091    1808    2471    1630    3253    6490    5595
River Rch & RM= Stream0648,Reach-1,20457
    1280    2134    2928    1938    3867    7715    6694
River Rch & RM= Stream0648,Reach-1,12649
    1495    2508    3455    2295    4579    9137    7986
River Rch & RM= Stream0648,Reach-1,8589
    1542    2580    3548    2352    4692    9362    8148
Boundary for River Rch & Prof#=Stream0648,Reach-1,1
Up Type=0
Dn Type=3
Dn Slope=0.005
Boundary for River Rch & Prof#=Stream0648,Reach-1,2
Up Type=0
Dn Type=3
Dn Slope=0.005
Boundary for River Rch & Prof#=Stream0648,Reach-1,3
Up Type=0
Dn Type=3
Dn Slope=0.005
Boundary for River Rch & Prof#=Stream0648,Reach-1,4
Up Type=0
Dn Type=3
Dn Slope=0.005
Boundary for River Rch & Prof#=Stream0648,Reach-1,5
Up Type=0
Dn Type=3
Dn Slope=0.005
Boundary for River Rch & Prof#=Stream0648,Reach-1,6
Up Type=0
Dn Type=3
Dn Slope=0.005
Boundary for River Rch & Prof#=Stream0648,Reach-1,7
Up Type=0
Dn Type=3
Dn Slope=0.005

--- Stream0648.g01 (geometry) ---

Geom Title=Existing Conditions
Program Version=4.10

River Reach=Stream0648      ,Reach-1
Reach XY= 30
        2391375.       13608775.      2391021.47     13610674.01
      2390382.98     13611068.62      2390182.81     13611921.59
      2390675.51     13612745.03      2390182.29     13613475.09
      2390468.12     13613674.97      2390082.28      13615025.1
      2390322.86     13615569.03      2388377.14     13618730.97
       2389025.4     13619445.13      2388922.09     13620217.09
      2388276.58     13620631.03      2388519.95     13621027.28
      2388124.99     13621267.47      2387872.73     13620980.05
      2387084.68     13622314.24       2385115.3     13623085.16
      2384877.59     13623920.03       2384445.1     13623624.45
      2383619.15     13624222.94      2383048.01     13624000.53
      2383070.06     13625327.57      2382477.45     13625919.55
      2381482.65     13626118.55      2381521.84     13627023.82
      2380883.75     13627268.16      2381123.42     13627568.95
      2380083.82       13628918.        2380025.       13629775.

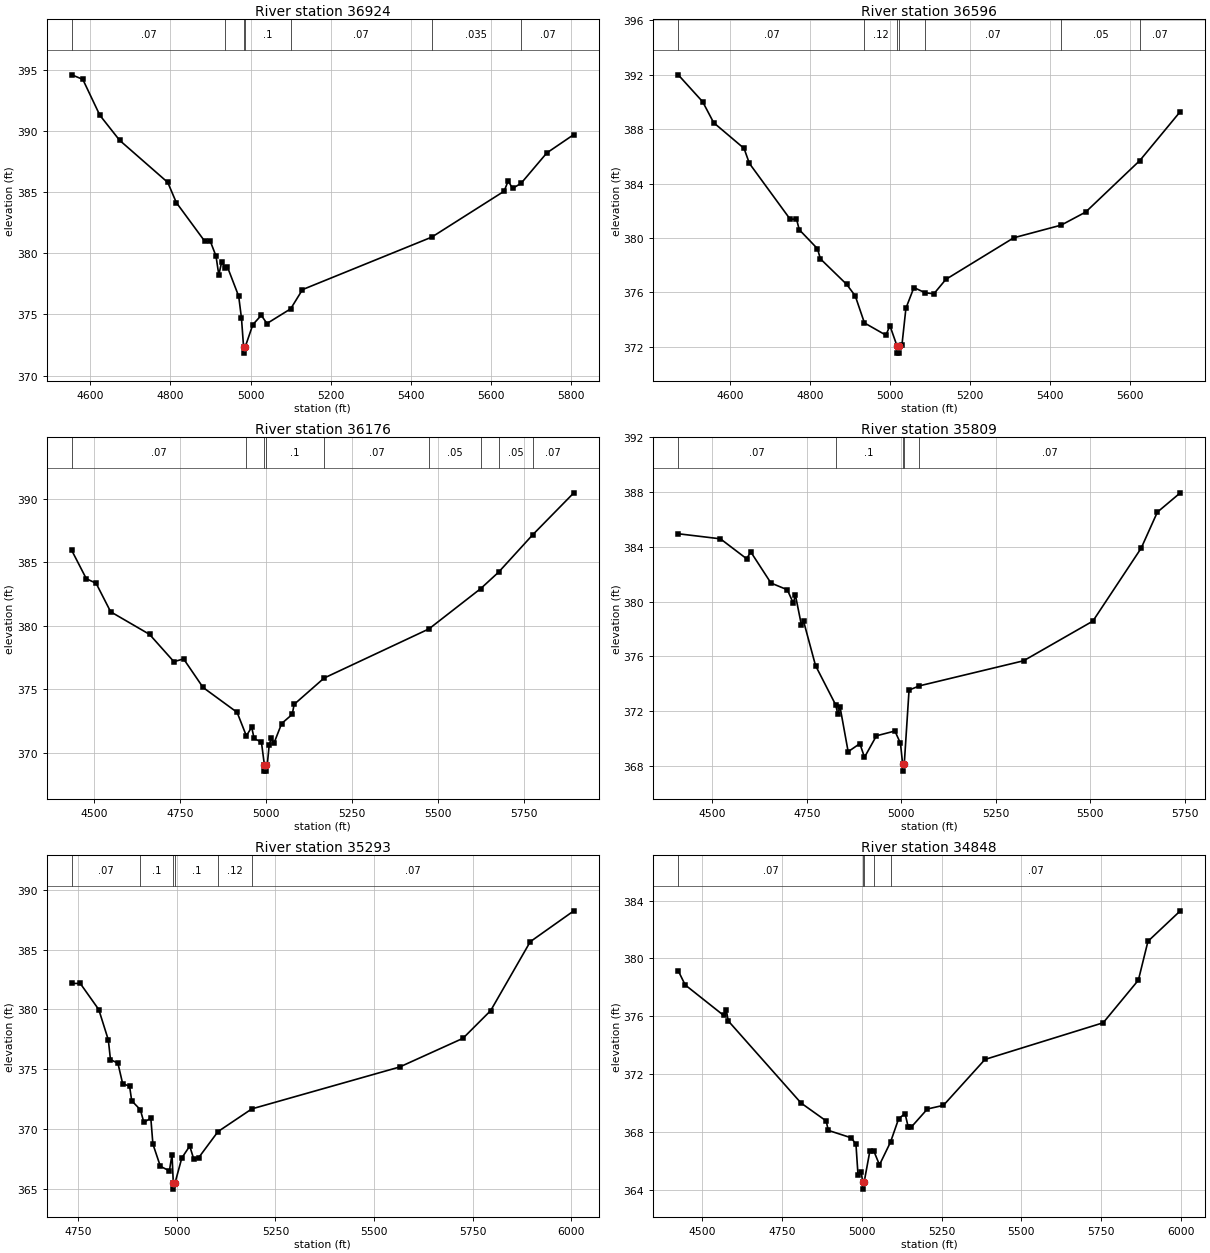
Type RM Length L Ch R = 1 ,36924   ,328,328,328
BEGIN DESCRIPTION:
Stream0648 65.0
END DESCRIPTION:
XS GIS Cut Line= 3
      2390964.53     13608516.69       2391338.2     13608876.25
      2392067.94     13608957.33
#Sta/Elev= 30
  4553.7  394.58  4581.2  394.21  4623.7  391.28  4673.1  389.23  4793.2  385.79
  4814.6  384.14  4885.3  380.99  4899.5  380.97  4913.6  379.77  4920.6  378.23
  4927.8  379.29  4936.8  378.79  4941.9   378.9  4970.2  376.49  4977.2  374.68
  4982.4  372.34  4982.6  371.84  4986.4  372.34  5005.5  374.17  5026.6  374.93
  5040.7  374.26  5099.9  375.46  5129.4  377.03    5452  381.32  5632.5  385.07
  5642.6  385.91  5653.6   385.3  5674.7  385.71  5739.1   388.2  5806.5   389.7
#Mann= 7 ,-1 , 0
  4553.7     .07       0  4936.8      .1       0  4982.4     .05       0
  4986.4      .1       0  5099.9     .07       0    5452    .035       0
  5674.7     .07       0
Bank Sta=4982.4,4986.4
XS Rating Curve= 0 ,0
Exp/Cntr=0.3,0.1

Type RM Length L Ch R = 1 ,36596   ,420,420,420
BEGIN DESCRIPTION:
XS7392
END DESCRIPTION:
XS GIS Cut Line= 3
      2390848.23     13608879.79      2391239.49     13609091.29
      2392051.91     13609059.63
#Sta/Elev= 30
  4469.2     392  4530.4  390.02    4558  388.48  4634.1  386.59  4647.4  385.49
  4749.7  381.38  4765.4   381.4  4772.5  380.61  4817.9  379.22  4825.4  378.47
    4891   376.6  4912.6  375.75  4935.7  373.76  4989.5  372.86  4999.5  373.56
  5017.6  372.04  5017.8  371.54  5021.3  371.54  5021.6  372.04  5029.6  372.13
  5039.6  374.84  5059.6  376.36  5087.7  375.98  5109.6   375.9  5139.6  376.96
  5309.8  380.02  5428.5  380.95  5489.9  381.91  5625.6   385.7    5727   389.3
#Mann= 7 ,-1 , 0
  4469.2     .07       0  4935.7     .12       0  5017.6     .05       0
  5021.6     .12       0  5087.7     .07       0  5428.5     .05       0
  5625.6     .07       0
Bank Sta=5017.6,5021.6
XS Rating Curve= 0 ,0
Exp/Cntr=0.3,0.1

Type RM Length L Ch R = 1 ,36176   ,367,367,367
BEGIN DESCRIPTION:
Stream0648 64.0
END DESCRIPTION:
XS GIS Cut Line= 3
      2390925.02     13609075.02        2391325.       13609475.
      2392125.01     13609074.99
#Sta/Elev= 30
  4434.9  385.93  4477.3   383.7  4505.6  383.35    4548   381.1  4661.1  379.32
  4731.9  377.17  4760.1  377.39  4816.7  375.14  4915.7  373.18  4942.6  371.33
  4958.1  372.01  4965.2  371.12  4986.4  370.84    4995  369.05  4995.3  368.55
  4998.8  368.55  4999.1  369.05  5003.4  369.05  5008.9  370.57  5014.5  371.15
  5022.9  370.75  5045.3   372.3    5076  373.02  5081.6  373.81  5168.7  375.88
  5473.5  379.75  5623.9  382.92  5676.1  384.22  5775.5  387.17    5895  390.47
#Mann= 9 ,-1 , 0
  4434.9     .07       0  4942.6      .1       0    4995     .05       0
  4999.1      .1       0  5168.7     .07       0  5473.5     .05       0
  5623.9     .07       0  5676.1     .05       0  5775.5     .07       0
Bank Sta=4995,4999.1
XS Rating Curve= 0 ,0
Exp/Cntr=0.3,0.1

Type RM Length L Ch R = 1 ,35809   ,516,516,516
BEGIN DESCRIPTION:
Stream0648 63.0
END DESCRIPTION:
XS GIS Cut Line= 3
      2390788.28     13609507.26      2391334.67     13609820.99
      2392025.03       13609925.
#Sta/Elev= 30
  4409.7  384.96  4521.3  384.59  4590.3  383.14  4601.9  383.62    4655  381.36
  4698.2  380.87    4714   379.9  4719.7  380.47  4735.5   378.3  4741.3  378.57
  4772.9  375.33  4826.2  372.46  4831.9  371.78  4837.6  372.33  4859.2  369.04
  4890.2  369.63  4902.4  368.63    4934   370.2  4982.9  370.55  4997.6  369.65
  5003.4  368.12  5003.7  367.62  5007.6  368.12  5020.3  373.54  5047.8  373.85
  5323.2  375.68  5506.6  378.58  5634.4  383.91  5677.2  386.54  5737.9  387.95
#Mann= 5 ,-1 , 0
  4409.7     .07       0  4826.2      .1       0  5003.4     .05       0
  5007.6      .1       0  5047.8     .07       0
Bank Sta=5003.4,5007.6
XS Rating Curve= 0 ,0
Exp/Cntr=0.3,0.1

Type RM Length L Ch R = 1 ,35293   ,445,445,445
BEGIN DESCRIPTION:
Stream0648 62.0
END DESCRIPTION:
XS GIS Cut Line= 3
      2390925.02     13609825.04        2391025.       13610075.
        2392025.       13610175.
#Sta/Elev= 30
    4733  382.17  4754.5  382.17  4801.6  379.98  4825.8  377.44  4831.2   375.8
  4850.1   375.5  4862.2  373.78  4879.7  373.58  4885.1  372.36    4907  371.61
    4916  370.55  4933.6  370.91  4938.9  368.74  4957.8  366.88  4980.7   366.5
  4987.4  367.85  4990.7  365.47  4990.9  364.97  4994.9  365.47  5012.3  367.58
  5032.4  368.57  5042.4   367.5    5055   367.6  5104.1  369.78    5190  371.68
    5565  375.18  5725.8  377.58  5796.2   379.9  5896.6  385.66  6007.2  388.24
#Mann= 6 ,-1 , 0
    4733     .07       0    4907      .1       0  4990.7     .05       0
  4994.9      .1       0  5104.1     .12       0    5190     .07       0
Bank Sta=4990.7,4994.9
XS Rating Curve= 0 ,0
Exp/Cntr=0.3,0.1

Type RM Length L Ch R = 1 ,34848   ,555,555,555
BEGIN DESCRIPTION:
Stream0648 61.0
END DESCRIPTION:
XS GIS Cut Line= 3
      2390625.01     13609975.01        2390975.       13610425.
      2391976.22     13610462.57
#Sta/Elev= 30
  4425.6  379.15  4447.3  378.17  4567.7  376.06  4575.8  376.46  4582.1  375.68
  4810.2  369.99  4888.9  368.75  4895.2   368.1  4967.6  367.58  4982.1  367.13
  4988.4  365.03  4998.2   365.2  5003.5  364.53  5003.8  364.03  5007.8  364.53
  5025.7  366.68  5037.9  366.67  5055.7  365.71  5090.3  367.29  5115.8  368.91
  5135.8  369.26  5145.8  368.32  5155.8  368.34  5205.8  369.58  5255.9  369.83
    5386  373.01  5756.2  375.55  5866.3   378.5  5896.3  381.19  5997.6   383.3
#Mann= 5 ,-1 , 0
  4425.6     .07       0  5003.5     .05       0  5007.8     .07       0
  5037.9     .12       0  5090.3     .07       0
Bank Sta=5003.5,5007.8
XS Rating Curve= 0 ,0
Exp/Cntr=0.3,0.1

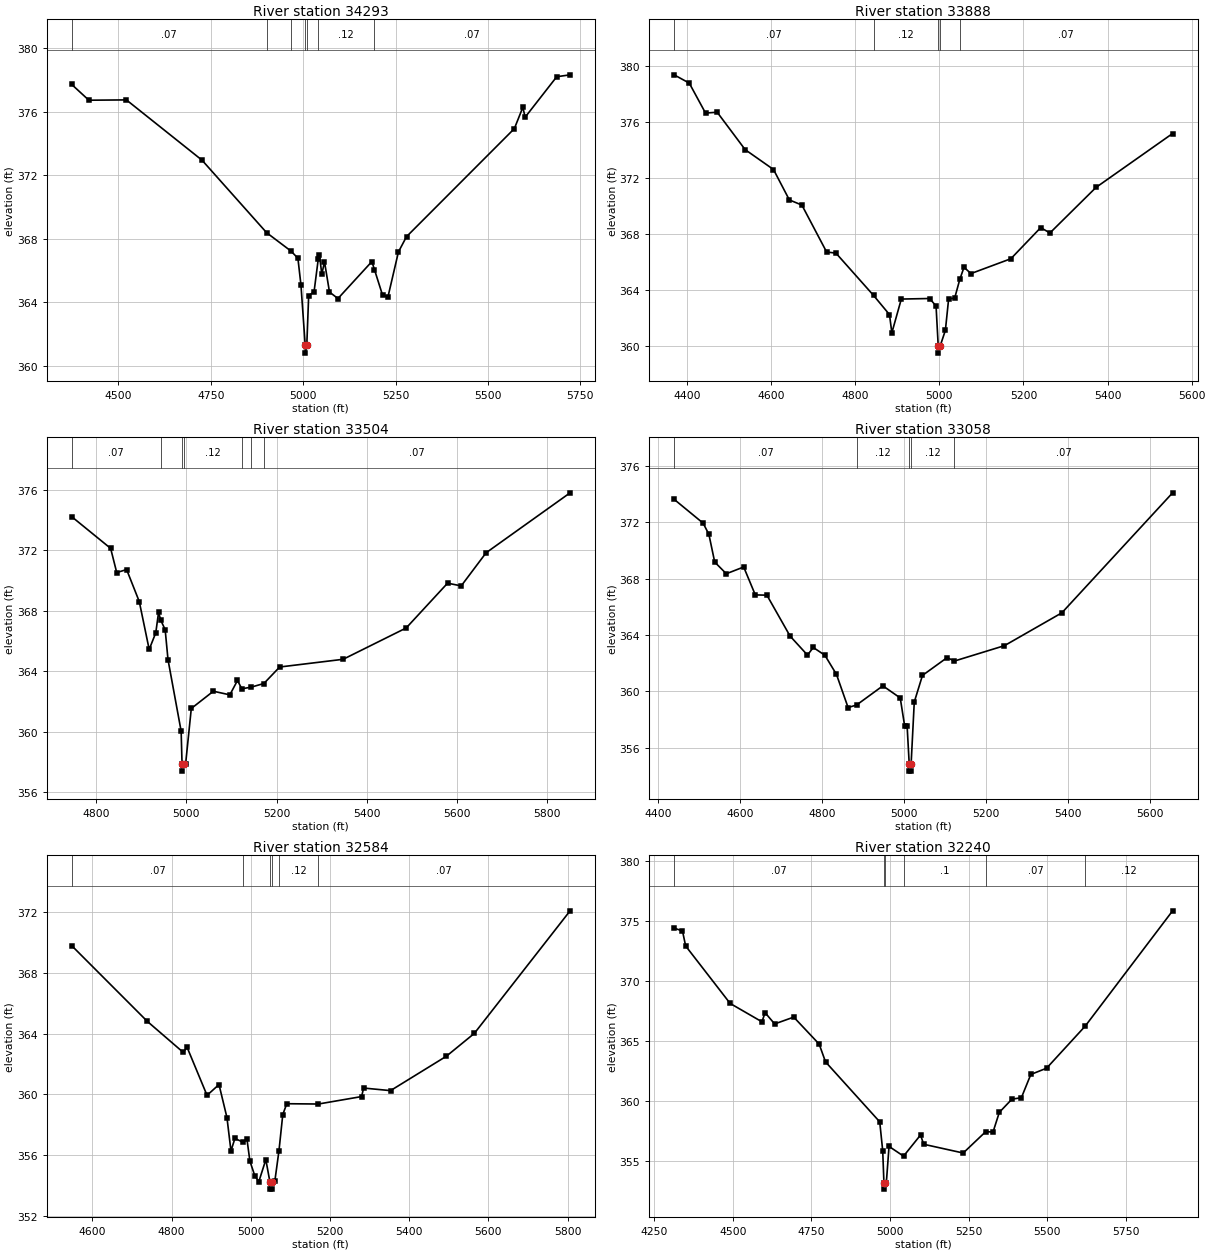
Type RM Length L Ch R = 1 ,34293   ,405,405,405
BEGIN DESCRIPTION:
Stream0648 60.0
END DESCRIPTION:
XS GIS Cut Line= 3
        2390575.     13610075.01      2390774.17     13610649.41
      2391366.38     13611093.56
#Sta/Elev= 30
  4373.8  377.72  4420.5  376.72    4522  376.74  4726.6  372.94  4901.3  368.37
  4967.3  367.21  4985.9  366.76  4994.2  365.06  5005.6  361.28  5005.9  360.78
  5009.9  361.28    5015   364.4  5029.6  364.65  5040.9   366.7  5044.2  366.97
  5050.5  365.75  5057.8  366.54  5071.3  364.63  5094.2  364.22  5185.9  366.55
    5193  366.04    5215  364.42  5229.6  364.34  5257.8  367.16  5279.6  368.12
  5571.3  374.93  5594.2  376.27  5600.5  375.65  5685.9   378.2    5722  378.32
#Mann= 7 ,-1 , 0
  4373.8     .07       0  4901.3     .12       0  4967.3     .07       0
  5005.6     .05       0  5009.9     .07       0  5040.9     .12       0
    5193     .07       0
Bank Sta=5005.6,5009.9
XS Rating Curve= 0 ,0
Exp/Cntr=0.3,0.1

Type RM Length L Ch R = 1 ,33888   ,384,384,384
BEGIN DESCRIPTION:
Stream0648 59.0
END DESCRIPTION:
XS GIS Cut Line= 3
      2390125.04     13610675.02      2390760.58     13611003.28
      2391224.97       13611075.
#Sta/Elev= 30
  4369.5  379.37  4405.5  378.78  4444.2  376.64  4471.9   376.7  4538.4  374.03
  4605.8  372.61  4643.5  370.44  4673.3  370.07  4732.1  366.72  4754.3  366.64
  4843.7  363.62  4881.6  362.25  4887.2  360.95  4909.7  363.36  4977.2   363.4
  4992.3  362.86  4997.5     360  4997.8   359.5    5002     360  5014.5  361.13
  5022.2  363.37  5036.6  363.43  5048.7  364.76  5058.8  365.63  5075.3  365.18
  5170.2  366.24  5241.1  368.46  5263.1  368.08  5372.6  371.33  5554.7  375.18
#Mann= 5 ,-1 , 0
  4369.5     .07       0  4843.7     .12       0  4997.5     .05       0
    5002     .12       0  5048.7     .07       0
Bank Sta=4997.5,5002
XS Rating Curve= 0 ,0
Exp/Cntr=0.3,0.1

Type RM Length L Ch R = 1 ,33504   ,446,446,446
BEGIN DESCRIPTION:
Stream0648 58.0
END DESCRIPTION:
XS GIS Cut Line= 3
      2390174.97     13610924.98        2390375.       13611075.
      2391174.96     13611374.99
#Sta/Elev= 30
  4745.9  374.22  4832.4  372.12  4845.9  370.52  4867.8  370.72  4895.9   368.6
  4917.8  365.44  4932.4  366.54  4938.6  367.89  4943.6  367.36  4953.2  366.75
  4959.5  364.77  4988.6  360.04  4990.6   357.9  4990.9   357.4  4995.1   357.9
  4998.6   357.9  5011.1  361.54    5060  362.68  5096.5  362.44  5113.4  363.39
  5123.1  362.84  5143.9  362.95  5171.9  363.19  5206.9  364.28  5347.5  364.79
  5487.2  366.86  5578.9  369.82  5609.1  369.64  5664.3  371.83  5850.3  375.79
#Mann= 7 ,-1 , 0
  4745.9     .07       0  4943.6     .12       0  4990.6     .05       0
  4995.1     .12       0  5123.1     .07       0  5143.9     .12       0
  5171.9     .07       0
Bank Sta=4990.6,4995.1
XS Rating Curve= 0 ,0
Exp/Cntr=0.3,0.1

Type RM Length L Ch R = 1 ,33058   ,474,474,474
BEGIN DESCRIPTION:
Stream0648 57.0
END DESCRIPTION:
XS GIS Cut Line= 3
      2390025.01     13611075.01        2390425.       13611475.
      2391075.03       13611475.
#Sta/Elev= 30
  4438.6  373.62  4509.3  371.93  4523.4  371.14  4537.6  369.17  4565.9  368.34
  4608.3  368.82  4636.6  366.84  4664.9  366.82  4721.4  363.92  4763.9  362.57
    4778  363.11  4806.3  362.56  4834.6   361.2  4862.9  358.85  4883.6  359.03
  4947.7  360.39  4990.1  359.53  5000.7  357.57  5006.8  357.57    5012  354.84
  5012.3  354.34  5016.2  354.34  5016.6  354.84  5024.3  359.24  5044.3  361.13
  5104.3  362.39  5122.4  362.15  5244.3  363.24  5384.3  365.57  5654.3  374.08
#Mann= 5 ,-1 , 0
  4438.6     .07       0  4883.6     .12       0    5012     .05       0
  5016.6     .12       0  5122.4     .07       0
Bank Sta=5012,5016.6
XS Rating Curve= 0 ,0
Exp/Cntr=0.3,0.1

Type RM Length L Ch R = 1 ,32584   ,344,344,344
BEGIN DESCRIPTION:
Stream0648 56.0
END DESCRIPTION:
XS GIS Cut Line= 3
      2389774.97       13611925.        2390225.       13611875.
      2391024.98       13611775.
#Sta/Elev= 30
  4547.4  369.78  4738.6   364.8  4829.1  362.77  4839.2  363.09  4889.5  359.94
  4919.7  360.65  4939.8  358.48  4949.9  356.29  4959.9  357.11  4981.3  356.85
  4990.1   357.1  4997.7  355.63  5010.3  354.64  5020.4  354.28    5038  355.72
  5048.1  354.28  5048.5  353.78  5052.7  353.78    5053  354.28  5060.7   354.3
  5071.2  356.31  5080.8  358.68  5090.9  359.39  5170.7  359.37  5279.9  359.86
  5284.9  360.42  5352.9  360.25    5494  362.51  5564.6  364.01  5806.4  372.06
#Mann= 6 ,-1 , 0
  4547.4     .07       0  4981.3      .1       0  5048.1     .05       0
    5053      .1       0  5071.2     .12       0  5170.7     .07       0
Bank Sta=5048.1,5053
XS Rating Curve= 0 ,0
Exp/Cntr=0.3,0.1

Type RM Length L Ch R = 1 ,32240   ,586,586,586
BEGIN DESCRIPTION:
Stream0648 55.0
END DESCRIPTION:
XS GIS Cut Line= 3
      2389598.66     13612078.22      2390262.62     13612173.07
      2391174.96       13612125.
#Sta/Elev= 30
  4313.5  374.44  4340.1   374.2  4350.2  372.95  4491.6  368.16  4592.6  366.63
  4602.7  367.39    4633  366.45  4693.7  367.02  4774.5  364.77  4794.7  363.29
    4967  358.29  4976.5  355.88  4980.4  353.18  4980.8  352.68  4985.3  353.18
  4987.9  353.18  4996.6  356.24  5042.7  355.43  5096.7  357.19  5106.7  356.42
  5232.3  355.69  5303.8  357.47  5327.1  357.44  5347.1  359.08  5387.1  360.18
  5417.2   360.3  5447.2  362.24  5497.3  362.76  5620.1  366.27  5897.8  375.88
#Mann= 6 ,-1 , 0
  4313.5     .07       0  4980.4     .05       0  4985.3     .07       0
  5042.7      .1       0  5303.8     .07       0  5620.1     .12       0
Bank Sta=4980.4,4985.3
XS Rating Curve= 0 ,0
Exp/Cntr=0.3,0.1

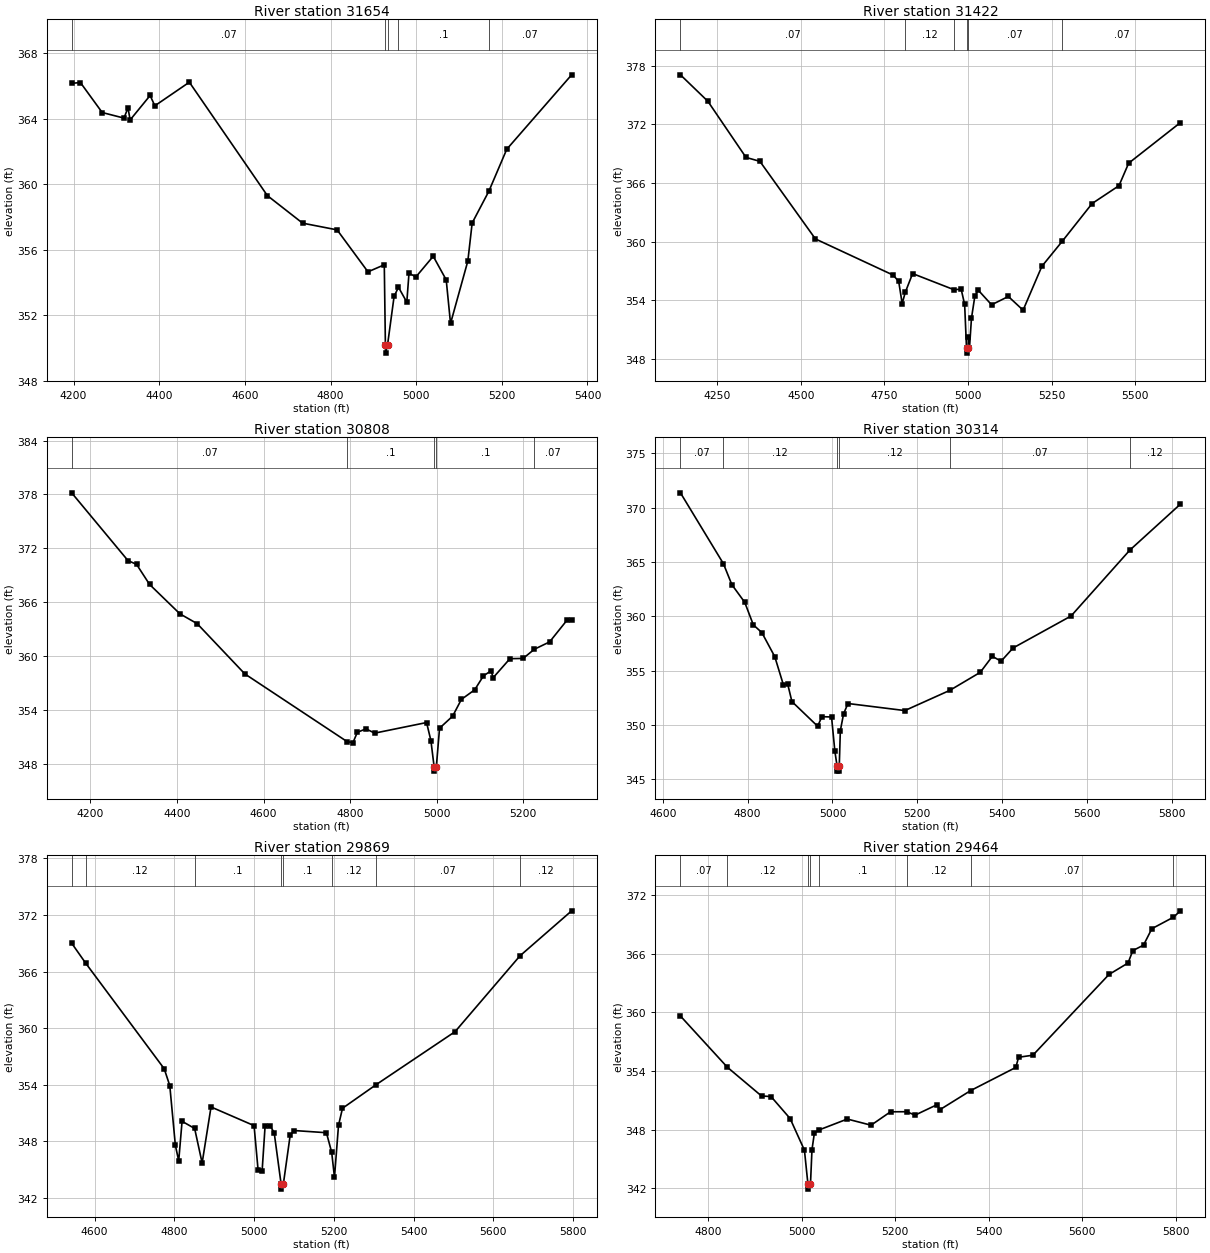
Type RM Length L Ch R = 1 ,31654   ,232,232,232
BEGIN DESCRIPTION:
Stream0648 54.0
END DESCRIPTION:
XS GIS Cut Line= 3
      2389774.96     13612274.99        2390575.       13612425.
      2390924.96     13612375.01
#Sta/Elev= 30
  4195.5  366.15  4215.9   366.2  4266.8  364.37  4317.6  364.03    4327  364.65
  4332.1  363.92  4378.7  365.41  4389.7  364.78  4470.3  366.22  4652.5   359.3
  4734.8  357.62  4815.3  357.21  4887.4  354.65  4925.5  355.08  4928.1  350.19
  4928.5  349.69  4933.1  350.19  4948.4  353.15  4958.6  353.71  4978.1   352.8
  4983.2  354.57  4999.3  354.34  5039.8   355.6  5070.1  354.16  5080.2   351.5
  5120.6  355.31  5130.7  357.63  5169.7  359.57  5211.5  362.13    5363  366.67
#Mann= 5 ,-1 , 0
  4195.5     .07       0  4928.1     .05       0  4933.1     .07       0
  4958.6      .1       0  5169.7     .07       0
Bank Sta=4928.1,4933.1
XS Rating Curve= 0 ,0
Exp/Cntr=0.3,0.1

Type RM Length L Ch R = 1 ,31422   ,614,614,614
BEGIN DESCRIPTION:
XS7391
END DESCRIPTION:
XS GIS Cut Line= 3
      2389646.08     13612829.11      2390476.03     13612599.88
      2391108.37      13612639.4
#Sta/Elev= 30
  4140.3  377.05  4222.2  374.35  4336.3  368.61  4377.8  368.21  4543.8  360.28
  4776.4  356.58  4792.8  355.93  4803.1  353.68  4812.5  354.83  4834.3  356.74
  4957.3   355.1  4979.5  355.14  4989.9  353.58  4995.5  349.11  4995.9  348.61
  5000.5  349.11  5001.1  350.29  5004.3  349.11  5010.3  352.18  5020.3  354.41
  5030.4  355.05  5070.4  353.55  5120.5   354.4  5164.6     353  5220.7  357.48
  5282.1  360.06    5371   363.9  5451.2  365.72  5480.2  368.02  5634.9  372.17
#Mann= 6 ,-1 , 0
  4140.3     .07       0  4812.5     .12       0  4957.3     .07       0
  4995.5     .05       0  5000.5     .07       0  5282.1     .07       0
Bank Sta=4995.5,5000.5
XS Rating Curve= 0 ,0
Exp/Cntr=0.3,0.1

Type RM Length L Ch R = 1 ,30808   ,494,494,494
BEGIN DESCRIPTION:
Stream0648 53.0
END DESCRIPTION:
XS GIS Cut Line= 3
      2389725.03       13612975.      2390594.59     13612979.27
      2390875.02       13612925.
#Sta/Elev= 30
  4156.6  378.18  4286.6  370.64  4306.6  370.21  4336.6  367.98  4406.6  364.71
  4446.6  363.61  4556.6  358.02  4793.2  350.47  4806.6  350.37  4816.6  351.51
  4836.6   351.9  4856.6  351.42  4976.6   352.6  4986.6   350.6    4994  347.69
  4994.4  347.19  4999.2  347.69  5006.6  351.97  5036.8  353.31  5057.1  355.18
  5087.7  356.24  5108.1   357.8  5125.5  358.36  5130.6   357.6  5169.2  359.71
  5199.7  359.74  5225.6  360.76  5260.9  361.58  5301.6  364.03  5311.8  364.02
#Mann= 5 ,-1 , 0
  4156.6     .07       0  4793.2      .1       0    4994     .05       0
  4999.2      .1       0  5225.6     .07       0
Bank Sta=4994,4999.2
XS Rating Curve= 0 ,0
Exp/Cntr=0.3,0.1

Type RM Length L Ch R = 1 ,30314   ,445,445,445
BEGIN DESCRIPTION:
Stream0648 52.0
END DESCRIPTION:
XS GIS Cut Line= 3
      2389924.98       13613225.        2390275.       13613275.
      2391075.01       13613475.
#Sta/Elev= 30
  4641.8  371.35  4743.1  364.83    4763   362.9  4793.3  361.28  4813.5  359.21
  4833.7  358.49  4864.1  356.28  4884.3   353.7  4894.4  353.78  4904.5  352.15
  4965.1  349.88  4975.2  350.76  4997.9  350.73  5005.7  347.58  5010.8  346.25
  5011.2  345.75  5015.7  345.75  5016.1  346.25  5018.6  349.47  5026.3  351.03
  5036.6  351.97  5170.6  351.32  5276.6  353.18  5348.4  354.84  5376.8  356.31
  5397.4  355.86  5425.7  357.08  5562.3  360.02  5700.8  366.08    5820  370.31
#Mann= 6 ,-1 , 0
  4641.8     .07       0  4743.1     .12       0  5010.8     .05       0
  5016.1     .12       0  5276.6     .07       0  5700.8     .12       0
Bank Sta=5010.8,5016.1
XS Rating Curve= 0 ,0
Exp/Cntr=0.3,0.1

Type RM Length L Ch R = 1 ,29869   ,405,405,405
BEGIN DESCRIPTION:
Stream0648 51.0
END DESCRIPTION:
XS GIS Cut Line= 3
      2389924.96     13613424.98        2390325.       13613625.
      2391125.02       13613525.
#Sta/Elev= 30
  4542.6  369.02  4577.6  366.91  4774.6  355.71  4788.6  353.92  4802.6  347.58
    4811  345.95  4819.4  350.14  4850.9  349.38  4869.7  345.72    4892  351.66
  4999.9  349.68    5010  344.97  5020.1  344.88  5027.6  349.67  5040.2  349.64
  5050.3  348.95  5067.8  343.45  5068.2  342.95  5073.2  343.45  5090.6  348.71
  5100.7  349.16  5181.3  348.93  5194.5  346.85  5201.5   344.2  5211.6  349.71
  5221.6  351.52  5306.5  354.04  5503.8  359.64  5666.6  367.68  5796.1  372.45
#Mann= 8 ,-1 , 0
  4542.6     .07       0  4577.6     .12       0  4850.9      .1       0
  5067.8     .05       0  5073.2      .1       0  5194.5     .12       0
  5306.5     .07       0  5666.6     .12       0
Bank Sta=5067.8,5073.2
XS Rating Curve= 0 ,0
Exp/Cntr=0.3,0.1

Type RM Length L Ch R = 1 ,29464   ,445,445,445
BEGIN DESCRIPTION:
Stream0648 50.0
END DESCRIPTION:
XS GIS Cut Line= 3
      2390025.04     13613775.01        2390275.       13613825.
      2391075.05     13613674.99
#Sta/Elev= 30
  4740.7  359.64    4841   354.4    4914  351.46  4934.4   351.4  4975.2  349.15
  5005.8  345.91  5013.3  342.43  5013.7  341.93  5018.7  342.43  5021.9  345.96
    5027  347.64  5036.3  347.97  5097.4   349.1  5148.2  348.47  5189.8  349.84
  5224.4  349.85  5242.3   349.5  5289.8  350.58  5294.9  350.04  5361.1  352.01
  5457.7  354.38  5463.6  355.42  5494.2  355.63  5656.9  363.89  5697.6  365.06
  5707.8  366.33  5730.7  366.89  5748.5  368.57  5794.8  369.75  5809.6   370.4
#Mann= 8 ,-1 , 0
  4740.7     .07       0    4841     .12       0  5013.3     .05       0
  5018.7     .12       0  5036.3      .1       0  5224.4     .12       0
  5361.1     .07       0  5794.8     .12       0
Bank Sta=5013.3,5018.7
XS Rating Curve= 0 ,0
Exp/Cntr=0.3,0.1

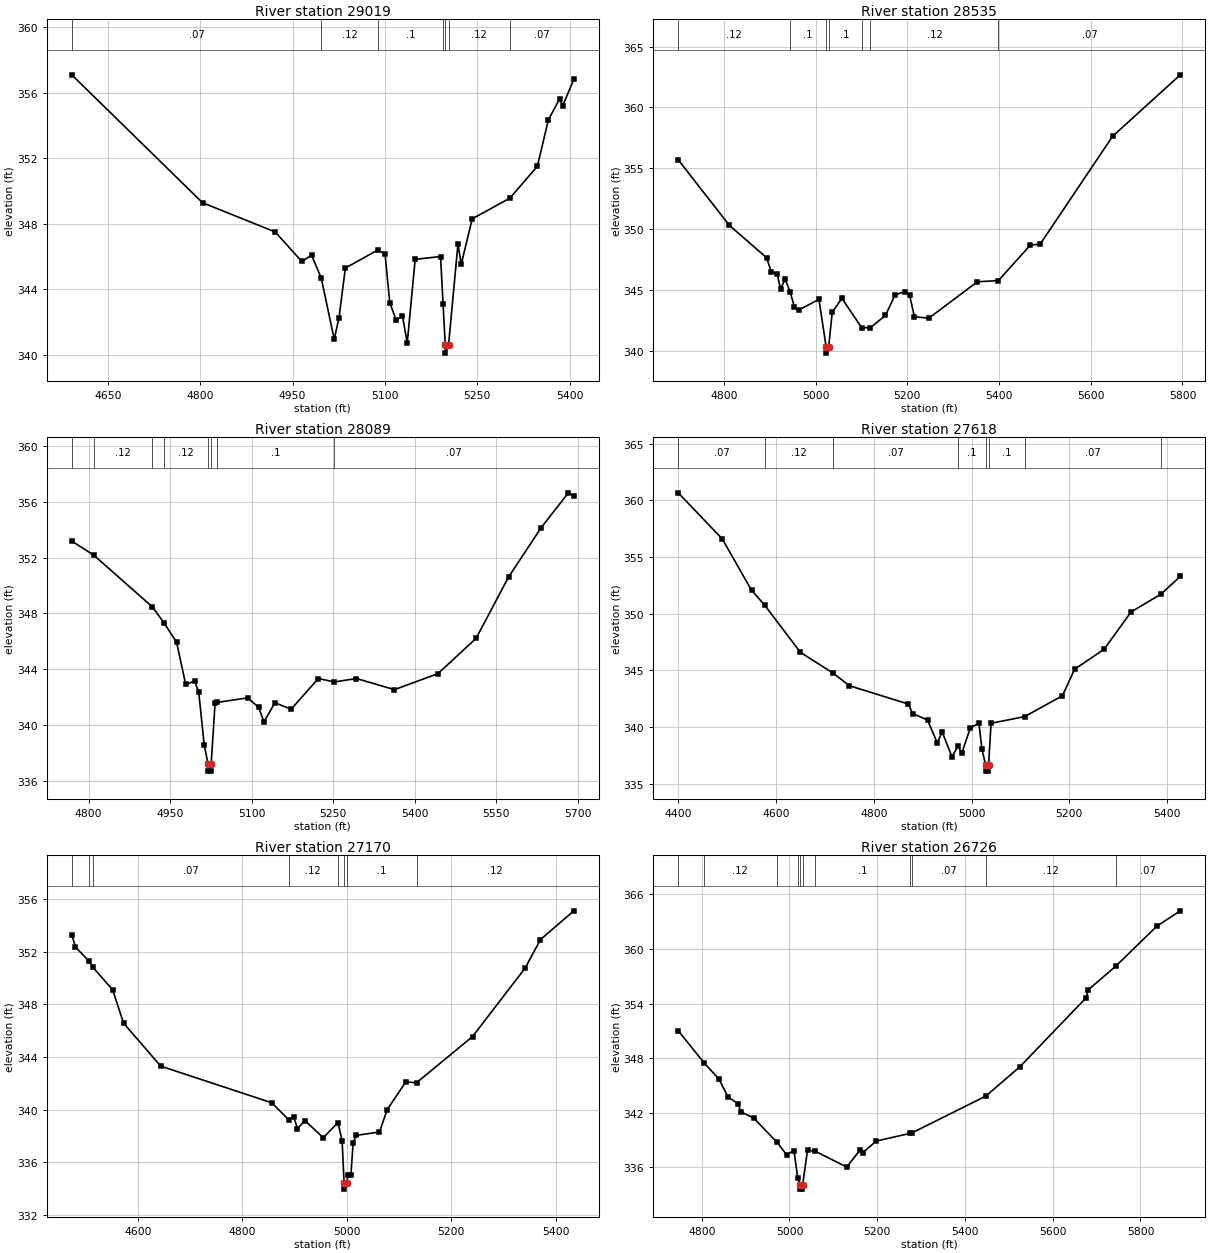
Type RM Length L Ch R = 1 ,29019   ,484,484,484
BEGIN DESCRIPTION:
Stream0648 49.0
END DESCRIPTION:
XS GIS Cut Line= 3
      2389974.97     13613974.99        2390325.       13614175.
      2390725.05     13614074.99
#Sta/Elev= 30
  4591.3  357.08  4803.7  349.28  4921.7   347.5  4964.9   345.7  4980.8  346.08
  4996.5  344.69  5017.6  340.95  5025.4  342.28  5035.7   345.3  5088.1  346.39
  5100.1  346.17  5107.8  343.19  5118.1  342.13  5128.4  342.38  5136.2  340.74
  5149.1  345.83  5190.3     346  5194.4  343.09  5197.9  340.61  5198.3  340.11
  5203.3  340.61  5218.6  346.78  5223.8  345.52  5241.8   348.3  5302.9  349.56
  5347.5   351.5  5365.5  354.34  5383.6  355.61  5388.7  355.19  5406.8  356.81
#Mann= 7 ,-1 , 0
  4591.3     .07       0  4996.5     .12       0  5088.1      .1       0
  5194.4     .12       0  5197.9     .05       0  5203.3     .12       0
  5302.9     .07       0
Bank Sta=5197.9,5203.3
XS Rating Curve= 0 ,0
Exp/Cntr=0.3,0.1

Type RM Length L Ch R = 1 ,28535   ,446,446,446
BEGIN DESCRIPTION:
Stream0648 48.0
END DESCRIPTION:
XS GIS Cut Line= 3
      2389925.01       13614575.        2390225.       13614625.
      2390975.01       13614375.
#Sta/Elev= 30
  4700.6  355.71  4812.1  350.33  4893.2  347.68  4903.3  346.54    4916  346.37
  4923.6  345.14  4933.8   345.9  4944.3   344.9    4954  343.63  4964.2   343.4
  5007.4  344.26  5023.1  340.35  5023.5  339.85  5028.6  340.35  5036.3  343.19
  5057.4  344.35  5100.6  341.93  5119.6  341.94  5152.3  342.94  5173.4  344.62
  5194.5   344.9    5205  344.62  5215.5  342.83  5247.2  342.72  5352.6   345.7
  5398.7   345.8  5468.5  348.72  5489.6  348.78  5647.7  357.64  5795.3  362.68
#Mann= 7 ,-1 , 0
  4700.6     .12       0  4944.3      .1       0  5023.1     .05       0
  5028.6      .1       0  5100.6     .07       0  5119.6     .12       0
  5398.7     .07       0
Bank Sta=5023.1,5028.6
XS Rating Curve= 0 ,0
Exp/Cntr=0.3,0.1

Type RM Length L Ch R = 1 ,28089   ,471,471,471
BEGIN DESCRIPTION:
Stream0648 47.0
END DESCRIPTION:
XS GIS Cut Line= 3
        2389875.       13614925.        2390075.       13615025.
        2390775.       13615025.
#Sta/Elev= 30
  4769.1  353.19  4809.6  352.18  4917.5  348.47  4938.8  347.33    4962  345.93
  4978.7  342.91  4995.2  343.16  5002.7  342.34  5012.7  338.58  5019.9   337.2
  5020.4   336.7  5025.1   336.7  5025.5   337.2  5032.7  341.57  5035.4  341.62
  5092.7  341.95  5112.7  341.28  5122.7  340.23  5142.7   341.6  5172.7  341.14
  5222.7  343.34  5252.1  343.09  5292.7  343.34  5362.7  342.54  5442.7  343.69
  5512.7  346.21  5572.7  350.62  5632.7  354.16  5682.7  356.65  5692.7  356.44
#Mann= 8 ,-1 , 0
  4769.1     .07       0  4809.6     .12       0  4917.5     .07       0
  4938.8     .12       0  5019.9     .05       0  5025.5     .12       0
  5035.4      .1       0  5252.1     .07       0
Bank Sta=5019.9,5025.5
XS Rating Curve= 0 ,0
Exp/Cntr=0.3,0.1

Type RM Length L Ch R = 1 ,27618   ,448,448,448
BEGIN DESCRIPTION:
Stream0648 46.0
END DESCRIPTION:
XS GIS Cut Line= 3
        2389725.       13615275.        2390325.       13615275.
        2390725.       13615125.
#Sta/Elev= 30
    4400  360.66    4490   356.6    4550  352.06  4576.6  350.76    4650  346.58
  4716.2  344.77    4750  343.64    4870  342.03    4880  341.17    4910  340.61
    4930  338.59    4940  339.56    4960  337.36  4972.6  338.33    4980  337.67
  4997.5  339.91  5015.1  340.33  5021.4  338.03  5029.2   336.6  5029.6   336.1
  5034.4   336.1  5034.9   336.6    5040  340.32  5108.6  340.91    5186  342.75
  5210.9  345.09  5271.4  346.86  5326.6  350.15    5388  351.73  5427.2  353.29
#Mann= 8 ,-1 , 0
    4400     .07       0  4576.6     .12       0  4716.2     .07       0
  4972.6      .1       0  5029.2     .05       0  5034.9      .1       0
  5108.6     .07       0    5388     .12       0
Bank Sta=5029.2,5034.9
XS Rating Curve= 0 ,0
Exp/Cntr=0.3,0.1

Type RM Length L Ch R = 1 ,27170   ,444,444,444
BEGIN DESCRIPTION:
Stream0648 45.0
END DESCRIPTION:
XS GIS Cut Line= 3
      2389874.99     13615324.99        2390275.       13615675.
      2390624.97     13615924.98
#Sta/Elev= 30
  4473.1  353.29  4480.2  352.34  4505.7  351.29  4513.8   350.8  4551.4   349.1
  4572.3  346.57  4643.5  343.31  4856.1  340.53  4888.2  339.26  4898.3  339.45
  4905.4  338.57  4919.7  339.18  4954.8  337.88    4983  339.03  4990.9  337.62
  4994.6  334.48  4995.1  333.98  5000.4  334.48  5001.3  335.08  5007.7  335.08
    5012   337.5  5018.1  338.06  5062.4  338.31  5077.1     340  5112.8  342.11
  5133.4  342.05  5240.6  345.55  5341.3  350.74  5370.8  352.91  5434.7  355.09
#Mann= 8 ,-1 , 0
  4473.1     .07       0  4505.7     .12       0  4513.8     .07       0
  4888.2     .12       0    4983      .1       0  4994.6     .05       0
  5000.4      .1       0  5133.4     .12       0
Bank Sta=4994.6,5000.4
XS Rating Curve= 0 ,0
Exp/Cntr=0.3,0.1

Type RM Length L Ch R = 1 ,26726   ,429,429,429
BEGIN DESCRIPTION:
Stream0648 44.0
END DESCRIPTION:
XS GIS Cut Line= 3
      2389725.03     13615775.02        2389925.       13615925.
        2390725.       13616325.
#Sta/Elev= 30
  4746.4  351.02  4804.7  347.52  4839.1  345.71  4859.9  343.74  4882.8  342.99
  4889.1   342.1  4918.2  341.43  4970.6   338.8  4993.2  337.41  5010.3  337.84
  5018.7  334.86  5024.2  334.11  5024.7  333.61  5029.6  333.61    5030  334.11
  5041.1  337.89  5058.3  337.78  5130.5  336.04  5161.3  337.94  5166.9  337.61
  5197.6  338.89  5275.1  339.74  5279.6   339.8  5447.4  343.83  5524.6  347.03
  5675.6  354.61  5681.2  355.52  5744.1  358.13  5837.7  362.52  5890.8  364.19
#Mann= 11 ,-1 , 0
  4746.4     .07       0  4804.7     .12       0  4970.6     .07       0
  5018.7     .12       0  5024.2     .05       0    5030     .12       0
  5058.3      .1       0  5275.1     .12       0  5279.6     .07       0
  5447.4     .12       0  5744.1     .07       0
Bank Sta=5024.2,5030
XS Rating Curve= 0 ,0
Exp/Cntr=0.3,0.1

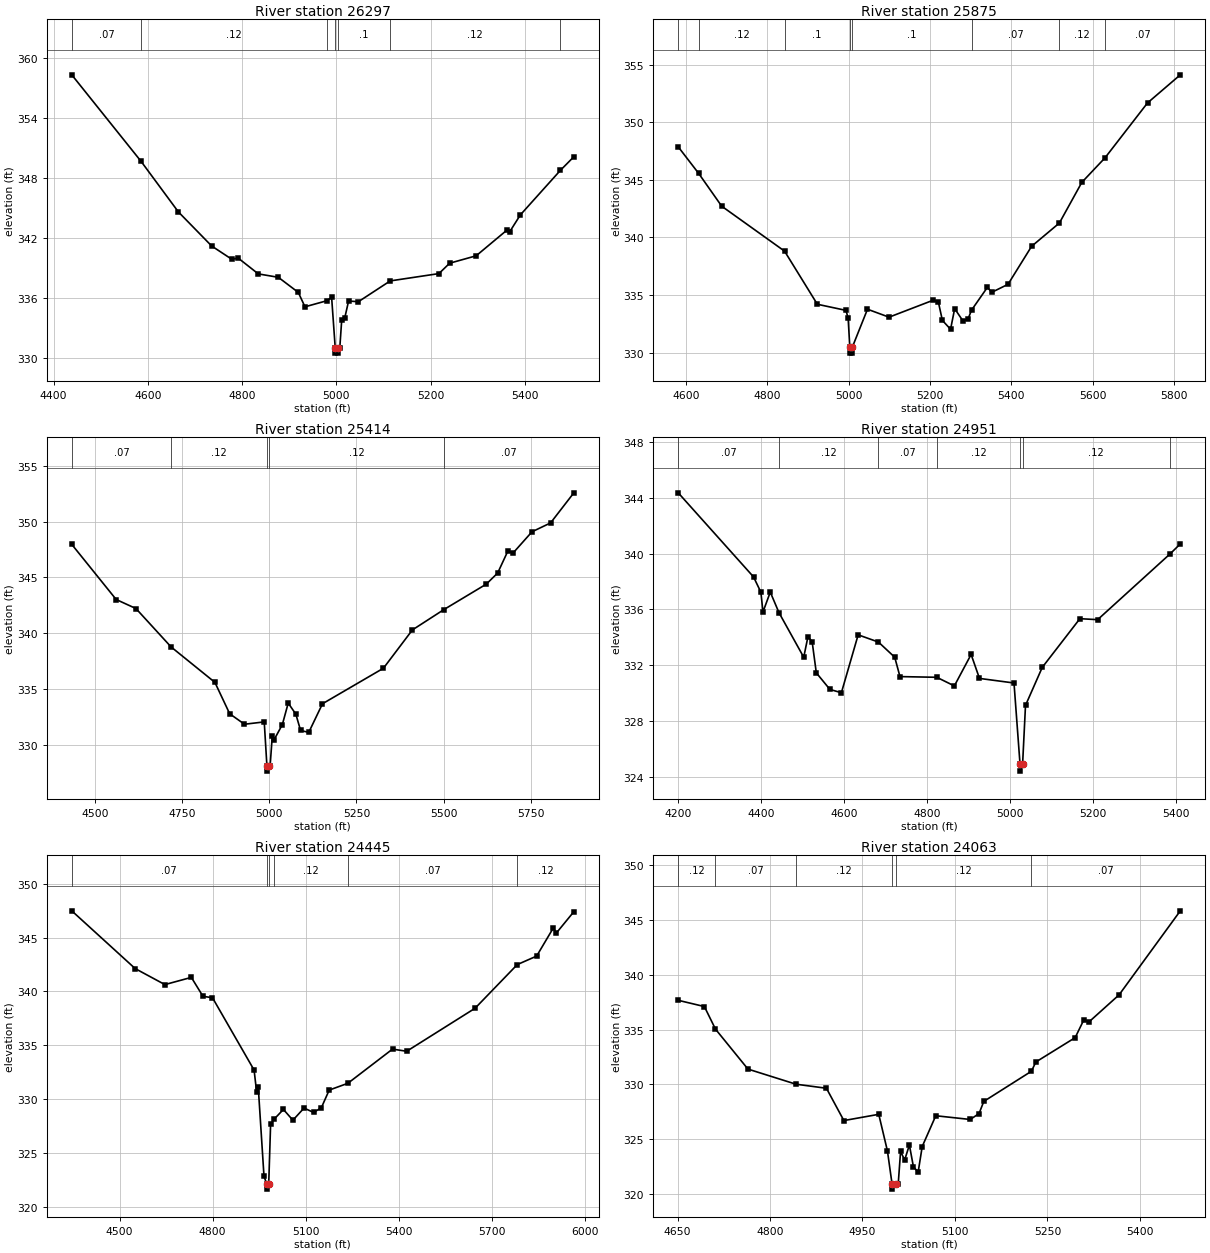
Type RM Length L Ch R = 1 ,26297   ,422,422,422
BEGIN DESCRIPTION:
Stream0648 43.0
END DESCRIPTION:
XS GIS Cut Line= 3
      2389475.03     13615825.03        2389875.       13616225.
      2390274.97     13616524.98
#Sta/Elev= 30
  4438.6  358.34  4585.7  349.69  4664.8  344.64  4735.5  341.23    4778  339.91
  4792.1  340.01  4834.5  338.44    4877   338.1  4919.4  336.59  4933.5  335.15
  4980.2  335.76  4990.1   336.1  4997.8  331.02  4998.3  330.52  5003.2  330.52
  5003.7  331.02  5007.4  331.02  5011.5  333.82  5017.8     334  5026.1  335.73
  5046.9  335.66  5114.5  337.74  5217.8  338.47  5240.7  339.51  5296.9  340.25
  5361.5  342.79  5367.8  342.63  5390.7  344.34  5475.8   348.8  5504.2  350.15
#Mann= 7 ,-1 , 0
  4438.6     .07       0  4585.7     .12       0  4980.2      .1       0
  4997.8     .05       0  5003.7      .1       0  5114.5     .12       0
  5475.8     .07       0
Bank Sta=4997.8,5003.7
XS Rating Curve= 0 ,0
Exp/Cntr=0.3,0.1

Type RM Length L Ch R = 1 ,25875   ,461,461,461
BEGIN DESCRIPTION:
Stream0648 42.0
END DESCRIPTION:
XS GIS Cut Line= 3
      2389425.02     13616075.04        2389575.       13616475.
      2390375.02       13616575.
#Sta/Elev= 30
  4581.5  347.86  4631.6  345.56  4688.3  342.71  4842.7  338.81  4923.2   334.2
  4993.5  333.67  4998.9     333    5003  330.46  5003.5  329.96  5008.5  329.96
    5009  330.46  5046.4  333.77  5099.4  333.08  5207.7  334.55  5220.3  334.43
  5230.4   332.8  5250.5  332.03  5260.6  333.82  5280.8  332.76  5293.4  332.92
    5302  333.69  5341.2  335.68  5351.3  335.23  5391.6  335.93  5449.6  339.23
  5517.8  341.25    5573  344.78    5630  346.91  5734.3  351.67  5814.9  354.11
#Mann= 8 ,-1 , 0
  4581.5     .07       0  4631.6     .12       0  4842.7      .1       0
    5003     .05       0    5009      .1       0    5302     .07       0
  5517.8     .12       0    5630     .07       0
Bank Sta=5003,5009
XS Rating Curve= 0 ,0
Exp/Cntr=0.3,0.1

Type RM Length L Ch R = 1 ,25414   ,463,463,463
BEGIN DESCRIPTION:
Stream0648 41.0
END DESCRIPTION:
XS GIS Cut Line= 3
      2388974.97     13616374.97        2389375.       13616775.
      2390174.96     13617124.98
#Sta/Elev= 30
  4434.2  347.97  4561.5  343.02  4618.1  342.21  4718.9  338.76  4844.4  335.58
  4886.8  332.76  4929.2  331.82  4985.8  332.03  4993.4  328.11  4993.9  327.61
  4999.4  328.11  5002.7  328.11  5008.9  330.79  5014.4  330.45  5037.7  331.79
  5054.5  333.72  5076.3  332.73    5090  331.26  5113.4  331.09  5152.7  333.66
  5327.4  336.85  5410.4  340.29  5500.9  342.12  5622.1   344.4  5654.8   345.4
  5684.1  347.38  5698.5  347.18  5753.1   349.1  5806.5   349.9  5873.1   352.6
#Mann= 5 ,-1 , 0
  4434.2     .07       0  4718.9     .12       0  4993.4     .05       0
  4999.4     .12       0  5500.9     .07       0
Bank Sta=4993.4,4999.4
XS Rating Curve= 0 ,0
Exp/Cntr=0.3,0.1

Type RM Length L Ch R = 1 ,24951   ,506,506,506
BEGIN DESCRIPTION:
Stream0648 40.0
END DESCRIPTION:
XS GIS Cut Line= 3
      2388574.99       13616975.        2389375.       13617075.
      2389775.05     13617024.99
#Sta/Elev= 30
  4201.1  344.38  4382.5  338.34  4400.2  337.24  4405.2  335.82  4422.8  337.25
  4443.8  335.77  4503.4  332.57  4513.5  334.04  4523.6   333.7  4533.7  331.45
  4566.4  330.26  4594.1  330.02  4634.5  334.18  4683.4  333.66  4722.6  332.57
  4735.2  331.18  4823.9  331.13  4866.2  330.51  4906.6  332.77  4926.7  331.05
  5009.9  330.72  5024.4  324.89  5024.9  324.39  5030.6  324.89  5037.6  329.11
  5077.9  331.84  5168.6  335.34  5211.4  335.27  5385.7  339.99  5410.5  340.71
#Mann= 7 ,-1 , 0
  4201.1     .07       0  4443.8     .12       0  4683.4     .07       0
  4823.9     .12       0  5024.4     .05       0  5030.6     .12       0
  5385.7     .07       0
Bank Sta=5024.4,5030.6
XS Rating Curve= 0 ,0
Exp/Cntr=0.3,0.1

Type RM Length L Ch R = 1 ,24445   ,382,382,382
BEGIN DESCRIPTION:
Stream0648 39.0
END DESCRIPTION:
XS GIS Cut Line= 3
      2388413.12     13617105.16      2389258.82     13617413.41
      2389938.58     13617642.63
#Sta/Elev= 30
  4346.1   347.5  4550.3  342.13  4646.1  340.64  4731.3  341.31  4768.8  339.55
  4799.4  339.42  4933.5  332.69  4941.5  330.69  4946.9   331.1  4965.4   322.8
  4974.2  322.12  4974.7  321.62  4980.6  322.12  4986.7  327.67  4998.8  328.15
  5027.9  329.03  5058.5  328.03  5094.4  329.16  5125.1  328.75  5150.2  329.19
  5175.4  330.83  5235.5  331.46  5379.4  334.64  5425.1  334.44  5645.4  338.44
  5781.3   342.5  5843.7  343.29  5897.3   345.9  5907.1  345.43  5963.6  347.42
#Mann= 6 ,-1 , 0
  4346.1     .07       0  4974.2     .05       0  4980.6     .07       0
  4998.8     .12       0  5235.5     .07       0  5781.3     .12       0
Bank Sta=4974.2,4980.6
XS Rating Curve= 0 ,0
Exp/Cntr=0.3,0.1

Type RM Length L Ch R = 1 ,24063   ,478,478,478
BEGIN DESCRIPTION:
Stream0648 38.0
END DESCRIPTION:
XS GIS Cut Line= 3
        2388775.       13617425.        2389025.       13617675.
      2389374.97     13617974.98
#Sta/Elev= 30
  4651.1  337.68  4693.5  337.11  4711.5  335.05  4764.2   331.4  4842.1  330.02
  4891.5  329.65  4919.8   326.7  4976.4  327.27  4990.5  323.92  4997.9  320.94
  4998.4  320.44  5004.4  320.94    5008  320.94  5011.8  323.88  5018.4   323.1
  5026.1  324.47  5032.6  322.49  5040.3  321.99  5046.9  324.33  5068.9  327.14
  5124.8   326.8  5139.1  327.34  5146.8  328.45    5224   331.2  5231.3  332.05
    5295  334.27  5309.2  335.91  5316.9  335.68  5366.3  338.18  5465.6  345.85
#Mann= 6 ,-1 , 0
  4651.1     .12       0  4711.5     .07       0  4842.1     .12       0
  4997.9     .05       0  5004.4     .12       0    5224     .07       0
Bank Sta=4997.9,5004.4
XS Rating Curve= 0 ,0
Exp/Cntr=0.3,0.1