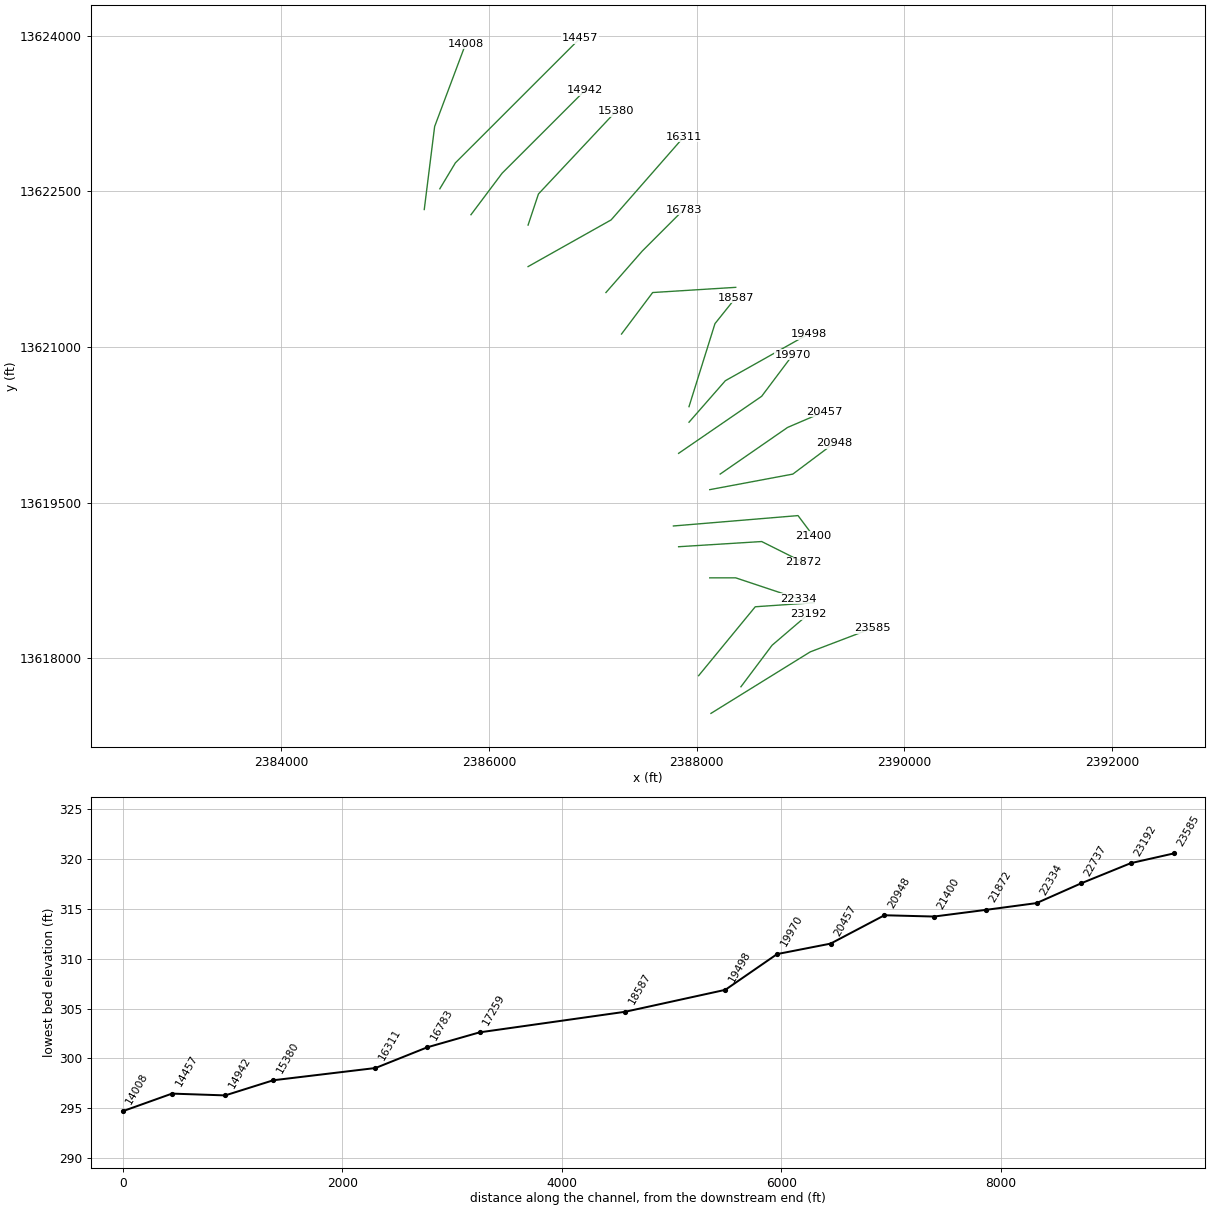
HEC-RAS study Stream0648.prj: Stream0648 Base Level Engineering

--- Stream0648.g01 (geometry) --- (continued)

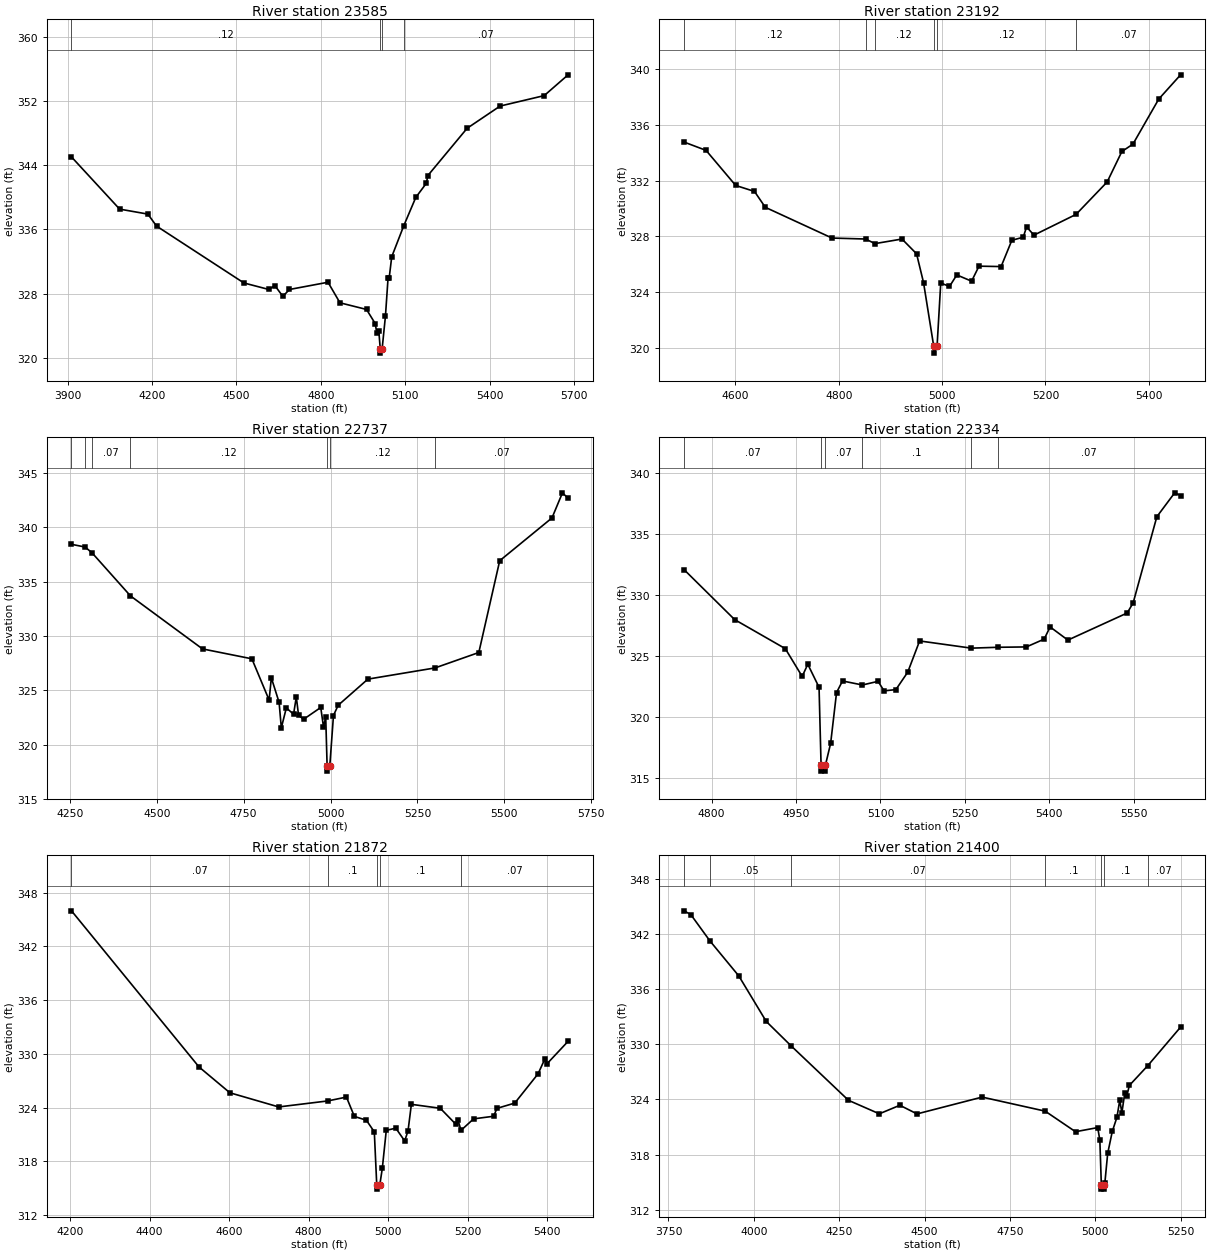
Type RM Length L Ch R = 1 ,23585   ,393,393,393
BEGIN DESCRIPTION:
Stream0648 37.0
END DESCRIPTION:
XS GIS Cut Line= 3
      2388136.43     13617468.72      2389092.83     13618061.54
      2389690.75     13618289.69
#Sta/Elev= 30
  3913.7  345.02  4084.8  338.52  4185.2   337.9  4215.9  336.41  4526.6  329.32
  4615.2  328.51  4636.5     329    4665  327.65  4688.5  328.51  4825.5  329.41
    4868  326.85  4962.5  326.02  4993.3  324.26  4999.2  323.04  5006.2  323.29
  5011.3  321.08  5011.8  320.58  5017.8  321.08  5029.7   325.2  5038.9   329.9
  5042.8   329.9    5052  332.58  5094.6  336.43  5137.6  339.98    5175  341.74
  5180.4   342.7    5320  348.59  5437.3  351.36    5594  352.66  5678.9  355.25
#Mann= 4 ,-1 , 0
  3913.7     .12       0  5011.3     .05       0  5017.8     .12       0
  5094.6     .07       0
Bank Sta=5011.3,5017.8
XS Rating Curve= 0 ,0
Exp/Cntr=0.3,0.1

Type RM Length L Ch R = 1 ,23192   ,455,455,455
BEGIN DESCRIPTION:
Stream0648 36.0
END DESCRIPTION:
XS GIS Cut Line= 3
      2388425.02     13617725.03        2388725.       13618125.
      2389074.97     13618424.97
#Sta/Elev= 30
  4500.6  334.77  4543.3  334.17  4600.6  331.65    4637  331.22  4657.9  330.08
    4787  327.87  4851.9   327.8  4870.1  327.47  4922.4   327.8  4950.6  326.74
  4964.1  324.67  4983.8   320.1  4984.3   319.6  4990.3   320.1  4997.4  324.64
  5014.3  324.39  5028.5  325.22  5057.1  324.77  5071.4  325.85  5114.2  325.82
    5135  327.71    5157  327.93  5163.5  328.67  5177.8  328.08  5259.2  329.57
  5319.4   331.9  5347.9  334.09  5369.3  334.62  5419.3  337.86  5461.5   339.6
#Mann= 6 ,-1 , 0
  4500.6     .12       0  4851.9     .07       0  4870.1     .12       0
  4983.8     .05       0  4990.3     .12       0  5259.2     .07       0
Bank Sta=4983.8,4990.3
XS Rating Curve= 0 ,0
Exp/Cntr=0.3,0.1

Type RM Length L Ch R = 1 ,22737   ,403,403,403
BEGIN DESCRIPTION:
XS7390
END DESCRIPTION:
XS GIS Cut Line= 3
      2388017.89     13617832.31      2388563.27     13618496.26
      2389131.18     13618535.69
#Sta/Elev= 30
  4254.9  338.44    4294  338.19  4313.9  337.66  4424.6  333.69  4631.8  328.81
  4773.8   327.9  4823.4   324.1  4829.8  326.15  4852.1  323.89  4858.5  321.54
  4872.9  323.38  4893.7   322.8  4901.6  324.38    4908  322.72  4922.4  322.33
  4971.9  323.42  4979.8  321.63  4986.2  322.54  4990.2  318.06  4990.7  317.56
    4998  318.06  5008.5  322.68  5021.9  323.62  5107.5  326.03  5300.5  327.06
  5426.6  328.48  5486.7  336.93  5637.1  340.87  5667.2  343.18  5683.4  342.68
#Mann= 7 ,-1 , 0
  4254.9     .07       0    4294     .12       0  4313.9     .07       0
  4424.6     .12       0  4990.2     .05       0    4998     .12       0
  5300.5     .07       0
Bank Sta=4990.2,4998
XS Rating Curve= 0 ,0
Exp/Cntr=0.3,0.1

Type RM Length L Ch R = 1 ,22334   ,462,462,462
BEGIN DESCRIPTION:
Stream0648 35.0
END DESCRIPTION:
XS GIS Cut Line= 3
      2388124.96       13618775.        2388375.       13618775.
        2388975.       13618575.
#Sta/Elev= 30
  4750.8  332.11  4840.8  328.01  4930.8  325.63  4960.8  323.35  4970.8  324.35
  4990.8  322.46  4994.4  316.09  4994.9  315.59  5001.7  315.59  5002.2  316.09
  5011.4  317.87  5021.9  322.03  5032.5  322.98  5067.8  322.65  5095.7  322.95
  5106.3  322.17  5127.3  322.27  5148.4   323.7  5169.5  326.26  5261.3  325.67
  5308.3  325.74  5359.2  325.77  5390.9  326.41  5401.4  327.41    5433  326.33
  5538.4  328.55    5549  329.38  5591.1  336.44  5622.8   338.4  5633.3  338.18
#Mann= 6 ,-1 , 0
  4750.8     .07       0  4994.4     .05       0  5002.2     .07       0
  5067.8      .1       0  5261.3     .12       0  5308.3     .07       0
Bank Sta=4994.4,5002.2
XS Rating Curve= 0 ,0
Exp/Cntr=0.3,0.1

Type RM Length L Ch R = 1 ,21872   ,472,472,472
BEGIN DESCRIPTION:
Stream0648 34.0
END DESCRIPTION:
XS GIS Cut Line= 3
      2387824.95       13619075.        2388625.       13619125.
      2389024.98     13618925.01
#Sta/Elev= 30
  4203.6  345.96  4524.3  328.54  4601.9  325.66  4724.7  324.08  4848.1  324.75
    4895  325.18    4915  323.02  4945.1   322.6  4965.1   321.3  4971.2  315.41
  4971.7  314.91    4979  315.41  4985.2  317.22  4995.2  321.47  5019.2  321.71
  5041.5  320.29  5049.9  321.41  5058.3  324.37    5131  323.93  5170.1  322.15
  5175.7  322.57  5183.2  321.47  5214.8  322.75  5265.1  323.04  5273.5  323.92
  5318.3  324.51    5377  327.78  5393.7  329.41  5399.3  328.89  5452.4   331.4
#Mann= 5 ,-1 , 0
  4203.6     .07       0  4848.1      .1       0  4971.2     .05       0
    4979      .1       0  5183.2     .07       0
Bank Sta=4971.2,4979
XS Rating Curve= 0 ,0
Exp/Cntr=0.3,0.1

Type RM Length L Ch R = 1 ,21400   ,452,452,452
BEGIN DESCRIPTION:
Stream0648 33.0
END DESCRIPTION:
XS GIS Cut Line= 3
      2387775.04       13619275.        2388975.       13619375.
      2389124.99     13619175.02
#Sta/Elev= 30
  3795.4  344.54  3815.4  344.13  3871.2  341.27  3955.9  337.45  4036.2   332.5
    4109  329.84    4277  323.91  4367.3  322.44  4427.5  323.37  4477.7  322.43
  4668.4  324.26    4853  322.73  4941.8  320.49  5006.8  320.94  5013.1  319.57
  5017.4  314.74  5017.9  314.24  5024.8  314.24  5025.3  314.74  5027.6  314.86
    5036  318.12  5049.5  320.52  5063.1  322.06  5071.4  323.92  5077.6  322.55
    5086   324.7  5092.2  324.42  5099.5  325.53  5153.6  327.69  5249.5  331.88
#Mann= 7 ,-1 , 0
  3795.4     .07       0  3871.2     .05       0    4109     .07       0
    4853      .1       0  5017.4     .05       0  5025.3      .1       0
  5153.6     .07       0
Bank Sta=5017.4,5025.3
XS Rating Curve= 0 ,0
Exp/Cntr=0.3,0.1

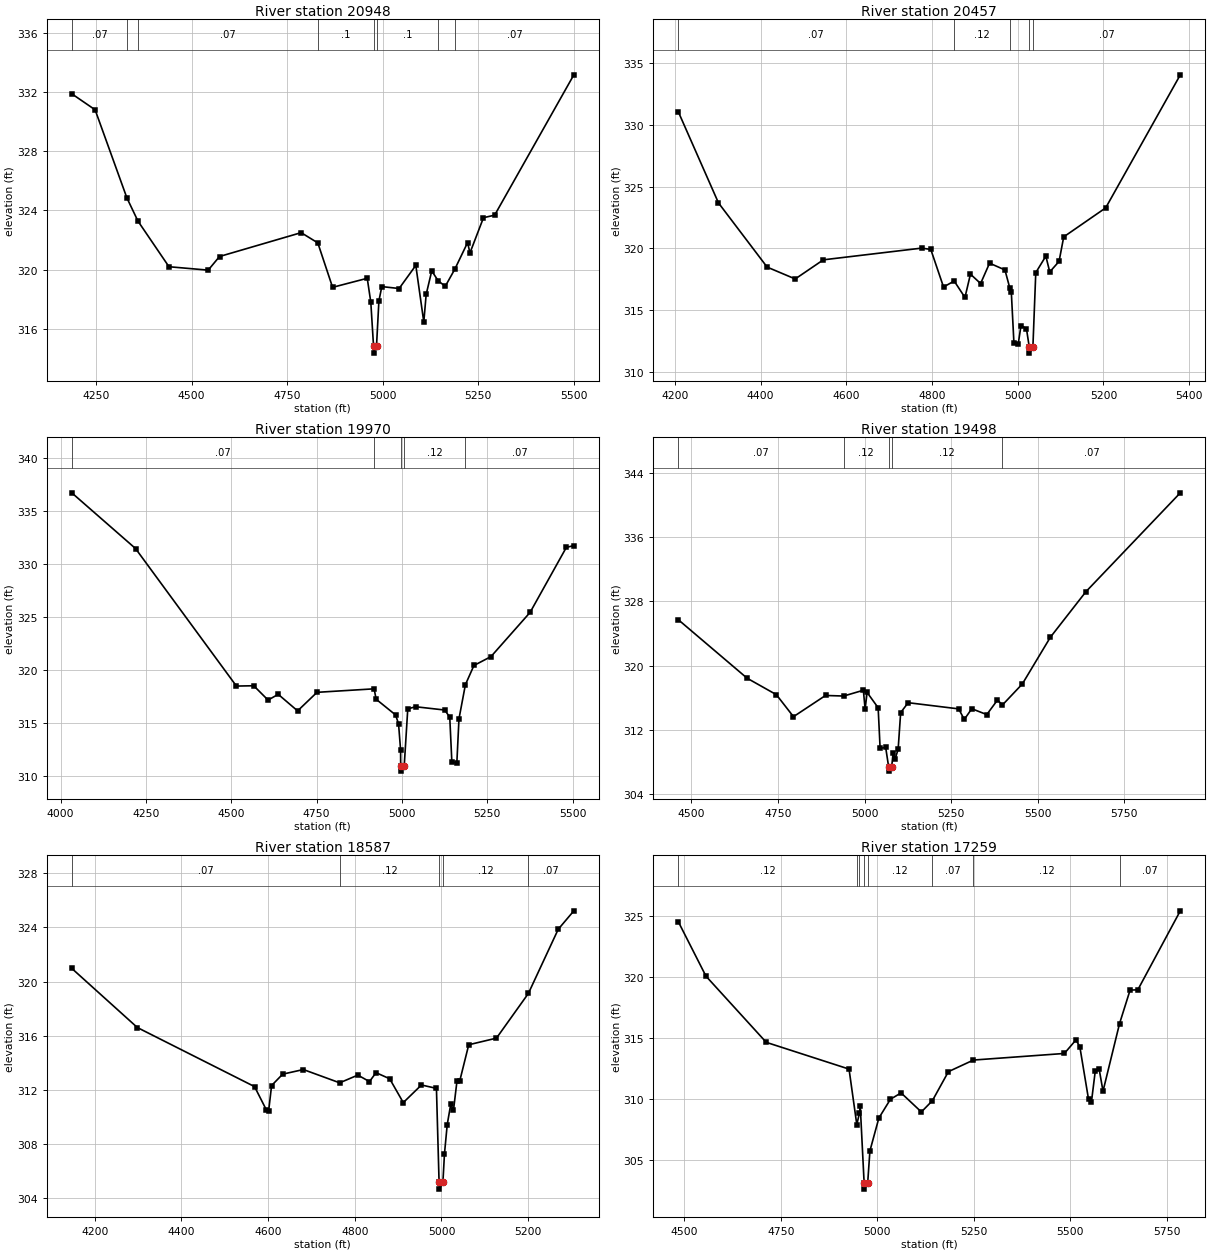
Type RM Length L Ch R = 1 ,20948   ,491,491,491
BEGIN DESCRIPTION:
Stream0648 32.0
END DESCRIPTION:
XS GIS Cut Line= 3
      2388124.95     13619624.99        2388925.       13619775.
      2389325.01     13620075.01
#Sta/Elev= 30
  4186.4  331.87  4247.5  330.79  4330.6  324.85  4359.6  323.28  4440.8   320.2
  4543.4  319.97  4573.1  320.89  4786.7   322.5  4830.3  321.81    4869  318.81
  4959.7  319.42    4969  317.81  4976.1  314.87  4976.6  314.37    4984  314.87
  4990.2  317.89  4997.8  318.86  5043.1  318.73  5086.8  320.29  5107.7  316.47
  5113.9  318.33  5128.5  319.92  5145.3  319.25  5163.9  318.88    5189  320.04
  5222.3  321.83  5228.5  321.13  5263.9  323.51  5293.1  323.68  5500.4  333.15
#Mann= 8 ,-1 , 0
  4186.4     .07       0  4330.6     .05       0  4359.6     .07       0
  4830.3      .1       0  4976.1     .05       0    4984      .1       0
  5145.3     .12       0    5189     .07       0
Bank Sta=4976.1,4984
XS Rating Curve= 0 ,0
Exp/Cntr=0.3,0.1

Type RM Length L Ch R = 1 ,20457   ,487,487,487
BEGIN DESCRIPTION:
Stream0648 31.0
END DESCRIPTION:
XS GIS Cut Line= 3
      2388225.03     13619775.02        2388875.       13620225.
      2389224.98     13620374.99
#Sta/Elev= 30
  4207.9  331.09  4301.8  323.69  4415.3  318.49  4480.8  317.53  4546.4  319.08
  4776.1  320.03  4797.1  319.92  4826.8  316.88  4851.7  317.36  4876.8  316.03
  4889.6  317.92  4913.3  317.16  4934.2  318.81  4970.1  318.26  4981.5  316.78
  4984.9  316.49    4991  312.37  5001.2  312.29  5007.5  313.75  5020.2  313.51
  5026.8  312.02  5027.3  311.52  5035.3  312.02    5042  318.04  5065.5  319.38
  5074.6   318.1  5096.3  318.95  5107.2  320.94  5205.1  323.29  5379.2  334.07
#Mann= 5 ,-1 , 0
  4207.9     .07       0  4851.7     .12       0  4981.5     .07       0
  5026.8     .05       0  5035.3     .07       0
Bank Sta=5026.8,5035.3
XS Rating Curve= 0 ,0
Exp/Cntr=0.3,0.1

Type RM Length L Ch R = 1 ,19970   ,472,472,472
BEGIN DESCRIPTION:
Stream0648 30.0
END DESCRIPTION:
XS GIS Cut Line= 3
      2387825.02     13619975.02        2388625.       13620525.
        2388925.       13620925.
#Sta/Elev= 30
    4033  336.71  4219.7  331.46  4515.3  318.49  4566.1  318.52    4608  317.17
  4637.8  317.71  4694.6  316.15  4751.4   317.9  4918.7  318.23  4924.6  317.25
  4981.5  315.77  4990.3  314.93  4996.3  312.44  4996.5  310.97    4997  310.47
    5005  310.97  5006.9  310.97  5017.3  316.34  5040.3  316.54  5125.7  316.23
  5140.3  315.55  5146.5   311.3  5161.1  311.28  5167.3   315.4  5186.1  318.62
  5211.1  320.43  5261.1  321.27  5375.7  325.44  5481.9  331.57  5503.8  331.73
#Mann= 5 ,-1 , 0
    4033     .07       0  4918.7     .12       0  4996.5     .05       0
    5005     .12       0  5186.1     .07       0
Bank Sta=4996.5,5005
XS Rating Curve= 0 ,0
Exp/Cntr=0.3,0.1

Type RM Length L Ch R = 1 ,19498   ,911,911,911
BEGIN DESCRIPTION:
Stream0648 29.0
END DESCRIPTION:
XS GIS Cut Line= 3
        2387925.       13620275.        2388275.       13620675.
      2389075.01       13621125.
#Sta/Elev= 30
    4462  325.74  4660.8  318.45  4745.3   316.4  4794.7  313.66  4887.2   316.3
  4939.7  316.23  4996.4  316.95  5001.5   314.6  5007.2  316.68  5039.1  314.77
  5044.8  309.71  5060.8  309.84  5069.5  307.38    5070  306.88  5078.2  307.38
  5082.4  309.19  5088.2  308.42  5096.8  309.59  5104.1  314.17  5125.8   315.4
  5271.7  314.63  5287.7  313.31  5309.4  314.65  5352.7  313.92  5383.6  315.73
    5398  315.12  5455.3  317.73  5536.3  323.55  5638.9  329.22  5911.4  341.53
#Mann= 5 ,-1 , 0
    4462     .07       0  4939.7     .12       0  5069.5     .05       0
  5078.2     .12       0    5398     .07       0
Bank Sta=5069.5,5078.2
XS Rating Curve= 0 ,0
Exp/Cntr=0.3,0.1

Type RM Length L Ch R = 1 ,18587   ,1328,1328,1328
BEGIN DESCRIPTION:
Stream0648 28.0
END DESCRIPTION:
XS GIS Cut Line= 3
        2387925.     13620425.01        2388175.       13621225.
        2388375.       13621475.
#Sta/Elev= 30
  4147.1  320.98  4298.5  316.61  4568.8  312.25    4596  310.53  4601.3  310.46
  4608.1  312.33  4633.7  313.17  4681.4  313.51  4765.2  312.53  4807.1   313.1
  4833.9  312.62    4849  313.28  4880.5  312.83  4911.9  311.07  4953.8  312.37
  4988.4  312.12  4994.5  305.18    4995  304.68  5003.3  305.18  5006.9  307.28
  5013.3  309.45  5021.3  310.93  5027.7   310.5  5035.7  312.64  5042.1  312.66
  5062.9  315.34  5126.9  315.83  5200.5  319.13  5269.4  323.87  5305.4  325.23
#Mann= 5 ,-1 , 0
  4147.1     .07       0  4765.2     .12       0  4994.5     .05       0
  5003.3     .12       0  5200.5     .07       0
Bank Sta=4994.5,5003.3
XS Rating Curve= 0 ,0
Exp/Cntr=0.3,0.1

Type RM Length L Ch R = 1 ,17259   ,476,476,476
BEGIN DESCRIPTION:
Stream0648 27.0
END DESCRIPTION:
XS GIS Cut Line= 3
      2387274.97     13621124.96        2387575.       13621525.
      2388374.99       13621575.
#Sta/Elev= 30
  4484.2  324.52  4556.1  320.05  4712.4  314.63    4927  312.44  4947.1   307.9
  4954.1  308.85  4956.1  309.41  4966.1  303.11  4966.6  302.61  4975.3  303.11
  4981.1  305.74  5004.3  308.43  5034.3  309.97  5061.9  310.49  5114.5  308.93
    5143  309.85  5184.6  312.23  5249.5  313.18  5485.2  313.72  5515.3  314.83
  5525.3  314.27  5547.8  309.98  5555.4  309.75  5565.4   312.3  5575.4  312.44
  5585.4  310.63  5628.3  316.17  5655.6  318.91  5675.6  318.93  5785.8   325.4
#Mann= 8 ,-1 , 0
  4484.2     .12       0  4947.1     .07       0  4954.1     .12       0
  4966.1     .05       0  4975.3     .12       0    5143     .07       0
  5249.5     .12       0  5628.3     .07       0
Bank Sta=4966.1,4975.3
XS Rating Curve= 0 ,0
Exp/Cntr=0.3,0.1

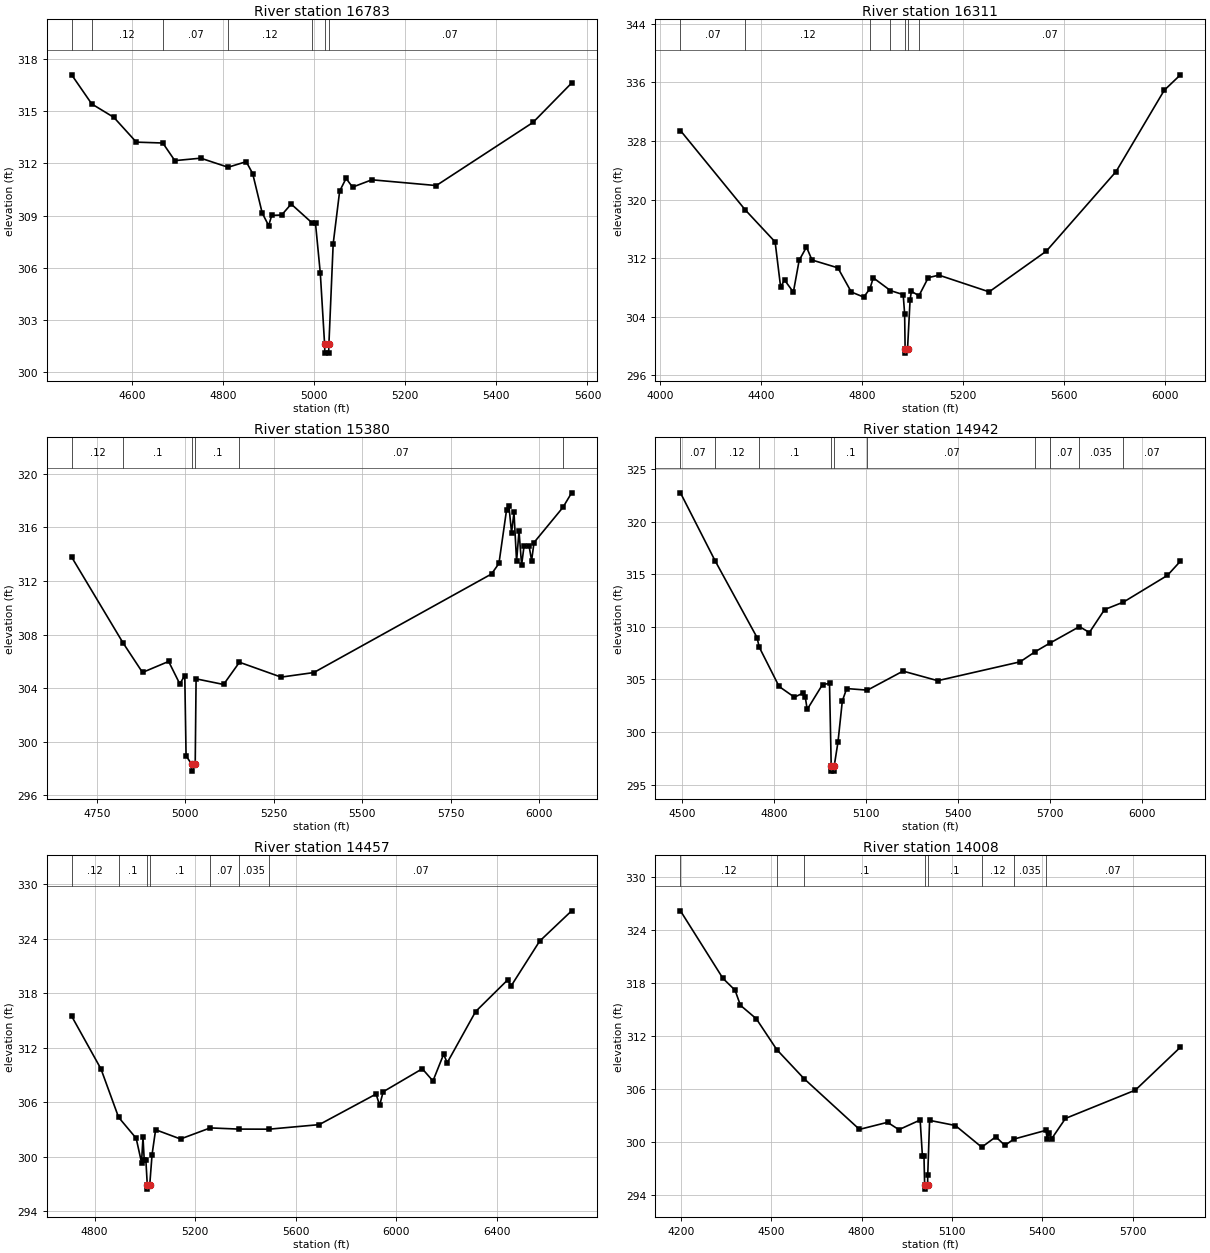
Type RM Length L Ch R = 1 ,16783   ,472,472,472
BEGIN DESCRIPTION:
Stream0648 26.0
END DESCRIPTION:
XS GIS Cut Line= 3
      2387124.99     13621524.99        2387475.       13621925.
        2387875.       13622325.
#Sta/Elev= 30
    4468  317.07  4512.1   315.4  4560.6  314.63  4609.9  313.21    4668  313.16
  4694.4  312.15  4751.3  312.29  4811.3  311.77    4851  312.09  4865.2  311.41
  4886.1  309.15  4900.3  308.42    4907  309.01  4928.8  309.03  4949.7  309.66
  4995.5  308.58  5003.1  308.55  5013.7  305.68  5023.1  301.61  5023.6  301.11
    5032  301.11  5032.5  301.61  5041.9  307.38  5056.1   310.4  5070.2  311.13
  5084.4  310.63  5126.8  311.05  5268.2  310.72  5480.4  314.34  5565.2   316.6
#Mann= 7 ,-1 , 0
    4468     .07       0  4512.1     .12       0    4668     .07       0
  4811.3     .12       0  4995.5     .07       0  5023.1     .05       0
  5032.5     .07       0
Bank Sta=5023.1,5032.5
XS Rating Curve= 0 ,0
Exp/Cntr=0.3,0.1

Type RM Length L Ch R = 1 ,16311   ,931,931,931
BEGIN DESCRIPTION:
Stream0648 25.0
END DESCRIPTION:
XS GIS Cut Line= 3
      2386375.02     13621775.01        2387175.       13622225.
      2387875.02     13623025.03
#Sta/Elev= 30
  4081.9  329.43  4338.7  318.59    4457  314.22  4478.7  308.09  4494.6     309
  4529.3  307.36  4552.3  311.71  4581.3  313.52    4603  311.75  4705.6  310.68
  4758.8  307.38  4808.2  306.68  4832.9  307.85  4845.8  309.32  4914.1  307.57
  4964.4  307.02  4970.1  304.43  4972.1  299.53  4972.6  299.03  4981.5  299.53
  4991.8  306.33  4996.9  307.47  5026.9  306.87  5063.8  309.34  5106.1  309.68
  5304.9   307.4  5531.3  312.95  5807.9  323.83  5998.7  334.93  6062.8  337.04
#Mann= 7 ,-1 , 0
  4081.9     .07       0  4338.7     .12       0  4832.9      .1       0
  4914.1     .12       0  4972.1     .05       0  4981.5     .12       0
  5026.9     .07       0
Bank Sta=4972.1,4981.5
XS Rating Curve= 0 ,0
Exp/Cntr=0.3,0.1

Type RM Length L Ch R = 1 ,15380   ,438,438,438
BEGIN DESCRIPTION:
Stream0648 24.0
END DESCRIPTION:
XS GIS Cut Line= 3
      2386375.01     13622175.04        2386475.       13622475.
      2387225.02     13623275.02
#Sta/Elev= 30
  4679.2  313.78  4824.5  307.37  4879.4  305.17  4953.2  305.99  4984.8  304.31
  4998.8  304.94  5002.5  298.94  5018.7   298.3  5019.2   297.8  5028.3   298.3
  5030.8  304.69  5108.5  304.27  5153.3  305.93  5271.1  304.82  5363.4  305.16
  5865.6  312.52  5886.6  313.31  5908.1  317.31  5914.9  317.56  5922.2  315.61
  5929.1  317.12  5936.4  313.46  5943.3  315.74  5950.6  313.19  5957.4  314.58
  5971.6  314.62  5978.9  313.52  5985.7  314.87  6067.3  317.49    6092  318.58
#Mann= 6 ,-1 , 0
  4679.2     .12       0  4824.5      .1       0  5018.7     .05       0
  5028.3      .1       0  5153.3     .07       0  6067.3    .035       0
Bank Sta=5018.7,5028.3
XS Rating Curve= 0 ,0
Exp/Cntr=0.3,0.1

Type RM Length L Ch R = 1 ,14942   ,485,485,485
BEGIN DESCRIPTION:
Stream0648 23.0
END DESCRIPTION:
XS GIS Cut Line= 3
      2385825.02     13622275.03        2386125.       13622675.
      2386924.98     13623474.98
#Sta/Elev= 30
  4495.4  322.74  4608.1   316.3  4745.4  308.98  4752.1  308.09  4817.2  304.33
  4867.2  303.31  4895.4   303.7  4902.7  303.33  4908.9  302.14  4958.9  304.51
  4981.8  304.62  4987.3  296.78  4987.8  296.28  4996.7  296.28  4997.2  296.78
  5009.5  299.07  5023.6  302.95  5037.8  304.13  5105.5  303.98  5221.6  305.79
  5334.8  304.88  5603.5  306.67  5653.7  307.65  5699.6  308.43  5797.2  310.02
  5829.7  309.46  5879.2  311.64  5940.7  312.35  6084.3  314.89  6126.7  316.24
#Mann= 10 ,-1 , 0
  4495.4     .07       0  4608.1     .12       0  4752.1      .1       0
  4987.3     .05       0  4997.2      .1       0  5105.5     .07       0
  5653.7    .035       0  5699.6     .07       0  5797.2    .035       0
  5940.7     .07       0
Bank Sta=4987.3,4997.2
XS Rating Curve= 0 ,0
Exp/Cntr=0.3,0.1

Type RM Length L Ch R = 1 ,14457   ,449,449,449
BEGIN DESCRIPTION:
Stream0648 22.0
END DESCRIPTION:
XS GIS Cut Line= 3
      2385525.01     13622525.02        2385675.       13622775.
      2386875.02     13623975.02
#Sta/Elev= 30
    4709   315.5  4825.6  309.69  4895.6  304.37  4965.5  302.06  4986.9  299.39
  4992.7  302.17  4997.6  299.68  5004.1  299.68  5009.7  296.96  5010.2  296.46
  5019.6  296.96  5028.8  300.27  5042.9     303  5141.9  301.98  5260.3   303.2
  5372.7  303.07  5494.2  303.06  5693.5  303.56  5919.8  306.93  5933.9  305.68
    5948  307.18  6103.6  309.71    6146  308.37  6188.5  311.31  6202.6  310.37
  6315.7  316.01    6443  319.49  6457.2  318.84  6570.3  323.76  6697.6   327.1
#Mann= 7 ,-1 , 0
    4709     .12       0  4895.6      .1       0  5009.7     .05       0
  5019.6      .1       0  5260.3     .07       0  5372.7    .035       0
  5494.2     .07       0
Bank Sta=5009.7,5019.6
XS Rating Curve= 0 ,0
Exp/Cntr=0.3,0.1

Type RM Length L Ch R = 1 ,14008   ,661,661,661
BEGIN DESCRIPTION:
Stream0648 21.0
END DESCRIPTION:
XS GIS Cut Line= 3
        2385375.     13622324.96        2385475.       13623125.
      2385775.01     13623925.03
#Sta/Elev= 30
  4198.1  326.14  4339.2  318.51  4379.5  317.17  4397.2  315.47  4450.1  313.94
    4518  310.46  4608.5  307.18  4792.7  301.44  4885.9  302.24  4923.7  301.41
  4994.3   302.5  5001.8  298.45    5007  298.45  5009.2  295.19  5009.7  294.69
  5019.1  295.19  5019.5  296.27  5025.7  302.46  5111.2  301.88  5198.9  299.43
  5245.6   300.6  5275.8  299.63  5305.3  300.34  5411.7  301.33  5416.4  300.41
  5421.8     301  5431.6  300.41    5477  302.68  5709.2  305.88  5858.8  310.73
#Mann= 8 ,-1 , 0
  4198.1     .12       0    4518     .07       0  4608.5      .1       0
  5009.2     .05       0  5019.1      .1       0  5198.9     .12       0
  5305.3    .035       0  5411.7     .07       0
Bank Sta=5009.2,5019.1
XS Rating Curve= 0 ,0
Exp/Cntr=0.3,0.1