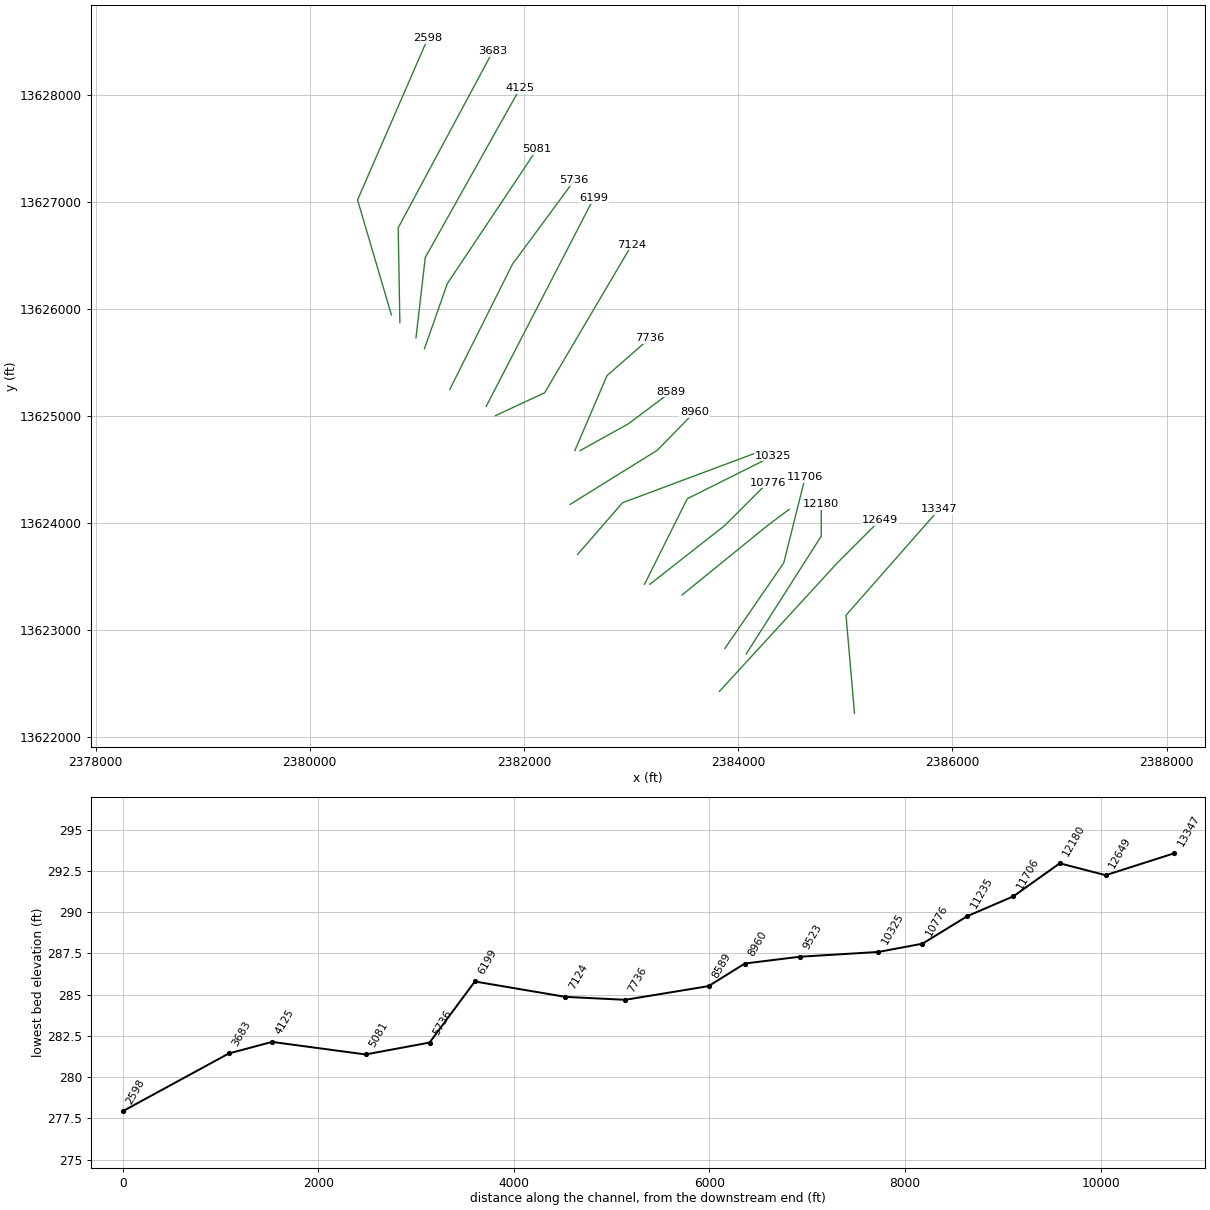
HEC-RAS study Stream0648.prj: Stream0648 Base Level Engineering

--- Stream0648.g01 (geometry) --- (continued)

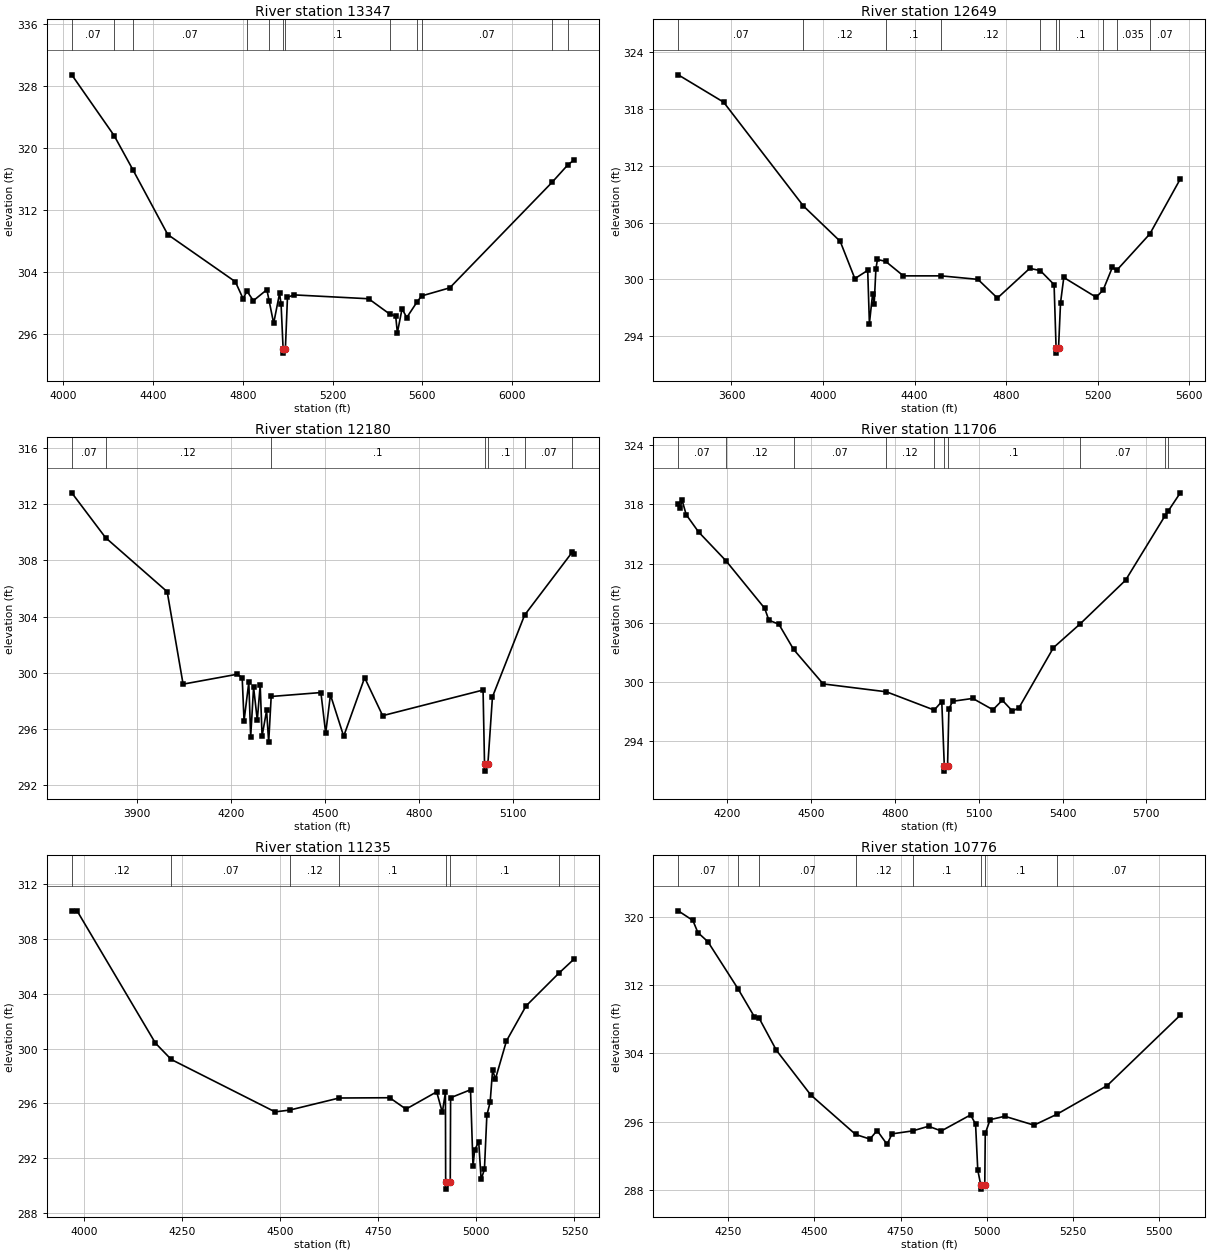
Type RM Length L Ch R = 1 ,13347   ,698,698,698
BEGIN DESCRIPTION:
Stream0648 20.0
END DESCRIPTION:
XS GIS Cut Line= 3
      2385085.51     13622219.06      2385006.47      13623135.9
      2385874.97     13624124.97
#Sta/Elev= 30
  4038.1  329.49  4226.9  321.64    4311   317.2  4465.6  308.87  4766.7  302.78
  4801.4  300.58  4818.3  301.57    4847  300.33  4907.2  301.75    4917  300.34
  4937.4  297.41  4963.7  301.27  4970.5  299.88  4979.6  294.06  4980.1  293.56
  4989.6  294.06  4998.9  300.76  5027.3  301.08  5360.4  300.58    5455  298.59
  5480.9  298.35  5488.5  296.19  5509.4  299.29  5530.2  298.15  5574.6   300.1
    5596  300.94  5721.9  301.99  6176.8  315.59  6247.3  317.85  6274.6  318.48
#Mann= 12 ,-1 , 0
  4038.1     .07       0  4226.9     .12       0    4311     .07       0
  4818.3     .12       0    4917      .1       0  4979.6     .05       0
  4989.6      .1       0    5455     .12       0  5574.6    .035       0
    5596     .07       0  6176.8    .035       0  6247.3     .07       0
Bank Sta=4979.6,4989.6
XS Rating Curve= 0 ,0
Exp/Cntr=0.3,0.1

Type RM Length L Ch R = 1 ,12649   ,469,469,469
BEGIN DESCRIPTION:
Stream0648 19.0
END DESCRIPTION:
XS GIS Cut Line= 3
      2383824.98     13622424.98        2384925.       13623625.
        2385325.       13624025.
#Sta/Elev= 30
  3367.5  321.56  3565.8  318.68  3914.4  307.74  4075.1  304.02  4139.2  300.09
  4195.3  300.96  4202.7  295.36  4216.9  298.52  4223.7  297.45  4231.1  301.11
  4237.9  302.11    4274   301.9  4351.3  300.38  4516.5  300.38  4676.9  300.01
    4762  298.04  4903.2  301.17  4949.1  300.94  5009.6  299.46  5018.4  292.74
  5018.9  292.24    5029  292.74  5037.8  297.55    5052  300.21  5193.4  298.13
  5223.8  298.88  5264.1  301.27  5282.7  300.95    5428   304.8  5561.1  310.59
#Mann= 10 ,-1 , 0
  3367.5     .07       0  3914.4     .12       0    4274      .1       0
  4516.5     .12       0  4949.1      .1       0  5018.4     .05       0
    5029      .1       0  5223.8     .12       0  5282.7    .035       0
    5428     .07       0
Bank Sta=5018.4,5029
XS Rating Curve= 0 ,0
Exp/Cntr=0.3,0.1

Type RM Length L Ch R = 1 ,12180   ,474,474,474
BEGIN DESCRIPTION:
Stream0648 18.0
END DESCRIPTION:
XS GIS Cut Line= 3
      2384075.01     13622775.02        2384775.       13623875.
        2384775.     13624174.99
#Sta/Elev= 30
  3691.5  312.83  3799.4  309.63  3996.3  305.77  4047.1  299.17  4220.6  299.88
  4235.9  299.62  4241.8  296.55    4257   299.3    4263  295.41  4272.3  298.95
  4284.1   296.6  4293.4   299.1  4299.4  295.45  4313.8  297.29  4320.5  295.02
  4328.5  298.29  4487.3  298.57  4502.6  295.67  4517.8  298.41  4560.1  295.45
    4627  299.63  4684.6  296.92  5005.3  298.75    5010  293.46  5010.5  292.96
  5020.7  293.46  5035.3  298.26    5138   304.1  5290.4   308.6  5295.3  308.45
#Mann= 7 ,-1 , 0
  3691.5     .07       0  3799.4     .12       0  4328.5      .1       0
    5010     .05       0  5020.7      .1       0    5138     .07       0
  5290.4    .035       0
Bank Sta=5010,5020.7
XS Rating Curve= 0 ,0
Exp/Cntr=0.3,0.1

Type RM Length L Ch R = 1 ,11706   ,471,471,471
BEGIN DESCRIPTION:
Stream0648 17.0
END DESCRIPTION:
XS GIS Cut Line= 3
        2383875.       13622825.        2384425.       13623625.
      2384624.99     13624424.96
#Sta/Elev= 30
  4025.8  318.04  4033.2  317.66  4039.3  318.45  4054.2  316.96  4098.6   315.2
  4196.2  312.29    4335  307.46  4349.9  306.26  4385.7  305.85  4438.3   303.3
    4544   299.8  4770.3     299  4941.1  297.15  4968.2  298.01  4977.3  291.46
  4977.8  290.96  4988.9  291.46  4993.6  297.24  5006.9  298.04  5079.1  298.33
  5151.2  297.18  5184.7  298.15  5220.8  297.05    5244  297.37  5367.7  303.48
  5463.6   305.9  5625.4  310.31  5766.3  316.83  5778.3  317.34  5821.2  319.17
#Mann= 10 ,-1 , 0
  4025.8     .07       0  4196.2     .12       0  4438.3     .07       0
  4770.3     .12       0  4941.1      .1       0  4977.3     .05       0
  4988.9      .1       0  5463.6     .07       0  5766.3    .035       0
  5778.3     .07       0
Bank Sta=4977.3,4988.9
XS Rating Curve= 0 ,0
Exp/Cntr=0.3,0.1

Type RM Length L Ch R = 1 ,11235   ,459,459,459
BEGIN DESCRIPTION:
Stream0648 16.0
END DESCRIPTION:
XS GIS Cut Line= 3
      2383474.98     13623324.99        2384275.       13623975.
        2384475.       13624125.
#Sta/Elev= 30
  3967.8  310.04  3981.5  310.03  4181.2   300.4  4221.5  299.21  4486.4  295.39
  4523.7  295.52  4649.9   296.4  4778.8  296.42  4820.4  295.59  4898.7  296.85
  4913.1  295.35    4921  296.82  4921.6  290.26  4922.1  289.76  4933.3  290.26
  4934.2  296.42    4985     297  4991.4  291.42  4995.4  292.59  5005.9  293.22
  5012.1  290.47  5020.5   291.2  5026.7  295.15  5035.1   296.1  5041.3  298.43
  5048.6  297.79  5076.7  300.56  5126.7  303.11  5210.2  305.49  5248.6  306.51
#Mann= 7 ,-1 , 0
  3967.8     .12       0  4221.5     .07       0  4523.7     .12       0
  4649.9      .1       0  4921.6     .05       0  4933.3      .1       0
  5210.2     .07       0
Bank Sta=4921.6,4933.3
XS Rating Curve= 0 ,0
Exp/Cntr=0.3,0.1

Type RM Length L Ch R = 1 ,10776   ,451,451,451
BEGIN DESCRIPTION:
Stream0648 15.0
END DESCRIPTION:
XS GIS Cut Line= 3
      2383174.97     13623424.98        2383875.       13623975.
      2384274.97     13624374.97
#Sta/Elev= 30
    4105  320.67  4147.5  319.54    4162  318.12  4190.9  317.06  4278.1  311.56
  4325.6  308.28  4339.6   308.1  4389.7  304.34  4489.2  299.12  4619.4  294.49
  4660.9  293.95  4681.7  294.95  4710.6  293.33    4725  294.56    4785  294.91
  4830.8  295.45  4867.8   294.9  4952.8  296.78  4967.2   295.7  4973.6  290.31
  4982.2  288.59  4982.7  288.09  4993.9  288.59  4995.3  294.61  5009.4  296.22
  5051.8  296.62  5136.7  295.58  5201.9  296.83  5348.8  300.21  5560.9  308.46
#Mann= 8 ,-1 , 0
    4105     .07       0  4278.1     .12       0  4339.6     .07       0
  4619.4     .12       0    4785      .1       0  4982.2     .05       0
  4993.9      .1       0  5201.9     .07       0
Bank Sta=4982.2,4993.9
XS Rating Curve= 0 ,0
Exp/Cntr=0.3,0.1

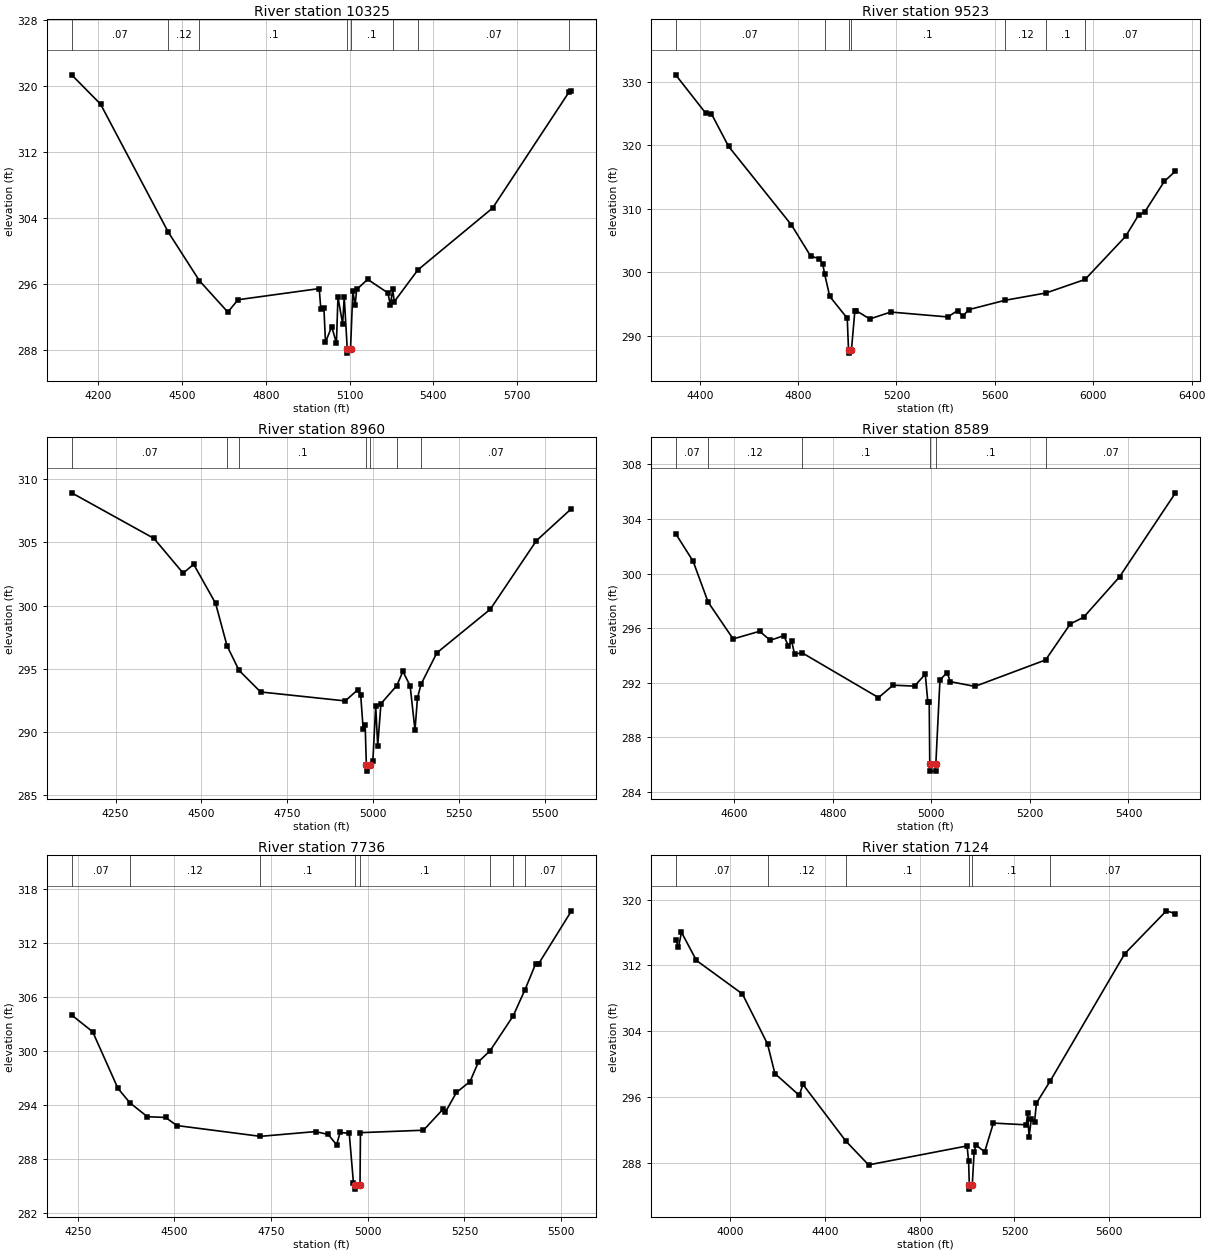
Type RM Length L Ch R = 1 ,10325   ,802,802,802
BEGIN DESCRIPTION:
Stream0648 14.0
END DESCRIPTION:
XS GIS Cut Line= 3
      2383124.99     13623424.98        2383525.       13624225.
      2384325.02     13624625.01
#Sta/Elev= 30
  4105.2  321.31  4208.6  317.76  4450.8  302.26  4562.5  296.36  4664.2  292.56
  4700.6  294.06  4991.3  295.41  4996.9  292.93    5008  293.09  5013.6  288.93
    5036  290.78  5052.8  288.82  5058.3  294.37  5075.1  291.13  5080.7   294.4
  5091.6  288.09  5092.1  287.59  5103.3  288.09  5111.5  295.08  5119.8  293.44
  5125.4  295.31  5164.6  296.53  5237.2  294.88  5245.6  293.42  5254.4  295.31
  5259.6  293.81  5344.2  297.67  5611.8  305.17  5884.6  319.19  5894.1  319.36
#Mann= 8 ,-1 , 0
  4105.2     .07       0  4450.8     .12       0  4562.5      .1       0
  5091.6     .05       0  5103.3      .1       0  5254.4     .12       0
  5344.2     .07       0  5884.6    .035       0
Bank Sta=5091.6,5103.3
XS Rating Curve= 0 ,0
Exp/Cntr=0.3,0.1

Type RM Length L Ch R = 1 ,9523    ,563,563,563
BEGIN DESCRIPTION:
Stream0648 13.0
END DESCRIPTION:
XS GIS Cut Line= 3
      2382500.94     13623705.01      2382919.82     13624187.13
      2384225.05     13624675.02
#Sta/Elev= 30
  4302.2  331.13  4425.4  325.04  4447.3  325.02  4517.5  319.85  4772.9  307.49
  4850.8   302.6  4885.9  302.15  4900.2  301.36  4907.7  299.78  4928.7  296.23
  4999.8   292.8    5005   287.8  5005.5   287.3  5016.9   287.8  5030.6   293.9
    5036  293.99  5091.2  292.68  5176.7  293.77  5408.4     293  5448.2  293.99
  5469.5  293.11    5494  294.15  5641.1  295.62  5807.5  296.77  5966.5   298.9
  6131.4  305.69  6184.8  309.08  6208.6  309.49  6288.8  314.34  6334.3  315.98
#Mann= 7 ,-1 , 0
  4302.2     .07       0  4907.7      .1       0    5005     .05       0
  5016.9      .1       0  5641.1     .12       0  5807.5      .1       0
  5966.5     .07       0
Bank Sta=5005,5016.9
XS Rating Curve= 0 ,0
Exp/Cntr=0.3,0.1

Type RM Length L Ch R = 1 ,8960    ,371,371,371
BEGIN DESCRIPTION:
Stream0648 12.0
END DESCRIPTION:
XS GIS Cut Line= 3
       2382429.8     13624171.34      2383243.88     13624677.17
      2383591.67     13625032.86
#Sta/Elev= 30
  4122.1  308.93  4361.8  305.32  4446.8  302.57  4477.5  303.27  4541.3  300.18
  4574.6  296.82  4609.6  294.87  4672.4  293.16  4919.1  292.45  4955.7  293.34
  4964.1  292.89  4971.1  290.26    4977  290.52  4980.5  287.39    4981  286.89
  4992.4  287.39  4999.4  287.67  5007.7  292.04  5013.6  288.89    5023  292.23
  5069.3  293.67  5086.9  294.79    5108  293.64  5122.2  290.13  5129.3  292.67
  5139.6  293.76  5185.9  296.26  5341.5  299.71  5475.8  305.14    5578  307.68
#Mann= 7 ,-1 , 0
  4122.1     .07       0  4574.6     .12       0  4609.6      .1       0
  4980.5     .05       0  4992.4      .1       0  5069.3     .12       0
  5139.6     .07       0
Bank Sta=4980.5,4992.4
XS Rating Curve= 0 ,0
Exp/Cntr=0.3,0.1

Type RM Length L Ch R = 1 ,8589    ,853,853,853
BEGIN DESCRIPTION:
Stream0648 11.0
END DESCRIPTION:
XS GIS Cut Line= 3
      2382525.01     13624675.01        2382975.       13624925.
      2383375.02     13625225.02
#Sta/Elev= 30
  4480.7  302.93  4516.2   300.9  4546.6  297.91  4597.4  295.21  4651.1  295.77
  4672.9  295.11  4700.3  295.45  4709.5   294.7  4716.3  295.03  4722.1   294.1
  4737.6  294.19  4892.5  290.91  4922.3  291.82  4965.7  291.75  4987.5  292.63
  4992.6  290.62  4995.5  290.62  4996.6  286.02  4997.1  285.52  5008.4  285.52
  5008.9  286.02  5017.3  292.21  5031.9  292.74  5038.2  292.08  5088.2  291.73
  5231.8  293.67  5281.9  296.31    5309   296.8  5381.9  299.76  5495.5  305.92
#Mann= 6 ,-1 , 0
  4480.7     .07       0  4546.6     .12       0  4737.6      .1       0
  4996.6     .05       0  5008.9      .1       0  5231.8     .07       0
Bank Sta=4996.6,5008.9
XS Rating Curve= 0 ,0
Exp/Cntr=0.3,0.1

Type RM Length L Ch R = 1 ,7736    ,612,612,612
BEGIN DESCRIPTION:
Stream0648 10.0
END DESCRIPTION:
XS GIS Cut Line= 3
      2382474.99     13624674.99        2382775.       13625375.
        2383175.       13625725.
#Sta/Elev= 30
    4234  304.02  4288.4  302.16  4353.7  295.88  4384.5  294.28  4429.8  292.73
    4477  292.65    4506  291.75  4722.2  290.55    4865  291.08  4897.7  290.76
  4919.4  289.61  4928.5  290.98  4952.1  290.89    4963  285.39  4967.7  285.19
  4968.2  284.69    4980  285.19  4981.1  290.96  5144.1  291.23  5194.4  293.55
  5201.1  293.26  5229.6  295.43  5264.7  296.64  5286.5  298.83  5316.6  300.06
  5376.3  303.93  5406.7  306.82  5434.6  309.73  5442.2  309.72  5527.1  315.59
#Mann= 8 ,-1 , 0
    4234     .07       0  4384.5     .12       0  4722.2      .1       0
  4967.7     .05       0    4980      .1       0  5316.6     .07       0
  5376.3     .12       0  5406.7     .07       0
Bank Sta=4967.7,4980
XS Rating Curve= 0 ,0
Exp/Cntr=0.3,0.1

Type RM Length L Ch R = 1 ,7124    ,925,925,925
BEGIN DESCRIPTION:
XS7389
END DESCRIPTION:
XS GIS Cut Line= 3
      2381734.21     13625001.23      2382192.65     13625214.64
      2383006.77     13626597.86
#Sta/Elev= 30
  3769.3  315.15  3781.2  314.21  3793.9  316.03    3857  312.61  4051.1  308.55
  4157.2  302.48  4188.4  298.89  4291.1  296.25  4306.8  297.57  4487.9   290.7
    4584  287.81  4999.9  290.11  5006.4  288.23  5009.4  285.37  5009.9  284.87
  5021.8  285.37  5029.6  289.32    5037  290.23  5074.1  289.39  5110.9  292.88
  5249.9  292.67  5255.7  294.07  5261.7  291.21  5271.4  293.43  5284.9  293.02
  5292.8   295.3  5351.6  298.02  5665.8  313.43  5841.5  318.63    5880  318.28
#Mann= 6 ,-1 , 0
  3769.3     .07       0  4157.2     .12       0  4487.9      .1       0
  5009.4     .05       0  5021.8      .1       0  5351.6     .07       0
Bank Sta=5009.4,5021.8
XS Rating Curve= 0 ,0
Exp/Cntr=0.3,0.1

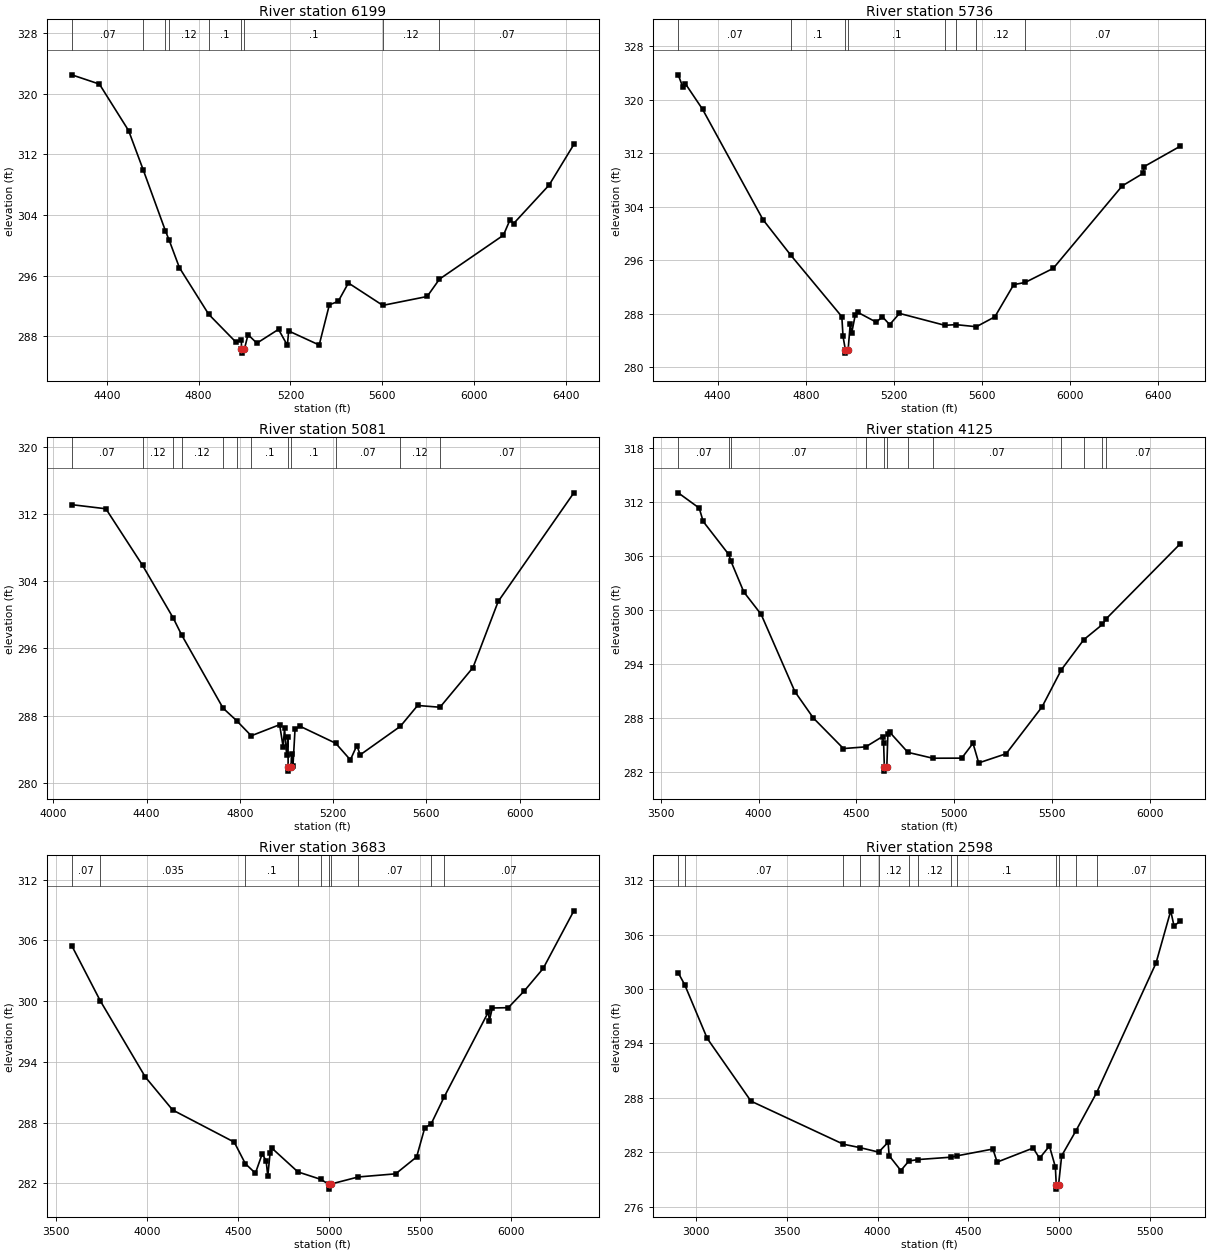
Type RM Length L Ch R = 1 ,6199    ,463,463,463
BEGIN DESCRIPTION:
XS7388
END DESCRIPTION:
XS GIS Cut Line= 2
      2381647.28     13625088.17      2382651.08     13627032.55
#Sta/Elev= 30
  4247.1  322.46  4367.5  321.24  4494.8  315.11  4559.4  309.87  4654.9  301.94
  4671.9  300.65  4716.3  297.05    4844  290.91  4963.8  287.21  4986.3  287.55
  4986.8   286.3  4987.3   285.8  4999.3   286.3  5015.2  288.24  5053.8  287.11
  5148.1  288.93  5186.8  286.83  5192.4  288.72  5325.4  286.87  5369.7  292.16
  5408.4  292.62  5452.7  295.04  5602.6  292.09  5795.9  293.26  5849.7  295.55
  6128.2  301.33  6156.7  303.33  6172.5  302.86  6327.5  307.94  6435.3  313.29
#Mann= 9 ,-1 , 0
  4247.1     .07       0  4559.4     .12       0  4654.9     .07       0
  4671.9     .12       0    4844      .1       0  4986.8     .05       0
  4999.3      .1       0  5602.6     .12       0  5849.7     .07       0
Bank Sta=4986.8,4999.3
XS Rating Curve= 0 ,0
Exp/Cntr=0.3,0.1

Type RM Length L Ch R = 1 ,5736    ,655,655,655
BEGIN DESCRIPTION:
XS7387
END DESCRIPTION:
XS GIS Cut Line= 3
      2381307.42     13625246.29       2381892.3     13626416.05
      2382469.32     13627198.58
#Sta/Elev= 30
    4221  323.72  4241.9  321.87  4253.9  322.37  4331.4  318.57  4606.1  302.05
  4732.8  296.72  4963.9  287.56  4969.4   284.6    4980   282.6  4980.5   282.1
  4992.5   282.6  5002.2  286.49  5008.6  285.09  5024.5  287.74  5036.5   288.2
  5120.4  286.73  5148.3  287.54  5181.1  286.36  5225.8  288.04    5432  286.26
    5482  286.36  5574.8  286.05  5658.9  287.53  5744.5  292.34  5796.4  292.67
  5924.1  294.78  6237.3  307.11  6331.3  308.97  6337.5  310.01  6501.1  313.05
#Mann= 8 ,-1 , 0
    4221     .07       0  4732.8      .1       0    4980     .05       0
  4992.5      .1       0    5432     .07       0    5482      .1       0
  5574.8     .12       0  5796.4     .07       0
Bank Sta=4980,4992.5
XS Rating Curve= 0 ,0
Exp/Cntr=0.3,0.1

Type RM Length L Ch R = 1 ,5081    ,956,956,956
BEGIN DESCRIPTION:
XS7386
END DESCRIPTION:
XS GIS Cut Line= 3
      2381070.28     13625625.63       2381283.7     13626234.26
      2382120.43     13627489.36
#Sta/Elev= 30
  4079.3  313.12  4225.6  312.63  4382.7   305.9  4514.4  299.62    4550  297.63
  4728.3  288.88  4786.4  287.39  4849.1  285.59  4970.8  286.91  4985.8  284.27
  4991.8  286.46  5000.8  283.34  5006.8   285.4  5007.3  281.88  5007.8  281.38
  5019.8  281.88  5021.8   283.4  5027.8  281.94  5036.9  286.38  5057.9  286.73
  5211.3   284.7  5274.2  282.72    5302  284.43  5316.3  283.32  5488.7  286.72
  5562.7   289.2  5658.6  288.99    5800  293.71  5908.2  301.59  6232.7  314.53
#Mann= 12 ,-1 , 0
  4079.3     .07       0  4382.7     .12       0  4514.4     .07       0
    4550     .12       0  4728.3      .1       0  4786.4     .07       0
  4849.1      .1       0  5007.3     .05       0  5019.8      .1       0
  5211.3     .07       0  5488.7     .12       0  5658.6     .07       0
Bank Sta=5007.3,5019.8
XS Rating Curve= 0 ,0
Exp/Cntr=0.3,0.1

Type RM Length L Ch R = 1 ,4125    ,442,442,442
BEGIN DESCRIPTION:
XS7385
END DESCRIPTION:
XS GIS Cut Line= 3
      2380991.25     13625728.39      2381078.19     13626479.28
      2381963.44     13628060.08
#Sta/Elev= 30
  3588.7  312.98    3696  311.29  3716.2  309.81    3847  306.15  3858.7  305.38
  3924.1  301.99  4012.8  299.51  4185.3  290.95  4279.9  288.02  4433.6  284.64
  4547.6  284.83  4633.4  285.97  4639.1  285.21  4642.8  282.64  4643.3  282.14
  4655.5  282.64  4660.8  286.26  4671.1  286.43  4763.3  284.22  4890.3  283.57
  5038.6  283.58  5096.1  285.23  5125.4  283.05  5265.8  284.07  5449.6  289.27
  5548.2  293.38  5662.9  296.71  5757.9  298.39  5777.7  299.03  6156.4  307.34
#Mann= 12 ,-1 , 0
  3588.7     .07       0    3847     .12       0  3858.7     .07       0
  4547.6      .1       0  4642.8     .05       0  4655.5      .1       0
  4763.3     .12       0  4890.3     .07       0  5548.2    .035       0
  5662.9     .07       0  5757.9    .035       0  5777.7     .07       0
Bank Sta=4642.8,4655.5
XS Rating Curve= 0 ,0
Exp/Cntr=0.3,0.1

Type RM Length L Ch R = 1 ,3683    ,1085,1085,1085
BEGIN DESCRIPTION:
XS7384
END DESCRIPTION:
XS GIS Cut Line= 3
      2380841.07      13625870.7      2380825.27     13626755.92
      2381710.26     13628407.38
#Sta/Elev= 30
  3587.3  305.47  3744.2  300.02  3991.7   292.5  4141.7  289.25    4480  286.08
  4541.2  283.95  4596.4  283.01  4633.5  284.91  4655.4  284.24  4664.5  282.72
  4677.4  285.05  4687.2  285.48    4830  283.14  4954.5  282.41  4998.4  281.94
  4998.9  281.44  5011.2  281.94  5161.5  282.64  5367.1  282.95  5482.4  284.62
  5526.7  287.47    5563  287.91  5632.9  290.51  5876.4  298.92  5882.1  298.07
  5898.3  299.32    5986  299.35  6073.8     301  6177.7  303.22  6346.3  308.91
#Mann= 10 ,-1 , 0
  3587.3     .07       0  3744.2    .035       0  4541.2      .1       0
    4830     .12       0  4954.5      .1       0  4998.4     .05       0
  5011.2      .1       0  5161.5     .07       0    5563    .035       0
  5632.9     .07       0
Bank Sta=4998.4,5011.2
XS Rating Curve= 0 ,0
Exp/Cntr=0.3,0.1

Type RM Length L Ch R = 1 ,2598    ,0,0,0
BEGIN DESCRIPTION:
XS7383
END DESCRIPTION:
XS GIS Cut Line= 3
      2380762.02     13625941.85      2380445.87     13627016.75
      2381101.91     13628526.44
#Sta/Elev= 30
  2901.8  301.78  2937.1  300.49  3061.4  294.56  3302.6  287.64  3811.8  282.89
  3904.5  282.51  4006.3  282.02  4058.1  283.11  4063.9  281.63  4128.4  279.99
  4172.7  281.04  4222.8   281.2  4404.1  281.46  4440.4  281.62  4635.6  282.36
    4659  280.92  4857.5  282.47  4892.6  281.34  4947.1  282.69  4979.8  280.39
  4984.7  278.44  4985.2  277.94  4997.6  278.44  5014.6  281.62  5093.1  284.37
  5207.1  288.57  5534.2  302.85  5615.5  308.62  5633.5  306.96  5668.3  307.49
#Mann= 13 ,-1 , 0
  2901.8    .035       0  2937.1     .07       0  3811.8     .12       0
  3904.5     .07       0  4006.3     .12       0  4172.7      .1       0
  4222.8     .12       0  4404.1    .035       0  4440.4      .1       0
  4984.7     .05       0  4997.6      .1       0  5093.1     .12       0
  5207.1     .07       0
Bank Sta=4984.7,4997.6
XS Rating Curve= 0 ,0
Exp/Cntr=0.3,0.1

Chan Stop Cuts=-1
Use User Specified Reach Order=0
Composite Channel Slope=5