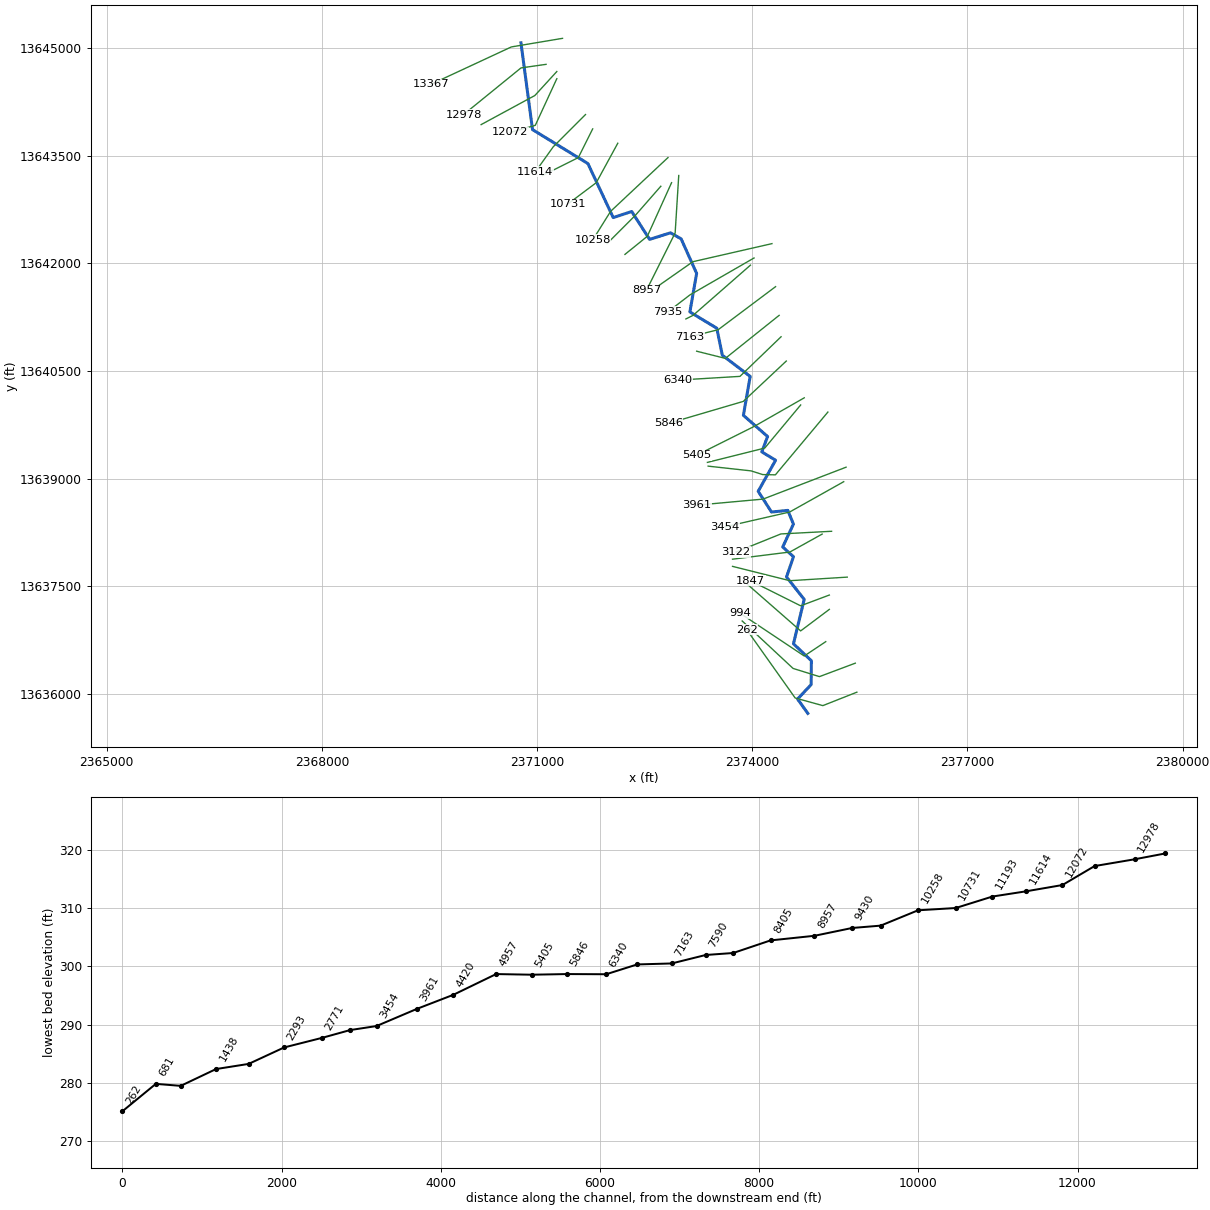
--- Stream0653.prj (project) ---

Proj Title=Stream0653 Base Level Engineering
Current Plan=p01
Default Exp/Contr=0.3,0.1
English Units
Geom File=g01
Flow File=f01
Plan File=p01
Y Axis Title=Elevation
X Axis Title(PF)=Main Channel Distance
X Axis Title(XS)=Station
BEGIN DESCRIPTION:
Stream0653
END DESCRIPTION:
DSS Export Rating Curves= 0
DSS Export Rating Curve Sorted= 0
DSS Export Volume Flow Curves= 0
DXF OffsetX= 0
DXF OffsetY= 0
DXF ScaleX= 1
DXF ScaleY= 10

--- Stream0653.p01 (plan) ---

Plan Title=Multiple Run
Short Identifier=Multiple
Geom File=g01
Flow File=f01
Subcritical Flow
K Sum by GR= 0
Std Step Tol= 0.01
Critical Tol= 0.01
Num of Std Step Trials= 20
Max Error Tol= 0.3
Flow Tol Ratio= 0.001
Split Flow NTrial= 30
Split Flow Tol= 0.02
Split Flow Ratio= 0.02
Log Output Level= 0
Friction Slope Method= 1
Unsteady Friction Slope Method= 2
Unsteady Bridges Friction Slope Method= 1
Parabolic Critical Depth
Global Vel Dist=  1 , 1 , 1
Global Log Level= 0
CheckData=True
Encroach Param= -1, 0, 0, 0
BEGIN DESCRIPTION:
Multiple Run
END DESCRIPTION:

--- Stream0653.f01 (steady flow) ---

Flow Title=Multiple
Number of Profiles=7
Profile Names=10-year,25-year,50-year,1pct_min,100-year,1pct_plu,500-year
River Rch & RM= Stream0653,Reach-1,13367
     676    1102    1491     977    1949    3889    3302
River Rch & RM= Stream0653,Reach-1,12072
     781    1278    1733    1137    2268    4524    3851
River Rch & RM= Stream0653,Reach-1,8405
    1093    1819    2493    1650    3292    6569    5698
River Rch & RM= Stream0653,Reach-1,5405
    1178    1958    2681    1772    3535    7053    6099
Boundary for River Rch & Prof#=Stream0653,Reach-1,1
Up Type=0
Dn Type=3
Dn Slope=0.005
Boundary for River Rch & Prof#=Stream0653,Reach-1,2
Up Type=0
Dn Type=3
Dn Slope=0.005
Boundary for River Rch & Prof#=Stream0653,Reach-1,3
Up Type=0
Dn Type=3
Dn Slope=0.005
Boundary for River Rch & Prof#=Stream0653,Reach-1,4
Up Type=0
Dn Type=3
Dn Slope=0.005
Boundary for River Rch & Prof#=Stream0653,Reach-1,5
Up Type=0
Dn Type=3
Dn Slope=0.005
Boundary for River Rch & Prof#=Stream0653,Reach-1,6
Up Type=0
Dn Type=3
Dn Slope=0.005
Boundary for River Rch & Prof#=Stream0653,Reach-1,7
Up Type=0
Dn Type=3
Dn Slope=0.005

--- Stream0653.g01 (geometry) ---

Geom Title=Existing Conditions
Program Version=4.10

River Reach=Stream0653      ,Reach-1
Reach XY= 30
        2370775.       13645075.       2370936.1     13643864.94
      2371708.37     13643391.71      2372061.25     13642638.24
      2372319.35     13642723.04      2372568.31     13642334.29
      2372859.92     13642425.79      2373008.37     13642341.71
      2373224.48     13641859.78       2373130.4     13641322.57
      2373505.58     13641095.65      2373582.81     13640718.81
      2373971.26     13640423.45      2373876.66     13639881.05
      2374214.04       13639585.      2374132.87     13639371.38
      2374325.45     13639254.98      2374082.67     13638821.34
      2374268.61     13638532.34      2374495.64     13638555.62
      2374574.24     13638364.31      2374424.74     13638044.95
      2374574.81     13637909.91      2374478.12     13637626.63
      2374724.44     13637314.36      2374574.59     13636695.13
      2374824.34     13636459.17      2374821.46     13636126.46
      2374632.07       13635925.        2374775.       13635725.

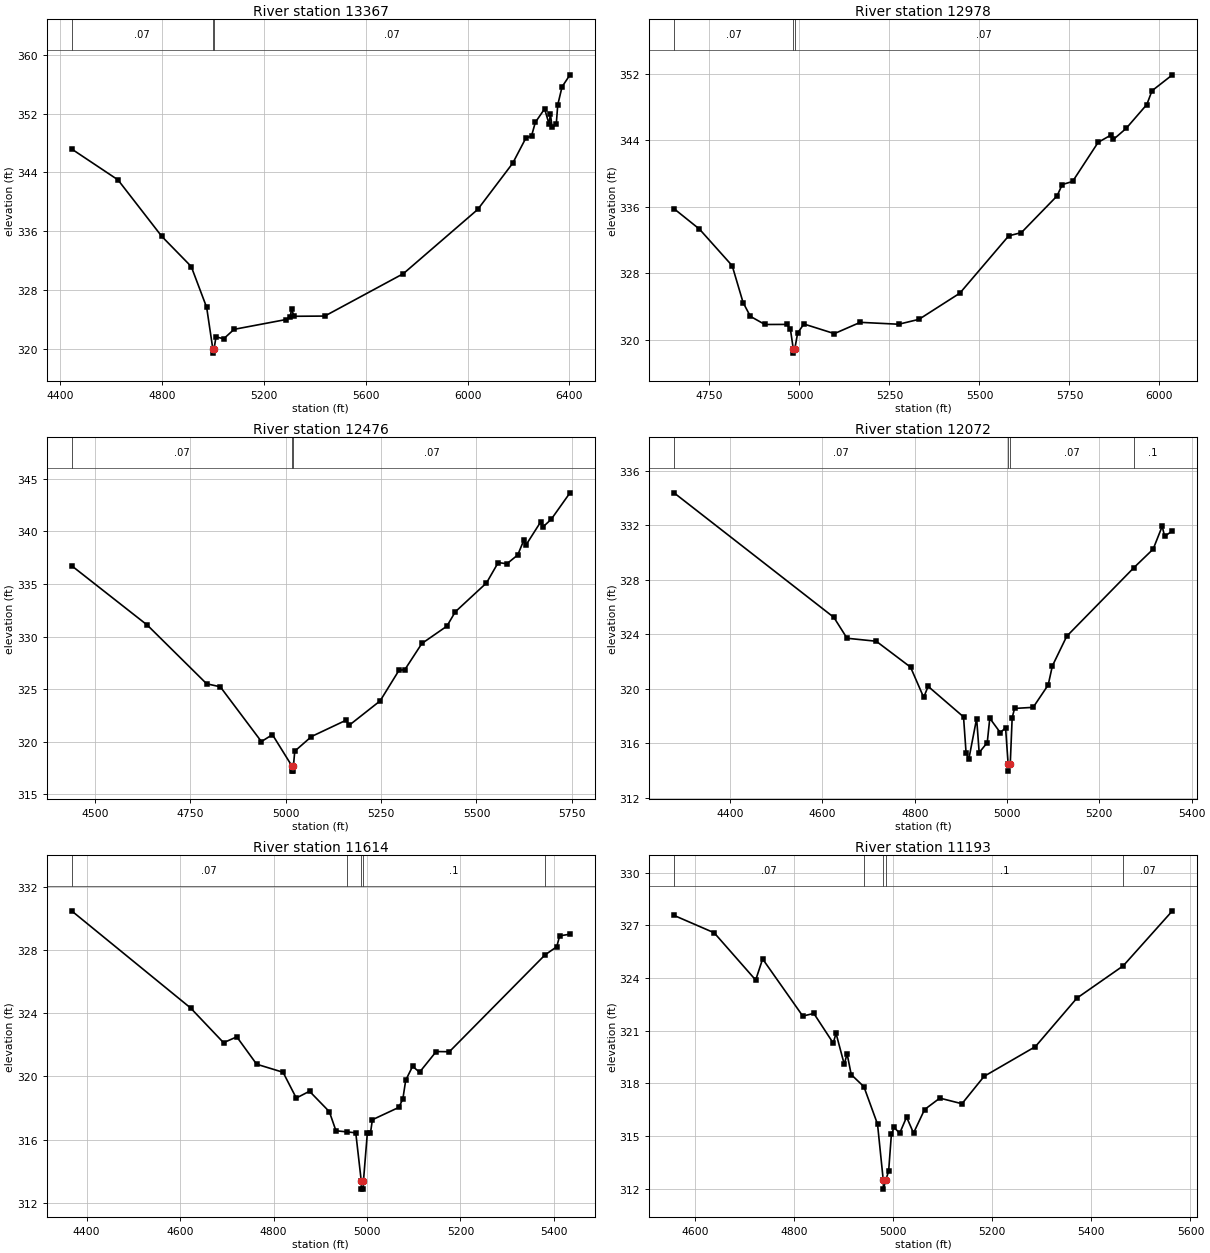
Type RM Length L Ch R = 1 ,13367   ,389,389,389
BEGIN DESCRIPTION:
XS7408
END DESCRIPTION:
XS GIS Cut Line= 3
      2371354.69     13645137.69      2370641.15      13645017.9
      2369521.37     13644497.07
#Sta/Elev= 30
  4443.6  347.19  4625.8  342.98  4798.2  335.27  4913.8  331.17  4974.4   325.6
  4998.9  319.87  4999.2  319.37    5003  319.87  5011.1  321.58  5041.5  321.33
  5082.1  322.61  5285.2  323.94  5302.6  324.29  5308.1  325.41  5317.3  324.39
  5438.6  324.42  5747.4   330.2  6039.6  338.95  6176.9  345.24  6228.2  348.64
  6251.1  348.97  6265.8  350.81  6302.3  352.65  6319.7  350.61  6325.2  351.93
  6331.9  350.14  6348.1  350.53    6354   353.2    6371  355.66  6402.1  357.29
#Mann= 3 ,-1 , 0
  4443.6     .07       0  4998.9     .07       0    5003     .07       0
Bank Sta=4998.9,5003
XS Rating Curve= 0 ,0
Exp/Cntr=0.3,0.1

Type RM Length L Ch R = 1 ,12978   ,502,502,502
BEGIN DESCRIPTION:
Stream0653 27.0
END DESCRIPTION:
XS GIS Cut Line= 3
      2371124.96     13644774.99        2370775.       13644725.
      2369974.99       13644075.
#Sta/Elev= 30
  4651.6  335.76  4722.3   333.3  4813.2  328.89  4843.5  324.45  4863.7  322.79
  4904.1  321.81  4964.7  321.82  4974.8  321.26  4982.9  318.86  4983.1  318.36
    4987  318.86    4995  320.78  5012.3  321.87    5097  320.71  5168.9  322.07
  5275.7  321.84  5331.9  322.43  5445.4  325.58  5581.2  332.49  5616.4  332.88
  5715.5   337.3  5729.9  338.67  5758.6  339.04  5829.7  343.76  5865.7  344.64
  5872.1  344.11  5907.3  345.43  5964.8  348.31  5979.2  349.97  6035.9  351.89
#Mann= 3 ,-1 , 0
  4651.6     .07       0  4982.9     .07       0    4987     .07       0
Bank Sta=4982.9,4987
XS Rating Curve= 0 ,0
Exp/Cntr=0.3,0.1

Type RM Length L Ch R = 1 ,12476   ,404,404,404
BEGIN DESCRIPTION:
Stream0653 26.0
END DESCRIPTION:
XS GIS Cut Line= 3
      2371275.03     13644675.04      2370969.27     13644340.81
      2370219.66     13643934.77
#Sta/Elev= 30
  4439.4  336.74  4637.7  331.09  4793.1  325.51  4828.9  325.22  4936.6  320.01
  4965.5  320.67  5016.3   317.7  5016.5   317.2  5020.2   317.2  5020.5   317.7
    5024   319.1  5067.8  320.49  5158.8  322.05  5165.8  321.54  5247.6  323.88
    5297  326.79  5312.3  326.85  5356.9  329.34  5422.5  330.99  5444.4  332.35
  5526.2   335.1  5556.9  337.04  5579.6  336.92    5608  337.76  5624.2  339.18
  5629.9  338.72  5667.9  340.89  5673.6  340.41  5695.5  341.14  5744.9  343.67
#Mann= 3 ,-1 , 0
  4439.4     .07       0  5016.3     .07       0  5020.5     .07       0
Bank Sta=5016.3,5020.5
XS Rating Curve= 0 ,0
Exp/Cntr=0.3,0.1

Type RM Length L Ch R = 1 ,12072   ,458,458,458
BEGIN DESCRIPTION:
Stream0653 25.0
END DESCRIPTION:
XS GIS Cut Line= 3
      2371274.98     13644574.96        2370975.       13643925.
      2370624.95     13643824.99
#Sta/Elev= 30
  4278.4  334.37  4624.8  325.23  4653.3   323.7  4716.6  323.48  4790.9  321.58
  4819.4  319.36    4829  320.17  4905.7  317.93  4911.2   315.3  4917.1  314.82
  4934.1  317.81  4939.6  315.31  4957.1  316.04  4962.6  317.83  4985.5  316.77
  4996.8  317.14  5002.4  314.45  5002.7  313.95  5006.9  314.45  5011.1  317.87
  5016.3  318.55  5056.6  318.63  5089.1  320.27  5098.2  321.67  5129.4  323.85
  5275.2  328.89  5316.6  330.24  5336.2  331.92  5341.4  331.17  5358.3  331.58
#Mann= 4 ,-1 , 0
  4278.4     .07       0  5002.4     .07       0  5006.9     .07       0
  5275.2      .1       0
Bank Sta=5002.4,5006.9
XS Rating Curve= 0 ,0
Exp/Cntr=0.3,0.1

Type RM Length L Ch R = 1 ,11614   ,421,421,421
BEGIN DESCRIPTION:
Stream0653 24.0
END DESCRIPTION:
XS GIS Cut Line= 3
      2371674.98     13644074.98        2371225.       13643625.
      2370974.99     13643274.99
#Sta/Elev= 30
  4367.9  330.47  4622.4  324.33  4693.1  322.13  4721.4   322.5  4763.9  320.77
  4820.4  320.26  4848.7  318.63    4877  319.06  4919.4  317.77  4933.6  316.56
  4957.3  316.49    4976  316.43  4987.8  313.37  4988.1  312.87  4992.1  312.87
  4992.4  313.37  5000.7  316.39  5007.3  316.39  5011.6  317.26  5068.2  318.04
  5076.8  318.58  5082.9  319.76  5097.7  320.64  5112.4  320.26  5148.1  321.57
  5176.3  321.56  5380.9  327.68  5406.1   328.2  5412.3  328.89  5434.4  328.99
#Mann= 5 ,-1 , 0
  4367.9     .07       0  4957.3      .1       0  4987.8     .07       0
  4992.4      .1       0  5380.9     .07       0
Bank Sta=4987.8,4992.4
XS Rating Curve= 0 ,0
Exp/Cntr=0.3,0.1

Type RM Length L Ch R = 1 ,11193   ,462,462,462
BEGIN DESCRIPTION:
Stream0653 23.0
END DESCRIPTION:
XS GIS Cut Line= 3
      2371775.02     13643875.03        2371575.       13643475.
      2371074.97     13643224.98
#Sta/Elev= 30
  4557.3  327.56  4638.4  326.57  4722.2  323.88  4736.2  325.08  4817.3  321.83
  4839.6  321.98  4878.8  320.29  4884.4  320.85  4901.1  319.08  4906.7  319.69
  4915.1   318.5  4940.7  317.81  4968.2  315.68  4979.8  312.48  4980.2  311.98
  4984.5  312.48  4990.6  312.99  4996.2   315.1  5001.8  315.49  5012.9  315.16
  5026.9  316.08  5040.9  315.17  5063.2  316.51    5094  317.16  5138.7  316.84
  5183.4   318.4  5286.9  320.09  5370.7  322.85  5464.3  324.69  5563.6  327.82
#Mann= 5 ,-1 , 0
  4557.3     .07       0  4940.7      .1       0  4979.8     .07       0
  4984.5      .1       0  5464.3     .07       0
Bank Sta=4979.8,4984.5
XS Rating Curve= 0 ,0
Exp/Cntr=0.3,0.1

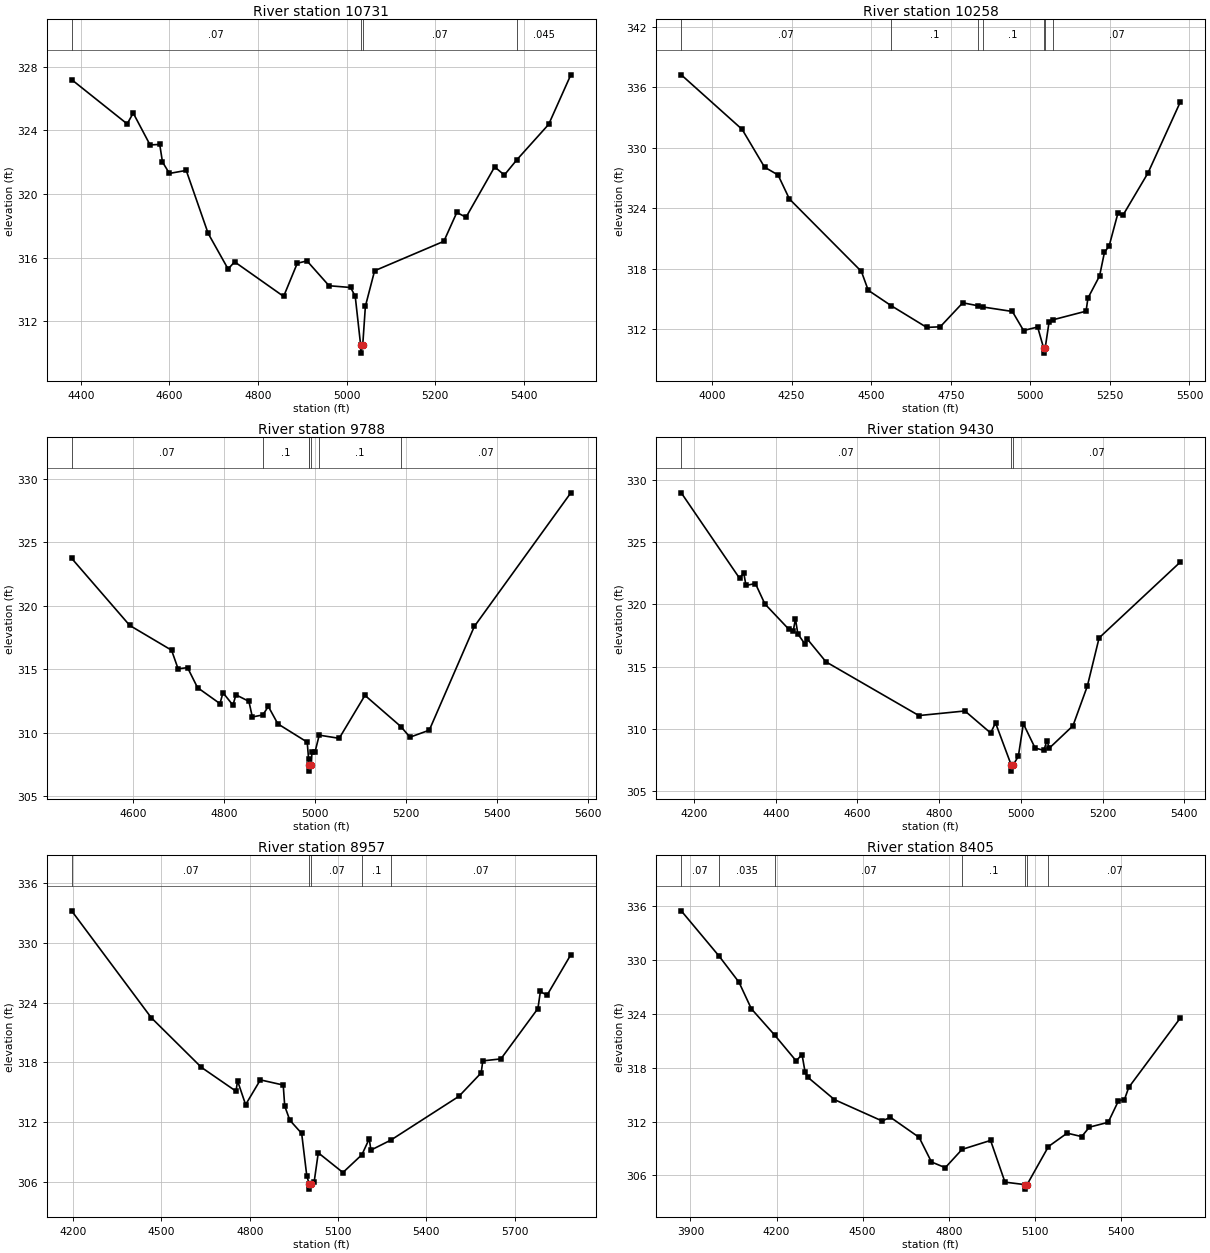
Type RM Length L Ch R = 1 ,10731   ,473,473,473
BEGIN DESCRIPTION:
Stream0653 22.0
END DESCRIPTION:
XS GIS Cut Line= 3
      2372124.98     13643674.96        2371825.       13643125.
      2371424.96     13642824.97
#Sta/Elev= 30
  4379.4  327.18  4504.7   324.4  4518.4  325.08  4556.4  323.08  4578.2  323.11
  4584.4  322.01  4600.1  321.29    4638  321.48  4687.4  317.53  4732.5  315.29
  4747.2  315.74  4857.8  313.57  4888.6  315.65  4910.5   315.8  4960.3  314.24
    5009  314.13  5019.4  313.57  5031.6  310.51  5031.9  310.01  5036.3  310.51
  5042.3  312.95  5063.1  315.18  5219.4  317.03  5248.6  318.84  5269.4  318.54
    5334   321.7  5355.9  321.19  5384.5  322.16  5455.9  324.37  5505.9  327.48
#Mann= 4 ,-1 , 0
  4379.4     .07       0  5031.6     .07       0  5036.3     .07       0
  5384.5    .045       0
Bank Sta=5031.6,5036.3
XS Rating Curve= 0 ,0
Exp/Cntr=0.3,0.1

Type RM Length L Ch R = 1 ,10258   ,470,470,470
BEGIN DESCRIPTION:
Stream0653 21.0
END DESCRIPTION:
XS GIS Cut Line= 3
      2372825.04     13643475.03        2372025.       13642725.
      2371775.02     13642325.03
#Sta/Elev= 30
  3903.3  337.21  4094.6   331.8  4164.9  328.06  4207.4  327.28  4243.1   324.9
  4469.2  317.72  4490.7  315.85  4562.5  314.33  4674.4  312.17  4716.9  312.23
  4787.7  314.61  4834.7  314.32  4849.7   314.2  4943.5  313.75  4978.7  311.86
  5022.9  312.21  5041.7  310.12  5042.1  309.62  5046.6  310.12  5058.9  312.72
  5070.4  312.92  5175.1  313.78  5180.9  315.07  5217.5  317.27  5232.8  319.61
  5247.6  320.25  5275.3  323.51  5290.6  323.27  5369.6  327.48  5471.6  334.55
#Mann= 7 ,-1 , 0
  3903.3     .07       0  4562.5      .1       0  4834.7     .07       0
  4849.7      .1       0  5041.7     .07       0  5046.6      .1       0
  5070.4     .07       0
Bank Sta=5041.7,5046.6
XS Rating Curve= 0 ,0
Exp/Cntr=0.3,0.1

Type RM Length L Ch R = 1 ,9788    ,358,358,358
BEGIN DESCRIPTION:
Stream0653 20.0
END DESCRIPTION:
XS GIS Cut Line= 3
      2372725.01     13643075.01        2372375.       13642675.
        2371975.       13642275.
#Sta/Elev= 30
  4464.3  323.73    4592  318.45    4684   316.5  4698.3  315.04  4719.1  315.13
    4741  313.56  4790.3   312.3    4797  313.16  4818.8  312.18  4825.5  312.99
  4853.9  312.48  4861.5  311.25  4884.6  311.41  4896.6  312.08  4917.5  310.71
  4982.1  309.27  4985.1  307.97  4986.2  307.49  4986.6  306.99  4991.1  307.49
  4992.5  308.52  4999.4  308.52  5008.5  309.82  5052.4  309.57    5109  312.95
  5187.8   310.5    5208  309.66  5250.4  310.21  5349.4  318.37  5561.5  328.88
#Mann= 7 ,-1 , 0
  4464.3     .07       0  4884.6      .1       0  4985.1     .07       0
  4986.2     .07       0  4991.1     .07       0  5008.5      .1       0
  5187.8     .07       0
Bank Sta=4986.2,4991.1
XS Rating Curve= 0 ,0
Exp/Cntr=0.3,0.1

Type RM Length L Ch R = 1 ,9430    ,473,473,473
BEGIN DESCRIPTION:
Stream0653 19.0
END DESCRIPTION:
XS GIS Cut Line= 3
      2372874.99     13643124.98      2372536.98     13642377.27
      2372224.98     13642124.98
#Sta/Elev= 30
  4168.7  328.98  4311.3  322.11  4321.7  322.53  4327.1  321.53  4350.2  321.68
  4373.4  320.04  4432.1     318  4442.7  317.85  4448.2  318.84    4454  317.63
  4471.3  316.82  4476.8  317.23    4523  315.38  4750.3  311.06    4863  311.43
  4925.9  309.66  4937.9  310.47  4976.2  307.09  4976.5  306.59  4981.1  307.09
  4993.7  307.78    5006   310.4  5034.7  308.45  5056.1  308.26  5063.5  309.02
  5069.9  308.45  5127.4  310.24  5162.6  313.43  5191.4  317.31  5390.5  323.42
#Mann= 3 ,-1 , 0
  4168.7     .07       0  4976.2     .07       0  4981.1     .07       0
Bank Sta=4976.2,4981.1
XS Rating Curve= 0 ,0
Exp/Cntr=0.3,0.1

Type RM Length L Ch R = 1 ,8957    ,552,552,552
BEGIN DESCRIPTION:
Stream0653 18.0
END DESCRIPTION:
XS GIS Cut Line= 3
        2372975.     13643224.96        2372925.       13642425.
      2372525.02     13641625.04
#Sta/Elev= 30
  4194.7  333.22  4465.2  322.48  4635.5  317.49  4753.2  315.09  4758.3  316.14
  4785.8  313.74  4835.9  316.23  4913.6  315.71  4918.6   313.6  4936.1  312.17
  4976.2  310.85  4993.7  306.56  5002.1  305.75  5002.5  305.25  5007.2  305.75
  5018.6  305.97  5032.6   308.9  5116.4  306.92  5180.9  308.71  5205.8  310.31
  5211.4  309.17  5279.3  310.18  5510.5  314.58    5586  316.93  5591.6  318.14
  5653.1  318.34  5778.8   323.4  5787.2  325.12  5809.6  324.73  5890.6  328.81
#Mann= 5 ,-1 , 0
  4194.7     .07       0  5002.1     .07       0  5007.2     .07       0
  5180.9      .1       0  5279.3     .07       0
Bank Sta=5002.1,5007.2
XS Rating Curve= 0 ,0
Exp/Cntr=0.3,0.1

Type RM Length L Ch R = 1 ,8405    ,470,470,470
BEGIN DESCRIPTION:
Stream0653 17.0
END DESCRIPTION:
XS GIS Cut Line= 3
      2374274.97     13642274.99       2373172.4     13642023.11
      2372674.99       13641675.
#Sta/Elev= 30
  3868.3  335.49  4000.3  330.43  4069.3  327.53  4112.3  324.57  4193.7  321.63
  4268.3  318.76  4288.8  319.47  4299.5   317.5  4309.4  316.92  4401.7  314.44
  4567.6  312.06  4596.6  312.47  4696.5  310.23  4739.4  307.49  4787.5  306.85
    4846  308.89  4945.3  309.89  4995.4  305.24  5065.4  304.96  5065.9  304.46
  5072.3  304.96  5146.8  309.21  5211.8   310.7  5262.4  310.32  5289.4  311.37
  5354.8  311.91  5390.6  314.31  5411.5  314.45  5426.3   315.8  5606.4  323.56
#Mann= 7 ,-1 , 0
  3868.3     .07       0  4000.3    .035       0  4193.7     .07       0
    4846      .1       0  5065.4     .07       0  5072.3      .1       0
  5146.8     .07       0
Bank Sta=5065.4,5072.3
XS Rating Curve= 0 ,0
Exp/Cntr=0.3,0.1

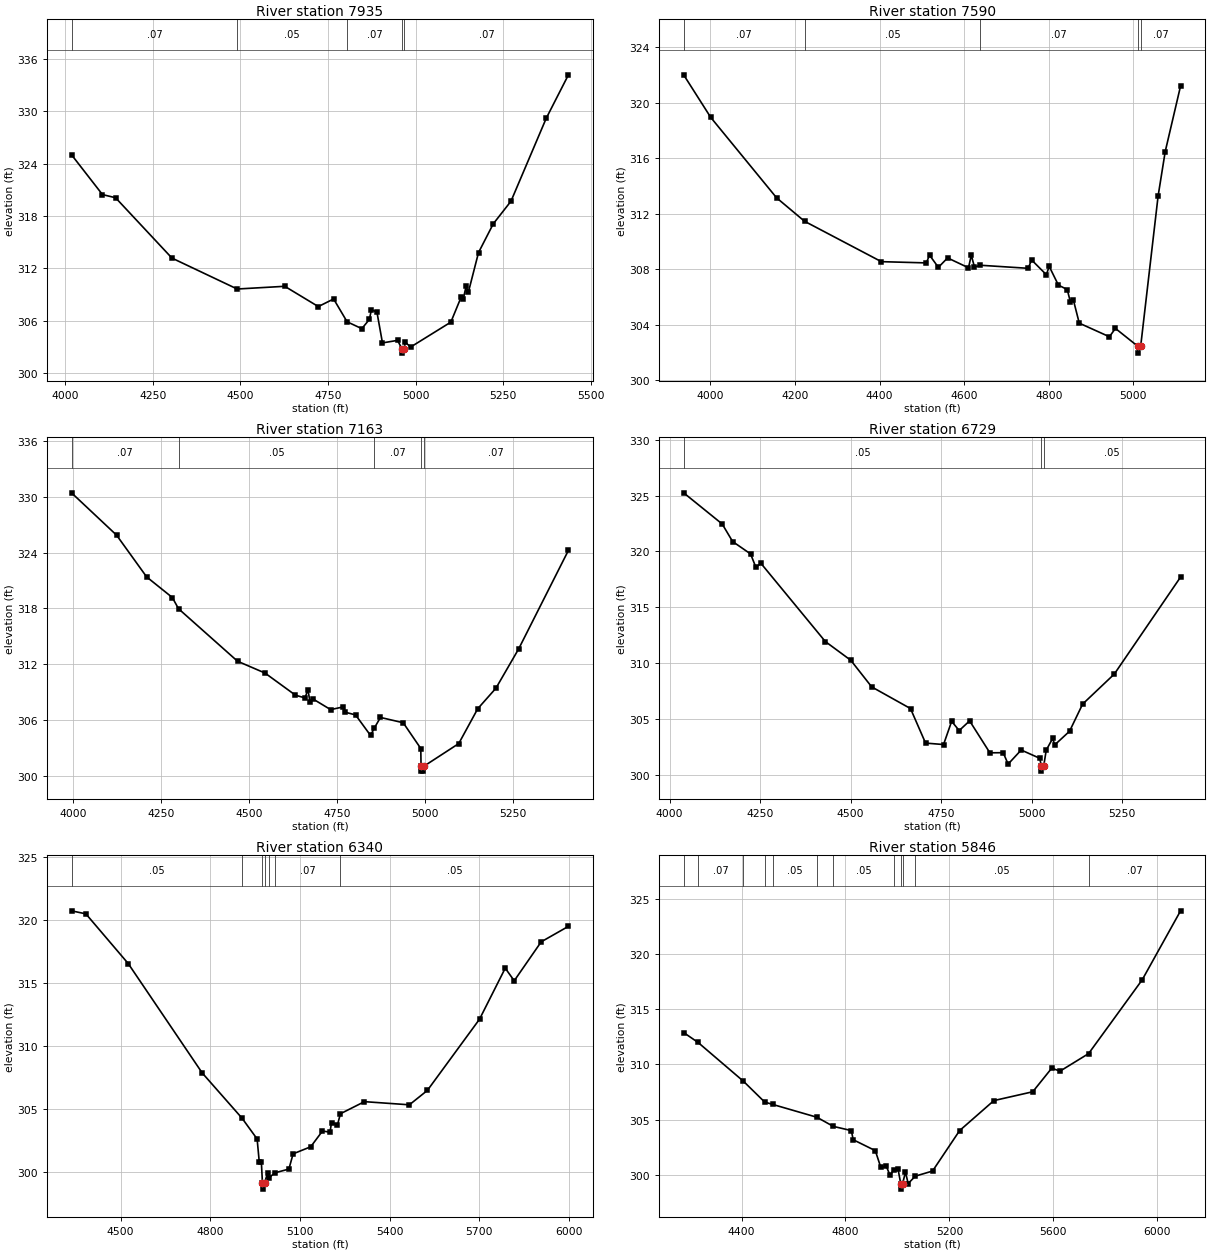
Type RM Length L Ch R = 1 ,7935    ,345,345,345
BEGIN DESCRIPTION:
Stream0653 16.0
END DESCRIPTION:
XS GIS Cut Line= 3
      2374024.96     13642074.98      2373130.73     13641559.56
      2372824.98     13641324.99
#Sta/Elev= 30
  4018.5  325.01  4106.8  320.45  4144.1  320.09    4305  313.18  4491.1  309.64
  4626.8  309.95  4722.5  307.63  4766.2   308.5  4804.6  305.89  4846.6   305.1
  4868.2  306.16  4873.9  307.26  4889.7  307.01  4905.5  303.47  4948.6  303.76
    4961   302.8  4961.5   302.3  4967.9   302.8  4970.2  303.55    4986     303
  5100.6  305.85  5129.6  308.68  5135.9  308.46  5144.1  309.96  5150.4  309.25
  5179.5  313.81  5221.7  317.11  5272.1  319.69  5372.6  329.18    5436  334.16
#Mann= 5 ,-1 , 0
  4018.5     .07       0  4491.1     .05       0  4804.6     .07       0
    4961     .07       0  4967.9     .07       0
Bank Sta=4961,4967.9
XS Rating Curve= 0 ,0
Exp/Cntr=0.3,0.1

Type RM Length L Ch R = 1 ,7590    ,427,427,427
BEGIN DESCRIPTION:
Stream0653 15.0
END DESCRIPTION:
XS GIS Cut Line= 3
      2373974.99     13641974.99        2373175.       13641275.
      2373075.01       13641225.
#Sta/Elev= 30
  3936.7  322.01  4000.8  318.94  4156.4  313.15  4222.5  311.46  4404.1  308.55
  4510.4  308.46    4518  309.02  4538.9  308.14  4560.7  308.82  4610.1  308.11
  4616.7  309.01  4624.3  308.16  4638.5  308.29  4751.5  308.07  4759.1  308.68
  4794.2  307.61  4800.9  308.21  4822.7  306.86  4843.6  306.54  4851.2  305.62
  4857.8  305.82    4872  304.12  4943.2  303.14  4957.5  303.74  5010.2  302.46
  5010.7  301.96  5017.2  302.46  5058.4  313.28  5075.2  316.48  5111.5  321.21
#Mann= 5 ,-1 , 0
  3936.7     .07       0  4222.5     .05       0  4638.5     .07       0
  5010.2     .07       0  5017.2     .07       0
Bank Sta=5010.2,5017.2
XS Rating Curve= 0 ,0
Exp/Cntr=0.3,0.1

Type RM Length L Ch R = 1 ,7163    ,434,434,434
BEGIN DESCRIPTION:
Stream0653 14.0
END DESCRIPTION:
XS GIS Cut Line= 3
      2374325.01     13641675.01        2373525.       13641075.
      2373125.03     13640975.01
#Sta/Elev= 30
  3996.2  330.42  4124.3  325.87  4209.8  321.38  4282.7  319.17  4300.4  317.96
  4468.1  312.32  4546.2  311.05  4632.7  308.67  4659.8  308.38  4668.1  309.26
  4674.3  307.89  4682.7  308.26  4732.7  307.12  4768.1  307.41  4774.3  306.84
  4803.5  306.55  4846.2  304.34  4856.3  305.11  4874.3  306.28  4938.9  305.71
  4988.9  302.94  4989.6  301.01  4990.1  300.51  4996.1  300.51  4996.6  301.01
  5096.7  303.47  5150.8  307.22  5202.4  309.42  5266.8  313.63  5408.5  324.24
#Mann= 5 ,-1 , 0
  3996.2     .07       0  4300.4     .05       0  4856.3     .07       0
  4989.6     .07       0  4996.6     .07       0
Bank Sta=4989.6,4996.6
XS Rating Curve= 0 ,0
Exp/Cntr=0.3,0.1

Type RM Length L Ch R = 1 ,6729    ,389,389,389
BEGIN DESCRIPTION:
Stream0653 13.0
END DESCRIPTION:
XS GIS Cut Line= 3
        2374375.       13641275.        2373625.       13640675.
      2373224.98       13640775.
#Sta/Elev= 30
    4039  325.25  4145.5  322.46  4174.3  320.89  4223.9  319.78  4238.3   318.6
  4252.7  318.93  4430.4  311.94  4500.8  310.26  4558.5  307.88  4665.7  305.94
  4707.3  302.85    4757  302.72  4779.4   304.8  4800.2  303.97    4829  304.84
    4885  301.98  4921.8  301.99  4935.4  300.97  4971.5  302.23  5022.7  301.49
  5026.9  300.84  5027.4  300.34  5033.9  300.84  5040.7  302.22  5058.7  303.28
  5063.9  302.68  5105.1  303.91  5141.2  306.34  5228.8  309.03  5411.8  317.71
#Mann= 3 ,-1 , 0
    4039     .05       0  5026.9     .05       0  5033.9     .05       0
Bank Sta=5026.9,5033.9
XS Rating Curve= 0 ,0
Exp/Cntr=0.3,0.1

Type RM Length L Ch R = 1 ,6340    ,494,494,494
BEGIN DESCRIPTION:
XS7407
END DESCRIPTION:
XS GIS Cut Line= 3
      2374401.56     13640976.22      2373828.65     13640424.15
      2372964.03     13640372.06
#Sta/Elev= 30
  4335.9  320.74  4383.9   320.5  4525.4  316.56  4772.9  307.88  4906.1  304.29
  4956.6  302.64  4963.8  300.81  4970.7  300.85  4974.4  299.16  4974.9  298.66
  4981.5  299.16  4992.1  299.97  4997.2  299.58  5015.5  299.95  5062.8  300.25
    5077  301.46  5135.8  302.02  5175.2  303.27  5200.4  303.18  5205.4  303.94
  5225.3  303.75  5235.1  304.64  5315.5   305.6  5465.8  305.35  5525.9  306.49
  5700.3  312.14  5786.4  316.19  5816.4  315.19  5906.6  318.28  5997.7  319.51
#Mann= 7 ,-1 , 0
  4335.9     .05       0  4906.1     .07       0  4974.4     .05       0
  4981.5     .07       0  4997.2     .05       0  5015.5     .07       0
  5235.1     .05       0
Bank Sta=4974.4,4981.5
XS Rating Curve= 0 ,0
Exp/Cntr=0.3,0.1

Type RM Length L Ch R = 1 ,5846    ,441,441,441
BEGIN DESCRIPTION:
Stream0653 12.0
END DESCRIPTION:
XS GIS Cut Line= 3
      2374474.45     13640637.66        2373875.       13640075.
      2372829.35      13639768.1
#Sta/Elev= 30
  4177.4  312.89    4233  311.99  4407.6  308.47    4489  306.59  4520.1  306.37
    4690  305.21  4753.2  304.38  4822.5     304  4829.8  303.17  4914.8  302.18
  4935.8  300.67  4957.3  300.76  4971.4  299.94  4986.2  300.46  5002.1  300.53
  5012.6  299.19  5013.1  298.69  5019.9  299.19  5030.8  300.24  5041.2   299.2
  5069.1  299.87    5135  300.33  5239.2     304    5371  306.72  5520.6  307.52
  5593.6  309.66  5625.5  309.39  5735.4  310.98  5941.6  317.67  6089.3  323.93
#Mann= 12 ,-1 , 0
  4177.4     .05       0    4233     .07       0  4407.6     .05       0
    4489     .07       0  4520.1     .05       0    4690     .07       0
  4753.2     .05       0  4986.2     .12       0  5012.6     .07       0
  5019.9     .12       0  5069.1     .05       0  5735.4     .07       0
Bank Sta=5012.6,5019.9
XS Rating Curve= 0 ,0
Exp/Cntr=0.3,0.1

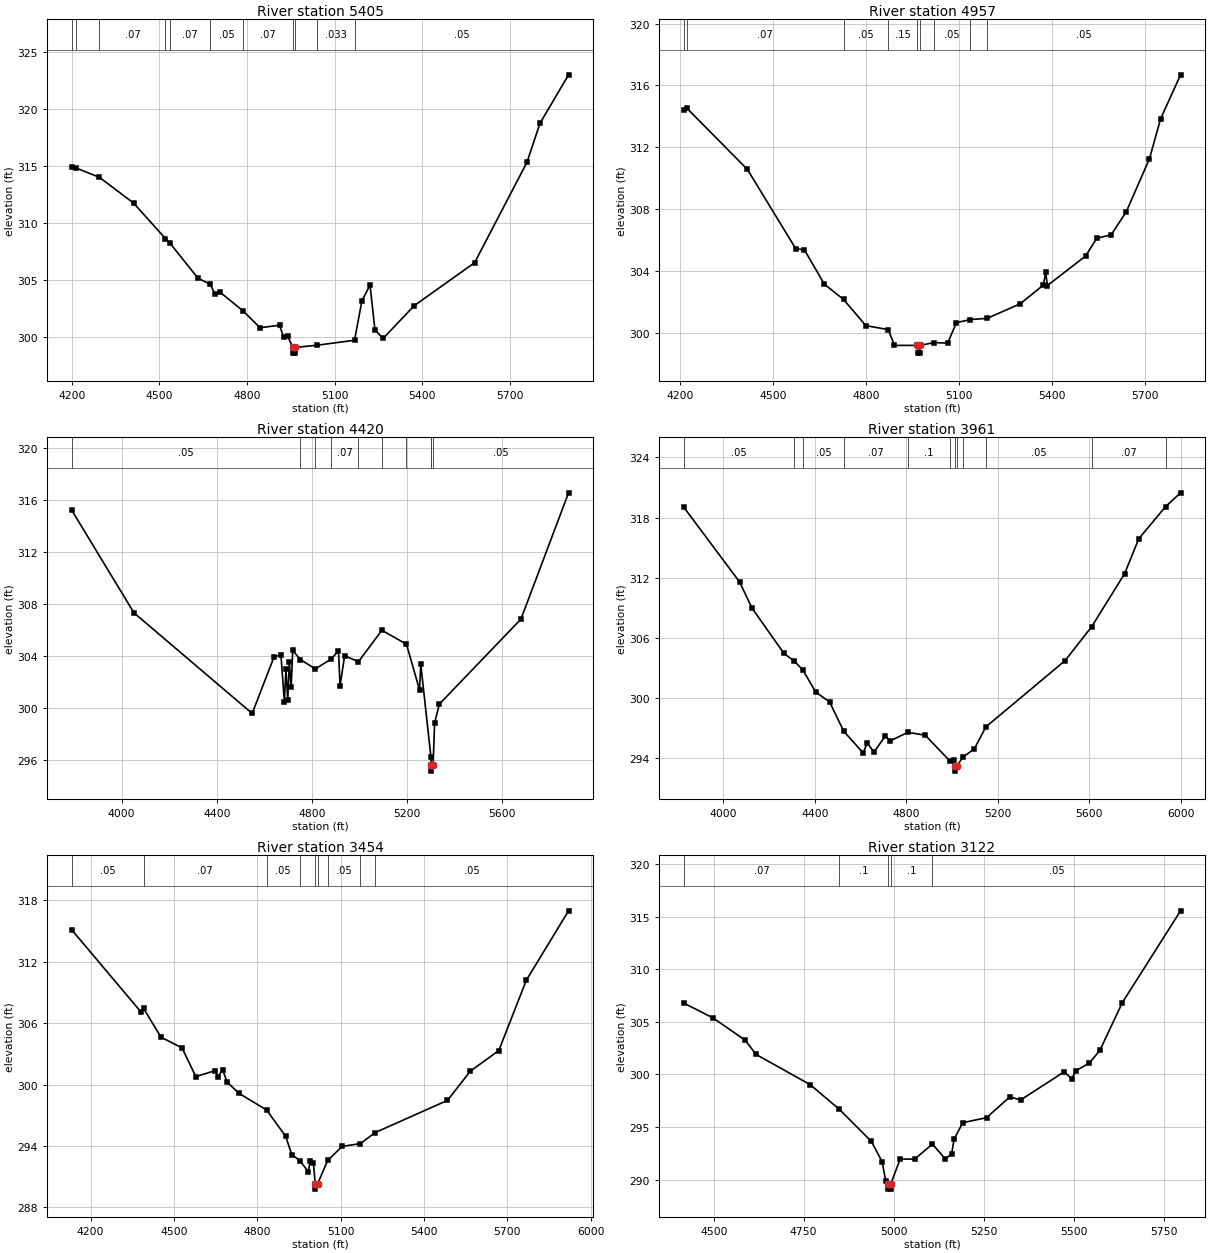
Type RM Length L Ch R = 1 ,5405    ,448,448,448
BEGIN DESCRIPTION:
Stream0653 11.0
END DESCRIPTION:
XS GIS Cut Line= 3
      2374724.97     13640124.98        2374025.       13639725.
      2373225.01     13639325.01
#Sta/Elev= 30
  4199.6  314.93  4215.1  314.83  4295.3  314.01  4411.9  311.75  4520.9  308.64
  4536.6  308.23  4632.2  305.16  4674.2  304.62  4691.2  303.74  4706.3  303.96
  4786.4  302.29  4844.5  300.81  4911.5  301.03  4925.2  299.97  4938.8   300.1
  4956.5  299.08    4957  298.58  4963.8  298.58  4964.3  299.08  5038.6  299.27
    5168  299.71  5193.1  303.17    5221  304.56  5237.8  300.62  5265.7  299.87
  5371.9  302.74  5578.8  306.52  5757.7  315.32  5802.4  318.75  5900.2  323.01
#Mann= 11 ,-1 , 0
  4199.6     .07       0  4215.1     .05       0  4295.3     .07       0
  4520.9     .05       0  4536.6     .07       0  4674.2     .05       0
  4786.4     .07       0  4956.5     .07       0  4964.3     .07       0
  5038.6    .033       0    5168     .05       0
Bank Sta=4956.5,4964.3
XS Rating Curve= 0 ,0
Exp/Cntr=0.3,0.1

Type RM Length L Ch R = 1 ,4957    ,537,537,537
BEGIN DESCRIPTION:
Stream0653 10.0
END DESCRIPTION:
XS GIS Cut Line= 3
      2374675.02     13640025.03        2374175.       13639425.
      2373374.98     13639224.99
#Sta/Elev= 30
  4210.3  314.39  4221.6  314.52  4416.7  310.57  4572.9  305.44  4600.8  305.37
  4665.3  303.15  4727.2  302.16  4799.4  300.47  4871.7  300.21  4891.8  299.19
    4966  299.19  4966.5  298.69  4973.3  298.69  4973.8  299.19  5019.3  299.37
  5063.5  299.34  5091.9  300.66  5136.6  300.86  5191.2  300.94    5298  301.88
  5372.7  303.09  5380.5  303.92  5385.6  303.06  5509.3  304.97  5545.4  306.12
  5591.8  306.34  5640.7  307.84  5715.5  311.26  5751.6  313.85    5816  316.69
#Mann= 9 ,-1 , 0
  4210.3     .05       0  4221.6     .07       0  4727.2     .05       0
  4871.7     .15       0    4966     .07       0  4973.8     .15       0
  5019.3     .05       0  5136.6     .07       0  5191.2     .05       0
Bank Sta=4966,4973.8
XS Rating Curve= 0 ,0
Exp/Cntr=0.3,0.1

Type RM Length L Ch R = 1 ,4420    ,459,459,459
BEGIN DESCRIPTION:
Stream0653 9.0
END DESCRIPTION:
XS GIS Cut Line= 5
      2375054.59     13639926.35      2374322.72     13639051.05
      2374146.04     13639054.74      2373984.38     13639106.21
      2373384.96     13639172.41
#Sta/Elev= 30
  3789.4  315.25  4052.2  307.32  4549.3  299.58  4641.7  303.96  4670.3  304.05
  4684.6  300.49  4691.1  302.98  4698.9  300.62  4705.4  303.56  4713.2  301.59
  4719.8  304.44  4751.4  303.73  4814.9  303.01  4881.2  303.76  4912.2   304.4
  4918.8  301.71  4938.1  304.02  4996.2  303.56  5094.7  305.98  5198.2  304.91
  5253.1  301.39  5258.3  303.37  5301.2  296.19  5302.3  295.64  5302.8  295.14
  5310.2  295.64  5316.4  298.84  5336.5   300.3  5679.6  306.84  5879.8  316.56
#Mann= 10 ,-1 , 0
  3789.4     .05       0  4751.4     .15       0  4814.9      .1       0
  4881.2     .07       0  4996.2     .15       0  5094.7     .05       0
  5198.2      .1       0  5301.2     .05       0  5302.3     .07       0
  5310.2     .05       0
Bank Sta=5302.3,5310.2
XS Rating Curve= 0 ,0
Exp/Cntr=0.3,0.1

Type RM Length L Ch R = 1 ,3961    ,507,507,507
BEGIN DESCRIPTION:
Stream0653 8.0
END DESCRIPTION:
XS GIS Cut Line= 3
       2375308.3     13639157.69      2374149.87      13638712.7
      2373223.08     13638628.12
#Sta/Elev= 30
  3826.8  319.07  4071.4  311.59    4126  308.98  4265.4  304.46  4310.9  303.68
  4348.2  302.81  4404.7  300.59  4464.7  299.63  4526.9  296.69  4612.3  294.52
  4628.8  295.56  4658.8  294.61  4708.1  296.22  4730.2  295.74  4807.1  296.59
  4882.8   296.3  4990.2  293.74  5008.7  293.82  5012.8  293.22  5013.3  292.72
  5020.7  293.22  5048.2  294.13  5097.6  294.95  5147.8  297.13  5494.4  303.75
  5610.4  307.14    5754  312.41  5815.7  315.89  5933.1   319.1  5998.4  320.47
#Mann= 12 ,-1 , 0
  3826.8     .05       0  4310.9     .07       0  4348.2     .05       0
  4526.9     .07       0  4807.1      .1       0  4990.2     .05       0
  5012.8     .05       0  5020.7     .05       0  5048.2      .1       0
  5147.8     .05       0  5610.4     .07       0  5933.1     .05       0
Bank Sta=5012.8,5020.7
XS Rating Curve= 0 ,0
Exp/Cntr=0.3,0.1

Type RM Length L Ch R = 1 ,3454    ,332,332,332
BEGIN DESCRIPTION:
Stream0653 7.0
END DESCRIPTION:
XS GIS Cut Line= 3
      2375275.21     13638955.41      2374521.32      13638532.5
      2373620.27     13638326.54
#Sta/Elev= 30
  4131.4  315.14  4382.9  307.04  4390.5  307.44  4453.7  304.62    4529  303.58
  4578.8  300.77  4647.6  301.35  4659.1  300.76  4675.1  301.46    4691  300.25
  4734.4  299.13  4833.1  297.52  4902.2  294.94  4923.8  293.16  4953.4  292.56
  4983.2  291.49  4990.8  292.56  5002.1  292.31  5008.4  290.28  5008.9  289.78
  5016.7  290.28  5053.3  292.58  5104.9  293.95    5171  294.23  5224.4  295.31
  5484.4  298.45  5566.5   301.3  5669.1  303.32  5768.2  310.19  5920.1  316.97
#Mann= 9 ,-1 , 0
  4131.4     .05       0  4390.5     .07       0  4833.1     .05       0
  4953.4      .1       0  5008.4     .07       0  5016.7      .1       0
  5053.3     .05       0    5171      .1       0  5224.4     .05       0
Bank Sta=5008.4,5016.7
XS Rating Curve= 0 ,0
Exp/Cntr=0.3,0.1

Type RM Length L Ch R = 1 ,3122    ,351,351,351
BEGIN DESCRIPTION:
Stream0653 6.0
END DESCRIPTION:
XS GIS Cut Line= 3
      2375106.08     13638264.03      2374399.96     13638227.25
      2373775.03     13637975.01
#Sta/Elev= 30
  4416.2  306.79    4498  305.37  4587.5  303.25  4617.6   301.9  4767.8  299.03
  4848.8  296.69    4938  293.63    4968   291.7    4978  289.87  4983.9  289.59
  4984.4  289.09  4991.7  289.09  4992.2  289.59  5018.1  291.95  5058.1  291.94
  5107.7  293.37  5143.7  291.96    5161  292.44  5167.9  293.83    5192  295.41
    5258  295.88  5322.7  297.86    5353  297.57  5473.7  300.24  5495.3  299.58
  5506.1  300.35  5543.6  301.07  5573.1  302.29  5635.5  306.83  5797.2  315.55
#Mann= 5 ,-1 , 0
  4416.2     .07       0  4848.8      .1       0  4983.9     .07       0
  4992.2      .1       0  5107.7     .05       0
Bank Sta=4983.9,4992.2
XS Rating Curve= 0 ,0
Exp/Cntr=0.3,0.1

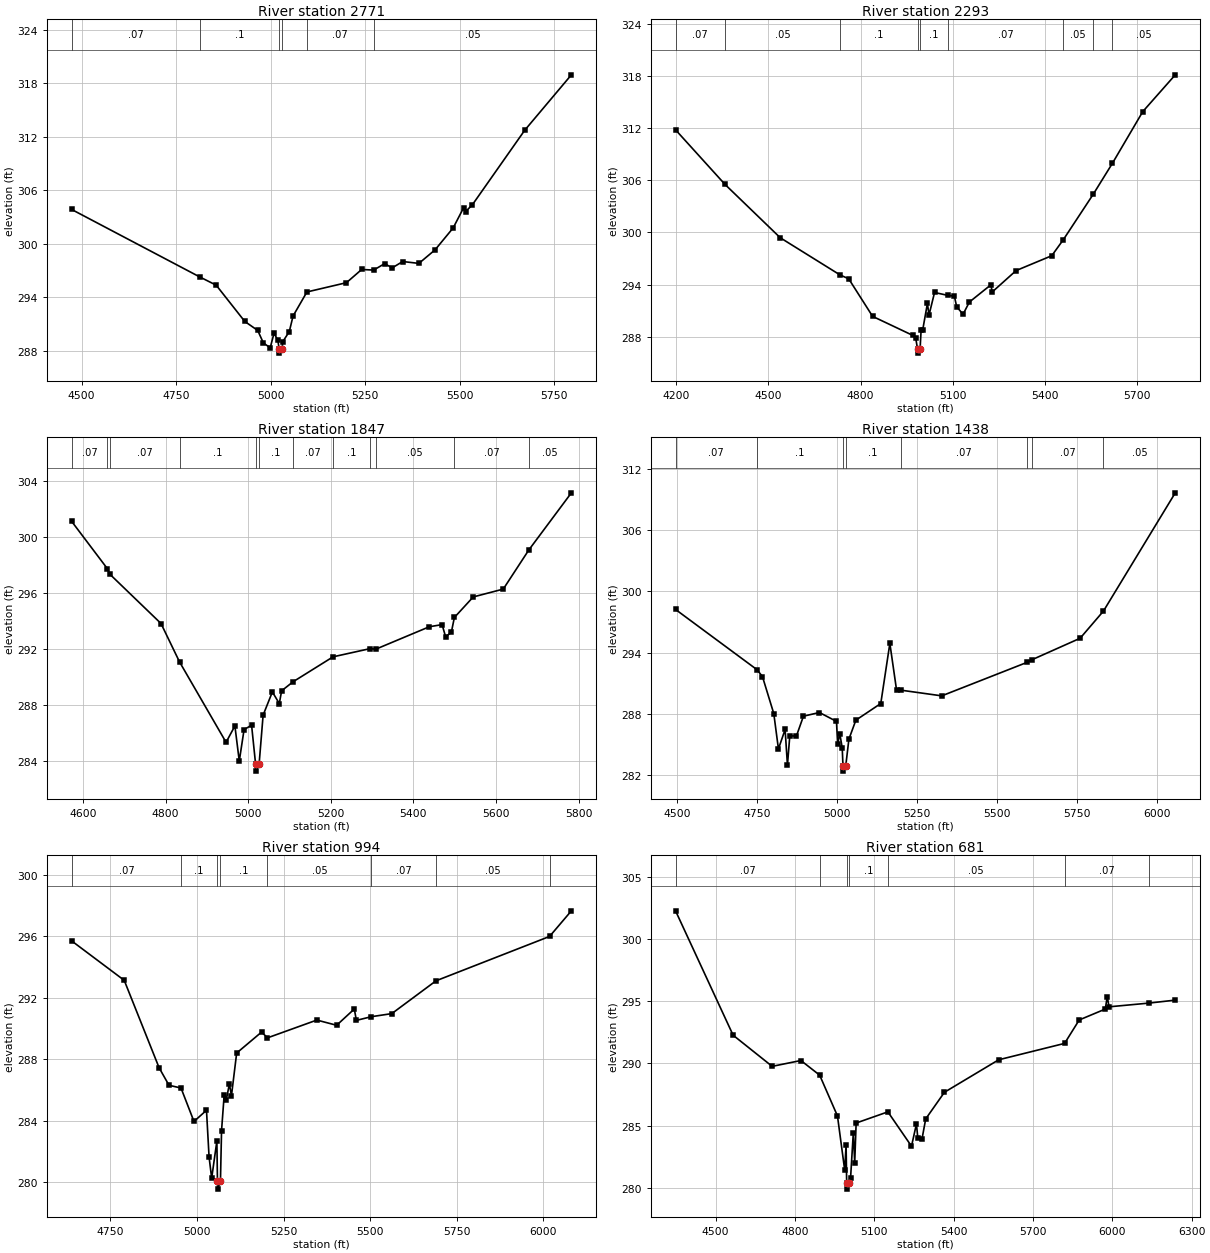
Type RM Length L Ch R = 1 ,2771    ,478,478,478
BEGIN DESCRIPTION:
Stream0653 5.0
END DESCRIPTION:
XS GIS Cut Line= 3
      2374975.01     13638225.01        2374525.       13637975.
      2373725.02       13637875.
#Sta/Elev= 30
  4473.9  303.85  4812.2   296.3    4856  295.37  4931.5  291.31  4965.8   290.3
  4980.7   288.9  4998.8  288.36  5008.9     290  5018.9   289.2  5022.3  288.26
  5022.8  287.76  5030.6  288.26  5031.5  289.01  5049.2  290.17  5059.2  291.92
  5095.8  294.61  5200.3  295.65  5240.6  297.13  5272.2  297.06  5301.1  297.78
  5321.3  297.31    5349  298.02  5391.8  297.81  5434.6  299.33  5482.5  301.79
  5510.2  304.06  5515.3  303.62  5532.9  304.36  5671.5  312.72  5794.9  318.93
#Mann= 6 ,-1 , 0
  4473.9     .07       0  4812.2      .1       0  5022.3     .07       0
  5030.6      .1       0  5095.8     .07       0  5272.2     .05       0
Bank Sta=5022.3,5030.6
XS Rating Curve= 0 ,0
Exp/Cntr=0.3,0.1

Type RM Length L Ch R = 1 ,2293    ,446,446,446
BEGIN DESCRIPTION:
Stream0653 4.0
END DESCRIPTION:
XS GIS Cut Line= 3
      2375325.02       13637625.        2374525.       13637575.
        2373725.       13637775.
#Sta/Elev= 30
  4197.9  311.81  4358.8  305.53  4538.6  299.39  4732.7  295.12  4761.5  294.66
  4839.2  290.34  4969.4  288.16  4979.4  287.84  4985.3  286.61  4985.8  286.11
  4993.7  286.61    4997  288.76  5002.1  288.76  5017.5  291.83  5022.7  290.49
  5040.7  293.09  5084.8  292.75  5105.1  292.67  5112.9  291.44  5133.5  290.58
  5154.1  291.99  5223.7  293.96  5228.8  293.16  5306.1  295.61  5422.1  297.32
  5459.7  299.16  5557.4  304.41  5619.4  307.95  5718.4  313.91  5824.1  318.14
#Mann= 9 ,-1 , 0
  4197.9     .07       0  4358.8     .05       0  4732.7      .1       0
  4985.3     .07       0  4993.7      .1       0  5084.8     .07       0
  5459.7     .05       0  5557.4     .07       0  5619.4     .05       0
Bank Sta=4985.3,4993.7
XS Rating Curve= 0 ,0
Exp/Cntr=0.3,0.1

Type RM Length L Ch R = 1 ,1847    ,409,409,409
BEGIN DESCRIPTION:
Stream0653 3.0
END DESCRIPTION:
XS GIS Cut Line= 3
      2375074.99       13637375.        2374675.       13637225.
      2373975.02     13637574.99
#Sta/Elev= 30
  4572.8  301.14    4659  297.77  4664.7  297.38  4789.1  293.84  4833.9   291.1
  4946.6  285.35    4968  286.52  4978.6  284.01  4990.2  286.26  5008.4  286.57
  5018.1  283.79  5018.6  283.29  5026.6  283.79  5036.3  287.29  5058.7  288.95
  5075.5  288.12  5081.1  289.03  5108.5  289.67  5205.7  291.46  5294.6  292.04
  5309.5  292.01  5438.8  293.61  5469.6  293.76    5478   292.9  5491.9   293.2
  5499.3  294.27    5545  295.74  5617.7   296.3  5679.4  299.09  5782.6  303.18
#Mann= 12 ,-1 , 0
  4572.8     .07       0    4659     .05       0  4664.7     .07       0
  4833.9      .1       0  5018.1     .07       0  5026.6      .1       0
  5108.5     .07       0  5205.7      .1       0  5294.6     .07       0
  5309.5     .05       0  5499.3     .07       0  5679.4     .05       0
Bank Sta=5018.1,5026.6
XS Rating Curve= 0 ,0
Exp/Cntr=0.3,0.1

Type RM Length L Ch R = 1 ,1438    ,444,444,444
BEGIN DESCRIPTION:
Stream0653 2.0
END DESCRIPTION:
XS GIS Cut Line= 3
      2375074.97     13637174.98        2374675.       13636875.
      2373874.99     13637575.01
#Sta/Elev= 30
  4495.2  298.24  4750.1  292.34    4767  291.67  4802.5  288.04    4817  284.58
  4837.9  286.49  4845.2  282.99  4852.5  285.86  4873.3  285.85  4895.2  287.79
  4945.2  288.15  4998.5  287.28  5002.3  285.04  5008.9  286.08  5016.5  284.69
  5018.9  282.91  5019.4  282.41  5027.5  282.91  5037.4  285.54  5059.2   287.4
  5137.1  289.03  5165.5  294.92  5186.4  290.36  5199.5  290.34  5327.8  289.78
  5594.6  293.06  5610.2  293.32  5760.6  295.42  5833.5  298.08  6058.2  309.66
#Mann= 8 ,-1 , 0
  4495.2     .07       0  4750.1      .1       0  5018.9     .07       0
  5027.5      .1       0  5199.5     .07       0  5594.6     .05       0
  5610.2     .07       0  5833.5     .05       0
Bank Sta=5018.9,5027.5
XS Rating Curve= 0 ,0
Exp/Cntr=0.3,0.1

Type RM Length L Ch R = 1 ,994     ,313,313,313
BEGIN DESCRIPTION:
Stream0653 1.0
END DESCRIPTION:
XS GIS Cut Line= 3
      2375024.98     13636724.99        2374725.       13636525.
        2373825.       13637125.
#Sta/Elev= 30
  4638.5  295.71  4790.2  293.14  4890.9  287.44  4919.4   286.3  4954.1  286.12
  4991.5  283.94  5027.6  284.67  5035.1  281.62  5042.6  280.24  5057.6  282.67
  5059.3  280.03  5059.8  279.53  5067.9  280.03  5071.1  283.35  5078.7  285.67
  5084.7  285.34  5093.7  286.39  5099.7  285.62  5114.7   288.4  5186.8  289.77
  5203.6  289.39  5346.1  290.55  5403.2  290.21  5454.2  291.27  5460.2  290.53
  5503.6  290.77  5562.4  290.97  5690.1  293.11  6017.7     296  6080.7  297.67
#Mann= 8 ,-1 , 0
  4638.5     .07       0  4954.1      .1       0  5059.3     .07       0
  5067.9      .1       0  5203.6     .05       0  5503.6     .07       0
  5690.1     .05       0  6017.7     .07       0
Bank Sta=5059.3,5067.9
XS Rating Curve= 0 ,0
Exp/Cntr=0.3,0.1

Type RM Length L Ch R = 1 ,681     ,419,419,419
BEGIN DESCRIPTION:
XS7406
END DESCRIPTION:
XS GIS Cut Line= 4
      2375437.08     13636425.21      2374936.89     13636237.64
      2374569.13     13636351.65      2373859.64     13637013.35
#Sta/Elev= 30
  4348.7  302.31  4566.4  292.28    4714  289.77  4822.7  290.24  4893.6  289.06
  4960.9  285.77  4988.3   281.4  4993.5  283.44  4995.7  280.37  4996.2  279.87
  5004.3  280.37  5010.5  280.78  5020.8  284.42  5026.1  282.01  5031.5   285.2
  5151.5   286.1  5240.8  283.33  5259.5  285.13  5264.7  283.98  5280.3  283.89
  5294.5  285.53  5365.3  287.68  5570.5   290.3  5819.6  291.62  5874.9  293.51
  5973.5  294.39  5980.9  295.39  5987.7  294.57  6138.3  294.87  6238.1  295.11
#Mann= 7 ,-1 , 0
  4348.7     .07       0  4893.6      .1       0  4995.7     .07       0
  5004.3      .1       0  5151.5     .05       0  5819.6     .07       0
  6138.3     .05       0
Bank Sta=4995.7,5004.3
XS Rating Curve= 0 ,0
Exp/Cntr=0.3,0.1

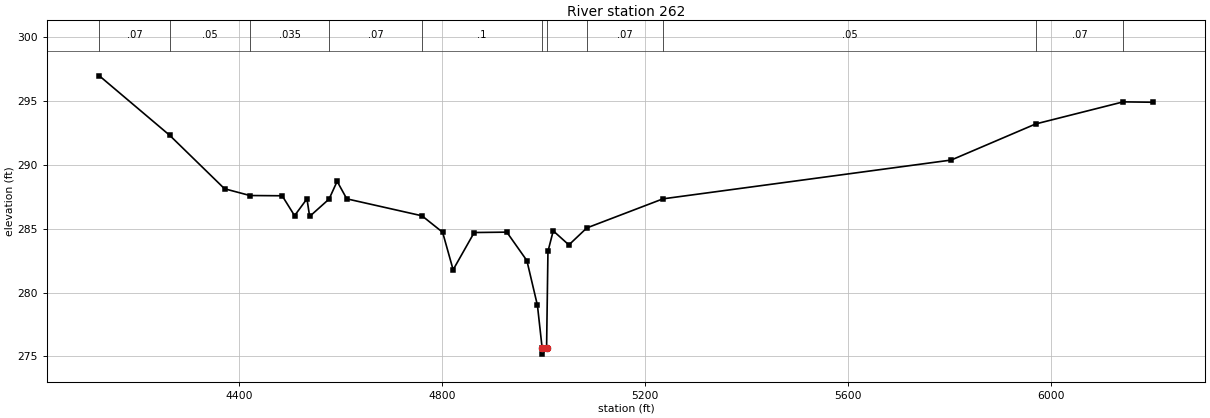
Type RM Length L Ch R = 1 ,262     ,0,0,0
BEGIN DESCRIPTION:
XS7405
END DESCRIPTION:
XS GIS Cut Line= 4
      2375459.14     13636020.67       2374984.7      13635833.1
      2374598.55     13635939.75      2373925.52     13636888.61
#Sta/Elev= 30
  4125.3  296.99  4263.8  292.33  4371.8  288.14  4421.8  287.61  4485.3  287.59
  4509.7  286.03  4534.1  287.35  4539.4  285.97  4577.6  287.33  4593.5  288.72
  4612.5  287.35  4760.6  286.02  4801.2  284.73  4821.9  281.79  4863.4  284.71
  4927.6  284.74  4967.1  282.51  4987.9     279  4997.1  275.68  4997.6  275.18
  5005.9  275.68  5008.6  283.23    5019  284.84  5049.8  283.74  5085.1  285.07
  5235.1  287.35  5802.6  290.39    5969  293.22  6141.3  294.95  6199.4  294.92
#Mann= 11 ,-1 , 0
  4125.3     .07       0  4263.8     .05       0  4421.8    .035       0
  4577.6     .07       0  4760.6      .1       0  4997.1     .07       0
  5005.9      .1       0  5085.1     .07       0  5235.1     .05       0
    5969     .07       0  6141.3     .05       0
Bank Sta=4997.1,5005.9
XS Rating Curve= 0 ,0
Exp/Cntr=0.3,0.1

Chan Stop Cuts=-1
Use User Specified Reach Order=0
Composite Channel Slope=5