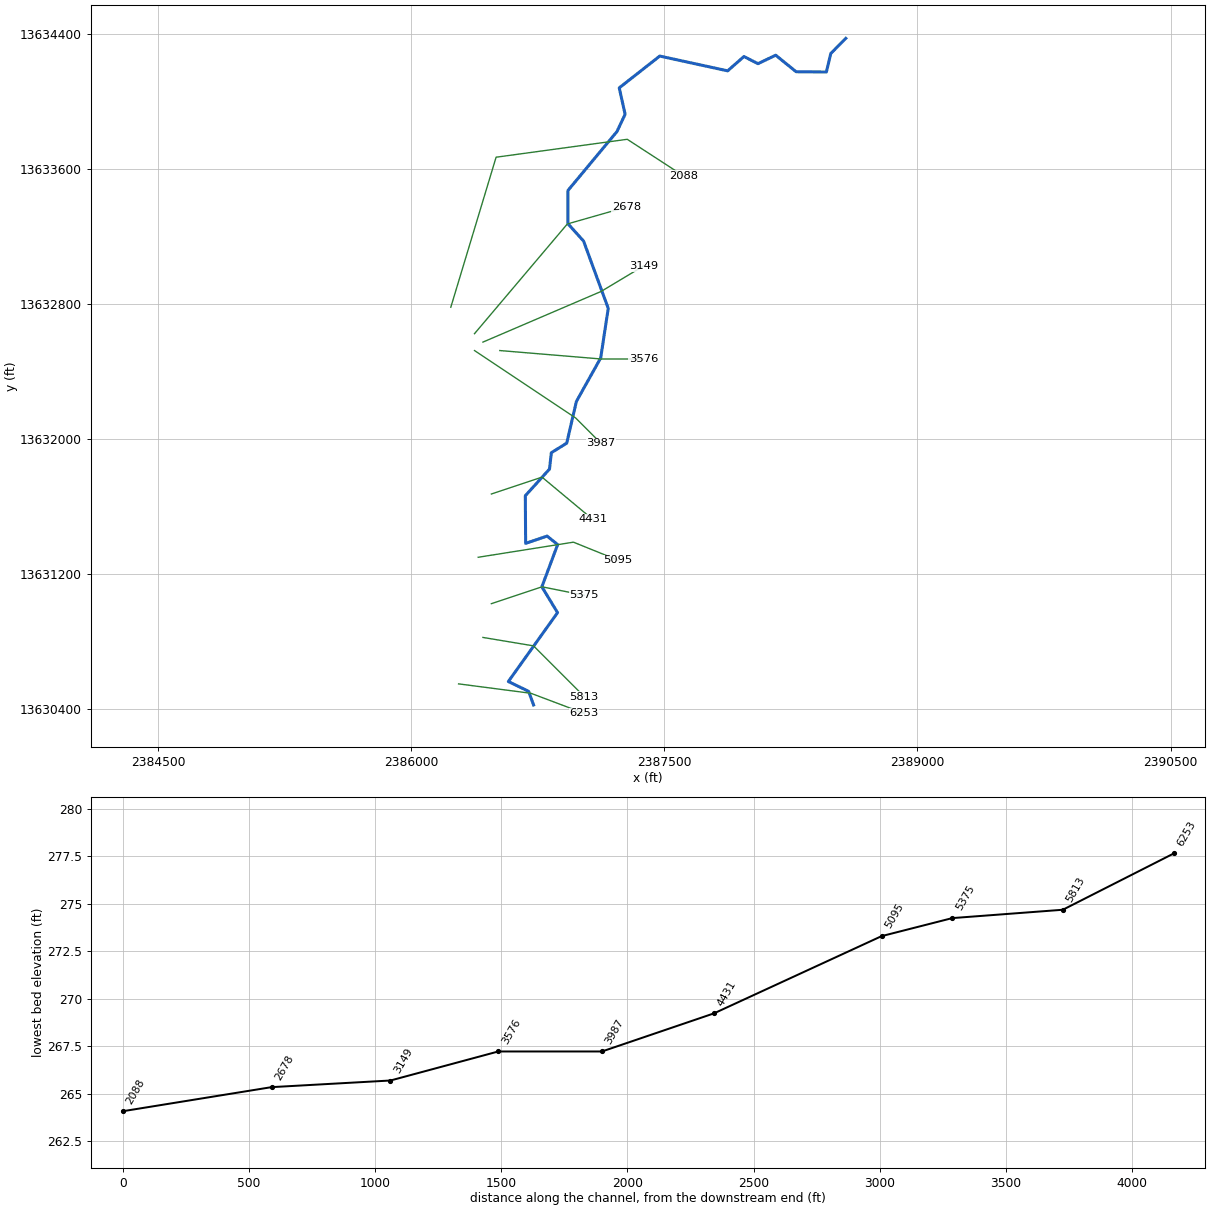
--- Stream0655.prj (project) ---

Proj Title=Stream0655 Base Level Engineering
Current Plan=p01
Default Exp/Contr=0.3,0.1
English Units
Geom File=g01
Flow File=f01
Plan File=p01
BEGIN DESCRIPTION:
Stream0655
END DESCRIPTION:

--- Stream0655.p01 (plan) ---

Plan Title=Multiple Run
Short Identifier=Multiple
Geom File=g01
Flow File=f01
Subcritical Flow
K Sum by GR= 0
Std Step Tol= 0.01
Critical Tol= 0.01
Num of Std Step Trials= 20
Max Error Tol= 0.3
Flow Tol Ratio= 0.001
Split Flow NTrial= 30
Split Flow Tol= 0.02
Split Flow Ratio= 0.02
Log Output Level= 0
Friction Slope Method= 1
Unsteady Friction Slope Method= 2
Unsteady Bridges Friction Slope Method= 1
Parabolic Critical Depth
Global Vel Dist=  1 , 1 , 1
Global Log Level= 0
CheckData=True
Encroach Param= -1, 0, 0, 0
BEGIN DESCRIPTION:
Multiple Run
END DESCRIPTION:

--- Stream0655.f01 (steady flow) ---

Flow Title=Multiple
Number of Profiles=7
Profile Names=10-year,25-year,50-year,1pct_min,100-year,1pct_plu,500-year
River Rch & RM= Stream0655,Reach-1,6253
     636    1035    1398     915    1825    3642    3085
River Rch & RM= Stream0655,Reach-1,3149
     618    1000    1344     875    1746    3484    2922
Boundary for River Rch & Prof#=Stream0655,Reach-1,1
Up Type=0
Dn Type=3
Dn Slope=0.005
Boundary for River Rch & Prof#=Stream0655,Reach-1,2
Up Type=0
Dn Type=3
Dn Slope=0.005
Boundary for River Rch & Prof#=Stream0655,Reach-1,3
Up Type=0
Dn Type=3
Dn Slope=0.005
Boundary for River Rch & Prof#=Stream0655,Reach-1,4
Up Type=0
Dn Type=3
Dn Slope=0.005
Boundary for River Rch & Prof#=Stream0655,Reach-1,5
Up Type=0
Dn Type=3
Dn Slope=0.005
Boundary for River Rch & Prof#=Stream0655,Reach-1,6
Up Type=0
Dn Type=3
Dn Slope=0.005
Boundary for River Rch & Prof#=Stream0655,Reach-1,7
Up Type=0
Dn Type=3
Dn Slope=0.005

--- Stream0655.g01 (geometry) ---

Geom Title=Existing Conditions

River Reach=Stream0655,Reach-1
Reach XY= 30
      2386725.00     13630425.00      2386695.52     13630505.68
      2386575.50     13630563.81      2386867.16     13630971.77
      2386774.15     13631124.99      2386867.78     13631375.38
      2386805.09     13631425.39      2386678.06     13631382.54
      2386676.05     13631664.57      2386819.45     13631822.63
      2386830.29     13631919.51      2386921.45     13631976.30
      2386978.82     13632223.44      2387122.74     13632480.93
      2387167.47     13632775.01      2387021.38     13633173.50
      2386928.55     13633276.47      2386928.74     13633473.48
      2387219.19     13633822.71      2387267.47     13633924.99
      2387232.64     13634081.45      2387472.70     13634269.91
      2387875.10     13634182.34      2387971.59     13634267.15
      2388054.80     13634224.81      2388159.66     13634275.04
      2388280.86     13634177.07      2388460.11     13634175.38
      2388486.09     13634284.99      2388575.00     13634375.00

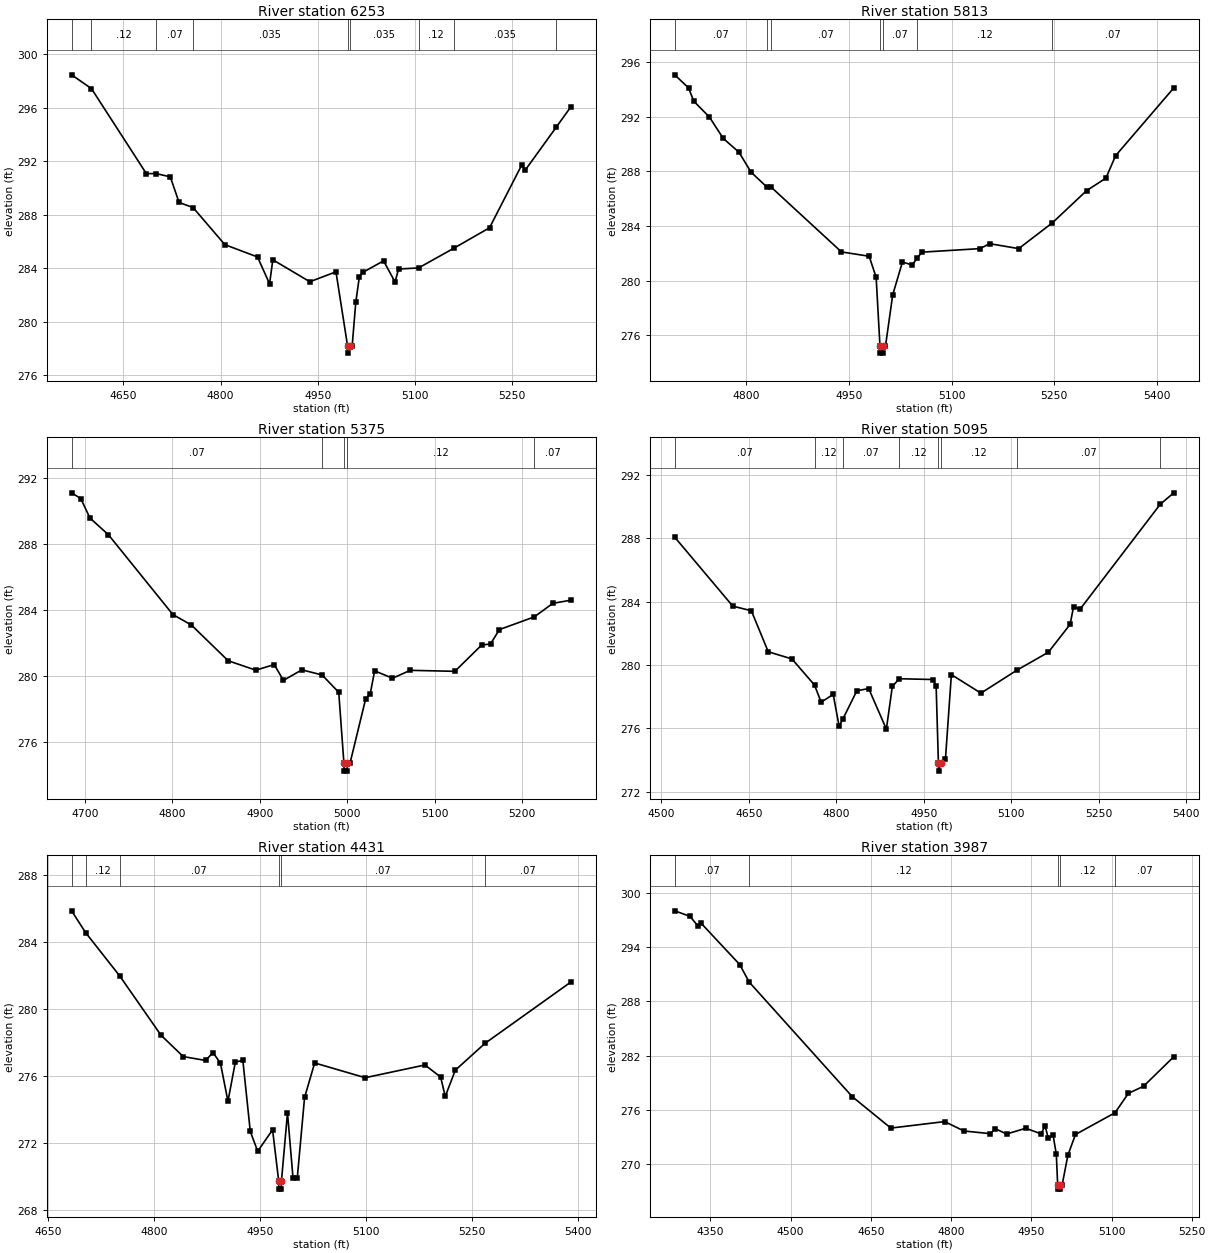
Type RM Length L Ch R = 1,6253,440,440,440
BEGIN DESCRIPTION:
Stream0655 10.0
END DESCRIPTION:
XS GIS Cut Line= 3
      2386280.68     13630549.88      2386709.69     13630493.98
      2387024.96     13630375.02
#Sta/Elev= 30
  4570.3  298.44  4600.9  297.41  4685.6  291.06  4700.5  291.07  4722.5  290.82
  4736.0  288.91  4757.6  288.53  4806.6  285.76  4857.0  284.84  4875.6  282.83
  4880.6  284.63  4937.7  282.99  4978.0  283.73  4996.0  278.16  4996.3  277.66
  5000.0  278.16  5002.9  278.16  5008.6  281.48  5014.1  283.37  5019.4  283.69
  5051.4  284.55  5069.1  282.97  5074.5  283.94  5105.3  284.02  5160.1  285.50
  5214.8  287.02  5264.5  291.71  5269.8  291.32  5318.0  294.55  5339.9  296.03
#Mann=9,-1,0
  4570.3    0.07       0  4600.9    0.12       0  4700.5    0.07       0
  4757.6   0.035       0  4996.0   0.035       0  5000.0   0.035       0
  5105.3    0.12       0  5160.1   0.035       0  5318.0    0.12       0
Bank Sta=4996,5000
Exp/Cntr=0.3,0.1

Type RM Length L Ch R = 1,5813,438,438,438
BEGIN DESCRIPTION:
Stream0655 9.0
END DESCRIPTION:
XS GIS Cut Line= 3
      2386425.04     13630824.99      2386725.00     13630775.00
      2387025.03     13630474.97
#Sta/Elev= 30
  4695.9  295.06  4716.1  294.10  4723.7  293.13  4746.5  291.97  4766.8  290.40
  4789.6  289.40  4807.4  287.93  4830.4  286.85  4836.2  286.86  4939.2  282.10
  4979.7  281.78  4989.9  280.24  4995.5  275.19  4995.7  274.69  4999.2  274.69
  4999.5  275.19  5003.5  275.19  5014.1  278.96  5028.3  281.36  5042.4  281.14
  5050.2  281.66  5056.6  282.08  5141.4  282.34  5155.6  282.70  5198.0  282.34
  5247.2  284.23  5297.0  286.58  5325.3  287.50  5339.4  289.14  5424.3  294.10
#Mann=7,-1,0
  4695.9    0.07       0  4830.4    0.12       0  4836.2    0.07       0
  4995.5    0.05       0  4999.5    0.07       0  5050.2    0.12       0
  5247.2    0.07       0
Bank Sta=4995.5,4999.5
Exp/Cntr=0.3,0.1

Type RM Length L Ch R = 1,5375,280,280,280
BEGIN DESCRIPTION:
Stream0655 8.0
END DESCRIPTION:
XS GIS Cut Line= 3
      2386475.03     13631025.01      2386775.00     13631125.00
      2387024.96     13631075.01
#Sta/Elev= 30
  4684.7  291.12  4695.2  290.77  4705.7  289.59  4726.8  288.58  4800.6  283.74
  4821.7  283.11  4863.9  280.94  4895.5  280.37  4916.6  280.71  4927.1  279.75
  4948.2  280.39  4971.3  280.08  4990.4  279.03  4996.3  274.75  4996.5  274.25
  5000.0  274.25  5000.3  274.75  5003.4  274.75  5021.3  278.65  5026.4  278.93
  5031.5  280.33  5051.9  279.88  5072.3  280.36  5123.3  280.30  5153.9  281.89
  5164.1  281.96  5174.3  282.83  5214.2  283.60  5235.4  284.42  5255.8  284.61
#Mann=5,-1,0
  4684.7    0.07       0  4971.3    0.12       0  4996.3    0.05       0
  5000.3    0.12       0  5214.2    0.07       0
Bank Sta=4996.3,5000.3
Exp/Cntr=0.3,0.1

Type RM Length L Ch R = 1,5095,664,664,664
BEGIN DESCRIPTION:
XS7410
END DESCRIPTION:
XS GIS Cut Line= 3
      2386396.72     13631300.03      2386961.40     13631389.49
      2387224.22     13631283.24
#Sta/Elev= 30
  4523.2  288.06  4622.7  283.71  4654.5  283.42  4683.5  280.83  4724.0  280.38
  4762.8  278.73  4774.1  277.65  4794.8  278.14  4804.9  276.14  4811.4  276.59
  4835.3  278.37  4855.6  278.51  4885.9  275.95  4896.1  278.64  4908.0  279.13
  4966.1  279.08  4971.2  278.64  4975.1  273.80  4975.3  273.30  4979.1  273.80
  4987.2  274.09  4997.3  279.39  5047.9  278.22  5110.1  279.68  5163.5  280.80
  5200.8  282.56  5206.7  283.68  5217.5  283.50  5355.3  290.14  5378.4  290.86
#Mann=8,-1,0
  4523.2    0.07       0  4762.8    0.12       0  4811.4    0.07       0
  4908.0    0.12       0  4975.1    0.05       0  4979.1    0.12       0
  5110.1    0.07       0  5355.3    0.12       0
Bank Sta=4975.1,4979.1
Exp/Cntr=0.3,0.1

Type RM Length L Ch R = 1,4431,444,444,444
BEGIN DESCRIPTION:
Stream0655 7.0
END DESCRIPTION:
XS GIS Cut Line= 3
      2386474.99     13631675.00      2386775.00     13631775.00
      2387074.96     13631525.03
#Sta/Elev= 30
  4683.5  285.84  4703.3  284.54  4751.7  281.95  4810.0  278.42  4841.6  277.14
  4873.2  276.91  4883.8  277.38  4894.3  276.74  4904.9  274.47  4915.4  276.82
  4926.0  276.91  4936.5  272.68  4947.0  271.49  4968.1  272.77  4976.7  269.73
  4976.9  269.23  4980.4  269.23  4980.7  269.73  4989.2  273.78  4997.1  269.87
  5003.0  269.87  5013.4  274.70  5027.7  276.76  5099.3  275.88  5183.9  276.64
  5206.1  275.92  5212.6  274.76  5226.9  276.33  5268.9  277.93  5390.2  281.58
#Mann=6,-1,0
  4683.5    0.07       0  4703.3    0.12       0  4751.7    0.07       0
  4976.7    0.05       0  4980.7    0.07       0  5268.9    0.07       0
Bank Sta=4976.7,4980.7
Exp/Cntr=0.3,0.1

Type RM Length L Ch R = 1,3987,411,411,411
BEGIN DESCRIPTION:
Stream0655 6.0
END DESCRIPTION:
XS GIS Cut Line= 3
      2386375.00     13632525.00      2386975.00     13632125.00
      2387124.97     13631975.03
#Sta/Elev= 30
  4283.2  298.04  4311.7  297.43  4326.8  296.35  4332.8  296.65  4404.9  292.08
  4422.3  290.16  4615.2  277.46  4687.3  273.98  4788.0  274.70  4824.0  273.66
  4873.6  273.36  4882.6  273.92  4903.7  273.32  4939.7  273.96  4968.3  273.34
  4975.8  274.23  4981.8  272.84  4990.8  273.20  4996.8  271.06  4999.3  267.72
  4999.6  267.22  5003.1  267.22  5003.3  267.72  5007.8  267.72  5018.4  270.97
  5032.6  273.27  5106.6  275.68  5131.6  277.83  5159.9  278.61  5216.4  281.88
#Mann=5,-1,0
  4283.2    0.07       0  4422.3    0.12       0  4999.3    0.05       0
  5003.3    0.12       0  5106.6    0.07       0
Bank Sta=4999.3,5003.3
Exp/Cntr=0.3,0.1

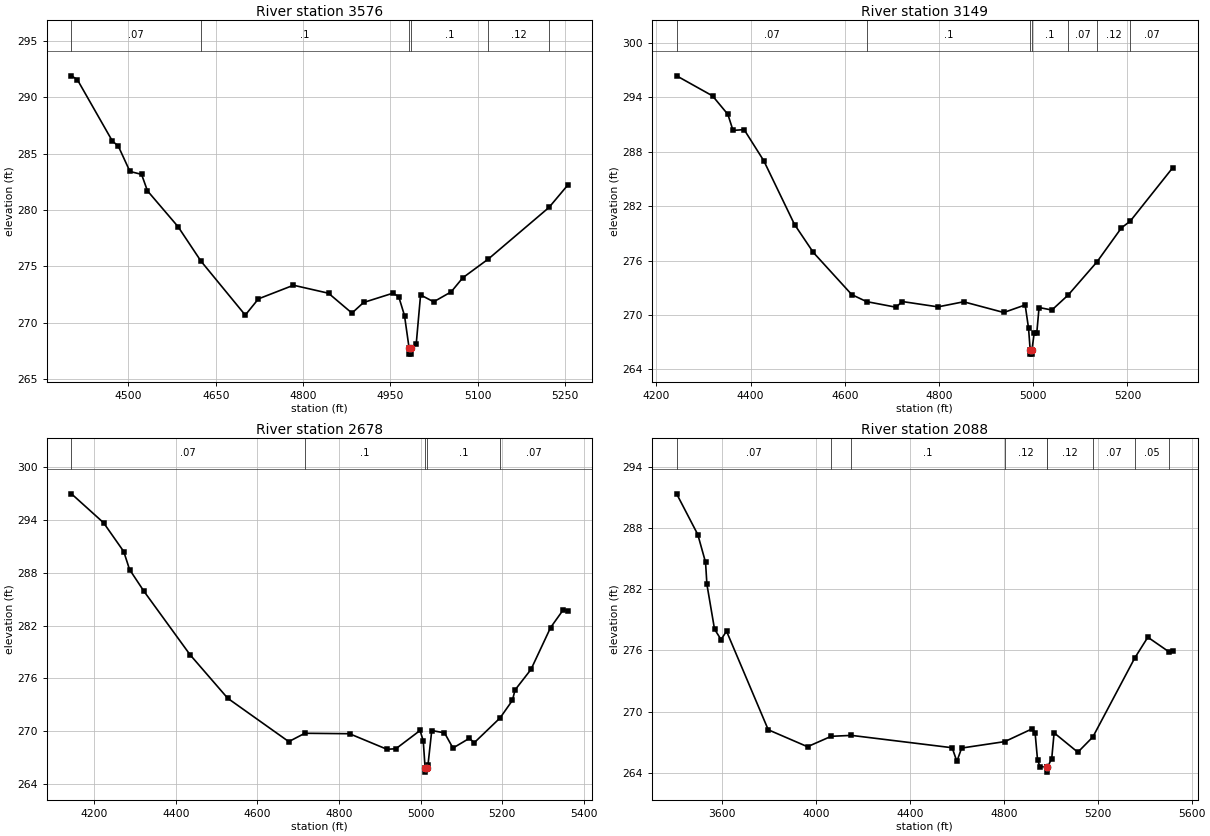
Type RM Length L Ch R = 1,3576,427,427,427
BEGIN DESCRIPTION:
Stream0655 5.0
END DESCRIPTION:
XS GIS Cut Line= 3
      2386524.98     13632525.00      2387125.00     13632475.00
      2387375.00     13632475.00
#Sta/Elev= 30
  4402.3  291.90  4412.4  291.56  4472.6  286.11  4482.6  285.68  4502.7  283.42
  4522.7  283.16  4532.8  281.70  4585.4  278.52  4624.8  275.46  4700.8  270.68
  4723.4  272.12  4783.6  273.33  4843.8  272.62  4884.0  270.86  4904.0  271.80
  4954.2  272.62  4964.3  272.33  4974.3  270.64  4982.3  267.72  4982.6  267.22
  4986.1  267.22  4986.3  267.72  4994.4  268.10  5001.9  272.47  5024.4  271.86
  5054.4  272.74  5074.4  273.99  5118.4  275.66  5222.5  280.23  5254.4  282.19
#Mann=6,-1,0
  4402.3    0.07       0  4624.8     0.1       0  4982.3    0.05       0
  4986.3     0.1       0  5118.4    0.12       0  5222.5    0.07       0
Bank Sta=4982.3,4986.3
Exp/Cntr=0.3,0.1

Type RM Length L Ch R = 1,3149,471,471,471
BEGIN DESCRIPTION:
Stream0655 4.0
END DESCRIPTION:
XS GIS Cut Line= 3
      2386424.97     13632574.99      2387125.00     13632875.00
      2387375.04     13633025.02
#Sta/Elev= 30
  4242.9  296.37  4319.1  294.16  4351.7  292.12  4362.6  290.35  4386.2  290.44
  4427.9  287.01  4493.2  279.98  4533.1  276.90  4614.7  272.25  4646.1  271.48
  4708.9  270.86  4721.6  271.49  4797.8  270.90  4852.2  271.46  4937.4  270.28
  4982.8  271.11  4990.0  268.54  4993.4  266.19  4993.7  265.69  4997.2  265.69
  4997.4  266.19  5001.8  267.98  5007.4  267.98  5012.3  270.83  5039.5  270.55
  5074.2  272.21  5135.3  275.86  5187.2  279.61  5205.9  280.35  5296.1  286.24
#Mann=7,-1,0
  4242.9    0.07       0  4646.1     0.1       0  4993.4    0.05       0
  4997.4     0.1       0  5074.2    0.07       0  5135.3    0.12       0
  5205.9    0.07       0
Bank Sta=4993.4,4997.4
Exp/Cntr=0.3,0.1

Type RM Length L Ch R = 1,2678,590,590,590
BEGIN DESCRIPTION:
Stream0655 3.0
END DESCRIPTION:
XS GIS Cut Line= 3
      2386374.98     13632624.97      2386925.00     13633275.00
      2387274.99     13633375.00
#Sta/Elev= 30
  4144.6  297.00  4223.2  293.71  4272.7  290.43  4286.9  288.39  4322.1  285.92
  4435.2  278.69  4527.5  273.74  4677.0  268.81  4716.3  269.76  4825.8  269.71
  4917.5  267.94  4939.5  268.00  4998.7  270.08  5006.5  268.88  5011.0  265.84
  5011.2  265.34  5015.1  265.84  5018.2  266.20  5027.3  270.07  5058.5  269.81
  5079.3  268.08  5119.6  269.19  5131.3  268.68  5194.6  271.50  5224.9  273.50
  5231.4  274.69  5270.4  277.02  5318.5  281.79  5349.7  283.82  5360.1  283.68
#Mann=5,-1,0
  4144.6    0.07       0  4716.3     0.1       0  5011.0    0.05       0
  5015.1     0.1       0  5194.6    0.07       0
Bank Sta=5011,5015.1
Exp/Cntr=0.3,0.1

Type RM Length L Ch R = 1,2088,0,0,0
BEGIN DESCRIPTION:
XS7409
END DESCRIPTION:
XS GIS Cut Line= 4
      2386234.60     13632781.63      2386502.95     13633670.55
      2387280.08     13633776.78      2387614.54     13633559.38
#Sta/Elev= 30
  3407.7  291.34  3497.8  287.35  3530.8  284.63  3536.6  282.47  3569.0  278.08
  3596.7  277.06  3620.1  277.88  3797.7  268.22  3964.8  266.56  4065.7  267.58
  4152.0  267.67  4580.5  266.46  4600.7  265.12  4620.9  266.43  4804.5  267.06
  4920.8  268.31  4933.8  267.87  4943.9  265.29  4954.0  264.62  4982.2  264.57
  4982.5  264.07  4986.3  264.57  5004.4  265.39  5014.5  267.92  5115.5  266.02
  5179.6  267.52  5357.7  275.25  5413.5  277.29  5503.3  275.86  5519.5  275.96
#Mann=9,-1,0
  3407.7    0.07       0  4065.7    0.12       0  4152.0     0.1       0
  4804.5    0.12       0  4982.2    0.05       0  4986.3    0.12       0
  5179.6    0.07       0  5357.7    0.05       0  5503.3   0.035       0
Bank Sta=4982.2,4986.3
Exp/Cntr=0.3,0.1

Chan Stop Cuts=-1