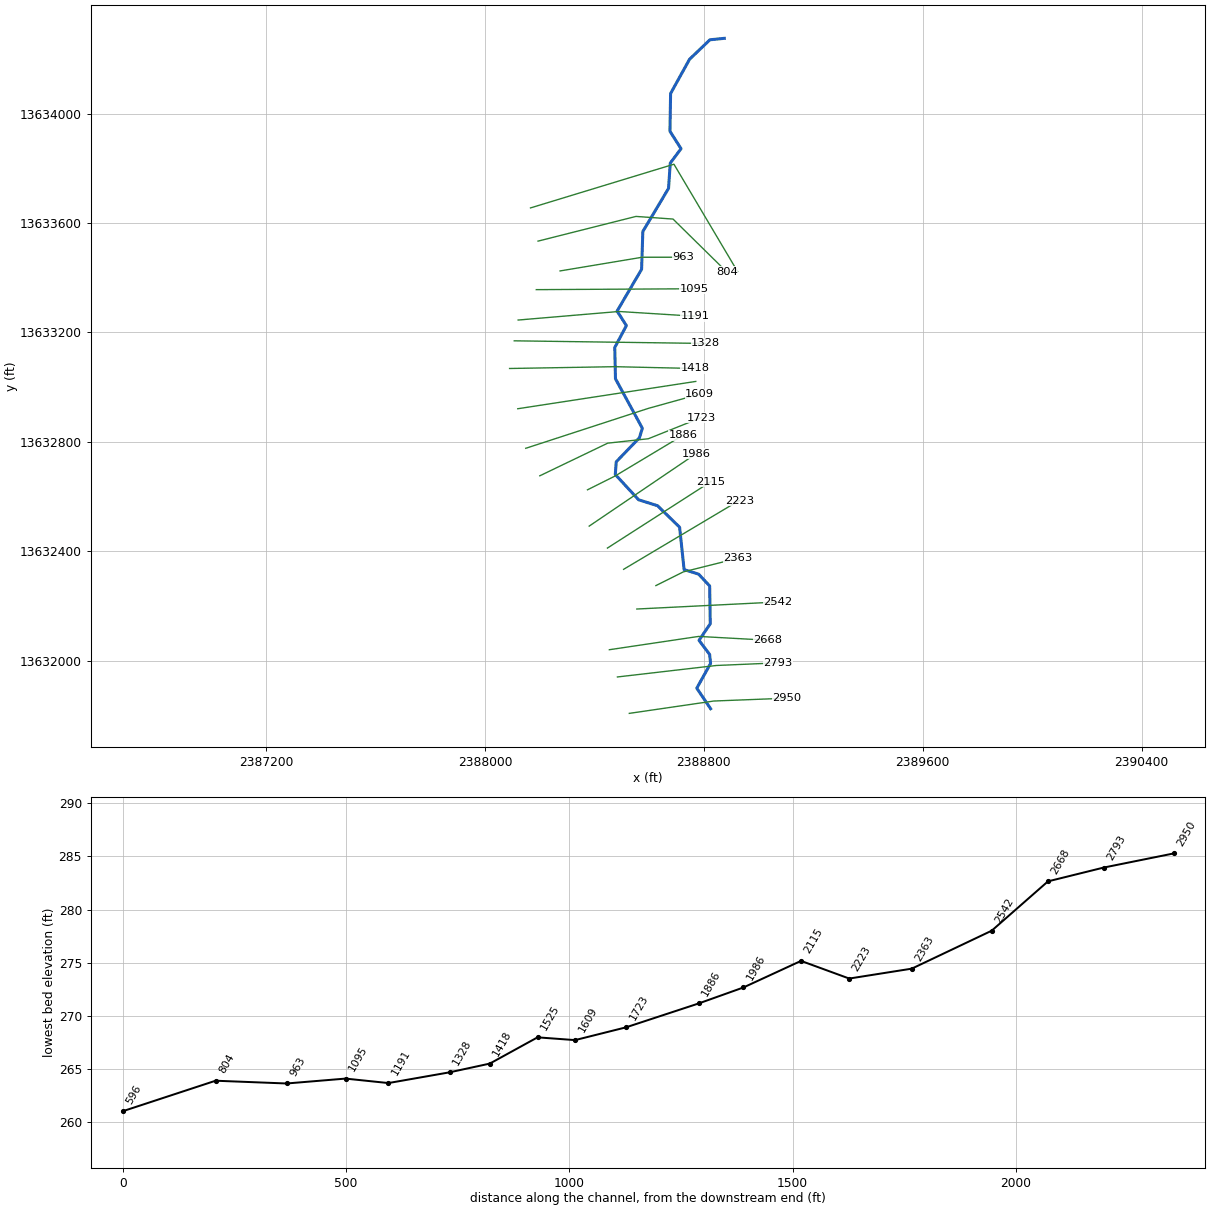
--- Stream0656.prj (project) ---

Proj Title=Stream0656 Base Level Engineering
Current Plan=p01
Default Exp/Contr=0.3,0.1
English Units
Geom File=g01
Flow File=f01
Plan File=p01
BEGIN DESCRIPTION:
Stream0656
END DESCRIPTION:

--- Stream0656.p01 (plan) ---

Plan Title=Multiple Run
Short Identifier=Multiple
Geom File=g01
Flow File=f01
Subcritical Flow
K Sum by GR= 0
Std Step Tol= 0.01
Critical Tol= 0.01
Num of Std Step Trials= 20
Max Error Tol= 0.3
Flow Tol Ratio= 0.001
Split Flow NTrial= 30
Split Flow Tol= 0.02
Split Flow Ratio= 0.02
Log Output Level= 0
Friction Slope Method= 1
Unsteady Friction Slope Method= 2
Unsteady Bridges Friction Slope Method= 1
Parabolic Critical Depth
Global Vel Dist=  1 , 1 , 1
Global Log Level= 0
CheckData=True
Encroach Param= -1, 0, 0, 0
BEGIN DESCRIPTION:
Multiple Run
END DESCRIPTION:

--- Stream0656.f01 (steady flow) ---

Flow Title=Multiple
Number of Profiles=7
Profile Names=10-year,25-year,50-year,1pct_min,100-year,1pct_plu,500-year
River Rch & RM= Stream0656,Reach-1,2950
     214     325     419     263     526    1049     816
Boundary for River Rch & Prof#=Stream0656,Reach-1,1
Up Type=0
Dn Type=3
Dn Slope=0.005
Boundary for River Rch & Prof#=Stream0656,Reach-1,2
Up Type=0
Dn Type=3
Dn Slope=0.005
Boundary for River Rch & Prof#=Stream0656,Reach-1,3
Up Type=0
Dn Type=3
Dn Slope=0.005
Boundary for River Rch & Prof#=Stream0656,Reach-1,4
Up Type=0
Dn Type=3
Dn Slope=0.005
Boundary for River Rch & Prof#=Stream0656,Reach-1,5
Up Type=0
Dn Type=3
Dn Slope=0.005
Boundary for River Rch & Prof#=Stream0656,Reach-1,6
Up Type=0
Dn Type=3
Dn Slope=0.005
Boundary for River Rch & Prof#=Stream0656,Reach-1,7
Up Type=0
Dn Type=3
Dn Slope=0.005

--- Stream0656.g01 (geometry) ---

Geom Title=Existing Conditions

River Reach=Stream0656,Reach-1
Reach XY= 30
      2388825.00     13631825.00      2388774.40     13631900.06
      2388824.84     13631990.41      2388821.39     13632023.36
      2388782.59     13632074.99      2388823.63     13632135.44
      2388821.53     13632273.73      2388781.03     13632316.83
      2388728.11     13632333.32      2388711.64     13632488.34
      2388631.07     13632566.85      2388561.76     13632588.62
      2388476.58     13632681.04      2388480.08     13632727.28
      2388564.79     13632815.33      2388575.50     13632849.97
      2388477.23     13633030.93      2388474.68     13633145.17
      2388517.20     13633225.10      2388483.24     13633278.23
      2388572.75     13633430.93      2388577.25     13633569.07
      2388671.18     13633726.59      2388677.55     13633819.11
      2388716.92     13633871.70      2388676.37     13633935.44
      2388678.74     13634073.44      2388747.97     13634198.51
      2388822.46     13634269.70      2388875.00     13634275.00

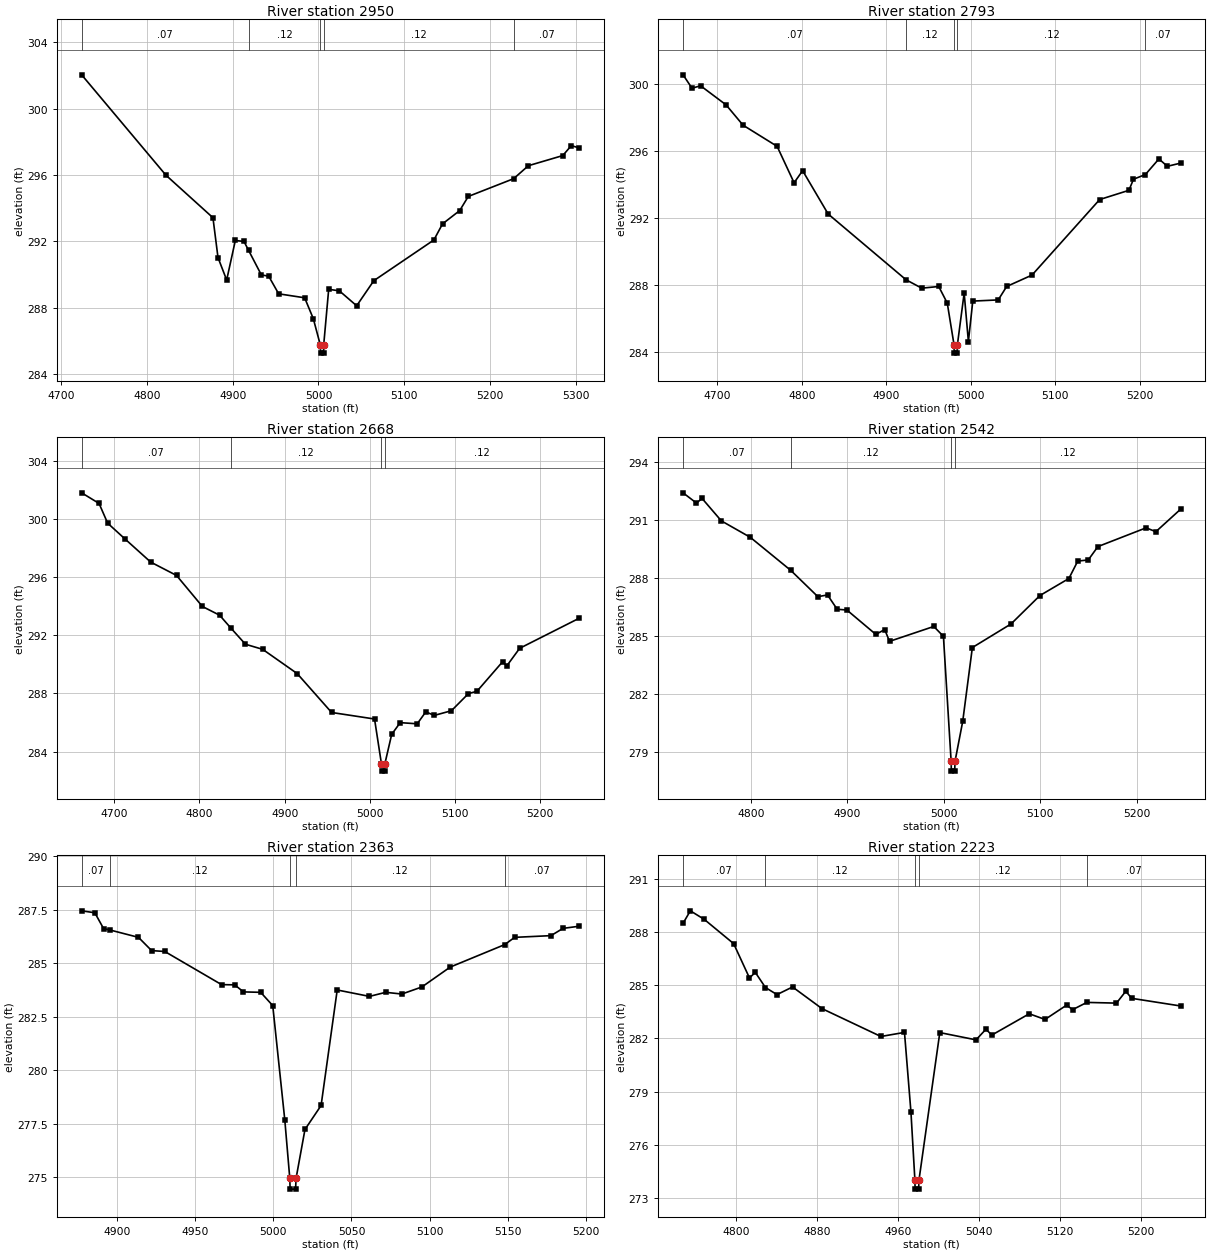
Type RM Length L Ch R = 1,2950,157,157,157
BEGIN DESCRIPTION:
XS7414
END DESCRIPTION:
XS GIS Cut Line= 3
      2388527.81     13631807.99      2388836.81     13631853.13
      2389104.13     13631863.54
#Sta/Elev= 30
  4724.0  302.03  4822.2  295.99  4877.0  293.43  4882.9  291.03  4893.0  289.68
  4903.1  292.06  4913.2  292.00  4918.6  291.46  4933.4  289.99  4942.0  289.91
  4953.6  288.85  4983.9  288.61  4994.0  287.35  5002.1  285.78  5002.4  285.28
  5005.9  285.28  5006.1  285.78  5011.9  289.12  5024.3  289.03  5044.5  288.13
  5064.5  289.64  5134.5  292.09  5144.6  293.06  5164.6  293.86  5174.6  294.71
  5227.5  295.78  5244.6  296.56  5284.7  297.17  5294.7  297.77  5303.8  297.63
#Mann=5,-1,0
  4724.0    0.07       0  4918.6    0.12       0  5002.1    0.05       0
  5006.1    0.12       0  5227.5    0.07       0
Bank Sta=5002.1,5006.1
Exp/Cntr=0.3,0.1

Type RM Length L Ch R = 1,2793,125,125,125
BEGIN DESCRIPTION:
E21233
END DESCRIPTION:
XS GIS Cut Line= 3
      2388484.43     13631941.07      2388845.60     13631982.99
      2389070.60     13631992.64
#Sta/Elev= 30
  4659.3  300.53  4669.9  299.73  4680.0  299.88  4710.2  298.74  4730.3  297.53
  4770.6  296.27  4790.7  294.10  4800.8  294.82  4831.0  292.24  4923.2  288.32
  4941.8  287.82  4961.9  287.92  4972.0  286.93  4980.0  284.45  4980.3  283.95
  4983.8  283.95  4984.0  284.45  4992.0  287.53  4997.0  284.64  5002.2  287.05
  5032.3  287.12  5042.3  287.92  5072.3  288.60  5152.4  293.10  5187.0  293.65
  5192.4  294.31  5206.5  294.59  5222.5  295.52  5232.5  295.08  5248.1  295.27
#Mann=5,-1,0
  4659.3    0.07       0  4923.2    0.12       0  4980.0    0.05       0
  4984.0    0.12       0  5206.5    0.07       0
Bank Sta=4980,4984
Exp/Cntr=0.3,0.1

Type RM Length L Ch R = 1,2668,126,126,126
BEGIN DESCRIPTION:
Stream0656 6.0
END DESCRIPTION:
XS GIS Cut Line= 3
      2388454.87     13632040.63      2388781.25     13632089.24
      2389034.69     13632075.35
#Sta/Elev= 30
  4661.8  301.82  4682.2  301.09  4692.3  299.73  4712.5  298.65  4742.8  297.05
  4773.1  296.13  4803.5  293.99  4823.7  293.39  4836.8  292.51  4854.0  291.39
  4874.2  291.04  4914.7  289.37  4955.1  286.69  5005.5  286.24  5013.6  283.15
  5013.8  282.65  5017.3  282.65  5017.6  283.15  5025.6  285.18  5035.6  285.99
  5055.6  285.91  5065.6  286.73  5075.7  286.49  5095.7  286.81  5115.7  287.99
  5125.7  288.15  5155.7  290.18  5160.7  289.90  5175.8  291.11  5245.6  293.18
#Mann=4,-1,0
  4661.8    0.07       0  4836.8    0.12       0  5013.6    0.05       0
  5017.6    0.12       0
Bank Sta=5013.6,5017.6
Exp/Cntr=0.3,0.1

Type RM Length L Ch R = 1,2542,179,179,179
BEGIN DESCRIPTION:
E21232
END DESCRIPTION:
XS GIS Cut Line= 2
      2388555.36     13632189.35      2389070.61     13632215.11
#Sta/Elev= 30
  4729.6  292.40  4743.5  291.87  4749.3  292.11  4769.3  290.95  4799.3  290.10
  4841.3  288.39  4869.4  287.03  4879.4  287.12  4889.4  286.38  4899.5  286.34
  4929.5  285.08  4938.7  285.33  4943.7  284.72  4989.6  285.49  4999.6  284.98
  5007.6  278.51  5007.8  278.01  5011.3  278.01  5011.6  278.51  5019.6  280.58
  5029.6  284.40  5069.7  285.62  5099.7  287.09  5129.7  287.97  5138.9  288.87
  5149.8  288.93  5159.8  289.62  5209.8  290.59  5219.9  290.39  5245.5  291.55
#Mann=4,-1,0
  4729.6    0.07       0  4841.3    0.12       0  5007.6    0.05       0
  5011.6    0.12       0
Bank Sta=5007.6,5011.6
Exp/Cntr=0.3,0.1

Type RM Length L Ch R = 1,2363,140,140,140
BEGIN DESCRIPTION:
Stream0656 5.0
END DESCRIPTION:
XS GIS Cut Line= 3
      2388625.01     13632275.00      2388725.00     13632325.00
      2388924.95     13632374.99
#Sta/Elev= 30
  4877.6  287.45  4886.0  287.36  4891.6  286.62  4895.9  286.55  4913.9  286.21
  4922.3  285.59  4930.7  285.55  4967.0  284.00  4975.4  283.99  4981.0  283.66
  4992.0  283.64  4999.7  283.02  5007.4  277.68  5010.6  274.94  5010.8  274.44
  5014.3  274.44  5014.6  274.94  5020.3  277.23  5030.6  278.35  5040.9  283.75
  5061.5  283.45  5071.9  283.64  5082.2  283.56  5095.0  283.89  5113.1  284.82
  5147.9  285.87  5154.3  286.21  5177.5  286.29  5185.2  286.63  5195.5  286.73
#Mann=5,-1,0
  4877.6    0.07       0  4895.9    0.12       0  5010.6    0.05       0
  5014.6    0.12       0  5147.9    0.07       0
Bank Sta=5010.6,5014.6
Exp/Cntr=0.3,0.1

Type RM Length L Ch R = 1,2223,108,108,108
BEGIN DESCRIPTION:
E21231
END DESCRIPTION:
XS GIS Cut Line= 2
      2388507.02     13632334.44      2388929.42     13632585.94
#Sta/Elev= 30
  4747.4  288.49  4754.6  289.19  4768.3  288.71  4797.4  287.34  4813.0  285.41
  4818.8  285.72  4828.8  284.87  4840.2  284.47  4855.6  284.90  4884.7  283.68
  4942.9  282.11  4966.2  282.34  4972.6  277.84  4976.5  274.01  4976.7  273.51
  4980.2  273.51  4980.5  274.01  5001.1  282.33  5036.9  281.92  5046.7  282.52
  5052.5  282.19  5089.5  283.39  5105.1  283.07  5126.5  283.88  5132.3  283.62
  5146.4  284.03  5175.7  283.99  5184.9  284.66  5190.7  284.26  5239.0  283.83
#Mann=5,-1,0
  4747.4    0.07       0  4828.8    0.12       0  4976.5    0.05       0
  4980.5    0.12       0  5146.4    0.07       0
Bank Sta=4976.5,4980.5
Exp/Cntr=0.3,0.1

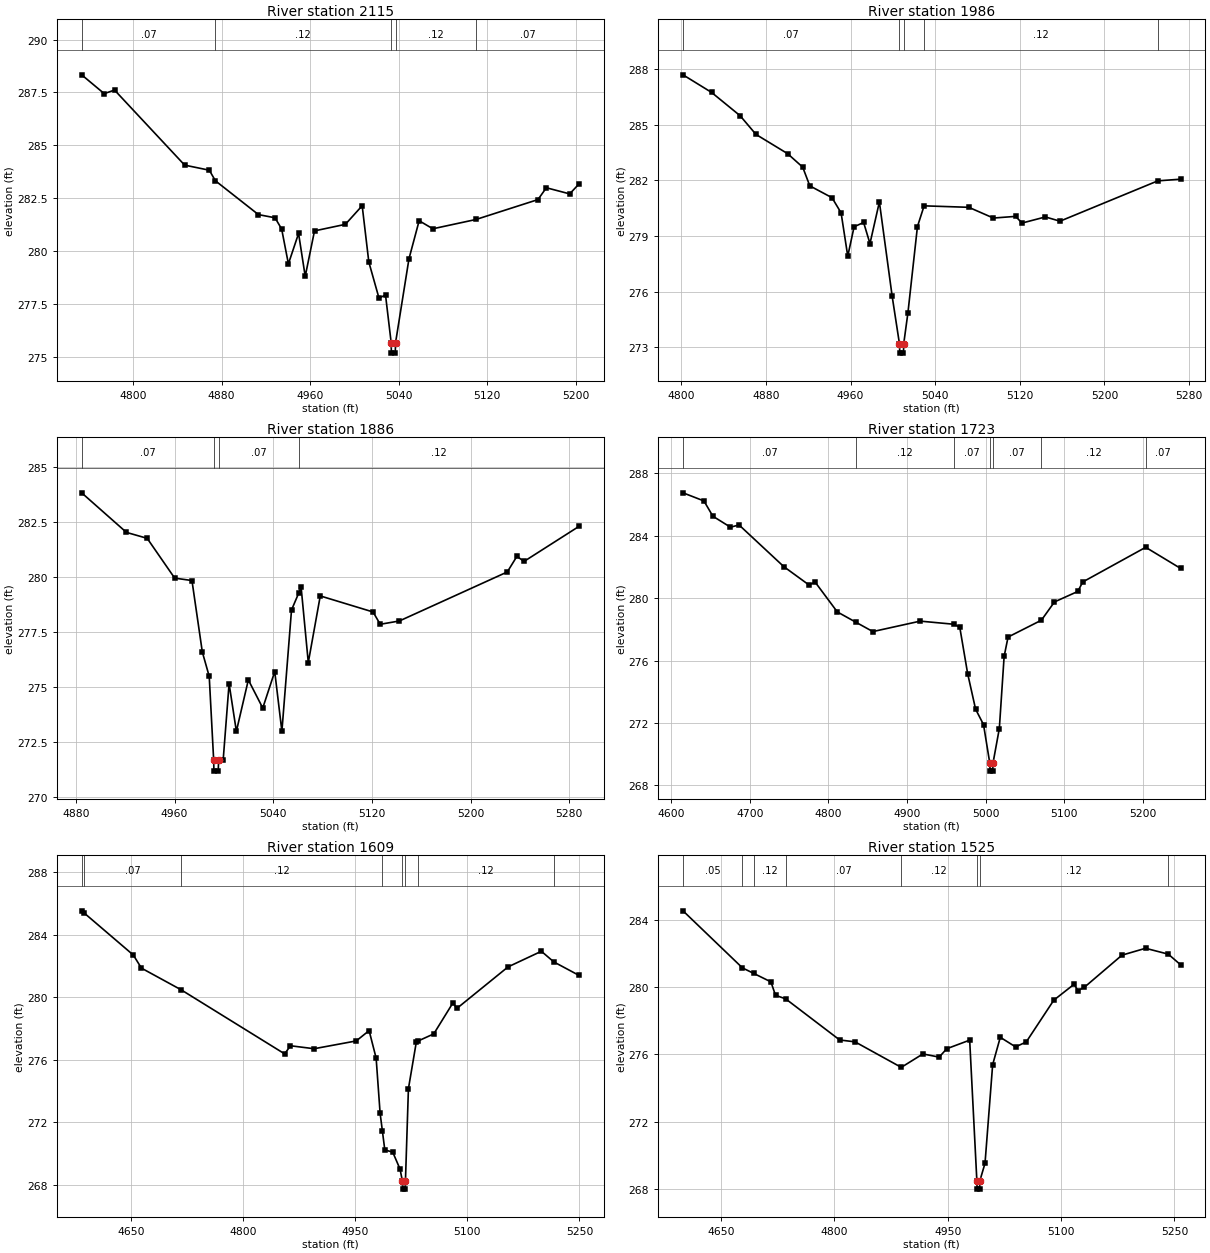
Type RM Length L Ch R = 1,2115,129,129,129
BEGIN DESCRIPTION:
XS7413
END DESCRIPTION:
XS GIS Cut Line= 2
      2388447.89     13632412.13      2388826.36     13632655.19
#Sta/Elev= 30
  4753.5  288.33  4773.9  287.44  4783.2  287.61  4846.6  284.06  4868.9  283.82
  4874.4  283.32  4913.3  281.72  4928.3  281.57  4934.3  281.04  4940.4  279.39
  4949.6  280.83  4955.6  278.80  4964.0  280.95  4991.9  281.26  5007.1  282.14
  5013.1  279.48  5022.3  277.77  5028.2  277.92  5033.3  275.67  5033.5  275.17
  5037.0  275.17  5037.3  275.67  5049.4  279.63  5058.6  281.43  5071.0  281.05
  5110.0  281.49  5166.0  282.43  5173.6  282.99  5194.7  282.70  5203.3  283.18
#Mann=5,-1,0
  4753.5    0.07       0  4874.4    0.12       0  5033.3    0.05       0
  5037.3    0.12       0  5110.0    0.07       0
Bank Sta=5033.3,5037.3
Exp/Cntr=0.3,0.1

Type RM Length L Ch R = 1,1986,100,100,100
BEGIN DESCRIPTION:
E21230
END DESCRIPTION:
XS GIS Cut Line= 2
      2388381.27     13632492.42      2388770.76     13632756.37
#Sta/Elev= 30
  4801.5  287.71  4828.5  286.76  4855.5  285.50  4870.5  284.49  4900.4  283.45
  4914.7  282.72  4921.4  281.71  4942.4  281.07  4951.0  280.25  4957.3  277.91
  4963.3  279.50  4972.3  279.73  4978.3  278.59  4987.2  280.84  4999.3  275.74
  5006.2  273.17  5006.5  272.67  5010.0  272.67  5010.2  273.17  5014.2  274.85
  5023.2  279.51  5029.5  280.63  5071.8  280.55  5095.0  279.97  5116.0  280.06
  5122.1  279.70  5144.2  280.03  5158.0  279.80  5250.5  281.98  5272.0  282.07
#Mann=5,-1,0
  4801.5    0.07       0  5006.2    0.05       0  5010.2    0.07       0
  5029.5    0.12       0  5250.5    0.07       0
Bank Sta=5006.2,5010.2
Exp/Cntr=0.3,0.1

Type RM Length L Ch R = 1,1886,163,163,163
BEGIN DESCRIPTION:
Stream0656 4.0
END DESCRIPTION:
XS GIS Cut Line= 3
      2388375.03     13632625.02      2388475.00     13632675.00
      2388724.99     13632824.99
#Sta/Elev= 30
  4884.7  283.83  4921.0  282.03  4937.8  281.76  4960.1  279.95  4974.1  279.84
  4982.5  276.59  4988.1  275.48  4991.7  271.67  4991.9  271.17  4995.4  271.17
  4995.7  271.67  4999.4  271.67  5004.2  275.15  5010.1  272.98  5019.8  275.32
  5031.5  274.04  5041.2  275.70  5047.0  272.98  5054.8  278.50  5060.8  279.29
  5062.6  279.53  5068.4  276.11  5078.1  279.14  5120.9  278.41  5126.7  277.85
  5142.2  278.00  5229.7  280.23  5237.5  280.94  5243.3  280.71  5288.0  282.31
#Mann=4,-1,0
  4884.7    0.07       0  4991.7    0.05       0  4995.7    0.07       0
  5060.8    0.12       0
Bank Sta=4991.7,4995.7
Exp/Cntr=0.3,0.1

Type RM Length L Ch R = 1,1723,114,114,114
BEGIN DESCRIPTION:
E21229
END DESCRIPTION:
XS GIS Cut Line= 4
      2388200.73     13632676.23      2388449.00     13632795.53
      2388597.32     13632811.65      2388790.41     13632888.88
#Sta/Elev= 30
  4615.1  286.75  4641.7  286.23  4653.1  285.25  4675.4  284.55  4686.4  284.69
  4743.3  282.02  4775.2  280.85  4783.1  281.03  4811.3  279.12  4834.9  278.46
  4856.5  277.86  4916.7  278.53  4959.5  278.33  4967.0  278.14  4977.0  275.17
  4987.1  272.89  4997.2  271.90  5005.2  269.42  5005.5  268.92  5009.0  268.92
  5009.2  269.42  5017.3  271.65  5023.4  276.27  5028.4  277.51  5070.8  278.59
  5087.4  279.76  5117.0  280.43  5123.4  281.04  5203.4  283.26  5247.7  281.91
#Mann=7,-1,0
  4615.1    0.07       0  4834.9    0.12       0  4959.5    0.07       0
  5005.2    0.05       0  5009.2    0.07       0  5070.8    0.12       0
  5203.4    0.07       0
Bank Sta=5005.2,5009.2
Exp/Cntr=0.3,0.1

Type RM Length L Ch R = 1,1609,84,84,84
BEGIN DESCRIPTION:
XS7412
END DESCRIPTION:
XS GIS Cut Line= 3
      2388149.28     13632776.73      2388597.22     13632922.57
      2388784.74     13632974.66
#Sta/Elev= 30
  4583.9  285.54  4587.5  285.39  4653.0  282.71  4663.9  281.87  4717.1  280.48
  4855.5  276.38  4863.3  276.90  4894.9  276.71  4951.3  277.21  4968.5  277.87
  4977.9  276.11  4983.2  272.59  4986.3  271.43  4989.5  270.23  5000.1  270.09
  5009.9  269.00  5013.1  268.22  5013.4  267.72  5016.9  267.72  5017.1  268.22
  5021.1  274.15  5031.6  277.12  5033.8  277.20  5055.0  277.66  5080.7  279.65
  5085.9  279.29  5154.4  281.95  5199.0  282.95  5215.6  282.27  5249.6  281.40
#Mann=8,-1,0
  4583.9    0.05       0  4587.5    0.07       0  4717.1    0.12       0
  4986.3    0.07       0  5013.1    0.05       0  5017.1    0.07       0
  5033.8    0.12       0  5215.6    0.07       0
Bank Sta=5013.1,5017.1
Exp/Cntr=0.3,0.1

Type RM Length L Ch R = 1,1525,107,107,107
BEGIN DESCRIPTION:
E21228
END DESCRIPTION:
XS GIS Cut Line= 2
      2388120.07     13632921.27      2388770.75     13633021.13
#Sta/Elev= 30
  4599.7  284.55  4678.4  281.15  4693.0  280.83  4716.0  280.32  4722.1  279.52
  4735.5  279.31  4807.0  276.86  4827.3  276.75  4888.5  275.23  4917.1  276.03
  4938.6  275.84  4948.7  276.34  4979.0  276.85  4988.5  268.48  4988.8  267.98
  4992.3  267.98  4992.5  268.48  4999.3  269.52  5009.4  275.39  5019.5  277.02
  5039.7  276.45  5053.8  276.74  5090.3  279.23  5117.2  280.18  5122.2  279.80
  5130.8  280.00  5180.5  281.91  5211.7  282.32  5241.8  281.97  5258.0  281.34
#Mann=8,-1,0
  4599.7    0.05       0  4678.4    0.07       0  4693.0    0.12       0
  4735.5    0.07       0  4888.5    0.12       0  4988.5    0.05       0
  4992.5    0.12       0  5241.8    0.07       0
Bank Sta=4988.5,4992.5
Exp/Cntr=0.3,0.1

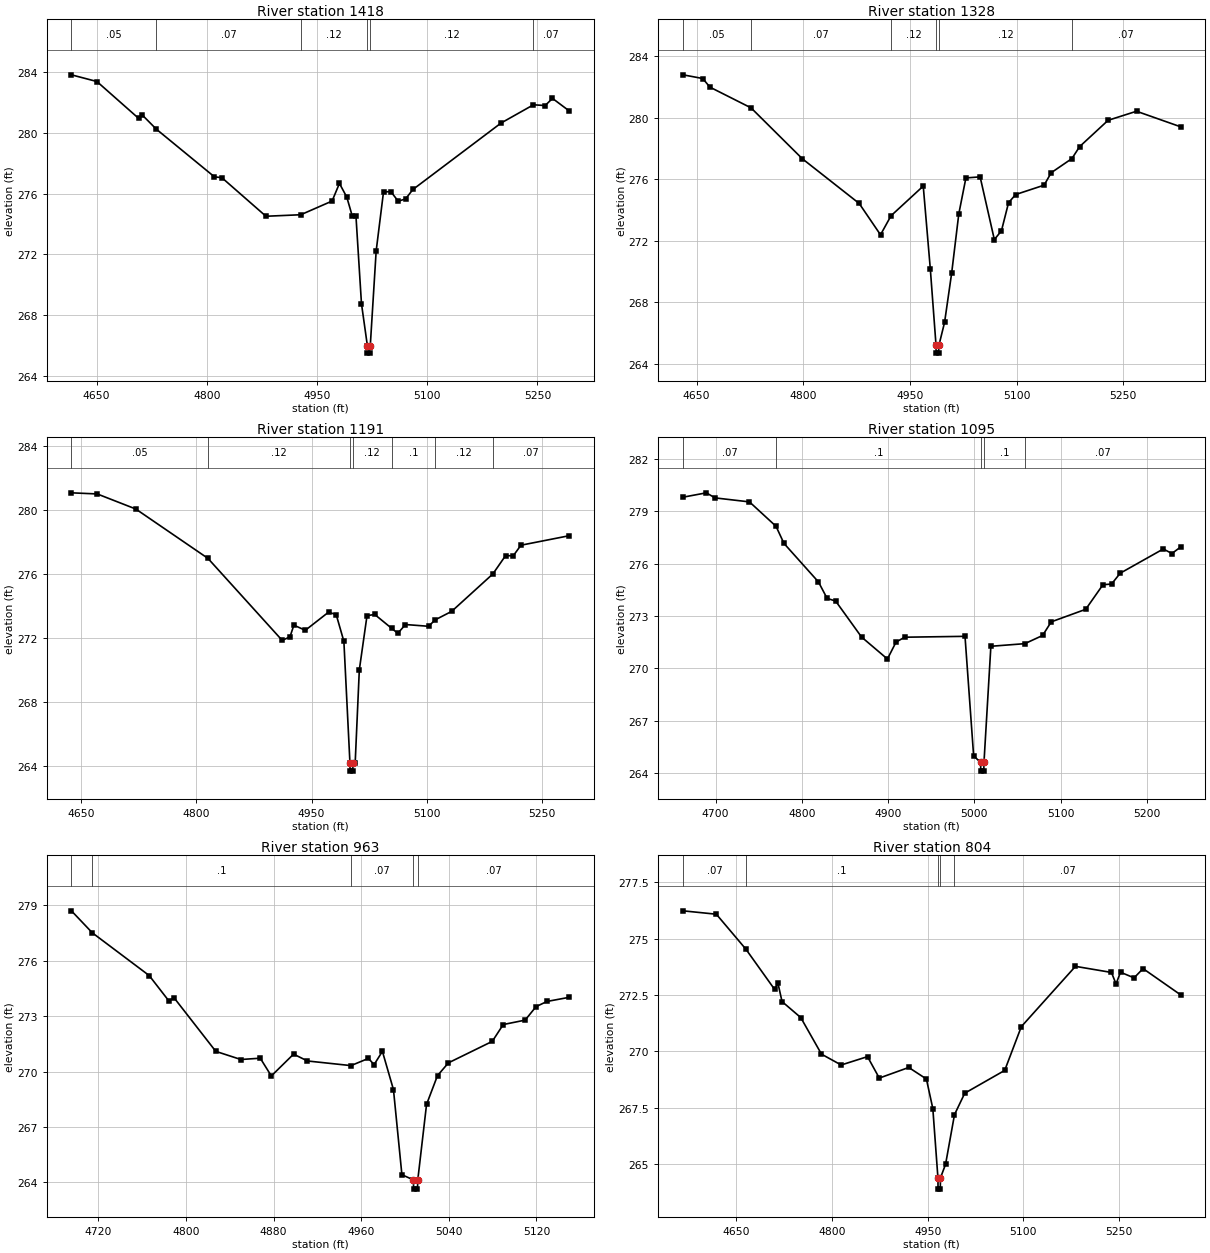
Type RM Length L Ch R = 1,1418,90,90,90
BEGIN DESCRIPTION:
Stream0656 3.0
END DESCRIPTION:
XS GIS Cut Line= 3
      2388090.28     13633068.40      2388475.00     13633075.00
      2388767.35     13633068.40
#Sta/Elev= 30
  4615.7  283.81  4650.4  283.37  4707.1  280.95  4712.1  281.17  4731.2  280.24
  4810.4  277.10  4820.4  277.05  4880.5  274.51  4927.9  274.61  4970.5  275.51
  4980.5  276.67  4990.5  275.77  4998.0  274.52  5003.0  274.52  5010.5  268.76
  5018.5  266.01  5018.7  265.51  5022.2  265.51  5022.5  266.01  5030.5  272.23
  5040.5  276.11  5050.5  276.13  5060.5  275.50  5070.5  275.65  5080.5  276.27
  5200.5  280.64  5244.6  281.84  5260.5  281.79  5270.5  282.26  5292.9  281.45
#Mann=6,-1,0
  4615.7    0.05       0  4731.2    0.07       0  4927.9    0.12       0
  5018.5    0.05       0  5022.5    0.12       0  5244.6    0.07       0
Bank Sta=5018.5,5022.5
Exp/Cntr=0.3,0.1

Type RM Length L Ch R = 1,1328,137,137,137
BEGIN DESCRIPTION:
E21227
END DESCRIPTION:
XS GIS Cut Line= 2
      2388107.18     13633169.55      2388806.91     13633159.88
#Sta/Elev= 30
  4630.8  282.80  4658.6  282.56  4668.6  282.00  4726.5  280.65  4798.6  277.34
  4878.6  274.43  4908.6  272.39  4923.4  273.63  4968.7  275.56  4978.7  270.14
  4986.7  265.19  4986.9  264.69  4990.4  264.69  4990.7  265.19  4998.7  266.69
  5008.7  269.91  5018.7  273.75  5028.7  276.09  5048.7  276.16  5068.7  272.08
  5078.7  272.65  5088.7  274.48  5098.7  275.01  5138.7  275.62  5148.7  276.43
  5177.8  277.35  5188.7  278.13  5228.7  279.84  5268.7  280.43  5330.6  279.42
#Mann=6,-1,0
  4630.8    0.05       0  4726.5    0.07       0  4923.4    0.12       0
  4986.7    0.05       0  4990.7    0.12       0  5177.8    0.07       0
Bank Sta=4986.7,4990.7
Exp/Cntr=0.3,0.1

Type RM Length L Ch R = 1,1191,96,96,96
BEGIN DESCRIPTION:
XS7411
END DESCRIPTION:
XS GIS Cut Line= 3
      2388121.55     13633245.49      2388489.58     13633276.74
      2388767.38     13633259.37
#Sta/Elev= 30
  4637.3  281.05  4670.9  280.98  4721.1  280.04  4815.0  276.96  4911.7  271.84
  4921.8  272.06  4926.9  272.79  4941.8  272.47  4972.0  273.60  4982.0  273.45
  4992.0  271.78  4999.9  264.18  5000.1  263.68  5003.6  263.68  5003.9  264.18
  5006.7  264.18  5012.1  270.00  5022.1  273.38  5032.1  273.46  5054.0  272.60
  5062.2  272.28  5072.2  272.83  5102.3  272.72  5110.8  273.12  5132.3  273.65
  5186.0  275.99  5202.5  277.13  5212.5  277.12  5222.5  277.78  5285.0  278.37
#Mann=7,-1,0
  4637.3    0.05       0  4815.0    0.12       0  4999.9    0.05       0
  5003.9    0.12       0  5054.0     0.1       0  5110.8    0.12       0
  5186.0    0.07       0
Bank Sta=4999.9,5003.9
Exp/Cntr=0.3,0.1

Type RM Length L Ch R = 1,1095,132,132,132
BEGIN DESCRIPTION:
E21226
END DESCRIPTION:
XS GIS Cut Line= 2
      2388187.87     13633356.56      2388764.96     13633359.79
#Sta/Elev= 30
  4662.1  279.81  4689.2  280.06  4699.2  279.77  4739.2  279.54  4770.0  278.14
  4779.2  277.16  4819.2  274.95  4829.2  274.01  4839.2  273.85  4869.2  271.79
  4899.2  270.53  4909.2  271.50  4919.2  271.78  4989.2  271.83  4999.2  264.98
  5007.2  264.60  5007.5  264.10  5011.0  264.10  5011.2  264.60  5019.2  271.26
  5058.6  271.41  5079.2  271.88  5089.2  272.66  5129.2  273.38  5149.2  274.79
  5159.2  274.83  5169.2  275.45  5219.2  276.84  5229.2  276.58  5239.2  276.95
#Mann=5,-1,0
  4662.1    0.07       0  4770.0     0.1       0  5007.2    0.05       0
  5011.2     0.1       0  5058.6    0.07       0
Bank Sta=5007.2,5011.2
Exp/Cntr=0.3,0.1

Type RM Length L Ch R = 1,963,159,159,159
BEGIN DESCRIPTION:
Stream0656 2.0
END DESCRIPTION:
XS GIS Cut Line= 3
      2388274.95     13633424.99      2388575.00     13633475.00
      2388725.01     13633475.00
#Sta/Elev= 30
  4695.5  278.69  4714.6  277.50  4766.5  275.19  4784.3  273.83  4789.3  273.98
  4827.3  271.09  4850.2  270.65  4867.9  270.72  4878.0  269.76  4898.3  270.94
  4911.0  270.57  4950.7  270.32  4966.7  270.71  4971.8  270.37  4979.4  271.09
  4989.5  269.02  4997.2  264.42  5007.7  264.14  5007.9  263.64  5011.4  263.64
  5011.7  264.14  5019.7  268.22  5029.7  269.78  5039.7  270.47  5079.7  271.63
  5089.7  272.54  5109.7  272.78  5119.7  273.51  5129.7  273.79  5149.7  274.01
#Mann=5,-1,0
  4695.5    0.07       0  4714.6     0.1       0  4950.7    0.07       0
  5007.7    0.05       0  5011.7    0.07       0
Bank Sta=5007.7,5011.7
Exp/Cntr=0.3,0.1

Type RM Length L Ch R = 1,804,208,208,208
BEGIN DESCRIPTION:
E21225
END DESCRIPTION:
XS GIS Cut Line= 4
      2388194.31     13633533.91      2388552.18     13633624.18
      2388687.60     13633614.51      2388884.26     13633421.07
#Sta/Elev= 30
  4566.1  276.23  4618.4  276.08  4664.8  274.53  4709.8  272.75  4715.0  273.03
  4721.5  272.21  4750.9  271.50  4783.4  269.88  4814.3  269.40  4855.6  269.77
  4874.1  268.82  4920.3  269.29  4948.0  268.78  4958.1  267.47  4966.1  264.40
  4966.3  263.90  4969.8  263.90  4970.1  264.40  4978.1  265.00  4992.1  267.20
  5008.2  268.15  5070.9  269.16  5097.0  271.10  5181.9  273.77  5238.4  273.50
  5245.6  272.99  5252.6  273.51  5273.9  273.26  5288.0  273.67  5346.8  272.51
#Mann=5,-1,0
  4566.1    0.07       0  4664.8     0.1       0  4966.1    0.05       0
  4970.1     0.1       0  4992.1    0.07       0
Bank Sta=4966.1,4970.1
Exp/Cntr=0.3,0.1

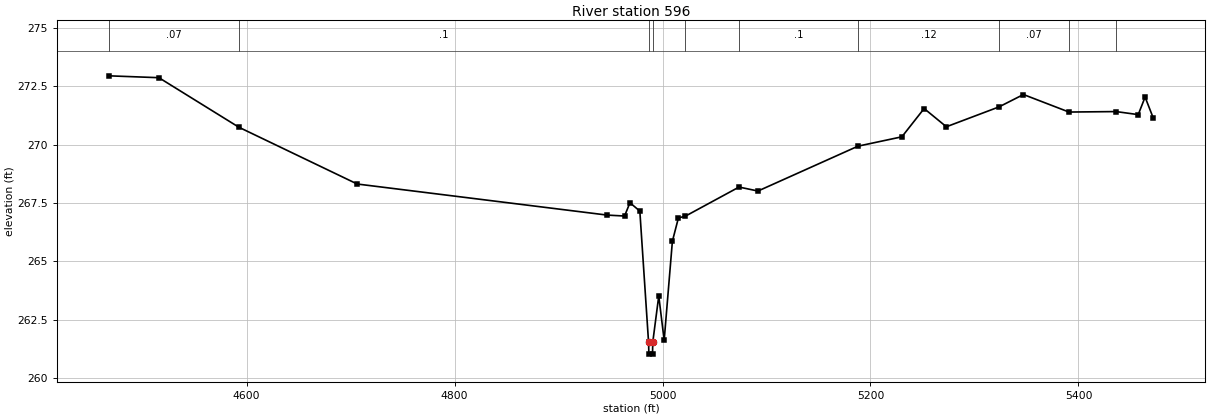
Type RM Length L Ch R = 1,596,0,0,0
BEGIN DESCRIPTION:
Stream0656 1.0
END DESCRIPTION:
XS GIS Cut Line= 3
      2388166.68     13633655.21      2388690.97     13633814.93
      2388923.60     13633422.59
#Sta/Elev= 30
  4467.7  272.94  4515.7  272.86  4592.6  270.74  4706.4  268.31  4946.8  266.98
  4963.5  266.94  4968.7  267.51  4978.2  267.15  4986.6  261.53  4986.9  261.03
  4990.4  261.03  4990.6  261.53  4996.4  263.52  5001.6  261.62  5009.5  265.86
  5015.3  266.86  5021.8  266.93  5073.6  268.18  5091.8  268.01  5188.0  269.93
  5230.2  270.33  5251.6  271.54  5273.0  270.76  5323.6  271.61  5347.1  272.14
  5390.9  271.39  5436.2  271.41  5457.5  271.28  5464.1  272.03  5471.9  271.14
#Mann=10,-1,0
  4467.7    0.07       0  4592.6     0.1       0  4986.6    0.05       0
  4990.6     0.1       0  5021.8    0.12       0  5073.6     0.1       0
  5188.0    0.12       0  5323.6    0.07       0  5390.9    0.12       0
  5436.2    0.07       0
Bank Sta=4986.6,4990.6
Exp/Cntr=0.3,0.1

Chan Stop Cuts=-1