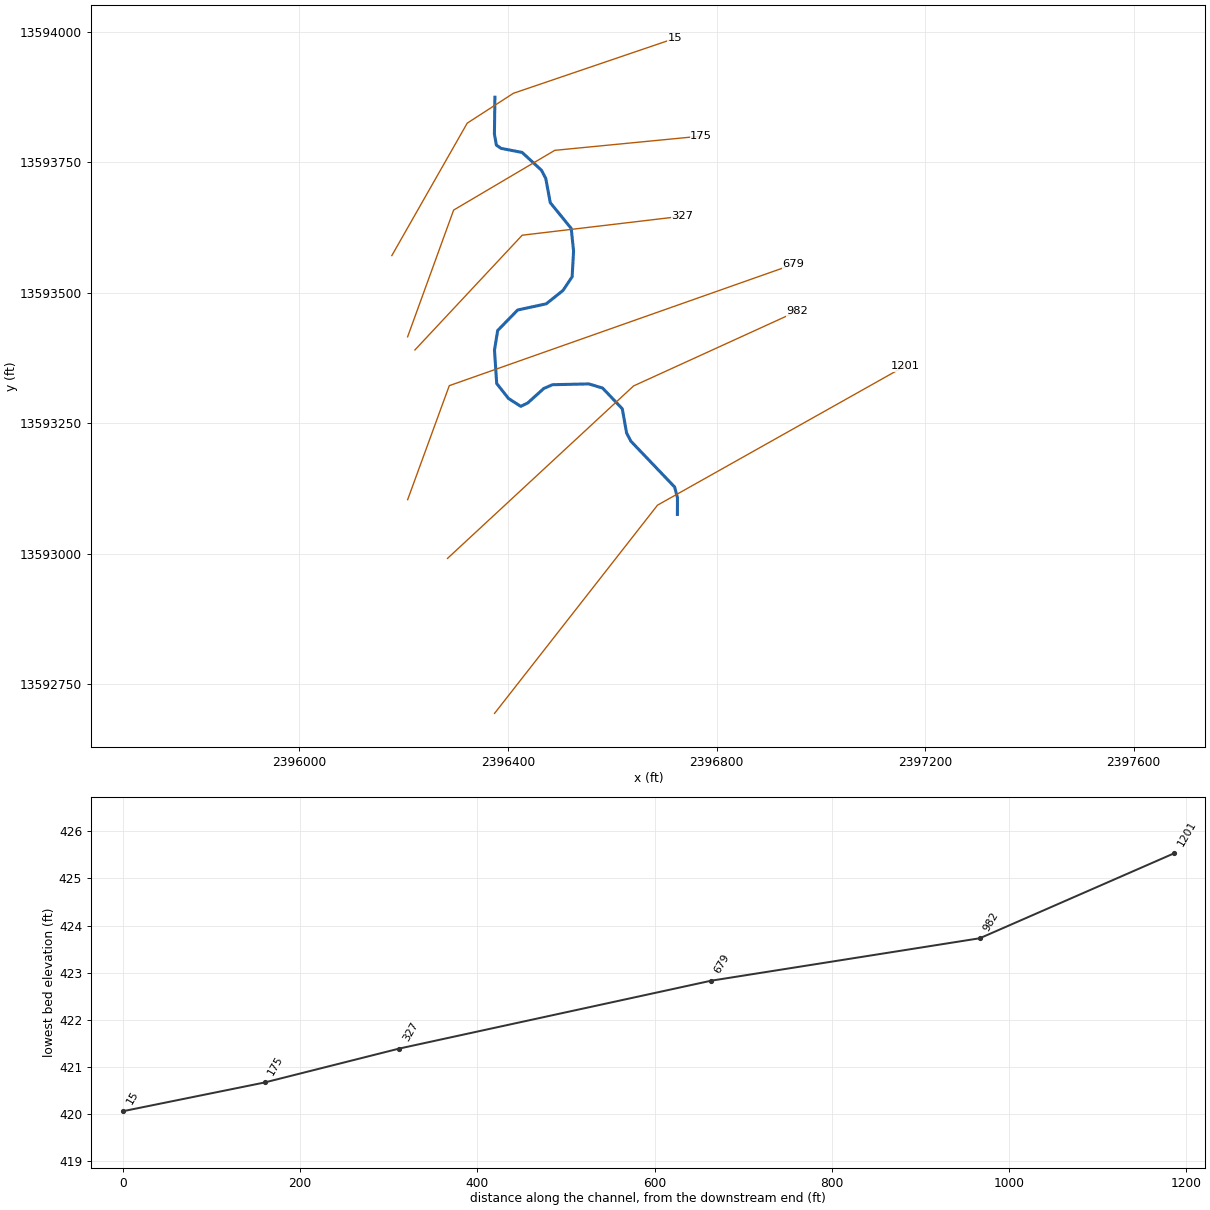
--- Stream0658.prj (project) ---

Proj Title=Stream0658 Base Level Engineering
Current Plan=p01
Default Exp/Contr=0.3,0.1
English Units
Geom File=g01
Flow File=f01
Plan File=p01
BEGIN DESCRIPTION:
Stream0658
END DESCRIPTION:

--- Stream0658.p01 (plan) ---

Plan Title=Multiple Run
Short Identifier=Multiple
Geom File=g01
Flow File=f01
Subcritical Flow
K Sum by GR= 0
Std Step Tol= 0.01
Critical Tol= 0.01
Num of Std Step Trials= 20
Max Error Tol= 0.3
Flow Tol Ratio= 0.001
Split Flow NTrial= 30
Split Flow Tol= 0.02
Split Flow Ratio= 0.02
Log Output Level= 0
Friction Slope Method= 1
Unsteady Friction Slope Method= 2
Unsteady Bridges Friction Slope Method= 1
Parabolic Critical Depth
Global Vel Dist=  1 , 1 , 1
Global Log Level= 0
CheckData=True
Encroach Param= -1, 0, 0, 0
BEGIN DESCRIPTION:
Multiple Run
END DESCRIPTION:

--- Stream0658.f01 (steady flow) ---

Flow Title=Multiple
Number of Profiles=7
Profile Names=10-year,25-year,50-year,1pct_min,100-year,1pct_plu,500-year
River Rch & RM= Stream0658,Reach-1,1201
     417     662     880     568    1132    2259    1856
River Rch & RM= Stream0658,Reach-1,15
     836    1392    1910    1270    2534    5056    4421
Boundary for River Rch & Prof#=Stream0658,Reach-1,1
Up Type=0
Dn Type=3
Dn Slope=0.005
Boundary for River Rch & Prof#=Stream0658,Reach-1,2
Up Type=0
Dn Type=3
Dn Slope=0.005
Boundary for River Rch & Prof#=Stream0658,Reach-1,3
Up Type=0
Dn Type=3
Dn Slope=0.005
Boundary for River Rch & Prof#=Stream0658,Reach-1,4
Up Type=0
Dn Type=3
Dn Slope=0.005
Boundary for River Rch & Prof#=Stream0658,Reach-1,5
Up Type=0
Dn Type=3
Dn Slope=0.005
Boundary for River Rch & Prof#=Stream0658,Reach-1,6
Up Type=0
Dn Type=3
Dn Slope=0.005
Boundary for River Rch & Prof#=Stream0658,Reach-1,7
Up Type=0
Dn Type=3
Dn Slope=0.005

--- Stream0658.g01 (geometry) ---

Geom Title=Existing Conditions

River Reach=Stream0658,Reach-1
Reach XY= 30
      2396725.00     13593075.00      2396725.07     13593106.88
      2396719.67     13593127.51      2396635.79     13593215.34
      2396627.56     13593231.09      2396619.26     13593277.58
      2396581.45     13593317.36      2396555.05     13593325.25
      2396485.48     13593323.73      2396468.81     13593316.57
      2396438.04     13593288.79      2396424.65     13593282.22
      2396401.12     13593297.25      2396378.45     13593326.02
      2396374.19     13593390.11      2396380.29     13593427.67
      2396418.64     13593466.97      2396473.57     13593478.89
      2396505.57     13593504.46      2396523.11     13593530.71
      2396525.85     13593580.00      2396521.33     13593623.41
      2396481.15     13593672.85      2396472.56     13593719.14
      2396464.32     13593734.98      2396427.19     13593769.14
      2396386.68     13593776.99      2396377.85     13593783.12
      2396374.07     13593804.20      2396375.00     13593875.00

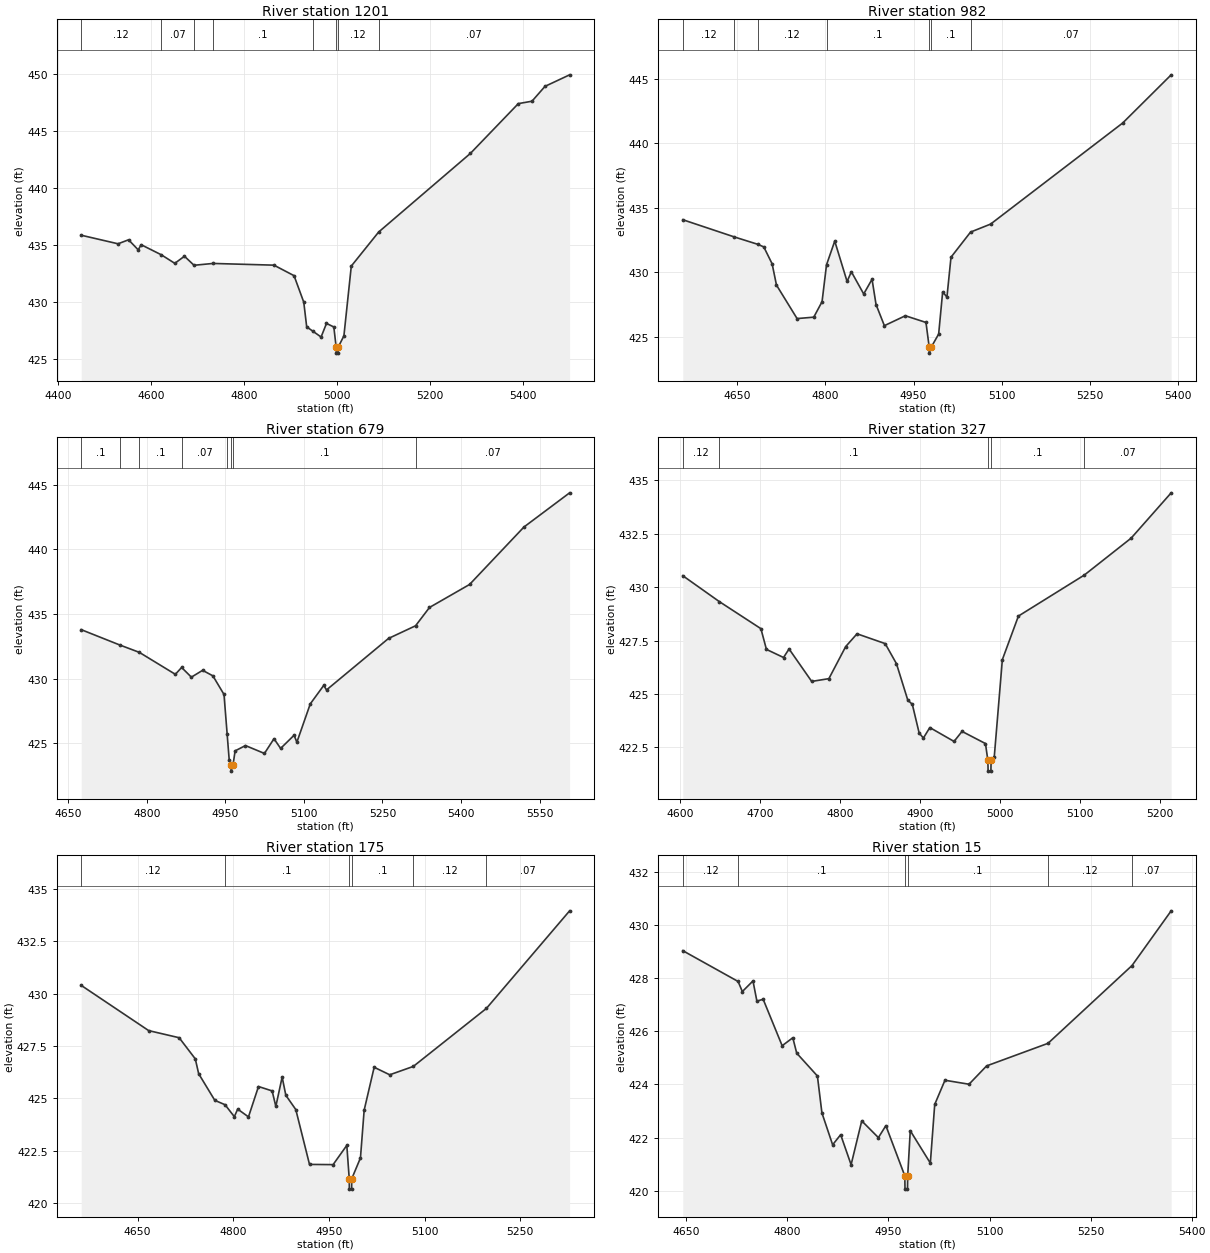
Type RM Length L Ch R = 1,1201,219,219,219
BEGIN DESCRIPTION:
XS7417
END DESCRIPTION:
XS GIS Cut Line= 3
      2396374.33     13592693.44      2396686.81     13593092.71
      2397161.20     13593359.34
#Sta/Elev= 30
  4450.0  435.85  4529.3  435.10  4551.9  435.45  4572.7  434.57  4579.0  435.02
  4622.3  434.14  4651.4  433.39  4672.2  434.01  4692.8  433.22  4733.8  433.38
  4864.8  433.23  4908.1  432.31  4929.0  429.99  4935.3  427.83  4948.9  427.44
  4966.3  426.94  4977.9  428.13  4993.7  427.82  4998.8  426.03  4999.1  425.53
  5002.6  425.53  5002.8  426.03  5015.4  427.04  5031.3  433.15  5090.2  436.13
  5287.6  443.01  5390.8  447.37  5420.2  447.58  5448.2  448.88  5501.2  449.89
#Mann=8,-1,0
  4450.0    0.12       0  4622.3    0.07       0  4692.8    0.12       0
  4733.8     0.1       0  4948.9    0.12       0  4998.8    0.05       0
  5002.8    0.12       0  5090.2    0.07       0
Bank Sta=4998.8,5002.8
Exp/Cntr=0.3,0.1

Type RM Length L Ch R = 1,982,303,303,303
BEGIN DESCRIPTION:
E21236
END DESCRIPTION:
XS GIS Cut Line= 3
      2396284.10     13592990.62      2396640.88     13593321.35
      2396954.64     13593464.57
#Sta/Elev= 30
  4557.1  434.08  4645.1  432.74  4684.9  432.17  4695.0  431.97  4709.2  430.66
  4716.6  429.01  4751.7  426.41  4780.1  426.52  4794.2  427.72  4801.8  430.58
  4815.8  432.42  4836.8  429.29  4844.1  430.04  4865.1  428.32  4879.3  429.46
  4886.1  427.50  4900.3  425.86  4936.0  426.63  4971.1  426.11  4976.5  424.23
  4976.7  423.73  4980.5  424.23  4992.7  425.21  4999.5  428.48  5006.8  428.08
  5013.7  431.17  5047.0  433.12  5081.1  433.74  5305.9  441.58  5388.5  445.32
#Mann=7,-1,0
  4557.1    0.12       0  4645.1    0.07       0  4684.9    0.12       0
  4801.8     0.1       0  4976.5    0.05       0  4980.5     0.1       0
  5047.0    0.07       0
Bank Sta=4976.5,4980.5
Exp/Cntr=0.3,0.1

Type RM Length L Ch R = 1,679,352,352,352
BEGIN DESCRIPTION:
XS7416
END DESCRIPTION:
XS GIS Cut Line= 3
      2396207.65     13593103.15      2396287.50     13593321.88
      2396947.24     13593554.52
#Sta/Elev= 30
  4675.0  433.79  4748.1  432.61  4786.0  432.03  4854.7  430.33  4866.7  430.86
  4885.3  430.11  4906.8  430.64  4926.4  430.21  4947.6  428.77  4953.6  425.70
  4957.6  423.66  4960.9  423.33  4961.2  422.83  4964.9  423.33  4968.8  424.40
  4988.6  424.81  5024.8  424.20  5043.0  425.34  5055.7  424.59  5081.4  425.61
  5086.7  425.07  5112.3  428.04  5138.0  429.47  5143.3  429.12  5261.7  433.11
  5313.3  434.09  5339.9  435.51  5416.4  437.29  5520.2  441.74  5607.4  444.39
#Mann=8,-1,0
  4675.0     0.1       0  4748.1    0.07       0  4786.0     0.1       0
  4866.7    0.07       0  4953.6     0.1       0  4960.9    0.05       0
  4964.9     0.1       0  5313.3    0.07       0
Bank Sta=4960.9,4964.9
Exp/Cntr=0.3,0.1

Type RM Length L Ch R = 1,327,152,152,152
BEGIN DESCRIPTION:
E21235
END DESCRIPTION:
XS GIS Cut Line= 3
      2396221.62     13593390.38      2396427.34     13593610.42
      2396734.66     13593646.88
#Sta/Elev= 30
  4603.5  430.54  4649.1  429.33  4701.2  428.06  4708.1  427.09  4729.5  426.71
  4736.4  427.11  4764.7  425.59  4786.2  425.72  4807.2  427.22  4821.4  427.82
  4856.6  427.36  4870.7  426.42  4884.9  424.71  4890.5  424.52  4899.1  423.17
  4904.4  422.94  4912.4  423.43  4942.7  422.78  4952.7  423.25  4982.0  422.68
  4985.0  421.89  4985.3  421.39  4988.8  421.39  4989.0  421.89  4993.0  422.06
  5003.1  426.61  5023.2  428.65  5105.6  430.57  5164.2  432.30  5214.2  434.42
#Mann=5,-1,0
  4603.5    0.12       0  4649.1     0.1       0  4985.0    0.05       0
  4989.0     0.1       0  5105.6    0.07       0
Bank Sta=4985,4989
Exp/Cntr=0.3,0.1

Type RM Length L Ch R = 1,175,160,160,160
BEGIN DESCRIPTION:
XS7415
END DESCRIPTION:
XS GIS Cut Line= 4
      2396207.62     13593415.58      2396295.83     13593658.59
      2396489.84     13593773.18      2396770.56     13593800.47
#Sta/Elev= 30
  4561.6  430.40  4667.4  428.24  4715.2  427.90  4740.5  426.89  4745.8  426.18
  4771.1  424.91  4787.2  424.70  4801.7  424.13  4807.0  424.49  4823.9  424.12
  4839.6  425.57  4861.0  425.36  4866.8  424.62  4876.7  426.02  4882.5  425.15
  4898.1  424.47  4919.6  421.85  4956.6  421.84  4978.1  422.76  4981.9  421.17
  4982.1  420.67  4985.6  420.67  4985.9  421.17  4999.5  422.16  5005.3  424.44
  5021.0  426.49  5045.4  426.13  5082.4  426.53  5197.0  429.30  5327.5  433.96
#Mann=6,-1,0
  4561.6    0.12       0  4787.2     0.1       0  4981.9    0.05       0
  4985.9     0.1       0  5082.4    0.12       0  5197.0    0.07       0
Bank Sta=4981.9,4985.9
Exp/Cntr=0.3,0.1

Type RM Length L Ch R = 1,15,0,0,0
BEGIN DESCRIPTION:
E21234
END DESCRIPTION:
XS GIS Cut Line= 4
      2396177.33     13593571.35      2396321.87     13593825.26
      2396410.41     13593882.55      2396720.14     13593987.96
#Sta/Elev= 30
  4644.8  429.04  4726.9  427.88  4733.2  427.50  4749.0  427.90  4754.8  427.14
  4764.1  427.21  4792.3  425.46  4808.1  425.76  4813.9  425.18  4844.6  424.32
  4851.3  422.93  4867.2  421.73  4879.1  422.11  4894.6  420.98  4910.4  422.63
  4935.1  422.00  4946.2  422.45  4974.3  420.56  4974.6  420.06  4978.3  420.06
  4978.6  420.56  4982.4  422.26  5012.2  421.04  5018.7  423.25  5033.9  424.16
  5069.6  424.01  5095.7  424.70  5186.8  425.55  5311.5  428.48  5369.6  430.54
#Mann=6,-1,0
  4644.8    0.12       0  4726.9     0.1       0  4974.3    0.05       0
  4978.6     0.1       0  5186.8    0.12       0  5311.5    0.07       0
Bank Sta=4974.3,4978.6
Exp/Cntr=0.3,0.1

Chan Stop Cuts=-1