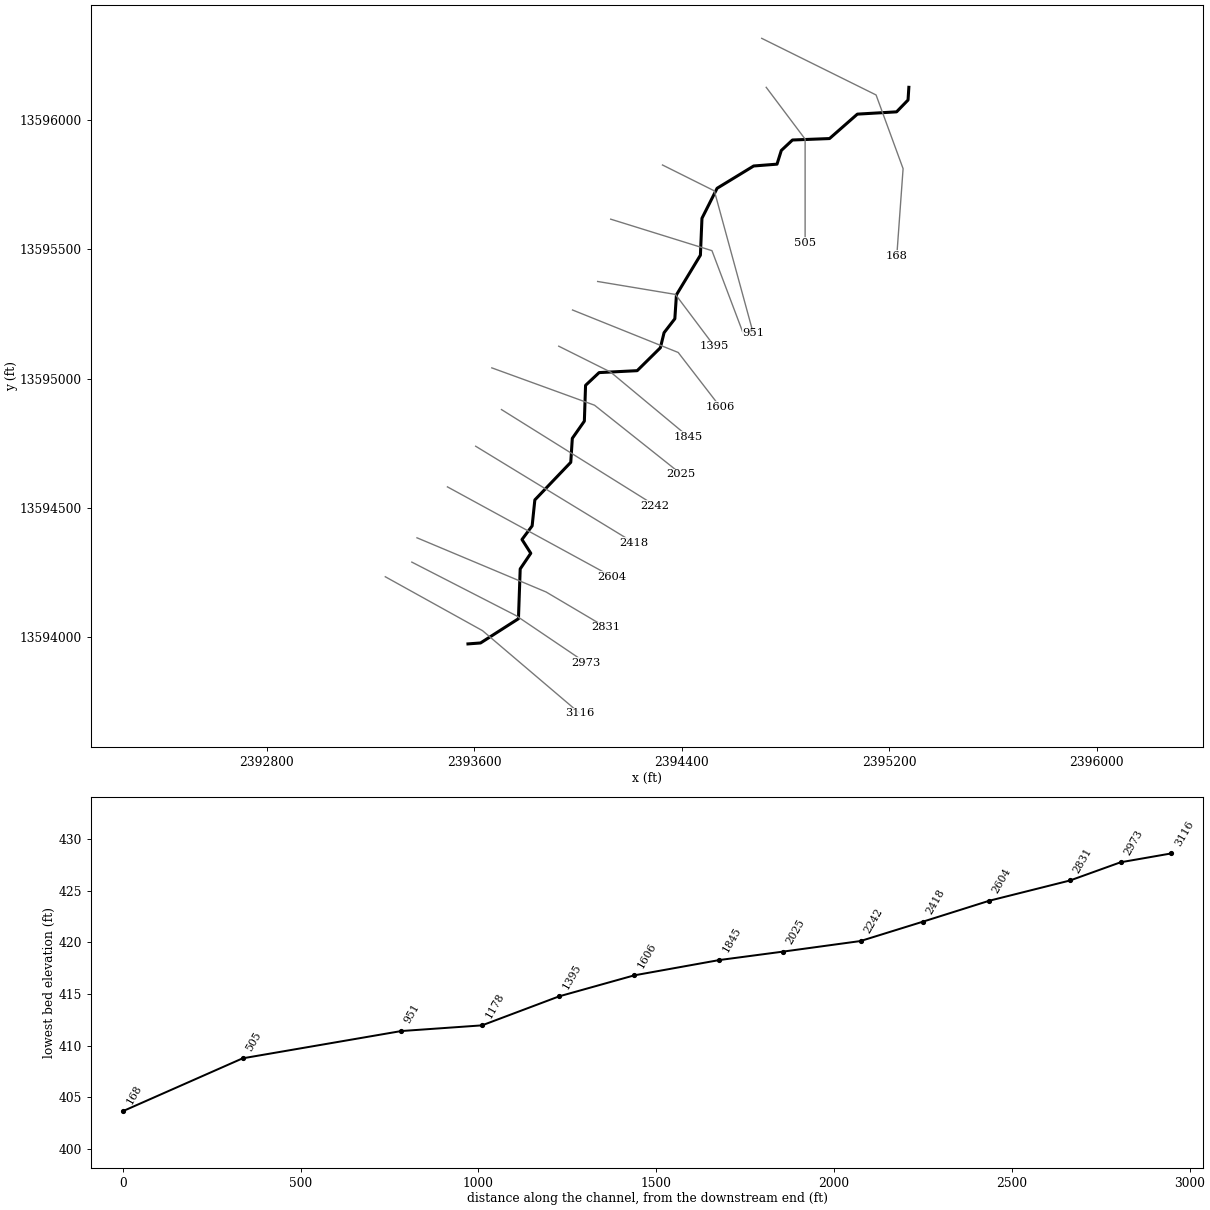
--- Stream0660.prj (project) ---

Proj Title=Stream0660 Base Level Engineering
Current Plan=p01
Default Exp/Contr=0.3,0.1
English Units
Geom File=g01
Flow File=f01
Plan File=p01
BEGIN DESCRIPTION:
Stream0660
END DESCRIPTION:

--- Stream0660.p01 (plan) ---

Plan Title=Multiple Run
Short Identifier=Multiple
Geom File=g01
Flow File=f01
Subcritical Flow
K Sum by GR= 0
Std Step Tol= 0.01
Critical Tol= 0.01
Num of Std Step Trials= 20
Max Error Tol= 0.3
Flow Tol Ratio= 0.001
Split Flow NTrial= 30
Split Flow Tol= 0.02
Split Flow Ratio= 0.02
Log Output Level= 0
Friction Slope Method= 1
Unsteady Friction Slope Method= 2
Unsteady Bridges Friction Slope Method= 1
Parabolic Critical Depth
Global Vel Dist=  1 , 1 , 1
Global Log Level= 0
CheckData=True
Encroach Param= -1, 0, 0, 0
BEGIN DESCRIPTION:
Multiple Run
END DESCRIPTION:

--- Stream0660.f01 (steady flow) ---

Flow Title=Multiple
Number of Profiles=7
Profile Names=10-year,25-year,50-year,1pct_min,100-year,1pct_plu,500-year
River Rch & RM= Stream0660,Reach-1,3116
     388     616     819     529    1055    2104    1732
Boundary for River Rch & Prof#=Stream0660,Reach-1,1
Up Type=0
Dn Type=3
Dn Slope=0.005
Boundary for River Rch & Prof#=Stream0660,Reach-1,2
Up Type=0
Dn Type=3
Dn Slope=0.005
Boundary for River Rch & Prof#=Stream0660,Reach-1,3
Up Type=0
Dn Type=3
Dn Slope=0.005
Boundary for River Rch & Prof#=Stream0660,Reach-1,4
Up Type=0
Dn Type=3
Dn Slope=0.005
Boundary for River Rch & Prof#=Stream0660,Reach-1,5
Up Type=0
Dn Type=3
Dn Slope=0.005
Boundary for River Rch & Prof#=Stream0660,Reach-1,6
Up Type=0
Dn Type=3
Dn Slope=0.005
Boundary for River Rch & Prof#=Stream0660,Reach-1,7
Up Type=0
Dn Type=3
Dn Slope=0.005

--- Stream0660.g01 (geometry) ---

Geom Title=Existing Conditions

River Reach=Stream0660,Reach-1
Reach XY= 30
      2393575.00     13593975.00      2393623.51     13593978.60
      2393769.64     13594072.30      2393776.38     13594264.57
      2393817.21     13594325.10      2393783.28     13594378.22
      2393822.45     13594430.89      2393832.86     13594531.17
      2393971.39     13594676.50      2393977.36     13594769.02
      2394023.77     13594835.51      2394028.44     13594973.78
      2394080.65     13595023.02      2394227.46     13595030.46
      2394316.87     13595118.92      2394331.14     13595177.17
      2394372.67     13595230.97      2394378.83     13595323.42
      2394471.24     13595476.56      2394477.25     13595619.07
      2394535.63     13595735.00      2394676.66     13595821.14
      2394766.65     13595828.19      2394783.17     13595881.03
      2394826.27     13595921.51      2394969.14     13595927.08
      2395076.47     13596021.44      2395227.69     13596030.27
      2395271.88     13596075.98      2395275.00     13596125.00

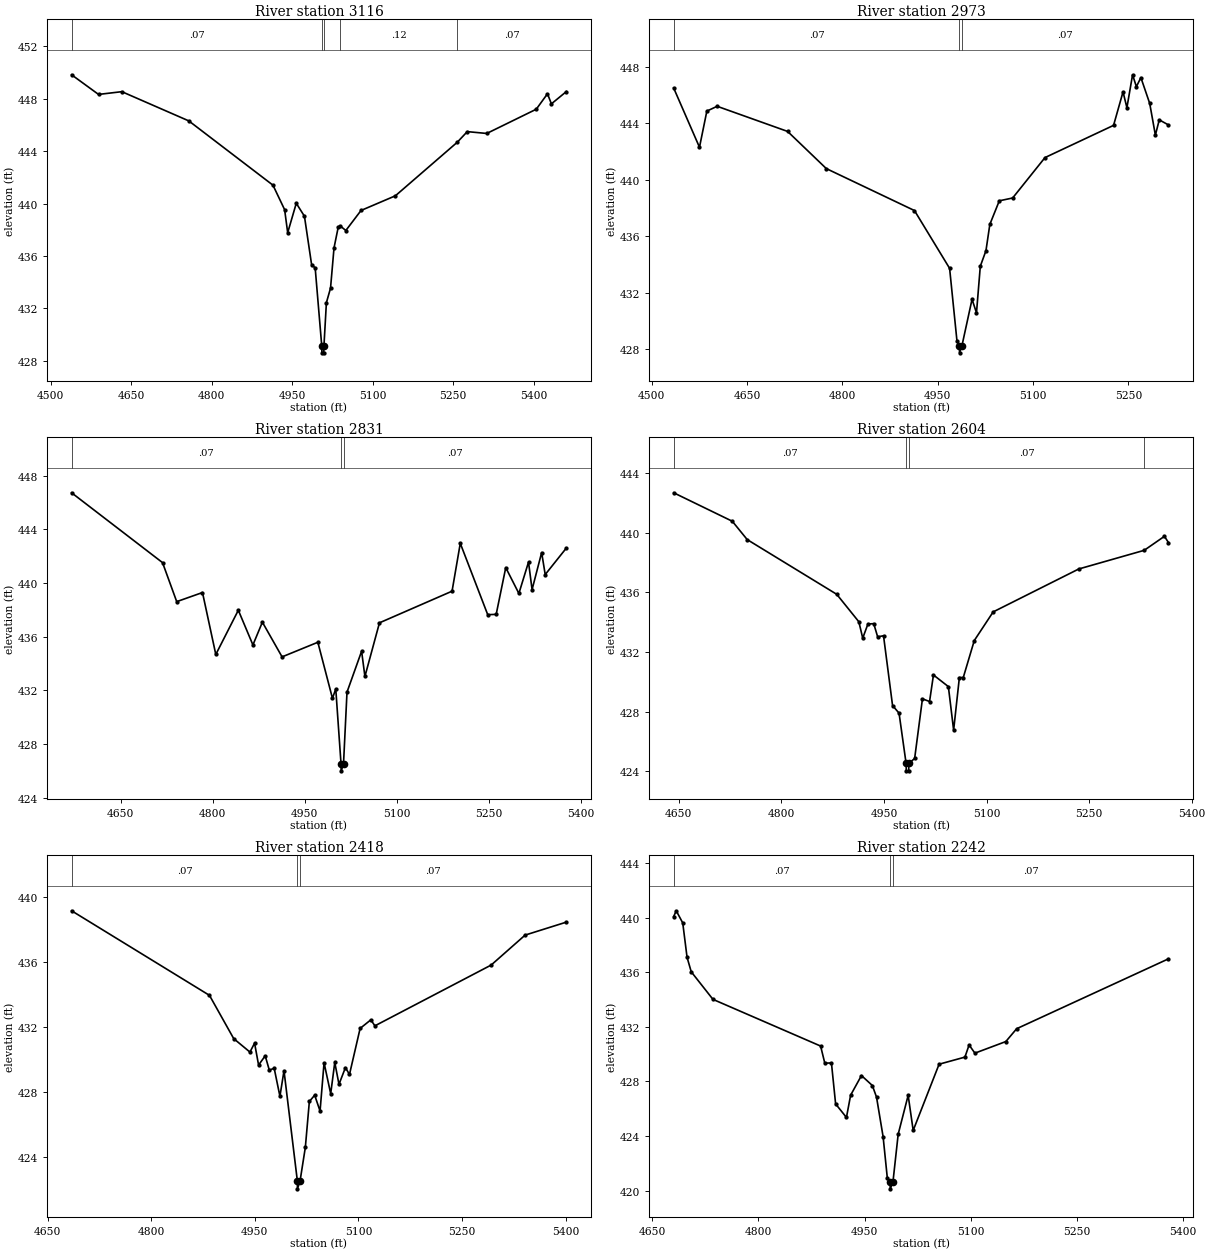
Type RM Length L Ch R = 1,3116,143,143,143
BEGIN DESCRIPTION:
XS7423
END DESCRIPTION:
XS GIS Cut Line= 3
      2393256.21     13594234.40      2393631.25     13594026.04
      2394006.21     13593706.63
#Sta/Elev= 30
  4539.2  449.84  4589.4  448.34  4632.8  448.55  4757.5  446.32  4914.3  441.41
  4936.0  439.54  4941.7  437.78  4957.7  440.03  4972.9  439.04  4986.3  435.33
  4992.9  435.10  5005.2  429.11  5005.4  428.61  5008.9  428.61  5009.2  429.11
  5013.8  432.44  5021.5  433.55  5028.0  436.62  5035.8  438.20  5039.9  438.29
  5050.0  437.95  5078.3  439.48  5142.3  440.60  5257.6  444.69  5276.2  445.50
  5312.5  445.36  5404.7  447.21  5425.6  448.39  5432.9  447.62  5460.8  448.56
#Mann=5,-1,0
  4539.2    0.07       0  5005.2    0.05       0  5009.2    0.07       0
  5039.9    0.12       0  5257.6    0.07       0
Bank Sta=5005.2,5009.2
Exp/Cntr=0.3,0.1

Type RM Length L Ch R = 1,2973,142,142,142
BEGIN DESCRIPTION:
E21245
END DESCRIPTION:
XS GIS Cut Line= 3
      2393358.54     13594290.92      2393760.34     13594084.37
      2394030.96     13593901.13
#Sta/Elev= 30
  4534.5  446.49  4575.1  442.30  4586.7  444.86  4602.9  445.20  4713.8  443.42
  4774.7  440.79  4913.4  437.82  4968.7  433.73  4980.3  428.58  4984.1  428.25
  4984.3  427.75  4988.1  428.25  5004.0  431.54  5011.0  430.58  5017.0  433.88
  5025.9  434.98  5032.0  436.84  5046.9  438.51  5067.9  438.71  5118.8  441.57
  5226.7  443.85  5241.6  446.22  5247.7  445.10  5256.6  447.43  5262.6  446.59
  5269.7  447.23  5283.6  445.40  5292.5  443.16  5298.6  444.24  5313.1  443.88
#Mann=3,-1,0
  4534.5    0.07       0  4984.1    0.05       0  4988.1    0.07       0
Bank Sta=4984.1,4988.1
Exp/Cntr=0.3,0.1

Type RM Length L Ch R = 1,2831,227,227,227
BEGIN DESCRIPTION:
E21244
END DESCRIPTION:
XS GIS Cut Line= 3
      2393378.39     13594384.84      2393876.35     13594175.48
      2394105.29     13594039.81
#Sta/Elev= 30
  4570.1  446.73  4718.3  441.52  4741.4  438.61  4783.4  439.29  4805.1  434.67
  4841.8  437.97  4865.6  435.38  4881.0  437.08  4913.1  434.49  4971.4  435.58
  4995.2  431.40  5000.6  432.10  5009.2  426.49  5009.4  425.99  5013.2  426.49
  5018.9  431.86  5042.7  434.91  5048.1  433.03  5071.8  437.03  5190.1  439.39
  5203.5  442.96  5248.2  437.64  5262.0  437.66  5277.6  441.15  5299.0  439.22
  5314.7  441.56  5320.5  439.51  5336.1  442.27  5341.9  440.63  5376.4  442.61
#Mann=3,-1,0
  4570.1    0.07       0  5009.2    0.05       0  5013.2    0.07       0
Bank Sta=5009.2,5013.2
Exp/Cntr=0.3,0.1

Type RM Length L Ch R = 1,2604,186,186,186
BEGIN DESCRIPTION:
XS7422
END DESCRIPTION:
XS GIS Cut Line= 2
      2393495.82     13594581.61      2394130.62     13594234.72
#Sta/Elev= 30
  4642.6  442.68  4728.3  440.77  4750.1  439.54  4881.0  435.87  4913.3  434.03
  4919.0  432.93  4926.6  433.88  4935.1  433.90  4940.8  433.02  4949.4  433.09
  4962.6  428.41  4972.1  427.90  4982.4  424.53  4982.7  424.03  4986.2  424.03
  4986.4  424.53  4994.9  424.86  5006.3  428.86  5016.7  428.68  5022.4  430.46
  5044.2  429.68  5051.9  426.76  5060.3  430.29  5066.0  430.29  5082.1  432.77
  5109.7  434.69  5234.9  437.57  5330.5  438.82  5360.1  439.76  5366.0  439.34
#Mann=4,-1,0
  4642.6    0.07       0  4982.4    0.05       0  4986.4    0.07       0
  5330.5    0.12       0
Bank Sta=4982.4,4986.4
Exp/Cntr=0.3,0.1

Type RM Length L Ch R = 1,2418,176,176,176
BEGIN DESCRIPTION:
E21243
END DESCRIPTION:
XS GIS Cut Line= 2
      2393604.71     13594738.55      2394215.92     13594365.03
#Sta/Elev= 30
  4684.7  439.17  4884.3  433.95  4919.4  431.28  4942.9  430.45  4949.6  431.00
  4955.4  429.65  4965.0  430.22  4970.9  429.34  4978.0  429.45  4986.3  427.72
  4992.2  429.30  5011.5  422.51  5011.7  422.01  5015.5  422.51  5023.1  424.57
  5028.9  427.40  5036.6  427.79  5044.4  426.81  5050.2  429.79  5059.8  427.88
  5065.7  429.81  5071.8  428.46  5081.1  429.49  5087.0  429.07  5102.4  431.91
  5117.9  432.44  5123.8  432.07  5292.1  435.82  5341.3  437.67  5401.0  438.47
#Mann=3,-1,0
  4684.7    0.07       0  5011.5    0.05       0  5015.5    0.07       0
Bank Sta=5011.5,5015.5
Exp/Cntr=0.3,0.1

Type RM Length L Ch R = 1,2242,217,217,217
BEGIN DESCRIPTION:
XS7421
END DESCRIPTION:
XS GIS Cut Line= 2
      2393704.19     13594880.20      2394296.83     13594509.36
#Sta/Elev= 30
  4680.3  440.08  4683.9  440.50  4693.1  439.61  4699.2  437.09  4705.1  436.03
  4735.8  434.01  4887.9  430.59  4893.8  429.34  4903.2  429.35  4909.1  426.35
  4924.4  425.36  4930.3  426.99  4945.6  428.43  4961.0  427.70  4966.9  426.85
  4976.2  423.95  4982.2  420.90  4986.1  420.63  4986.3  420.13  4990.1  420.63
  4997.5  424.13  5011.6  426.98  5018.7  424.41  5055.3  429.26  5091.8  429.78
  5097.7  430.67  5105.9  430.07  5149.6  430.92  5164.9  431.86  5379.4  436.98
#Mann=3,-1,0
  4680.3    0.07       0  4986.1    0.05       0  4990.1    0.07       0
Bank Sta=4986.1,4990.1
Exp/Cntr=0.3,0.1

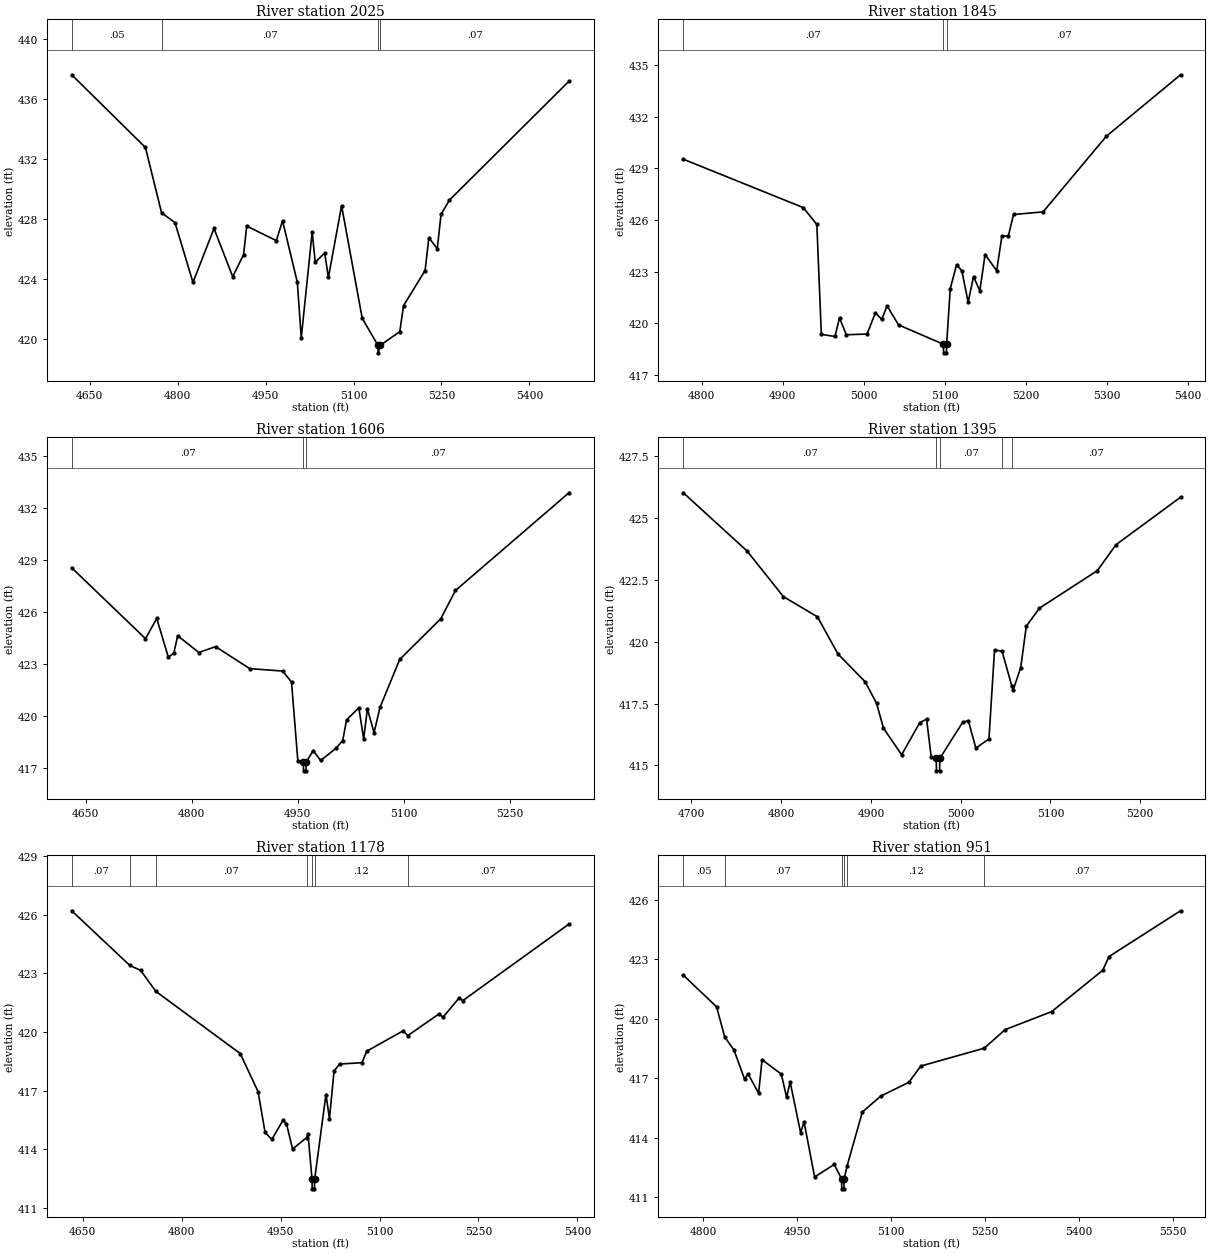
Type RM Length L Ch R = 1,2025,180,180,180
BEGIN DESCRIPTION:
E21242
END DESCRIPTION:
XS GIS Cut Line= 3
      2393666.94     13595041.31      2394063.09     13594897.00
      2394396.98     13594631.02
#Sta/Elev= 30
  4619.1  437.62  4744.9  432.78  4772.4  428.44  4795.4  427.77  4826.0  423.80
  4861.9  427.39  4893.8  424.18  4912.4  425.65  4917.7  427.55  4968.2  426.58
  4978.9  427.90  5004.1  423.80  5010.8  420.11  5029.4  427.14  5034.7  425.14
  5050.8  425.76  5057.1  424.13  5079.6  428.90  5114.8  421.41  5141.6  419.61
  5141.9  419.11  5145.6  419.61  5178.9  420.52  5185.3  422.25  5222.1  424.59
  5228.5  426.77  5242.9  426.05  5249.3  428.32  5263.7  429.28  5467.6  437.19
#Mann=4,-1,0
  4619.1    0.05       0  4772.4    0.07       0  5141.6    0.05       0
  5145.6    0.07       0
Bank Sta=5141.6,5145.6
Exp/Cntr=0.3,0.1

Type RM Length L Ch R = 1,1845,239,239,239
BEGIN DESCRIPTION:
Stream0660 4.0
END DESCRIPTION:
XS GIS Cut Line= 3
      2393924.98     13595125.01      2394125.00     13595025.00
      2394424.97     13594775.03
#Sta/Elev= 30
  4777.2  429.53  4925.4  426.72  4942.1  425.74  4947.7  419.36  4964.5  419.24
  4970.1  420.32  4978.5  419.34  5004.1  419.38  5014.5  420.62  5022.3  420.23
  5028.8  421.02  5043.1  419.91  5098.4  418.79  5098.7  418.29  5102.2  418.29
  5102.4  418.79  5106.9  422.02  5114.7  423.41  5121.2  423.05  5129.0  421.23
  5135.6  422.72  5143.4  421.89  5149.9  423.99  5164.2  423.06  5170.7  425.08
  5178.5  425.05  5185.0  426.32  5221.5  426.47  5299.6  430.86  5391.3  434.43
#Mann=3,-1,0
  4777.2    0.07       0  5098.4    0.05       0  5102.4    0.07       0
Bank Sta=5098.4,5102.4
Exp/Cntr=0.3,0.1

Type RM Length L Ch R = 1,1606,211,211,211
BEGIN DESCRIPTION:
E21241
END DESCRIPTION:
XS GIS Cut Line= 3
      2393978.17     13595264.85      2394385.66     13595100.72
      2394546.94     13594891.34
#Sta/Elev= 30
  4630.3  428.53  4734.7  424.44  4750.6  425.61  4767.0  423.37  4774.8  423.60
  4780.2  424.61  4810.2  423.64  4833.9  423.98  4882.2  422.71  4928.7  422.57
  4941.3  421.94  4950.3  417.37  4958.1  417.31  4958.3  416.81  4961.8  416.81
  4962.1  417.31  4971.9  417.98  4982.6  417.41  5004.2  418.11  5013.8  418.56
  5019.2  419.75  5036.6  420.45  5043.4  418.66  5048.7  420.38  5058.1  419.02
  5066.6  420.48  5094.4  423.24  5152.5  425.59  5173.3  427.22  5333.9  432.86
#Mann=3,-1,0
  4630.3    0.07       0  4958.1    0.05       0  4962.1    0.07       0
Bank Sta=4958.1,4962.1
Exp/Cntr=0.3,0.1

Type RM Length L Ch R = 1,1395,217,217,217
BEGIN DESCRIPTION:
Stream0660 3.0
END DESCRIPTION:
XS GIS Cut Line= 3
      2394075.04     13595374.99      2394375.00     13595325.00
      2394525.00     13595125.00
#Sta/Elev= 30
  4690.9  426.03  4761.8  423.68  4802.4  421.83  4840.4  421.01  4863.2  419.51
  4893.6  418.38  4906.3  417.51  4913.9  416.51  4934.2  415.43  4954.4  416.73
  4962.0  416.87  4967.1  415.36  4972.7  415.28  4973.0  414.78  4976.5  414.78
  4976.7  415.28  5002.3  416.75  5008.5  416.81  5016.9  415.70  5031.5  416.07
  5037.7  419.67  5046.1  419.62  5056.8  418.23  5058.5  418.05  5066.9  418.96
  5073.1  420.63  5087.7  421.36  5152.3  422.88  5173.1  423.93  5245.0  425.85
#Mann=5,-1,0
  4690.9    0.07       0  4972.7    0.05       0  4976.7    0.07       0
  5046.1    0.12       0  5056.8    0.07       0
Bank Sta=4972.7,4976.7
Exp/Cntr=0.3,0.1

Type RM Length L Ch R = 1,1178,227,227,227
BEGIN DESCRIPTION:
E21240
END DESCRIPTION:
XS GIS Cut Line= 3
      2394125.33     13595615.70      2394515.81     13595494.02
      2394637.50     13595171.41
#Sta/Elev= 30
  4633.4  426.21  4721.5  423.41  4737.8  423.16  4761.0  422.08  4888.8  418.90
  4915.9  416.95  4926.5  414.86  4936.8  414.50  4953.8  415.49  4959.0  415.30
  4968.2  414.01  4989.4  414.59  4991.6  414.77  4997.7  412.47  4997.9  411.97
  5001.4  411.97  5001.7  412.47  5018.8  416.80  5024.1  415.57  5031.1  418.00
  5039.4  418.36  5073.4  418.43  5080.7  419.02  5135.7  420.06  5142.9  419.82
  5190.8  420.94  5196.1  420.75  5221.0  421.76  5226.3  421.61  5387.2  425.53
#Mann=7,-1,0
  4633.4    0.07       0  4721.5    0.05       0  4761.0    0.07       0
  4989.4    0.12       0  4997.7    0.05       0  5001.7    0.12       0
  5142.9    0.07       0
Bank Sta=4997.7,5001.7
Exp/Cntr=0.3,0.1

Type RM Length L Ch R = 1,951,446,446,446
BEGIN DESCRIPTION:
Stream0660 2.0
END DESCRIPTION:
XS GIS Cut Line= 3
      2394325.03     13595824.99      2394525.00     13595725.00
      2394675.01     13595174.97
#Sta/Elev= 30
  4768.6  422.21  4821.7  420.61  4834.7  419.09  4849.6  418.42  4866.4  416.96
  4872.0  417.22  4888.8  416.25  4894.3  417.94  4925.1  417.21  4933.5  416.04
  4939.1  416.82  4955.8  414.26  4961.4  414.79  4978.2  412.02  5009.5  412.65
  5021.3  411.92  5021.5  411.42  5025.0  411.42  5025.3  411.92  5029.9  412.56
  5054.4  415.30  5083.7  416.10  5128.7  416.80  5147.7  417.62  5248.8  418.52
  5282.4  419.46  5356.7  420.37  5437.9  422.45  5448.2  423.15  5562.3  425.46
#Mann=6,-1,0
  4768.6    0.05       0  4834.7    0.07       0  5021.3    0.05       0
  5025.3    0.07       0  5029.9    0.12       0  5248.8    0.07       0
Bank Sta=5021.3,5025.3
Exp/Cntr=0.3,0.1

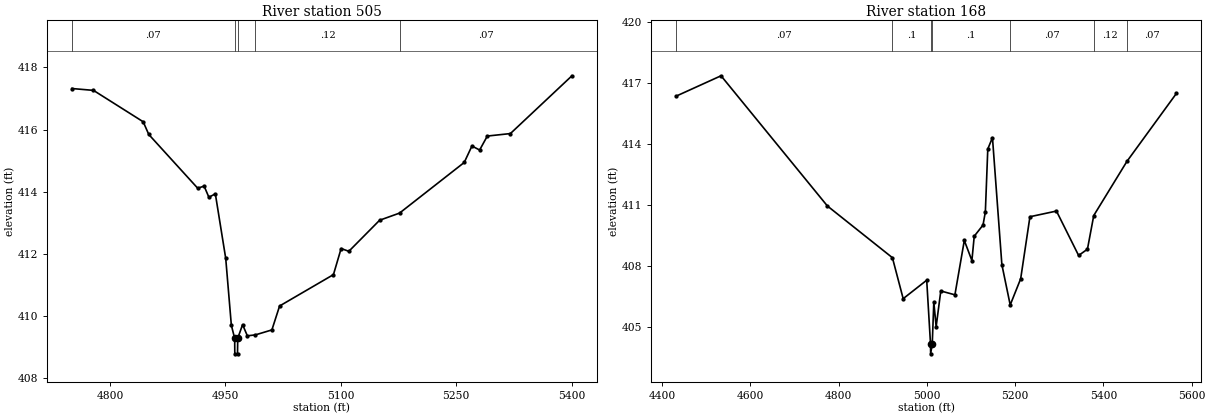
Type RM Length L Ch R = 1,505,337,337,337
BEGIN DESCRIPTION:
Stream0660 1.0
END DESCRIPTION:
XS GIS Cut Line= 3
      2394724.99     13596125.01      2394875.00     13595925.00
      2394875.00     13595525.01
#Sta/Elev= 30
  4750.4  417.32  4778.5  417.26  4843.1  416.25  4850.4  415.84  4914.0  414.11
  4922.3  414.18  4928.5  413.82  4936.9  413.93  4950.4  411.85  4957.7  409.70
  4962.0  409.28  4962.2  408.78  4965.7  408.78  4966.0  409.28  4972.3  409.72
  4978.5  409.36  4988.9  409.39  5010.4  409.55  5020.4  410.32  5090.4  411.33
  5100.4  412.17  5110.4  412.08  5150.4  413.08  5176.3  413.31  5260.4  414.94
  5270.4  415.47  5280.4  415.34  5290.4  415.79  5320.4  415.87  5400.4  417.73
#Mann=5,-1,0
  4750.4    0.07       0  4962.0    0.05       0  4966.0    0.07       0
  4988.9    0.12       0  5176.3    0.07       0
Bank Sta=4962,4966
Exp/Cntr=0.3,0.1

Type RM Length L Ch R = 1,168,0,0,0
BEGIN DESCRIPTION:
XS7420
END DESCRIPTION:
XS GIS Cut Line= 4
      2394707.67     13596314.22      2395148.61     13596095.49
      2395252.78     13595810.76      2395228.47     13595473.93
#Sta/Elev= 30
  4432.4  416.37  4533.7  417.37  4774.7  410.95  4922.0  408.40  4946.4  406.38
  4999.7  407.29  5008.3  404.16  5008.6  403.66  5012.3  404.16  5015.8  406.21
  5021.1  405.00  5031.6  406.76  5063.6  406.57  5084.9  409.25  5102.1  408.26
  5107.4  409.46  5127.3  410.01  5132.6  410.66  5138.1  413.76  5148.7  414.32
  5170.0  408.06  5188.9  406.07  5212.6  407.36  5233.6  410.42  5293.7  410.70
  5343.9  408.51  5363.9  408.82  5378.2  410.48  5453.4  413.15  5565.5  416.50
#Mann=7,-1,0
  4432.4    0.07       0  4922.0     0.1       0  5008.3    0.05       0
  5012.3     0.1       0  5188.9    0.07       0  5378.2    0.12       0
  5453.4    0.07       0
Bank Sta=5008.3,5012.3
Exp/Cntr=0.3,0.1

Chan Stop Cuts=-1