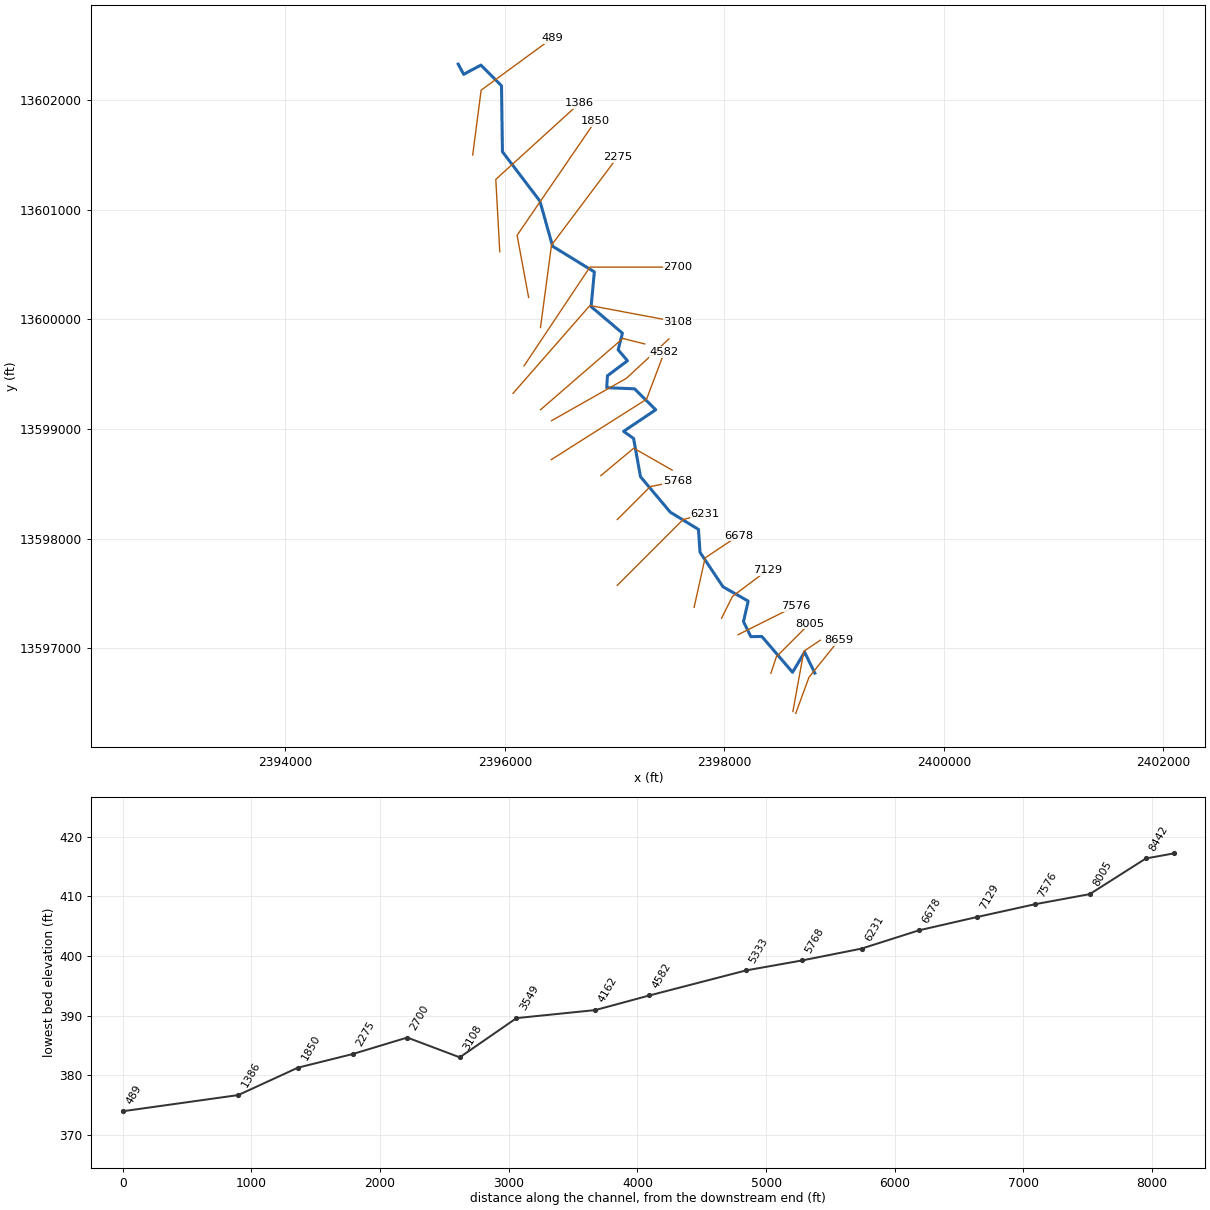
--- Stream0661.prj (project) ---

Proj Title=Stream0661 Base Level Engineering
Current Plan=p01
Default Exp/Contr=0.3,0.1
English Units
Geom File=g01
Flow File=f01
Plan File=p01
BEGIN DESCRIPTION:
Stream0661
END DESCRIPTION:

--- Stream0661.p01 (plan) ---

Plan Title=Multiple Run
Short Identifier=Multiple
Geom File=g01
Flow File=f01
Subcritical Flow
K Sum by GR= 0
Std Step Tol= 0.01
Critical Tol= 0.01
Num of Std Step Trials= 20
Max Error Tol= 0.3
Flow Tol Ratio= 0.001
Split Flow NTrial= 30
Split Flow Tol= 0.02
Split Flow Ratio= 0.02
Log Output Level= 0
Friction Slope Method= 1
Unsteady Friction Slope Method= 2
Unsteady Bridges Friction Slope Method= 1
Parabolic Critical Depth
Global Vel Dist=  1 , 1 , 1
Global Log Level= 0
CheckData=True
Encroach Param= -1, 0, 0, 0
BEGIN DESCRIPTION:
Multiple Run
END DESCRIPTION:

--- Stream0661.f01 (steady flow) ---

Flow Title=Multiple
Number of Profiles=7
Profile Names=10-year,25-year,50-year,1pct_min,100-year,1pct_plu,500-year
River Rch & RM= Stream0661,Reach-1,8659
     507     811    1083     701    1399    2791    2311
River Rch & RM= Stream0661,Reach-1,4582
     678    1101    1484     969    1932    3856    3249
Boundary for River Rch & Prof#=Stream0661,Reach-1,1
Up Type=0
Dn Type=3
Dn Slope=0.005
Boundary for River Rch & Prof#=Stream0661,Reach-1,2
Up Type=0
Dn Type=3
Dn Slope=0.005
Boundary for River Rch & Prof#=Stream0661,Reach-1,3
Up Type=0
Dn Type=3
Dn Slope=0.005
Boundary for River Rch & Prof#=Stream0661,Reach-1,4
Up Type=0
Dn Type=3
Dn Slope=0.005
Boundary for River Rch & Prof#=Stream0661,Reach-1,5
Up Type=0
Dn Type=3
Dn Slope=0.005
Boundary for River Rch & Prof#=Stream0661,Reach-1,6
Up Type=0
Dn Type=3
Dn Slope=0.005
Boundary for River Rch & Prof#=Stream0661,Reach-1,7
Up Type=0
Dn Type=3
Dn Slope=0.005

--- Stream0661.g01 (geometry) ---

Geom Title=Existing Conditions

River Reach=Stream0661,Reach-1
Reach XY= 30
      2398825.00     13596775.00      2398731.82     13596966.26
      2398621.87     13596782.50      2398342.04     13597108.76
      2398241.64     13597107.47      2398174.89     13597245.09
      2398217.65     13597431.38      2397988.39     13597561.67
      2397778.54     13597876.46      2397764.53     13598084.82
      2397507.95     13598241.49      2397236.23     13598564.98
      2397173.32     13598913.17      2397082.42     13598978.44
      2397375.00     13599175.00      2397182.02     13599365.99
      2396928.35     13599376.25      2396935.30     13599485.10
      2397117.40     13599621.65      2397032.83     13599721.58
      2397071.54     13599873.51      2396786.10     13600114.94
      2396815.70     13600431.67      2396435.61     13600664.94
      2396319.16     13601077.29      2395978.14     13601526.64
      2395969.55     13602127.45      2395781.73     13602315.89
      2395624.74     13602232.05      2395575.00     13602325.00

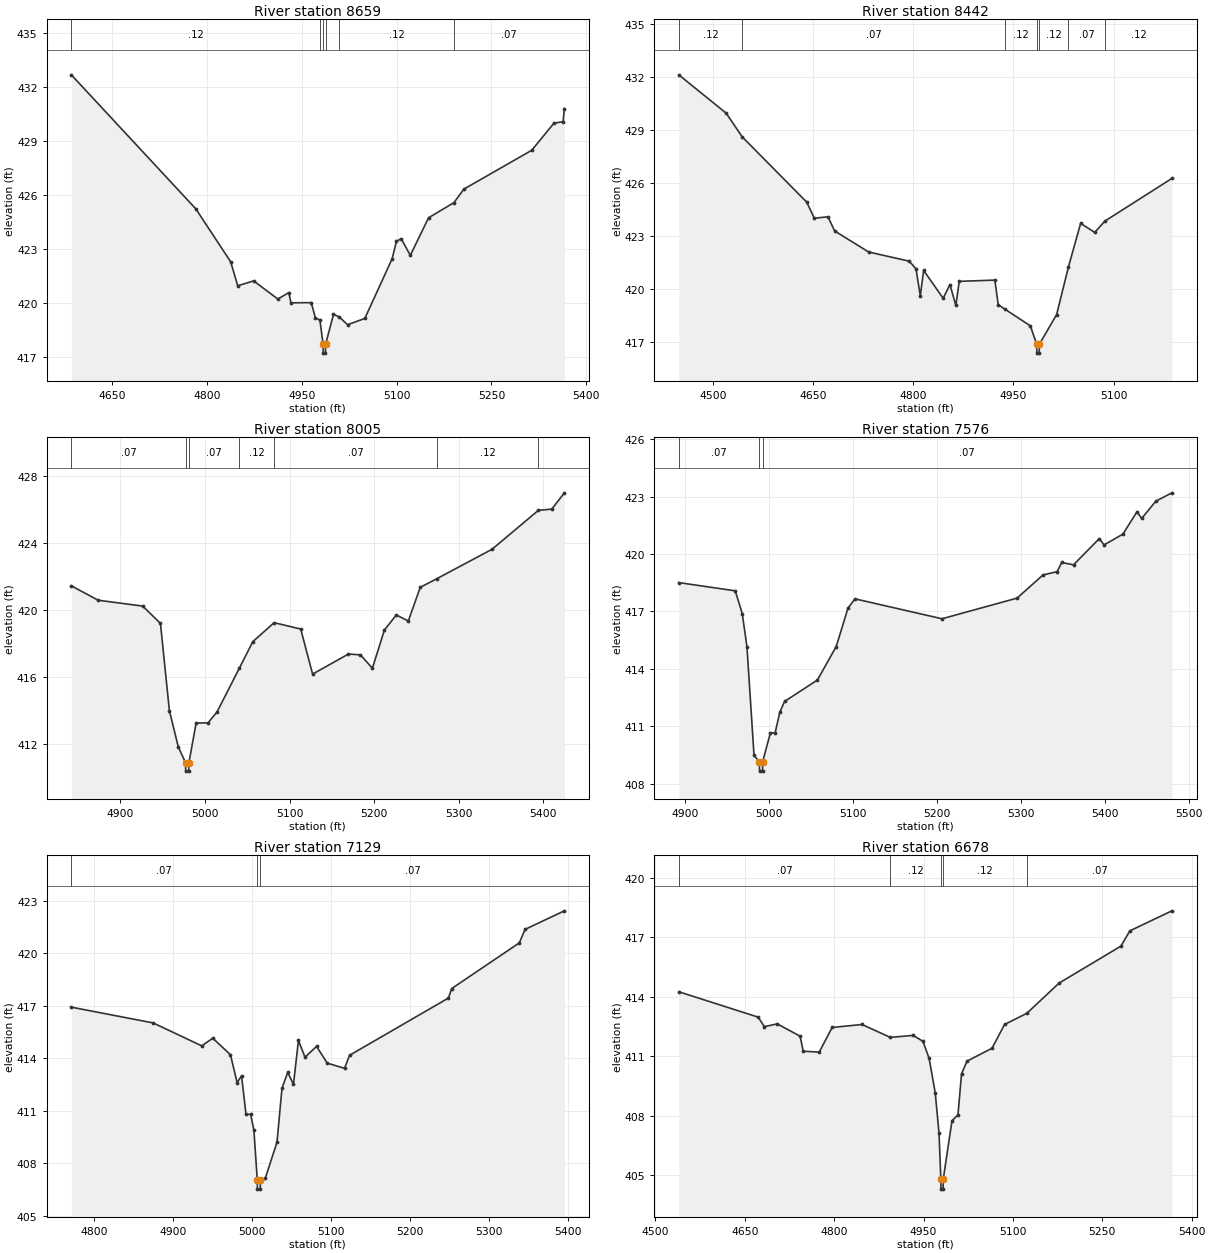
Type RM Length L Ch R = 1,8659,217,217,217
BEGIN DESCRIPTION:
E21660
END DESCRIPTION:
XS GIS Cut Line= 3
      2398650.88     13596408.25      2398771.40     13596736.34
      2399040.71     13597072.42
#Sta/Elev= 30
  4585.3  432.69  4782.3  425.23  4837.5  422.28  4848.6  420.95  4873.8  421.22
  4912.1  420.21  4929.4  420.57  4932.8  420.00  4964.9  420.01  4971.6  419.15
  4978.6  419.05  4983.7  417.70  4983.9  417.20  4987.4  417.20  4987.7  417.70
  5000.1  419.35  5008.7  419.23  5022.5  418.78  5049.7  419.13  5092.9  422.45
  5099.7  423.42  5107.3  423.57  5121.7  422.64  5150.5  424.73  5190.8  425.58
  5206.5  426.33  5313.8  428.49  5349.0  430.00  5363.4  430.08  5365.5  430.81
#Mann=6,-1,0
  4585.3    0.12       0  4978.6    0.07       0  4983.7    0.05       0
  4987.7    0.07       0  5008.7    0.12       0  5190.8    0.07       0
Bank Sta=4983.7,4987.7
Exp/Cntr=0.3,0.1

Type RM Length L Ch R = 1,8442,437,437,437
BEGIN DESCRIPTION:
Stream0661 14.0
END DESCRIPTION:
XS GIS Cut Line= 3
      2398625.01     13596425.04      2398725.00     13596975.00
      2398875.04     13597075.02
#Sta/Elev= 30
  4448.2  432.10  4519.3  429.93  4543.3  428.59  4640.0  424.90  4651.4  423.99
  4671.8  424.07  4681.9  423.27  4732.8  422.08  4793.7  421.56  4803.9  421.12
  4810.3  419.60  4815.3  421.04  4844.6  419.46  4854.7  420.24  4863.6  419.06
  4868.7  420.42  4922.1  420.49  4927.1  419.10  4937.0  418.85  4975.4  417.90
  4984.8  416.86  4985.1  416.36  4988.6  416.36  4988.8  416.86  5014.7  418.54
  5032.4  421.23  5050.7  423.70  5071.8  423.19  5087.2  423.83  5187.5  426.24
#Mann=7,-1,0
  4448.2    0.12       0  4543.3    0.07       0  4937.0    0.12       0
  4984.8    0.05       0  4988.8    0.12       0  5032.4    0.07       0
  5087.2    0.12       0
Bank Sta=4984.8,4988.8
Exp/Cntr=0.3,0.1

Type RM Length L Ch R = 1,8005,429,429,429
BEGIN DESCRIPTION:
Stream0661 13.0
END DESCRIPTION:
XS GIS Cut Line= 4
      2398424.99     13596774.97      2398475.00     13596925.00
      2398675.00     13597125.00      2398775.56     13597225.56
#Sta/Elev= 30
  4841.9  421.43  4873.6  420.57  4926.3  420.22  4947.3  419.19  4957.9  413.98
  4968.4  411.82  4977.0  410.87  4977.2  410.37  4980.7  410.37  4981.0  410.87
  4989.5  413.24  5003.6  413.25  5014.2  413.90  5040.6  416.51  5056.6  418.10
  5081.8  419.23  5113.2  418.85  5127.3  416.16  5169.7  417.36  5183.9  417.31
  5198.0  416.51  5212.2  418.79  5226.3  419.69  5240.5  419.33  5254.6  421.34
  5274.4  421.86  5339.5  423.61  5394.2  425.93  5410.2  426.01  5425.1  426.98
#Mann=7,-1,0
  4841.9    0.07       0  4977.0    0.05       0  4981.0    0.07       0
  5040.6    0.12       0  5081.8    0.07       0  5274.4    0.12       0
  5394.2    0.07       0
Bank Sta=4977,4981
Exp/Cntr=0.3,0.1

Type RM Length L Ch R = 1,7576,447,447,447
BEGIN DESCRIPTION:
Stream0661 12.0
END DESCRIPTION:
XS GIS Cut Line= 4
      2398124.98     13597124.99      2398225.00     13597175.00
      2398525.00     13597325.00      2398649.65     13597387.33
#Sta/Elev= 30
  4892.8  418.51  4959.9  418.08  4968.3  416.89  4973.9  415.15  4982.3  409.48
  4988.6  409.16  4988.9  408.66  4992.4  408.66  4992.6  409.16  5001.8  410.66
  5007.4  410.66  5013.0  411.74  5018.6  412.30  5057.7  413.42  5080.1  415.17
  5094.1  417.18  5102.5  417.66  5205.9  416.62  5295.3  417.70  5326.1  418.91
  5342.8  419.08  5348.4  419.56  5362.4  419.44  5393.1  420.81  5398.7  420.48
  5421.1  421.04  5437.9  422.21  5443.5  421.86  5460.2  422.76  5479.4  423.20
#Mann=3,-1,0
  4892.8    0.07       0  4988.6    0.05       0  4992.6    0.07       0
Bank Sta=4988.6,4992.6
Exp/Cntr=0.3,0.1

Type RM Length L Ch R = 1,7129,451,451,451
BEGIN DESCRIPTION:
Stream0661 11.0
END DESCRIPTION:
XS GIS Cut Line= 4
      2397975.02     13597275.04      2398075.00     13597475.00
      2398275.00     13597625.00      2398394.79     13597714.85
#Sta/Elev= 30
  4771.7  416.92  4875.1  416.02  4936.6  414.71  4950.5  415.15  4972.9  414.20
  4981.3  412.61  4986.9  413.00  4992.5  410.80  4998.4  410.80  5002.5  409.90
  5006.8  407.03  5007.0  406.53  5010.5  406.53  5010.8  407.03  5017.1  407.18
  5031.7  409.21  5038.0  412.29  5045.3  413.20  5052.5  412.51  5058.8  415.02
  5067.1  414.06  5081.7  414.68  5095.3  413.72  5117.1  413.43  5123.4  414.17
  5248.4  417.44  5252.5  417.98  5338.0  420.59  5345.3  421.36  5395.0  422.42
#Mann=3,-1,0
  4771.7    0.07       0  5006.8    0.05       0  5010.8    0.07       0
Bank Sta=5006.8,5010.8
Exp/Cntr=0.3,0.1

Type RM Length L Ch R = 1,6678,447,447,447
BEGIN DESCRIPTION:
Stream0661 10.0
END DESCRIPTION:
XS GIS Cut Line= 4
      2397724.99     13597374.95      2397825.00     13597825.00
      2397975.00     13597925.00      2398129.92     13598028.28
#Sta/Elev= 30
  4539.3  414.25  4672.5  412.97  4682.8  412.49  4704.5  412.63  4742.9  412.01
  4748.1  411.25  4775.0  411.21  4796.7  412.45  4846.7  412.60  4894.3  411.95
  4932.5  412.05  4949.1  411.75  4959.4  410.89  4969.6  409.17  4976.0  407.13
  4979.1  404.80  4979.4  404.30  4982.9  404.30  4983.1  404.80  4997.8  407.75
  5007.8  408.04  5013.8  410.11  5022.9  410.75  5064.9  411.40  5086.0  412.60
  5123.3  413.16  5177.6  414.69  5281.3  416.55  5296.3  417.32  5366.8  418.33
#Mann=5,-1,0
  4539.3    0.07       0  4894.3    0.12       0  4979.1    0.05       0
  4983.1    0.12       0  5123.3    0.07       0
Bank Sta=4979.1,4983.1
Exp/Cntr=0.3,0.1

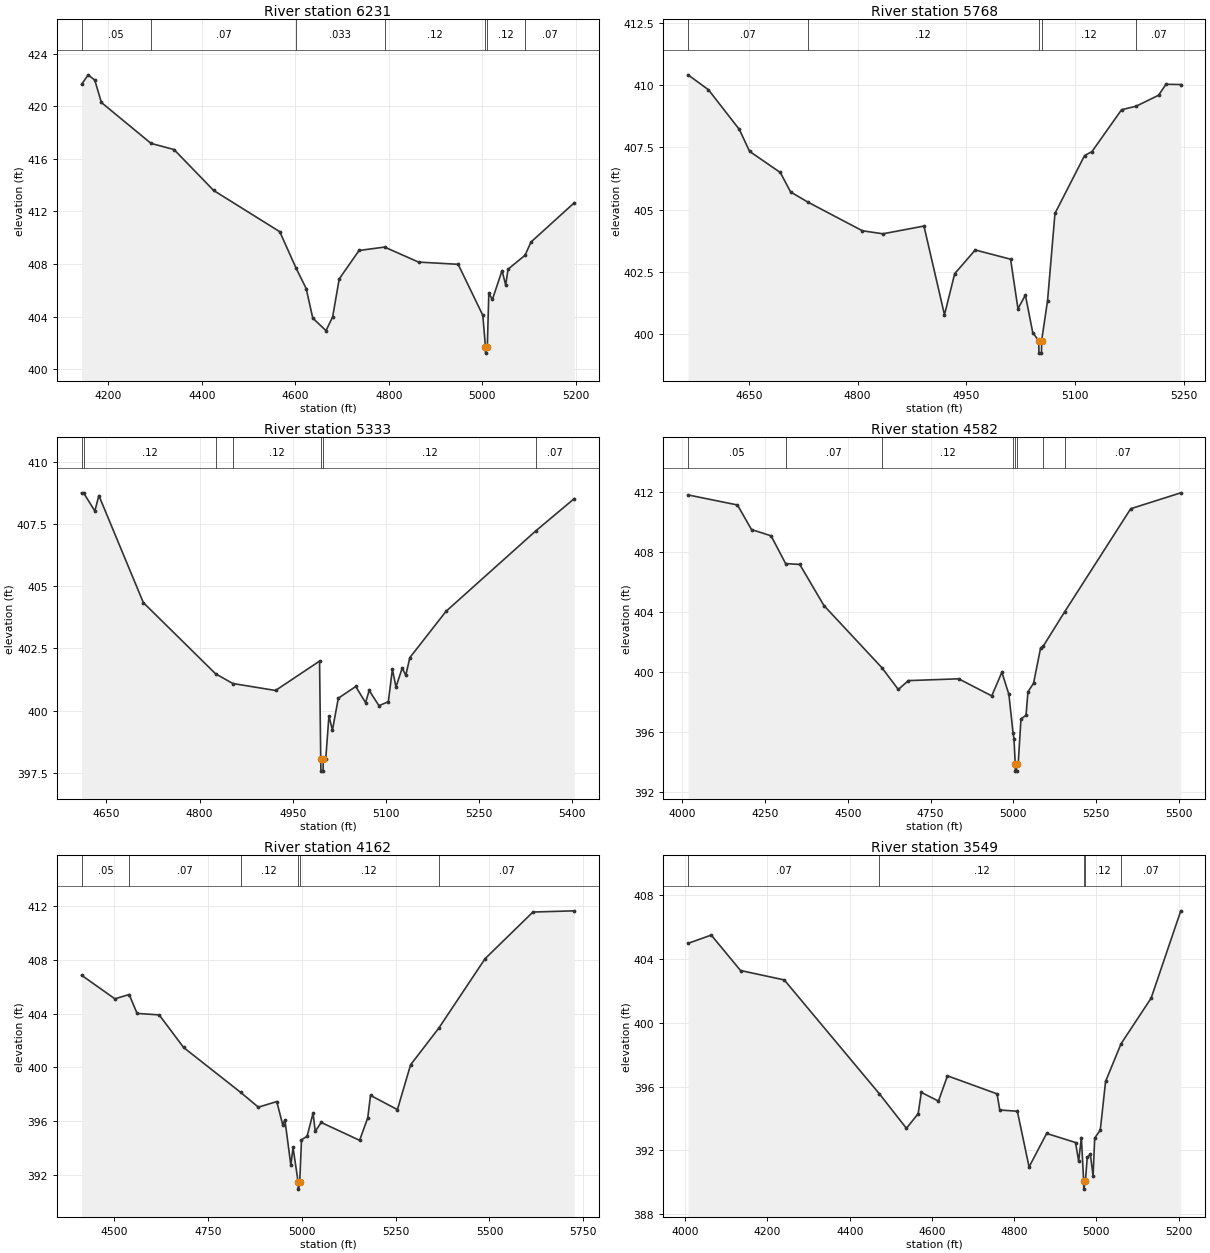
Type RM Length L Ch R = 1,6231,463,463,463
BEGIN DESCRIPTION:
Stream0661 9.0
END DESCRIPTION:
XS GIS Cut Line= 3
      2397025.02     13597575.02      2397625.00     13598175.00
      2397825.04     13598225.01
#Sta/Elev= 30
  4142.6  421.65  4156.7  422.38  4170.9  421.98  4185.0  420.28  4291.3  417.17
  4340.6  416.70  4425.4  413.59  4566.8  410.46  4601.9  407.68  4623.4  406.14
  4637.5  403.89  4665.8  402.94  4680.0  403.98  4694.1  406.87  4736.5  409.03
  4791.2  409.29  4863.8  408.15  4948.7  407.98  5001.4  404.11  5007.1  401.73
  5007.4  401.23  5011.1  401.73  5014.3  405.77  5022.0  405.31  5042.6  407.50
  5050.4  406.41  5055.5  407.61  5091.9  408.67  5104.5  409.67  5197.3  412.66
#Mann=7,-1,0
  4142.6    0.05       0  4291.3    0.07       0  4601.9   0.033       0
  4791.2    0.12       0  5007.1    0.05       0  5011.1    0.12       0
  5091.9    0.07       0
Bank Sta=5007.1,5011.1
Exp/Cntr=0.3,0.1

Type RM Length L Ch R = 1,5768,435,435,435
BEGIN DESCRIPTION:
Stream0661 8.0
END DESCRIPTION:
XS GIS Cut Line= 3
      2397025.03     13598175.03      2397325.00     13598475.00
      2397575.03     13598525.01
#Sta/Elev= 30
  4566.3  410.41  4594.5  409.81  4637.0  408.22  4651.1  407.34  4693.5  406.49
  4707.7  405.71  4731.6  405.30  4806.7  404.15  4835.0  404.03  4891.5  404.34
  4919.8  400.78  4933.9  402.43  4962.2  403.38  5010.9  403.01  5021.1  401.02
  5031.3  401.57  5041.5  400.06  5049.7  399.74  5050.0  399.24  5053.5  399.24
  5053.7  399.74  5061.9  401.35  5072.1  404.85  5112.9  407.17  5123.1  407.33
  5163.9  409.01  5183.9  409.15  5214.9  409.59  5225.1  410.03  5245.5  410.02
#Mann=5,-1,0
  4566.3    0.07       0  4731.6    0.12       0  5049.7    0.05       0
  5053.7    0.12       0  5183.9    0.07       0
Bank Sta=5049.7,5053.7
Exp/Cntr=0.3,0.1

Type RM Length L Ch R = 1,5333,751,751,751
BEGIN DESCRIPTION:
Stream0661 7.0
END DESCRIPTION:
XS GIS Cut Line= 3
      2396875.04     13598575.03      2397175.00     13598825.00
      2397525.02     13598624.99
#Sta/Elev= 30
  4609.9  408.75  4613.1  408.75  4631.3  408.02  4637.8  408.64  4709.4  404.34
  4825.8  401.48  4853.5  401.09  4922.3  400.81  4993.2  401.99  4995.1  398.07
  4995.4  397.57  4998.9  397.57  4999.1  398.07  5003.2  398.07  5008.3  399.78
  5014.0  399.22  5023.4  400.50  5051.5  400.97  5067.3  400.32  5073.1  400.81
  5088.9  400.20  5104.0  400.36  5110.5  401.66  5116.3  400.95  5126.3  401.71
  5132.1  401.42  5138.6  402.13  5196.9  403.99  5341.4  407.22  5403.5  408.52
#Mann=7,-1,0
  4609.9    0.07       0  4613.1    0.12       0  4825.8    0.07       0
  4853.5    0.12       0  4995.1    0.05       0  4999.1    0.12       0
  5341.4    0.07       0
Bank Sta=4995.1,4999.1
Exp/Cntr=0.3,0.1

Type RM Length L Ch R = 1,4582,420,420,420
BEGIN DESCRIPTION:
Stream0661 6.0
END DESCRIPTION:
XS GIS Cut Line= 3
      2396423.25     13598720.57      2397291.48     13599271.16
      2397453.49     13599700.84
#Sta/Elev= 30
  4018.0  411.80  4167.2  411.13  4209.6  409.49  4268.7  409.07  4312.6  407.22
  4355.3  407.16  4428.2  404.42  4602.8  400.28  4652.7  398.82  4683.2  399.41
  4834.9  399.53  4934.8  398.39  4965.3  399.97  4986.5  398.49  4998.9  395.94
  5001.8  395.54  5005.6  393.87  5005.9  393.37  5009.5  393.37  5009.7  393.87
  5014.7  393.91  5023.0  396.86  5038.2  397.09  5044.1  398.67  5060.9  399.23
  5082.3  401.60  5089.9  401.70  5154.5  403.99  5354.2  410.88  5505.3  411.94
#Mann=8,-1,0
  4018.0    0.05       0  4312.6    0.07       0  4602.8    0.12       0
  4998.9    0.07       0  5005.6    0.05       0  5009.7    0.07       0
  5089.9    0.12       0  5154.5    0.07       0
Bank Sta=5005.6,5009.7
Exp/Cntr=0.3,0.1

Type RM Length L Ch R = 1,4162,613,613,613
BEGIN DESCRIPTION:
Stream0661 5.0
END DESCRIPTION:
XS GIS Cut Line= 3
      2396424.98     13599074.99      2397107.96     13599461.74
      2397495.28     13599820.89
#Sta/Elev= 30
  4413.0  406.87  4501.8  405.11  4539.9  405.43  4561.0  404.02  4619.9  403.91
  4685.0  401.48  4836.7  398.14  4884.2  397.03  4933.2  397.45  4949.1  395.71
  4954.9  396.08  4970.8  392.69  4976.5  394.04  4990.3  391.42  4990.6  390.92
  4994.4  391.42  4999.1  394.60  5014.0  394.86  5029.9  396.59  5035.7  395.23
  5051.6  395.89  5154.0  394.56  5175.7  396.24  5183.0  397.91  5254.7  396.85
  5289.8  400.19  5365.1  402.93  5488.3  408.10  5615.8  411.58  5726.1  411.67
#Mann=6,-1,0
  4413.0    0.05       0  4539.9    0.07       0  4836.7    0.12       0
  4990.3    0.05       0  4994.4    0.12       0  5365.1    0.07       0
Bank Sta=4990.3,4994.4
Exp/Cntr=0.3,0.1

Type RM Length L Ch R = 1,3549,441,441,441
BEGIN DESCRIPTION:
Stream0661 4.0
END DESCRIPTION:
XS GIS Cut Line= 3
      2396325.01     13599175.01      2397075.00     13599825.00
      2397274.99     13599775.00
#Sta/Elev= 30
  4006.7  404.97  4063.2  405.49  4134.4  403.27  4240.8  402.68  4472.3  395.54
  4538.0  393.38  4566.5  394.30  4574.2  395.63  4615.9  395.09  4637.8  396.67
  4758.4  395.54  4765.0  394.53  4807.8  394.45  4836.3  390.96  4879.0  393.06
  4949.3  392.49  4956.9  391.32  4963.5  392.80  4969.1  390.07  4969.4  389.57
  4973.3  390.07  4977.8  391.57  4985.4  391.75  4992.0  390.39  4995.9  392.77
  5009.5  393.27  5022.4  396.32  5060.0  398.68  5133.2  401.54  5205.3  407.01
#Mann=5,-1,0
  4006.7    0.07       0  4472.3    0.12       0  4969.1    0.05       0
  4973.3    0.12       0  5060.0    0.07       0
Bank Sta=4969.1,4973.3
Exp/Cntr=0.3,0.1

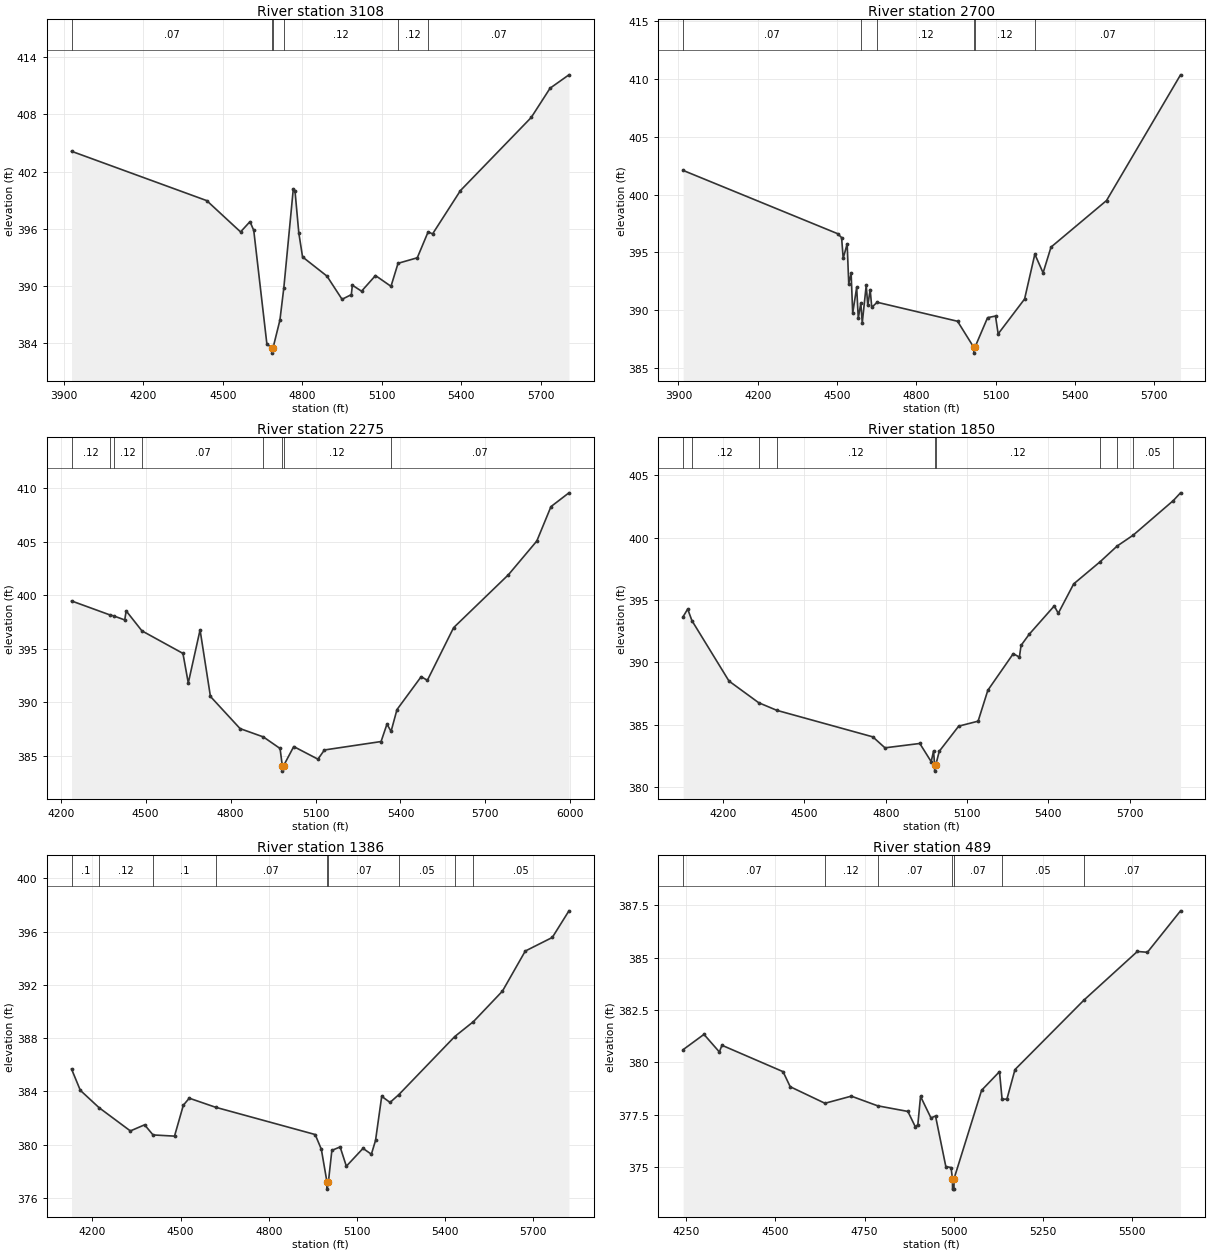
Type RM Length L Ch R = 1,3108,408,408,408
BEGIN DESCRIPTION:
Stream0661 3.0
END DESCRIPTION:
XS GIS Cut Line= 3
      2396075.03     13599325.04      2396775.00     13600125.00
      2397574.99     13599975.00
#Sta/Elev= 30
  3929.4  404.14  4439.5  398.97  4567.2  395.69  4602.8  396.77  4617.0  395.84
  4666.3  383.99  4685.1  383.49  4685.4  382.99  4689.3  383.49  4715.7  386.45
  4730.5  389.85  4766.0  400.15  4772.6  399.98  4786.9  395.60  4801.1  393.07
  4893.2  391.06  4950.1  388.63  4985.2  389.12  4989.0  390.11  5023.7  389.48
  5076.3  391.12  5134.8  389.99  5161.4  392.40  5234.0  392.98  5275.0  395.70
  5291.7  395.48  5396.8  400.02  5663.9  407.68  5735.1  410.75  5806.3  412.15
#Mann=6,-1,0
  3929.4    0.07       0  4685.1    0.05       0  4689.3    0.07       0
  4730.5    0.12       0  5161.4    0.12       0  5275.0    0.07       0
Bank Sta=4685.1,4689.3
Exp/Cntr=0.3,0.1

Type RM Length L Ch R = 1,2700,425,425,425
BEGIN DESCRIPTION:
Stream0661 2.0
END DESCRIPTION:
XS GIS Cut Line= 3
      2396174.98     13599574.97      2396775.00     13600475.00
      2397575.00     13600475.00
#Sta/Elev= 30
  3917.8  402.08  4502.2  396.62  4517.3  396.28  4523.3  394.49  4538.3  395.74
  4544.3  392.30  4553.3  393.21  4559.3  389.76  4574.3  391.98  4580.4  389.32
  4590.0  390.63  4595.4  388.91  4610.4  392.16  4616.4  390.43  4625.4  391.79
  4631.4  390.26  4651.7  390.70  4955.9  389.06  5017.3  386.81  5017.6  386.31
  5021.6  386.81  5069.5  389.37  5099.5  389.51  5109.5  387.97  5209.5  390.98
  5248.3  394.85  5279.5  393.24  5309.5  395.46  5519.5  399.48  5799.5  410.33
#Mann=6,-1,0
  3917.8    0.07       0  4590.0    0.12       0  4651.7    0.12       0
  5017.3    0.05       0  5021.6    0.12       0  5248.3    0.07       0
Bank Sta=5017.3,5021.6
Exp/Cntr=0.3,0.1

Type RM Length L Ch R = 1,2275,425,425,425
BEGIN DESCRIPTION:
Stream0661 1.0
END DESCRIPTION:
XS GIS Cut Line= 3
      2396325.01     13599925.04      2396425.00     13600675.00
      2397025.00     13601475.00
#Sta/Elev= 30
  4238.4  399.47  4373.0  398.17  4387.2  398.07  4426.3  397.69  4431.3  398.54
  4487.0  396.67  4631.8  394.56  4650.7  391.79  4692.3  396.76  4728.9  390.53
  4833.6  387.52  4915.9  386.74  4974.8  385.66  4982.7  384.04  4983.0  383.54
  4987.1  384.04  5023.1  385.84  5108.5  384.66  5131.5  385.52  5331.5  386.31
  5352.3  387.94  5366.8  387.26  5387.7  389.30  5473.1  392.38  5495.0  392.04
  5587.7  396.97  5781.5  401.93  5881.5  405.08  5931.5  408.30  5995.0  409.59
#Mann=8,-1,0
  4238.4    0.12       0  4373.0    0.07       0  4387.2    0.12       0
  4487.0    0.07       0  4915.9    0.12       0  4982.7    0.05       0
  4987.1    0.12       0  5366.8    0.07       0
Bank Sta=4982.7,4987.1
Exp/Cntr=0.3,0.1

Type RM Length L Ch R = 1,1850,464,464,464
BEGIN DESCRIPTION:
XS7426
END DESCRIPTION:
XS GIS Cut Line= 3
      2396216.81     13600198.51      2396111.64     13600764.83
      2396823.57     13601804.42
#Sta/Elev= 30
  4052.3  393.66  4069.1  394.27  4084.8  393.34  4221.6  388.49  4331.3  386.75
  4398.2  386.14  4752.5  384.01  4797.3  383.13  4925.9  383.48  4967.9  382.02
  4976.7  382.88  4980.5  381.76  4980.8  381.26  4984.9  381.76  4997.6  382.85
  5069.4  384.87  5141.1  385.27  5177.0  387.75  5270.9  390.69  5293.5  390.41
  5299.6  391.35  5329.4  392.24  5422.1  394.52  5437.0  393.93  5493.9  396.29
  5591.6  398.07  5654.4  399.33  5713.4  400.20  5861.7  402.98  5888.3  403.60
#Mann=10,-1,0
  4052.3    0.07       0  4084.8    0.12       0  4331.3     0.1       0
  4398.2    0.12       0  4980.5    0.05       0  4984.9    0.12       0
  5591.6    0.05       0  5654.4    0.07       0  5713.4    0.05       0
  5861.7    0.07       0
Bank Sta=4980.5,4984.9
Exp/Cntr=0.3,0.1

Type RM Length L Ch R = 1,1386,897,897,897
BEGIN DESCRIPTION:
XS7425
END DESCRIPTION:
XS GIS Cut Line= 3
      2395953.89     13600615.14      2395917.48     13601274.49
      2396680.84     13601969.19
#Sta/Elev= 30
  4128.8  385.68  4158.7  384.08  4222.3  382.78  4329.0  381.03  4377.4  381.49
  4406.1  380.73  4479.2  380.64  4509.2  382.96  4529.3  383.49  4618.7  382.81
  4957.8  380.76  4978.7  379.66  4998.2  377.16  4998.5  376.66  5002.6  377.16
  5014.6  379.57  5042.7  379.83  5063.9  378.38  5120.6  379.72  5149.0  379.28
  5163.2  380.32  5184.2  383.63  5212.5  383.17  5242.6  383.76  5432.8  388.12
  5496.3  389.24  5595.0  391.53  5672.7  394.54  5764.6  395.56  5821.3  397.56
#Mann=9,-1,0
  4128.8     0.1       0  4222.3    0.12       0  4406.1     0.1       0
  4618.7    0.07       0  4998.2    0.05       0  5002.6    0.07       0
  5242.6    0.05       0  5432.8    0.07       0  5496.3    0.05       0
Bank Sta=4998.2,5002.6
Exp/Cntr=0.3,0.1

Type RM Length L Ch R = 1,489,0,0,0
BEGIN DESCRIPTION:
XS7424
END DESCRIPTION:
XS GIS Cut Line= 3
      2395707.15     13601496.98      2395784.00     13602087.53
      2396430.07     13602559.96
#Sta/Elev= 30
  4240.8  380.61  4299.3  381.34  4342.5  380.50  4349.7  380.82  4521.2  379.56
  4541.3  378.84  4638.8  378.05  4712.8  378.39  4786.4  377.93  4871.5  377.66
  4892.3  376.93  4899.5  377.03  4907.0  378.38  4936.3  377.35  4949.1  377.44
  4978.0  375.03  4992.7  374.98  4996.6  374.45  4996.9  373.95  5000.8  373.95
  5001.1  374.45  5078.4  378.67  5128.6  379.56  5135.9  378.24  5149.5  378.25
  5172.1  379.66  5365.8  382.98  5515.5  385.30  5543.7  385.26  5636.7  387.24
#Mann=7,-1,0
  4240.8    0.07       0  4638.8    0.12       0  4786.4    0.07       0
  4996.6    0.05       0  5001.1    0.07       0  5135.9    0.05       0
  5365.8    0.07       0
Bank Sta=4996.6,5001.1
Exp/Cntr=0.3,0.1

Chan Stop Cuts=-1