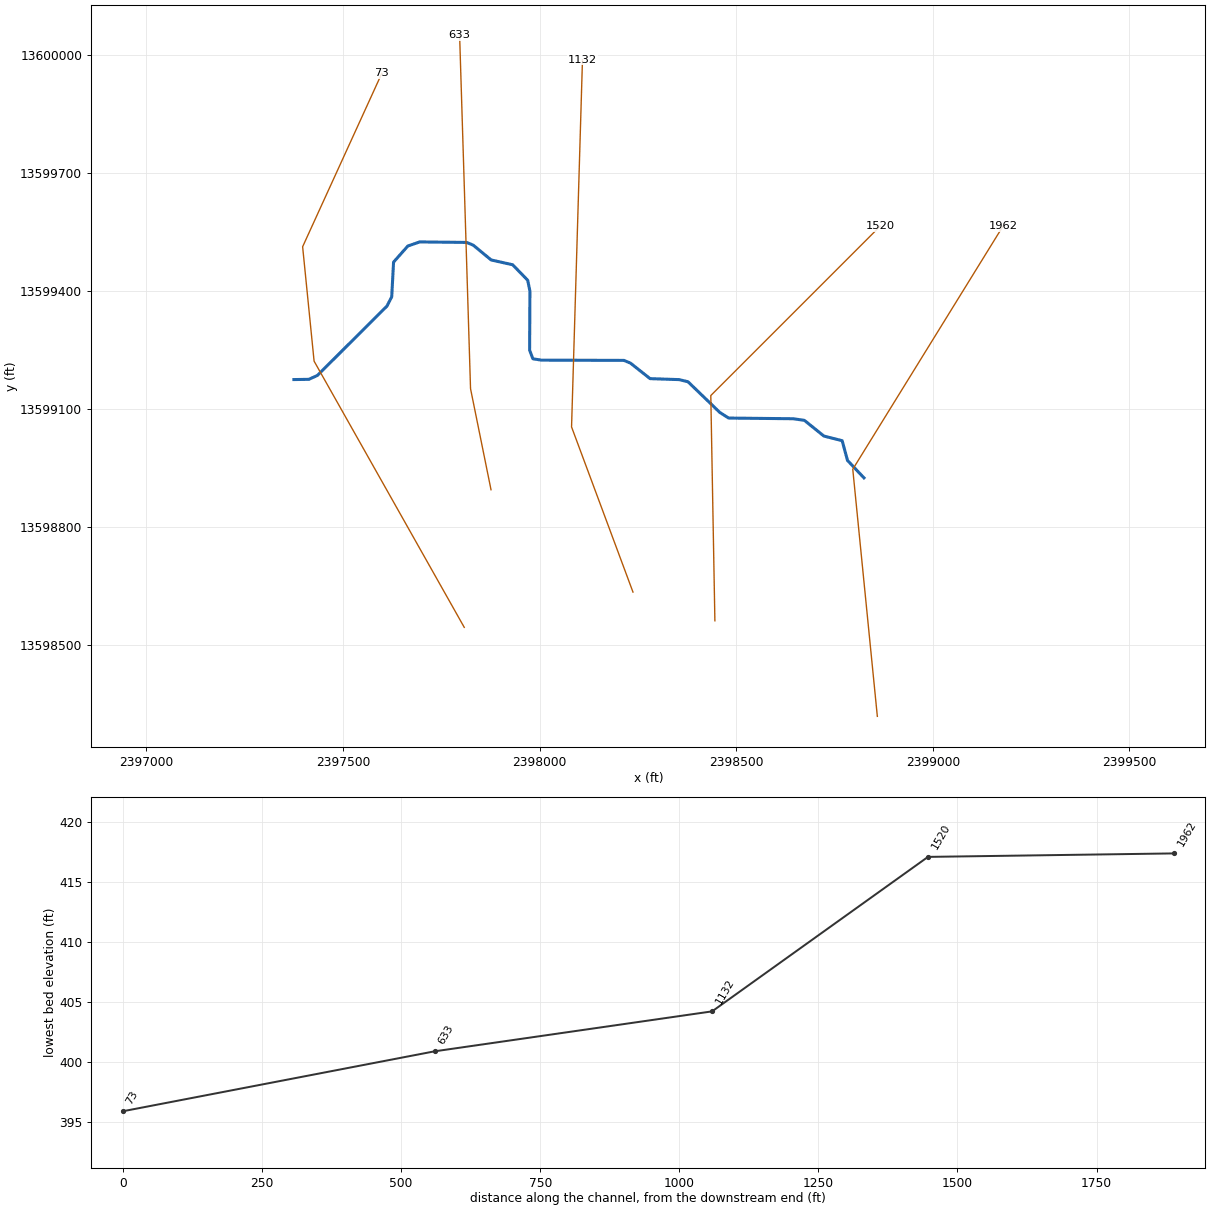
--- Stream0662.prj (project) ---

Proj Title=Stream0662 Base Level Engineering
Current Plan=p01
Default Exp/Contr=0.3,0.1
English Units
Geom File=g01
Flow File=f01
Plan File=p01
BEGIN DESCRIPTION:
Stream0662
END DESCRIPTION:

--- Stream0662.p01 (plan) ---

Plan Title=Multiple Run
Short Identifier=Multiple
Geom File=g01
Flow File=f01
Subcritical Flow
K Sum by GR= 0
Std Step Tol= 0.01
Critical Tol= 0.01
Num of Std Step Trials= 20
Max Error Tol= 0.3
Flow Tol Ratio= 0.001
Split Flow NTrial= 30
Split Flow Tol= 0.02
Split Flow Ratio= 0.02
Log Output Level= 0
Friction Slope Method= 1
Unsteady Friction Slope Method= 2
Unsteady Bridges Friction Slope Method= 1
Parabolic Critical Depth
Global Vel Dist=  1 , 1 , 1
Global Log Level= 0
CheckData=True
Encroach Param= -1, 0, 0, 0
BEGIN DESCRIPTION:
Multiple Run
END DESCRIPTION:

--- Stream0662.f01 (steady flow) ---

Flow Title=Multiple
Number of Profiles=7
Profile Names=10-year,25-year,50-year,1pct_min,100-year,1pct_plu,500-year
River Rch & RM= Stream0662,Reach-1,1962
     234     358     466     295     588    1173     925
Boundary for River Rch & Prof#=Stream0662,Reach-1,1
Up Type=0
Dn Type=3
Dn Slope=0.005
Boundary for River Rch & Prof#=Stream0662,Reach-1,2
Up Type=0
Dn Type=3
Dn Slope=0.005
Boundary for River Rch & Prof#=Stream0662,Reach-1,3
Up Type=0
Dn Type=3
Dn Slope=0.005
Boundary for River Rch & Prof#=Stream0662,Reach-1,4
Up Type=0
Dn Type=3
Dn Slope=0.005
Boundary for River Rch & Prof#=Stream0662,Reach-1,5
Up Type=0
Dn Type=3
Dn Slope=0.005
Boundary for River Rch & Prof#=Stream0662,Reach-1,6
Up Type=0
Dn Type=3
Dn Slope=0.005
Boundary for River Rch & Prof#=Stream0662,Reach-1,7
Up Type=0
Dn Type=3
Dn Slope=0.005

--- Stream0662.g01 (geometry) ---

Geom Title=Existing Conditions

River Reach=Stream0662,Reach-1
Reach XY= 30
      2398825.00     13598925.00      2398783.12     13598969.30
      2398769.58     13599019.53      2398723.16     13599031.26
      2398673.48     13599071.26      2398645.16     13599075.36
      2398480.86     13599077.07      2398458.25     13599091.47
      2398377.42     13599169.46      2398354.95     13599174.87
      2398280.98     13599177.36      2398231.06     13599216.86
      2398214.50     13599223.78      2398004.39     13599224.39
      2397982.91     13599227.91      2397974.58     13599249.58
      2397975.33     13599400.20      2397969.64     13599427.70
      2397931.39     13599467.00      2397876.78     13599479.23
      2397831.08     13599516.91      2397814.50     13599523.81
      2397694.88     13599525.11      2397664.83     13599514.68
      2397628.51     13599473.75      2397623.83     13599385.49
      2397611.59     13599361.70      2397434.79     13599185.51
      2397413.16     13599175.59      2397375.00     13599175.00

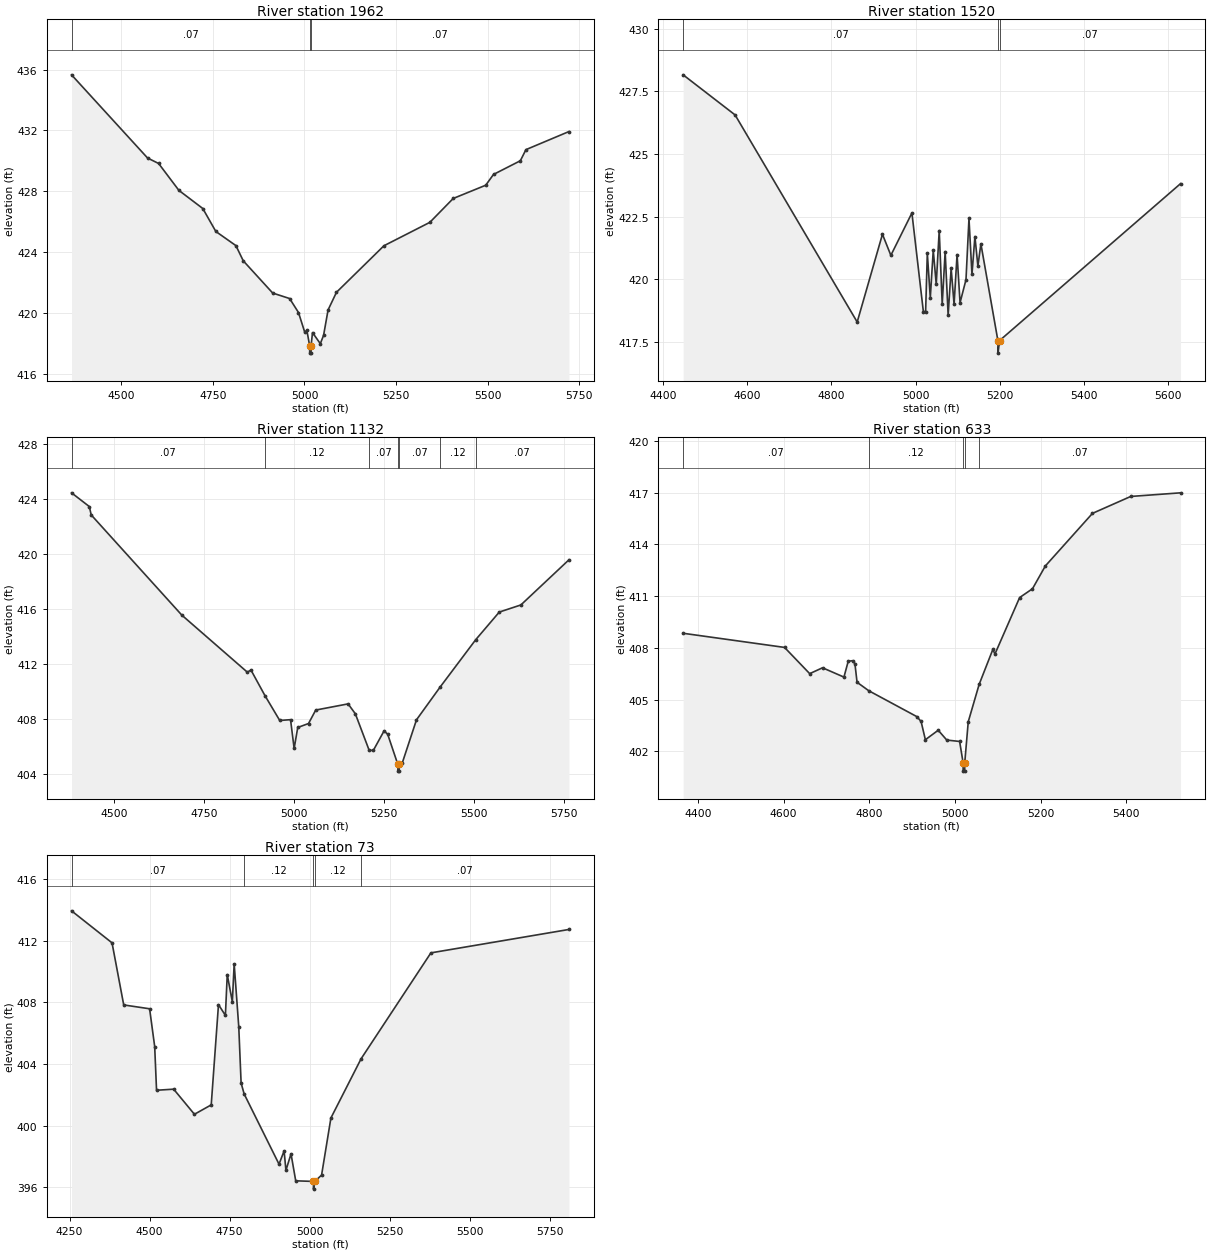
Type RM Length L Ch R = 1,1962,442,442,442
BEGIN DESCRIPTION:
XS7431
END DESCRIPTION:
XS GIS Cut Line= 3
      2398859.03     13598318.37      2398796.53     13598946.88
      2399178.50     13599564.97
#Sta/Elev= 30
  4364.0  435.65  4571.6  430.18  4601.8  429.82  4657.2  428.05  4722.4  426.86
  4758.0  425.35  4812.8  424.42  4832.9  423.42  4913.3  421.30  4959.5  420.94
  4983.7  420.02  5000.7  418.73  5006.6  418.84  5014.1  417.85  5014.4  417.35
  5017.9  417.35  5018.1  417.85  5022.0  418.70  5043.3  417.97  5052.2  418.52
  5064.5  420.19  5087.4  421.35  5217.0  424.41  5342.4  425.95  5406.2  427.52
  5494.9  428.39  5516.2  429.10  5589.5  430.00  5604.7  430.73  5722.2  431.92
#Mann=3,-1,0
  4364.0    0.07       0  5014.1    0.05       0  5018.1    0.07       0
Bank Sta=5014.1,5018.1
Exp/Cntr=0.3,0.1

Type RM Length L Ch R = 1,1520,388,388,388
BEGIN DESCRIPTION:
XS7430
END DESCRIPTION:
XS GIS Cut Line= 3
      2398445.83     13598561.49      2398435.42     13599134.38
      2398865.99     13599564.95
#Sta/Elev= 30
  4447.5  428.16  4571.0  426.56  4861.1  418.30  4921.1  421.80  4941.1  420.96
  4991.1  422.65  5018.3  418.72  5023.7  418.72  5027.7  421.04  5034.8  419.27
  5041.8  421.16  5048.9  419.81  5056.0  421.95  5063.1  419.01  5070.1  421.11
  5077.2  418.57  5084.3  420.44  5091.3  419.01  5098.4  420.99  5105.5  419.07
  5119.6  419.99  5126.7  422.43  5133.8  420.20  5140.8  421.71  5147.9  420.53
  5155.0  421.42  5195.4  417.56  5195.7  417.06  5199.4  417.56  5629.4  423.82
#Mann=3,-1,0
  4447.5    0.07       0  5195.4    0.05       0  5199.4    0.07       0
Bank Sta=5195.4,5199.4
Exp/Cntr=0.3,0.1

Type RM Length L Ch R = 1,1132,499,499,499
BEGIN DESCRIPTION:
XS7429
END DESCRIPTION:
XS GIS Cut Line= 3
      2398237.49     13598634.41      2398081.25     13599054.51
      2398109.03     13599988.58
#Sta/Elev= 30
  4381.3  424.47  4430.7  423.47  4436.0  422.86  4687.8  415.56  4870.0  411.40
  4880.0  411.56  4919.0  409.69  4960.1  407.88  4990.1  407.94  5000.1  405.84
  5010.1  407.37  5040.1  407.66  5060.1  408.64  5150.1  409.09  5170.2  408.37
  5208.6  405.71  5220.2  405.70  5250.2  407.13  5260.2  406.87  5288.2  404.69
  5288.5  404.19  5292.0  404.19  5292.2  404.69  5300.2  404.75  5340.2  407.93
  5406.0  410.32  5504.6  413.76  5570.3  415.78  5630.4  416.30  5764.0  419.59
#Mann=7,-1,0
  4381.3    0.07       0  4919.0    0.12       0  5208.6    0.07       0
  5288.2    0.05       0  5292.2    0.07       0  5406.0    0.12       0
  5504.6    0.07       0
Bank Sta=5288.2,5292.2
Exp/Cntr=0.3,0.1

Type RM Length L Ch R = 1,633,560,560,560
BEGIN DESCRIPTION:
XS7428
END DESCRIPTION:
XS GIS Cut Line= 3
      2397876.39     13598894.77      2397824.31     13599151.74
      2397796.54     13600050.51
#Sta/Elev= 30
  4365.3  408.85  4602.1  408.03  4660.8  406.51  4690.8  406.85  4740.8  406.31
  4750.8  407.23  4760.8  407.26  4766.4  407.09  4771.4  406.01  4798.7  405.52
  4910.9  404.02  4920.9  403.74  4930.9  402.68  4960.9  403.23  4980.9  402.66
  5010.9  402.58  5018.9  401.36  5019.2  400.86  5022.7  400.86  5022.9  401.36
  5031.0  403.72  5056.5  405.89  5088.4  407.91  5093.4  407.65  5151.0  410.92
  5181.0  411.43  5211.0  412.75  5321.1  415.80  5410.4  416.78  5526.7  416.99
#Mann=5,-1,0
  4365.3    0.07       0  4798.7    0.12       0  5018.9    0.05       0
  5022.9    0.12       0  5056.5    0.07       0
Bank Sta=5018.9,5022.9
Exp/Cntr=0.3,0.1

Type RM Length L Ch R = 1,73,0,0,0
BEGIN DESCRIPTION:
XS7427
END DESCRIPTION:
XS GIS Cut Line= 4
      2397808.33     13598544.73      2397426.39     13599221.81
      2397397.22     13599512.85      2397598.63     13599953.86
#Sta/Elev= 30
  4256.1  413.94  4382.7  411.86  4419.2  407.83  4500.1  407.58  4516.0  405.13
  4521.8  402.29  4575.3  402.36  4640.2  400.73  4692.7  401.34  4715.4  407.85
  4737.0  407.15  4742.8  409.80  4758.7  408.03  4764.4  410.50  4778.8  406.40
  4786.1  402.76  4795.6  402.05  4904.6  397.49  4920.5  398.35  4926.2  397.09
  4942.1  398.16  4956.8  396.41  5012.2  396.37  5012.4  395.87  5016.2  396.37
  5037.6  396.78  5066.8  400.49  5161.0  404.33  5379.3  411.21  5810.8  412.73
#Mann=5,-1,0
  4256.1    0.07       0  4795.6    0.12       0  5012.2    0.05       0
  5016.2    0.12       0  5161.0    0.07       0
Bank Sta=5012.2,5016.2
Exp/Cntr=0.3,0.1

Chan Stop Cuts=-1