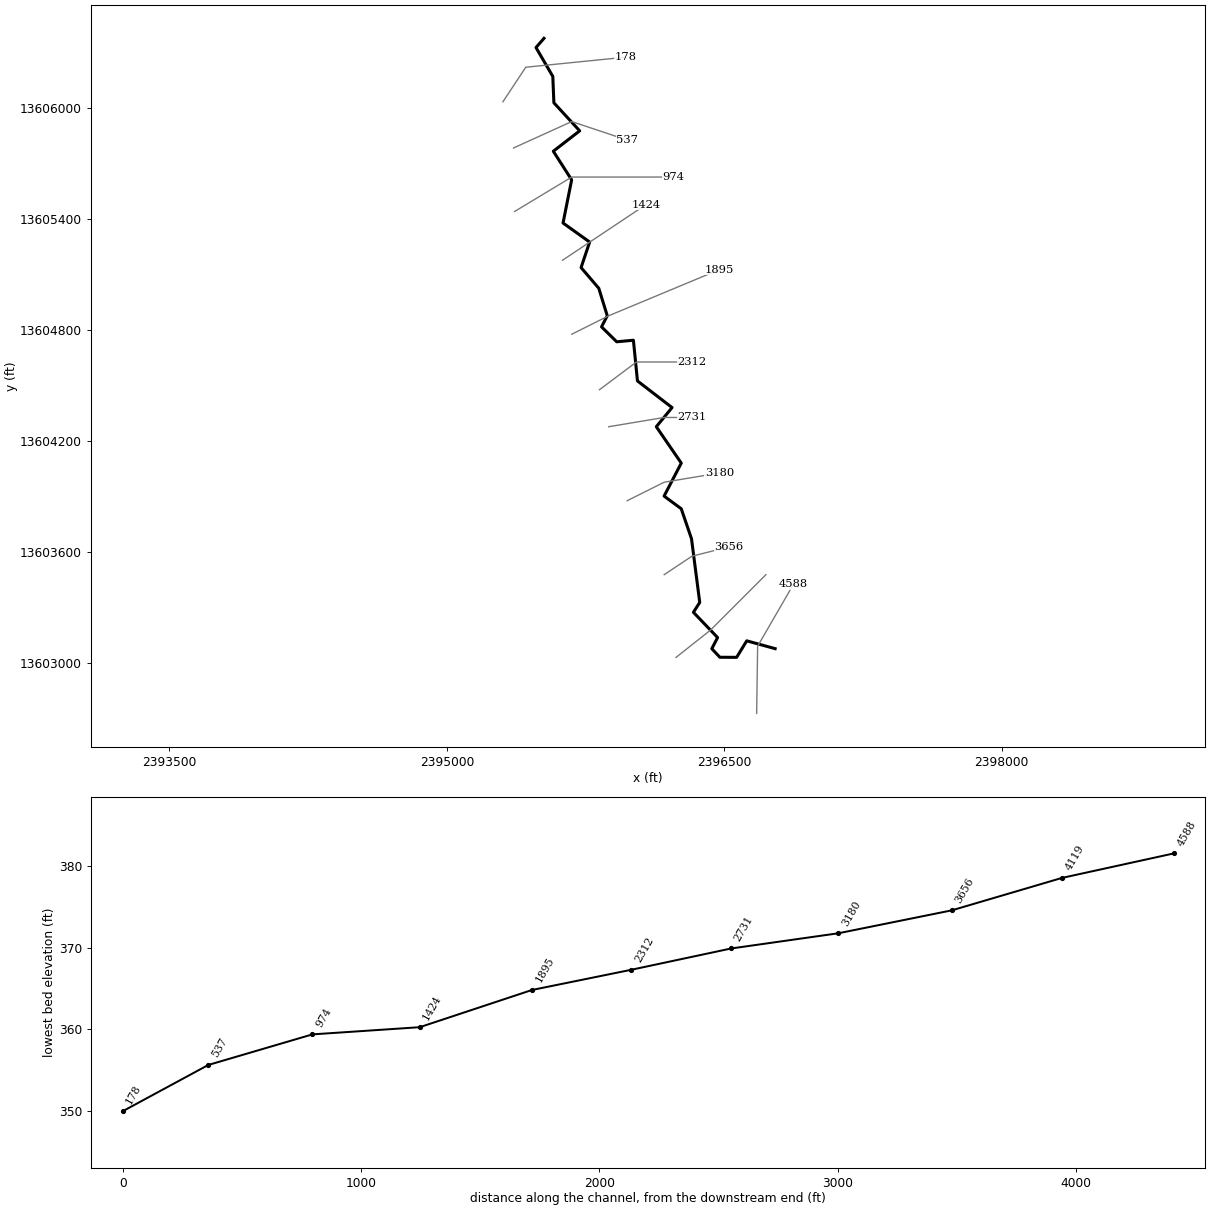
--- Stream0663.prj (project) ---

Proj Title=Stream0663 Base Level Engineering
Current Plan=p01
Default Exp/Contr=0.3,0.1
English Units
Geom File=g01
Flow File=f01
Plan File=p01
BEGIN DESCRIPTION:
Stream0663
END DESCRIPTION:

--- Stream0663.p01 (plan) ---

Plan Title=Multiple Run
Short Identifier=Multiple
Geom File=g01
Flow File=f01
Subcritical Flow
K Sum by GR= 0
Std Step Tol= 0.01
Critical Tol= 0.01
Num of Std Step Trials= 20
Max Error Tol= 0.3
Flow Tol Ratio= 0.001
Split Flow NTrial= 30
Split Flow Tol= 0.02
Split Flow Ratio= 0.02
Log Output Level= 0
Friction Slope Method= 1
Unsteady Friction Slope Method= 2
Unsteady Bridges Friction Slope Method= 1
Parabolic Critical Depth
Global Vel Dist=  1 , 1 , 1
Global Log Level= 0
CheckData=True
Encroach Param= -1, 0, 0, 0
BEGIN DESCRIPTION:
Multiple Run
END DESCRIPTION:

--- Stream0663.f01 (steady flow) ---

Flow Title=Multiple
Number of Profiles=7
Profile Names=10-year,25-year,50-year,1pct_min,100-year,1pct_plu,500-year
River Rch & RM= Stream0663,Reach-1,4588
     469     747     995     642    1281    2556    2104
Boundary for River Rch & Prof#=Stream0663,Reach-1,1
Up Type=0
Dn Type=3
Dn Slope=0.005
Boundary for River Rch & Prof#=Stream0663,Reach-1,2
Up Type=0
Dn Type=3
Dn Slope=0.005
Boundary for River Rch & Prof#=Stream0663,Reach-1,3
Up Type=0
Dn Type=3
Dn Slope=0.005
Boundary for River Rch & Prof#=Stream0663,Reach-1,4
Up Type=0
Dn Type=3
Dn Slope=0.005
Boundary for River Rch & Prof#=Stream0663,Reach-1,5
Up Type=0
Dn Type=3
Dn Slope=0.005
Boundary for River Rch & Prof#=Stream0663,Reach-1,6
Up Type=0
Dn Type=3
Dn Slope=0.005
Boundary for River Rch & Prof#=Stream0663,Reach-1,7
Up Type=0
Dn Type=3
Dn Slope=0.005

--- Stream0663.g01 (geometry) ---

Geom Title=Existing Conditions

River Reach=Stream0663,Reach-1
Reach XY= 30
      2396775.00     13603075.00      2396621.35     13603117.31
      2396566.65     13603028.02      2396476.10     13603028.43
      2396432.46     13603074.75      2396463.75     13603134.99
      2396332.99     13603271.66      2396367.19     13603324.90
      2396322.74     13603669.06      2396267.21     13603831.43
      2396174.47     13603899.88      2396267.39     13604078.33
      2396132.31     13604275.09      2396217.50     13604378.58
      2396030.45     13604522.53      2396008.57     13604742.62
      2395918.30     13604734.31      2395836.24     13604814.95
      2395867.20     13604874.90      2395821.38     13605023.50
      2395725.61     13605135.63      2395771.96     13605273.58
      2395628.04     13605376.42      2395674.63     13605609.83
      2395575.49     13605764.51      2395718.02     13605874.79
      2395578.54     13606026.47      2395572.75     13606169.07
      2395481.87     13606325.12      2395525.00     13606375.00

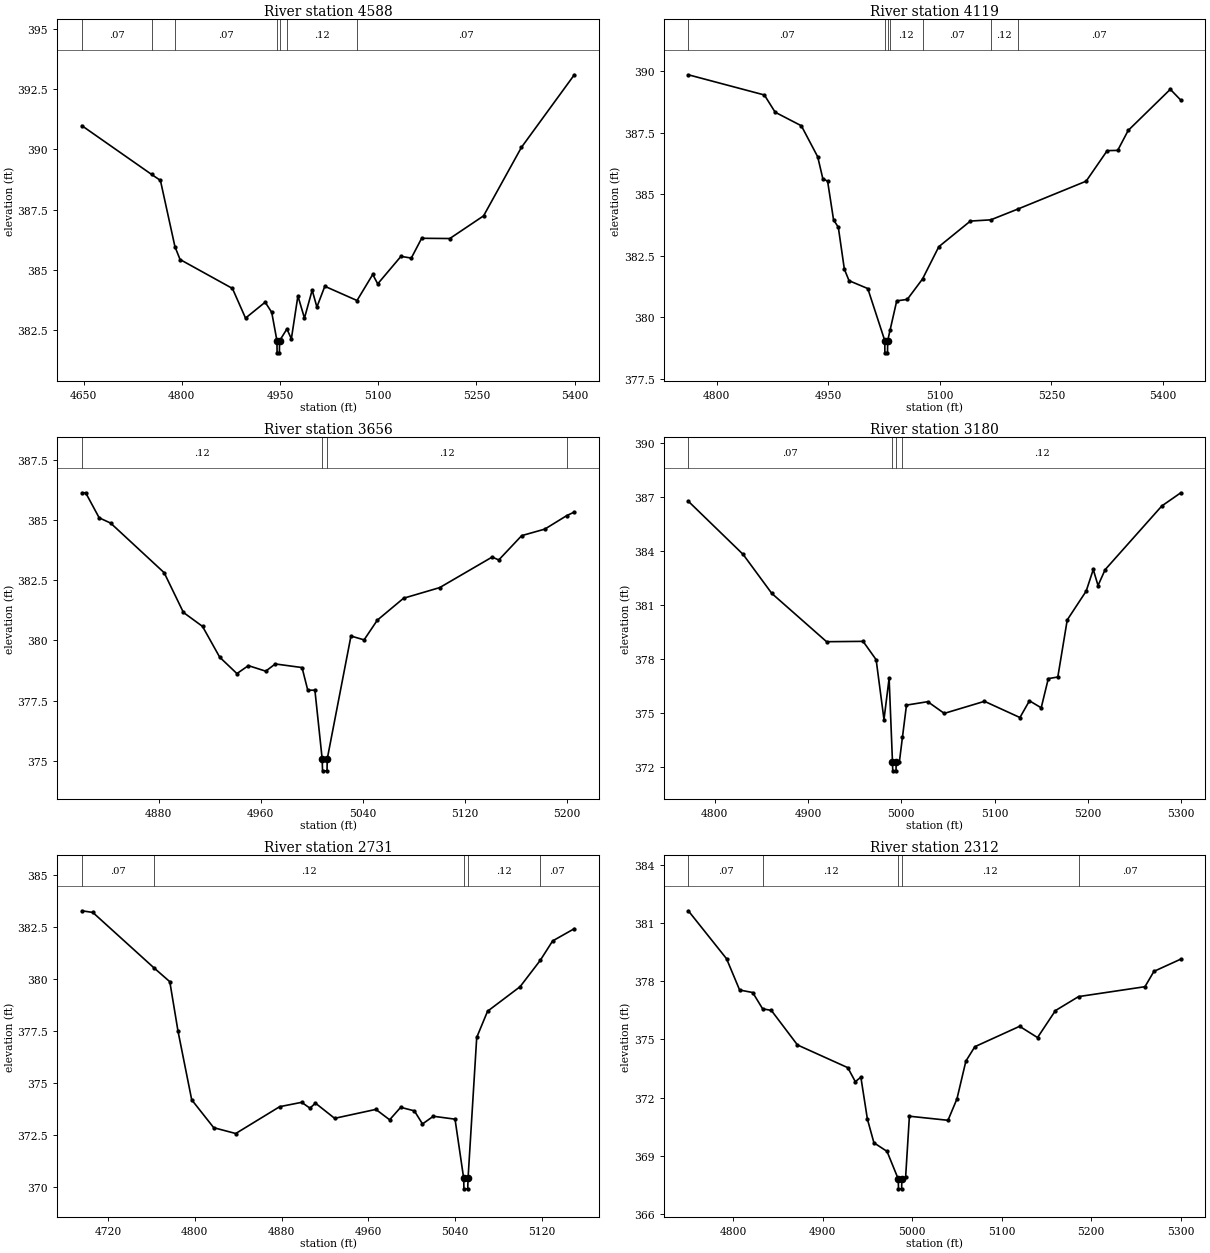
Type RM Length L Ch R = 1,4588,469,469,469
BEGIN DESCRIPTION:
Stream0663 10.0
END DESCRIPTION:
XS GIS Cut Line= 3
      2396675.00     13602725.05      2396680.21     13603088.02
      2396874.98     13603424.97
#Sta/Elev= 30
  4647.4  390.98  4753.8  388.96  4767.4  388.71  4789.6  385.96  4797.4  385.43
  4877.4  384.23  4897.4  383.00  4927.4  383.66  4937.4  383.24  4945.4  382.06
  4945.6  381.56  4949.1  381.56  4949.4  382.06  4960.6  382.55  4967.4  382.14
  4977.4  383.92  4987.4  383.00  4999.2  384.16  5006.4  383.46  5018.5  384.32
  5067.7  383.73  5091.7  384.81  5099.3  384.42  5134.8  385.56  5150.6  385.49
  5166.4  386.31  5209.4  386.30  5261.0  387.24  5318.8  390.08  5399.6  393.09
#Mann=7,-1,0
  4647.4    0.07       0  4753.8    0.12       0  4789.6    0.07       0
  4945.4    0.05       0  4949.4    0.07       0  4960.6    0.12       0
  5067.7    0.07       0
Bank Sta=4945.4,4949.4
Exp/Cntr=0.3,0.1

Type RM Length L Ch R = 1,4119,463,463,463
BEGIN DESCRIPTION:
Stream0663 9.0
END DESCRIPTION:
XS GIS Cut Line= 3
      2396238.64     13603027.48      2396425.00     13603175.00
      2396724.97     13603474.97
#Sta/Elev= 30
  4762.0  389.85  4864.2  389.03  4878.7  388.33  4913.9  387.78  4935.9  386.52
  4942.8  385.63  4949.2  385.53  4957.2  383.96  4963.6  383.66  4971.7  381.96
  4978.0  381.49  5003.2  381.17  5026.0  379.06  5026.2  378.56  5029.7  378.56
  5030.0  379.06  5033.3  379.50  5042.1  380.67  5056.3  380.73  5076.8  381.56
  5098.7  382.87  5141.1  383.91  5168.5  383.96  5205.1  384.40  5296.7  385.53
  5325.0  386.77  5339.1  386.78  5353.2  387.59  5409.8  389.26  5423.9  388.82
#Mann=7,-1,0
  4762.0    0.07       0  5026.0    0.05       0  5030.0    0.07       0
  5033.3    0.12       0  5076.8    0.07       0  5168.5    0.12       0
  5205.1    0.07       0
Bank Sta=5026,5030
Exp/Cntr=0.3,0.1

Type RM Length L Ch R = 1,3656,476,476,476
BEGIN DESCRIPTION:
Stream0663 8.0
END DESCRIPTION:
XS GIS Cut Line= 3
      2396174.97     13603474.98      2396325.00     13603575.00
      2396525.03     13603625.01
#Sta/Elev= 30
  4819.6  386.13  4822.6  386.13  4833.2  385.09  4842.2  384.87  4884.2  382.81
  4899.3  381.16  4914.3  380.58  4927.8  379.30  4941.3  378.62  4950.3  378.95
  4963.9  378.72  4971.4  379.02  4992.4  378.87  4996.9  377.93  5002.5  377.93
  5008.2  375.08  5008.5  374.58  5012.0  374.58  5012.2  375.08  5030.8  380.18
  5041.1  380.02  5051.5  380.84  5072.1  381.75  5100.4  382.19  5141.6  383.46
  5146.8  383.34  5164.8  384.35  5182.9  384.62  5200.1  385.18  5206.1  385.33
#Mann=4,-1,0
  4819.6    0.12       0  5008.2    0.05       0  5012.2    0.12       0
  5200.1    0.07       0
Bank Sta=5008.2,5012.2
Exp/Cntr=0.3,0.1

Type RM Length L Ch R = 1,3180,449,449,449
BEGIN DESCRIPTION:
Stream0663 7.0
END DESCRIPTION:
XS GIS Cut Line= 3
      2395974.98     13603874.99      2396175.00     13603975.00
      2396475.03     13604025.01
#Sta/Elev= 30
  4771.7  386.74  4830.4  383.79  4861.2  381.62  4919.9  378.94  4959.0  378.96
  4973.0  377.94  4981.4  374.62  4986.9  376.91  4990.5  372.27  4990.8  371.77
  4994.3  371.77  4994.5  372.27  4997.9  372.27  5001.2  373.64  5005.5  375.42
  5028.3  375.61  5046.0  374.96  5089.1  375.63  5127.1  374.73  5137.3  375.66
  5149.9  375.27  5157.5  376.89  5167.7  376.98  5177.8  380.15  5198.1  381.75
  5205.7  382.95  5210.8  382.06  5218.4  382.94  5279.2  386.48  5299.5  387.21
#Mann=4,-1,0
  4771.7    0.07       0  4990.5    0.05       0  4994.5    0.07       0
  5001.2    0.12       0
Bank Sta=4990.5,4994.5
Exp/Cntr=0.3,0.1

Type RM Length L Ch R = 1,2731,419,419,419
BEGIN DESCRIPTION:
Stream0663 6.0
END DESCRIPTION:
XS GIS Cut Line= 3
      2395875.05     13604275.01      2396175.00     13604325.00
      2396325.01     13604325.00
#Sta/Elev= 30
  4695.9  383.28  4706.0  383.20  4762.5  380.53  4777.0  379.87  4784.6  377.48
  4797.2  374.19  4817.5  372.85  4837.8  372.57  4878.3  373.86  4898.6  374.07
  4906.2  373.79  4911.3  374.03  4929.0  373.30  4967.0  373.73  4979.7  373.23
  4989.9  373.83  5002.5  373.66  5010.0  373.03  5020.0  373.40  5040.0  373.26
  5048.0  370.41  5048.2  369.91  5051.7  369.91  5052.0  370.41  5060.0  377.19
  5070.0  378.45  5100.0  379.63  5118.5  380.89  5130.0  381.83  5150.0  382.42
#Mann=5,-1,0
  4695.9    0.07       0  4762.5    0.12       0  5048.0    0.05       0
  5052.0    0.12       0  5118.5    0.07       0
Bank Sta=5048,5052
Exp/Cntr=0.3,0.1

Type RM Length L Ch R = 1,2312,417,417,417
BEGIN DESCRIPTION:
Stream0663 5.0
END DESCRIPTION:
XS GIS Cut Line= 3
      2395824.99     13604474.99      2396025.00     13604625.00
      2396324.99     13604625.00
#Sta/Elev= 30
  4750.0  381.62  4792.7  379.15  4807.3  377.54  4821.9  377.41  4833.0  376.57
  4842.7  376.49  4871.9  374.71  4928.1  373.54  4936.5  372.82  4942.7  373.05
  4950.0  370.89  4957.3  369.67  4971.9  369.23  4984.5  367.80  4984.7  367.30
  4988.2  367.30  4988.5  367.80  4992.7  367.91  4996.9  371.04  5040.0  370.83
  5050.0  371.93  5060.0  373.88  5070.0  374.62  5120.0  375.67  5140.0  375.09
  5160.0  376.48  5185.8  377.20  5260.0  377.71  5270.0  378.50  5300.0  379.13
#Mann=5,-1,0
  4750.0    0.07       0  4833.0    0.12       0  4984.5    0.05       0
  4988.5    0.12       0  5185.8    0.07       0
Bank Sta=4984.5,4988.5
Exp/Cntr=0.3,0.1

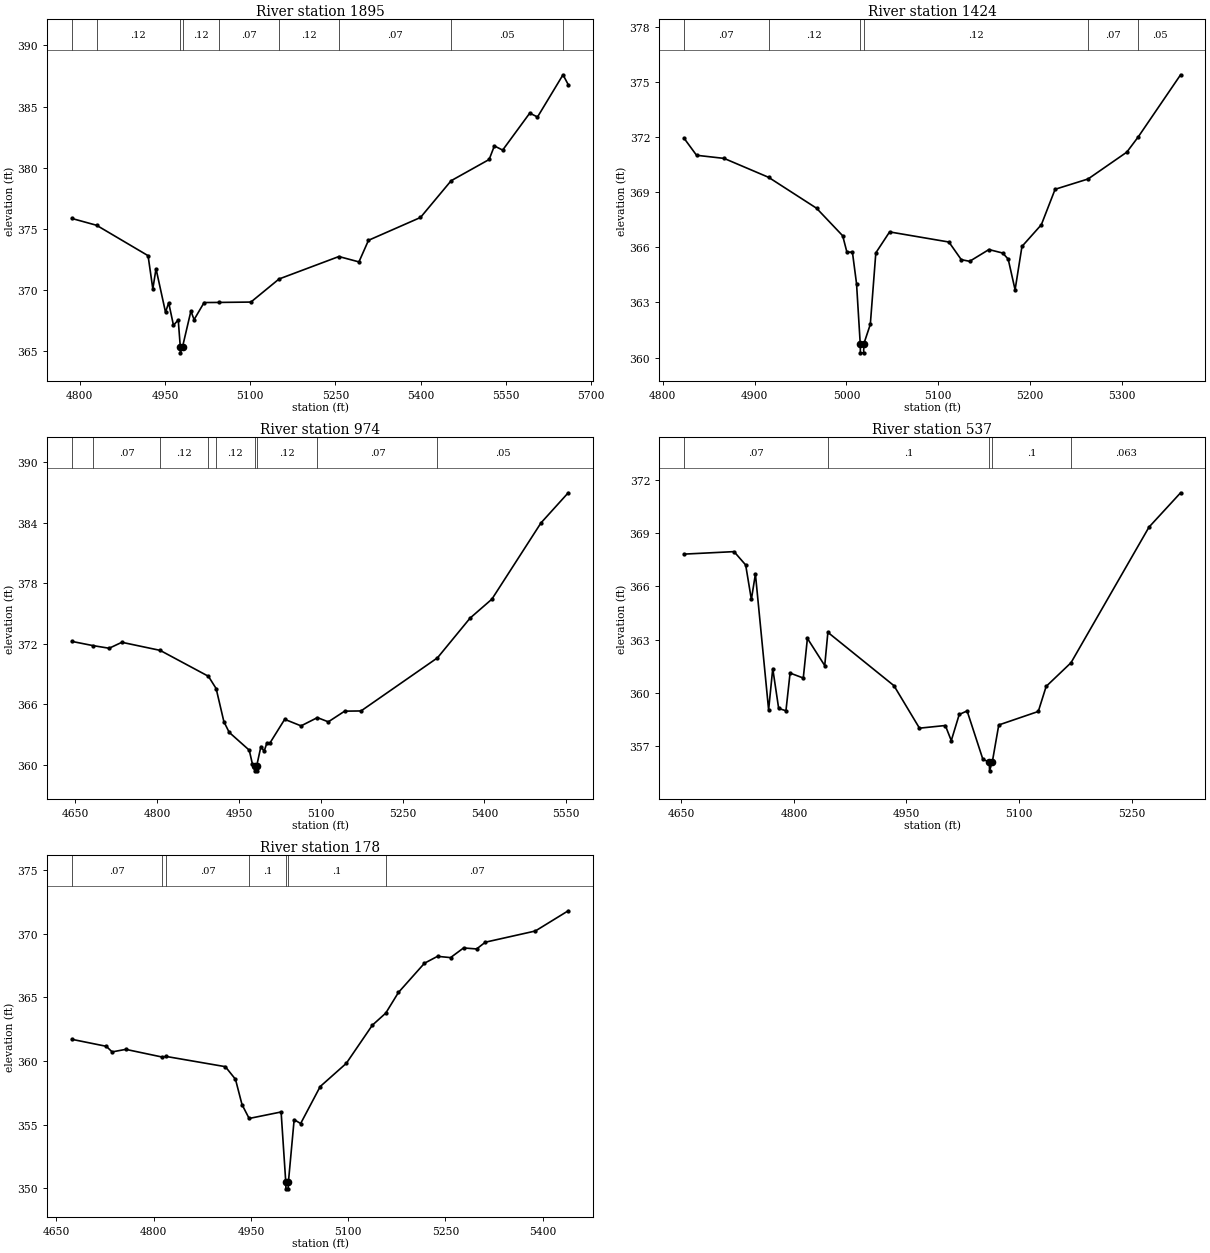
Type RM Length L Ch R = 1,1895,471,471,471
BEGIN DESCRIPTION:
Stream0663 4.0
END DESCRIPTION:
XS GIS Cut Line= 3
      2395674.99     13604774.99      2395875.00     13604875.00
      2396474.98     13605124.99
#Sta/Elev= 30
  4786.2  375.83  4829.8  375.27  4920.4  372.78  4928.8  370.06  4934.4  371.71
  4951.1  368.15  4956.7  368.92  4965.1  367.08  4973.5  367.51  4977.1  365.32
  4977.3  364.82  4981.1  365.32  4995.8  368.24  5001.4  367.54  5019.0  368.94
  5045.6  368.95  5101.4  368.98  5150.9  370.87  5256.2  372.71  5291.5  372.27
  5308.3  374.04  5399.8  375.91  5453.7  378.92  5520.6  380.66  5529.8  381.77
  5544.4  381.43  5592.1  384.46  5605.7  384.14  5650.6  387.60  5659.8  386.79
#Mann=9,-1,0
  4786.2    0.07       0  4829.8    0.12       0  4977.1    0.05       0
  4981.1    0.12       0  5045.6    0.07       0  5150.9    0.12       0
  5256.2    0.07       0  5453.7    0.05       0  5650.6    0.07       0
Bank Sta=4977.1,4981.1
Exp/Cntr=0.3,0.1

Type RM Length L Ch R = 1,1424,450,450,450
BEGIN DESCRIPTION:
Stream0663 3.0
END DESCRIPTION:
XS GIS Cut Line= 3
      2395625.02     13605175.01      2395775.00     13605275.00
      2396074.99     13605474.99
#Sta/Elev= 30
  4823.2  371.93  4836.7  371.01  4866.7  370.84  4915.2  369.81  4967.4  368.13
  4995.9  366.63  5000.5  365.74  5006.5  365.74  5011.0  364.02  5015.0  360.76
  5015.2  360.26  5018.7  360.26  5019.0  360.76  5026.0  361.81  5032.0  365.70
  5047.0  366.84  5111.6  366.29  5125.1  365.33  5134.2  365.24  5155.2  365.88
  5170.2  365.69  5176.2  365.36  5183.7  363.69  5191.2  366.05  5212.3  367.23
  5227.3  369.16  5263.2  369.72  5305.4  371.18  5318.0  372.02  5364.0  375.39
#Mann=6,-1,0
  4823.2    0.07       0  4915.2    0.12       0  5015.0    0.05       0
  5019.0    0.12       0  5263.2    0.07       0  5318.0    0.05       0
Bank Sta=5015,5019
Exp/Cntr=0.3,0.1

Type RM Length L Ch R = 1,974,437,437,437
BEGIN DESCRIPTION:
Stream0663 2.0
END DESCRIPTION:
XS GIS Cut Line= 3
      2395366.36     13605438.88      2395675.00     13605625.00
      2396224.98     13605625.00
#Sta/Elev= 30
  4643.5  372.22  4682.4  371.80  4712.0  371.54  4735.3  372.13  4805.4  371.33
  4894.0  368.76  4908.2  367.54  4922.4  364.26  4932.1  363.20  4968.9  361.43
  4974.8  360.04  4978.6  359.88  4978.9  359.38  4982.4  359.38  4982.6  359.88
  4990.3  361.79  4996.2  361.32  5001.0  362.10  5006.4  362.10  5033.9  364.49
  5063.9  363.84  5093.9  364.66  5113.9  364.24  5143.9  365.30  5173.9  365.32
  5314.1  370.59  5373.9  374.53  5413.9  376.41  5503.9  383.97  5553.9  386.96
#Mann=9,-1,0
  4643.5    0.05       0  4682.4    0.07       0  4805.4    0.12       0
  4894.0    0.07       0  4908.2    0.12       0  4978.6    0.05       0
  4982.6    0.12       0  5093.9    0.07       0  5314.1    0.05       0
Bank Sta=4978.6,4982.6
Exp/Cntr=0.3,0.1

Type RM Length L Ch R = 1,537,359,359,359
BEGIN DESCRIPTION:
Stream0663 1.0
END DESCRIPTION:
XS GIS Cut Line= 3
      2395360.31     13605782.14      2395675.00     13605925.00
      2395974.98     13605825.01
#Sta/Elev= 30
  4653.6  367.82  4720.1  367.96  4735.6  367.21  4743.2  365.27  4748.6  366.70
  4766.2  359.06  4771.7  361.38  4779.6  359.14  4789.3  359.01  4794.8  361.13
  4812.4  360.85  4817.9  363.08  4841.0  361.55  4845.2  363.42  4933.3  360.42
  4967.3  358.03  5001.8  358.18  5009.7  357.33  5020.3  358.80  5030.8  359.00
  5051.9  356.27  5060.4  356.13  5060.7  355.63  5064.4  356.13  5073.0  358.21
  5125.7  358.97  5136.2  360.38  5169.3  361.71  5273.3  369.34  5315.4  371.27
#Mann=5,-1,0
  4653.6    0.07       0  4845.2     0.1       0  5060.4    0.05       0
  5064.4     0.1       0  5169.3   0.063       0
Bank Sta=5060.4,5064.4
Exp/Cntr=0.3,0.1

Type RM Length L Ch R = 1,178,0,0,0
BEGIN DESCRIPTION:
XS7432
END DESCRIPTION:
XS GIS Cut Line= 3
      2395303.08     13606032.04      2395426.56     13606218.77
      2395965.58     13606272.97
#Sta/Elev= 30
  4673.8  361.71  4727.0  361.16  4736.0  360.72  4757.1  360.92  4812.8  360.32
  4819.7  360.36  4910.6  359.56  4926.2  358.57  4936.3  356.58  4947.3  355.49
  4996.6  356.00  5003.8  350.46  5004.0  349.96  5007.5  349.96  5007.8  350.46
  5016.7  355.40  5026.7  355.09  5056.9  358.00  5097.1  359.82  5137.3  362.82
  5158.0  363.77  5177.5  365.39  5217.7  367.69  5237.8  368.23  5257.9  368.13
  5278.0  368.89  5298.1  368.81  5311.5  369.34  5388.6  370.22  5439.4  371.81
#Mann=7,-1,0
  4673.8    0.07       0  4812.8    0.12       0  4819.7    0.07       0
  4947.3     0.1       0  5003.8    0.05       0  5007.8     0.1       0
  5158.0    0.07       0
Bank Sta=5003.8,5007.8
Exp/Cntr=0.3,0.1

Chan Stop Cuts=-1