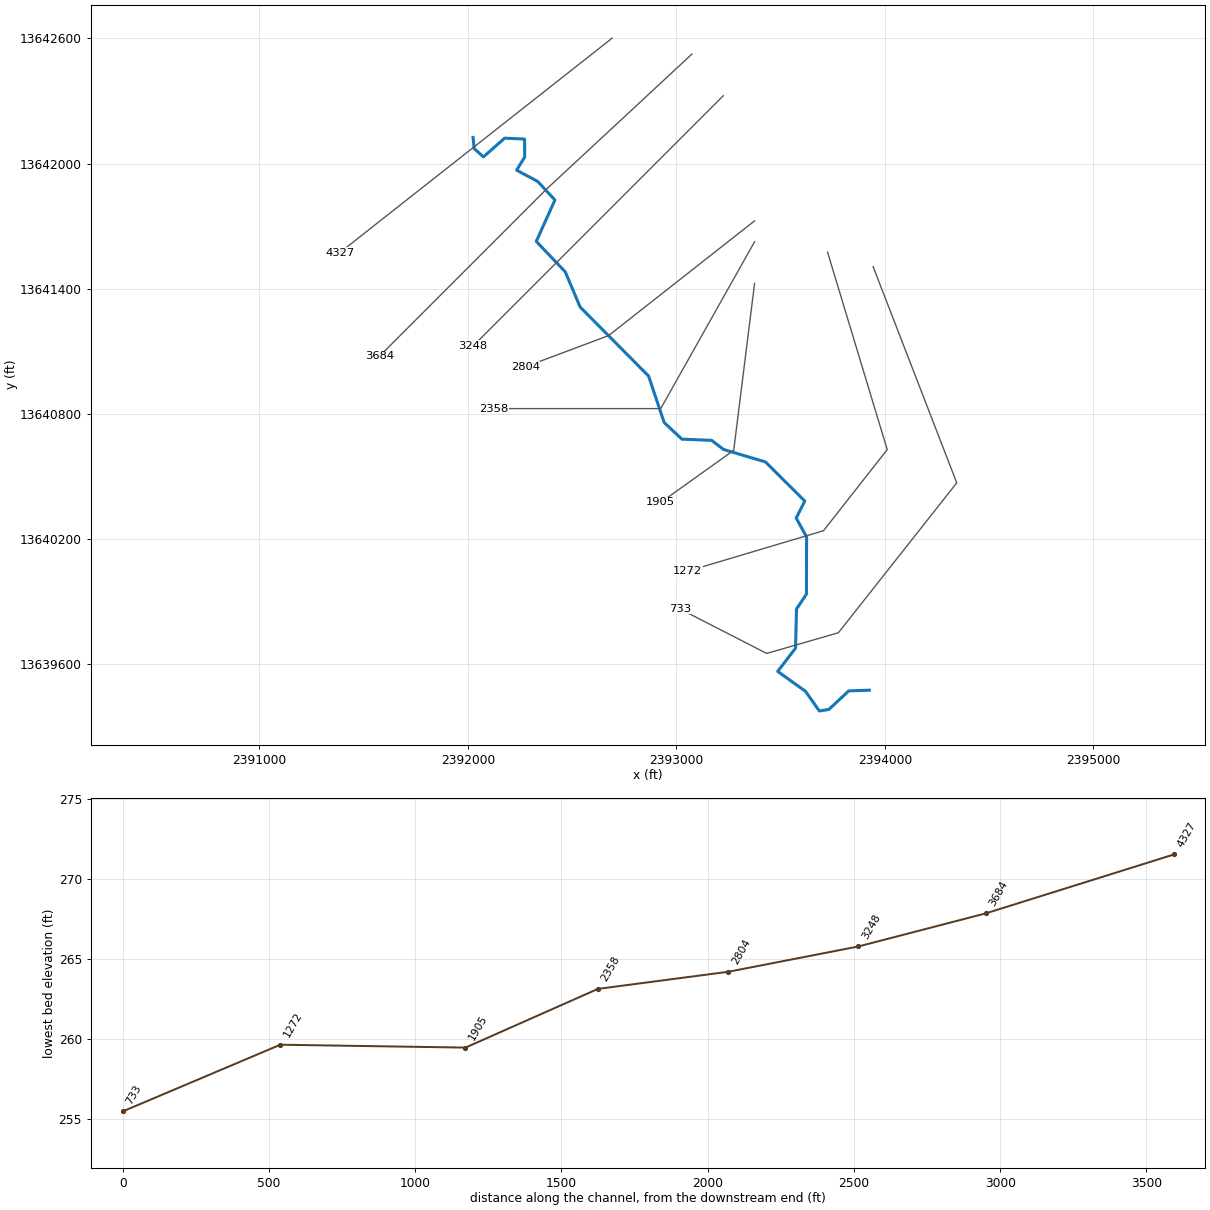
--- Stream0667.prj (project) ---

Proj Title=Stream0667 Base Level Engineering
Current Plan=p01
Default Exp/Contr=0.3,0.1
English Units
Geom File=g01
Flow File=f01
Plan File=p01
BEGIN DESCRIPTION:
Stream0667
END DESCRIPTION:

--- Stream0667.p01 (plan) ---

Plan Title=Multiple Run
Short Identifier=Multiple
Geom File=g01
Flow File=f01
Subcritical Flow
K Sum by GR= 0
Std Step Tol= 0.01
Critical Tol= 0.01
Num of Std Step Trials= 20
Max Error Tol= 0.3
Flow Tol Ratio= 0.001
Split Flow NTrial= 30
Split Flow Tol= 0.02
Split Flow Ratio= 0.02
Log Output Level= 0
Friction Slope Method= 1
Unsteady Friction Slope Method= 2
Unsteady Bridges Friction Slope Method= 1
Parabolic Critical Depth
Global Vel Dist=  1 , 1 , 1
Global Log Level= 0
CheckData=True
Encroach Param= -1, 0, 0, 0
BEGIN DESCRIPTION:
Multiple Run
END DESCRIPTION:

--- Stream0667.f01 (steady flow) ---

Flow Title=Multiple
Number of Profiles=7
Profile Names=10-year,25-year,50-year,1pct_min,100-year,1pct_plu,500-year
River Rch & RM= Stream0667,Reach-1,4327
     755    1227    1656    1081    2158    4306    3631
Boundary for River Rch & Prof#=Stream0667,Reach-1,1
Up Type=0
Dn Type=3
Dn Slope=0.005
Boundary for River Rch & Prof#=Stream0667,Reach-1,2
Up Type=0
Dn Type=3
Dn Slope=0.005
Boundary for River Rch & Prof#=Stream0667,Reach-1,3
Up Type=0
Dn Type=3
Dn Slope=0.005
Boundary for River Rch & Prof#=Stream0667,Reach-1,4
Up Type=0
Dn Type=3
Dn Slope=0.005
Boundary for River Rch & Prof#=Stream0667,Reach-1,5
Up Type=0
Dn Type=3
Dn Slope=0.005
Boundary for River Rch & Prof#=Stream0667,Reach-1,6
Up Type=0
Dn Type=3
Dn Slope=0.005
Boundary for River Rch & Prof#=Stream0667,Reach-1,7
Up Type=0
Dn Type=3
Dn Slope=0.005

--- Stream0667.g01 (geometry) ---

Geom Title=Existing Conditions

River Reach=Stream0667,Reach-1
Reach XY= 30
      2392025.00     13642125.00      2392030.31     13642071.63
      2392074.83     13642031.83      2392176.58     13642121.55
      2392272.16     13642117.12      2392272.67     13642030.98
      2392234.01     13641967.98      2392334.69     13641914.22
      2392417.72     13641825.10      2392328.12     13641626.63
      2392466.86     13641481.06      2392538.62     13641311.79
      2392866.86     13640981.06      2392941.44     13640758.21
      2393026.46     13640678.54      2393169.06     13640672.73
      2393226.60     13640628.86      2393427.30     13640569.17
      2393615.85     13640381.73      2393574.69     13640300.04
      2393624.46     13640209.79      2393623.78     13639935.50
      2393576.22     13639864.49      2393571.44     13639676.46
      2393485.95     13639564.98      2393619.36     13639469.34
      2393685.50     13639375.50      2393731.02     13639382.47
      2393826.41     13639471.60      2393925.00     13639475.00

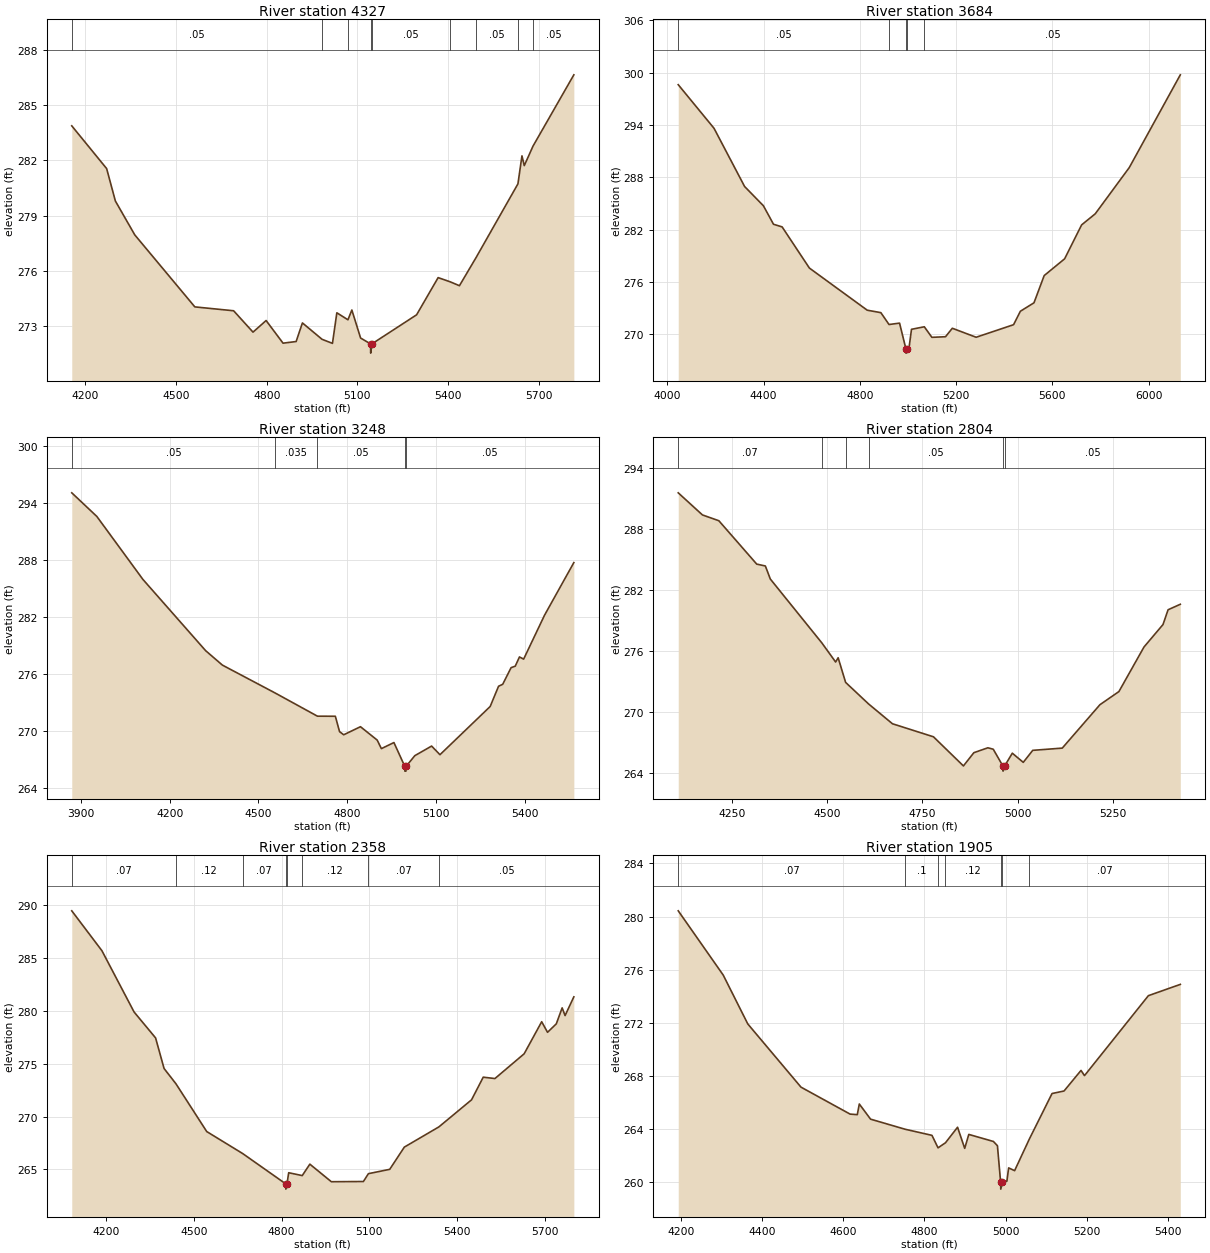
Type RM Length L Ch R = 1,4327,643,643,643
BEGIN DESCRIPTION:
XS7434
END DESCRIPTION:
XS GIS Cut Line= 2
      2392691.64     13642600.68      2391386.14     13641572.94
#Sta/Elev= 30
  4154.8  283.88  4270.2  281.56  4299.1  279.80  4363.3  277.96  4562.1  274.05
  4690.4  273.84  4754.6  272.68  4797.9  273.31  4854.0  272.08  4897.3  272.17
  4918.1  273.18  4983.1  272.29  5017.5  272.07  5032.0  273.73  5068.7  273.35
  5081.7  273.88  5110.6  272.36  5143.8  272.04  5144.0  271.54  5147.9  272.04
  5295.9  273.62  5367.2  275.64  5407.4  275.41  5437.7  275.20  5492.8  276.73
  5631.3  280.73  5644.6  282.25  5652.3  281.72  5681.2  282.78  5816.3  286.65
#Mann=9,-1,0
  4154.8    0.05       0  4983.1   0.035       0  5068.7    0.05       0
  5143.8   0.035       0  5147.9    0.05       0  5407.4   0.035       0
  5492.8    0.05       0  5631.3   0.035       0  5681.2    0.05       0
Bank Sta=5143.8,5147.9
Exp/Cntr=0.3,0.1

Type RM Length L Ch R = 1,3684,436,436,436
BEGIN DESCRIPTION:
Stream0667 6.0
END DESCRIPTION:
XS GIS Cut Line= 3
      2393075.00     13642525.00      2392375.00     13641875.00
      2391575.02     13641075.02
#Sta/Elev= 30
  4045.3  298.63  4194.1  293.63  4321.1  286.96  4399.3  284.75  4441.3  282.63
  4477.0  282.33  4590.4  277.61  4830.8  272.78  4887.4  272.50  4921.3  271.14
  4965.1  271.30  4991.4  268.36  4991.7  267.86  4995.6  268.36  5004.1  268.38
  5014.7  270.59  5068.0  270.88  5099.5  269.67  5156.1  269.74  5184.4  270.71
  5283.4  269.68  5439.0  271.12  5467.2  272.66  5523.8  273.63  5566.2  276.75
  5651.1  278.67  5721.8  282.56  5778.4  283.83  5919.8  289.13  6131.9  299.76
#Mann=5,-1,0
  4045.3    0.05       0  4921.3   0.035       0  4991.4   0.035       0
  4995.6   0.035       0  5068.0    0.05       0
Bank Sta=4991.4,4995.6
Exp/Cntr=0.3,0.1

Type RM Length L Ch R = 1,3248,444,444,444
BEGIN DESCRIPTION:
Stream0667 5.0
END DESCRIPTION:
XS GIS Cut Line= 3
      2393224.97     13642324.97      2392425.00     13641525.00
      2392025.01     13641125.01
#Sta/Elev= 30
  3868.9  295.11  3953.7  292.62  4109.3  285.99  4321.4  278.48  4378.0  276.96
  4555.8  274.03  4699.2  271.58  4759.8  271.57  4774.0  269.95  4788.1  269.62
  4844.7  270.47  4901.2  269.06  4915.4  268.16  4957.8  268.80  4994.5  266.29
  4994.8  265.79  4998.5  265.79  4998.8  266.29  5028.5  267.42  5085.1  268.43
  5113.4  267.52  5283.1  272.60  5311.4  274.73  5325.5  274.94  5353.8  276.69
  5367.9  276.85  5382.1  277.82  5396.2  277.59  5466.9  282.22  5565.9  287.76
#Mann=5,-1,0
  3868.9    0.05       0  4555.8   0.035       0  4699.2    0.05       0
  4994.5    0.05       0  4998.8    0.05       0
Bank Sta=4994.5,4998.8
Exp/Cntr=0.3,0.1

Type RM Length L Ch R = 1,2804,446,446,446
BEGIN DESCRIPTION:
Stream0667 4.0
END DESCRIPTION:
XS GIS Cut Line= 3
      2393374.97     13641724.97      2392675.00     13641175.00
      2392274.98     13641024.99
#Sta/Elev= 30
  4109.8  291.53  4173.3  289.36  4216.4  288.79  4315.8  284.53  4338.4  284.35
  4351.4  283.07  4486.8  276.79  4522.8  274.92  4529.4  275.34  4549.0  272.92
  4609.1  270.81  4671.9  268.86  4779.5  267.58  4858.1  264.72  4885.5  266.02
  4922.2  266.50  4936.4  266.36  4961.7  264.71  4962.0  264.21  4966.1  264.71
  4986.4  265.97  5015.1  265.07  5040.0  266.25  5117.5  266.47  5216.3  270.73
  5266.1  272.02  5332.0  276.40  5381.8  278.60  5395.1  280.05  5427.2  280.59
#Mann=6,-1,0
  4109.8    0.07       0  4486.8   0.035       0  4549.0    0.07       0
  4609.1    0.05       0  4961.7    0.05       0  4966.1    0.05       0
Bank Sta=4961.7,4966.1
Exp/Cntr=0.3,0.1

Type RM Length L Ch R = 1,2358,453,453,453
BEGIN DESCRIPTION:
Stream0667 3.0
END DESCRIPTION:
XS GIS Cut Line= 3
      2393374.99     13641624.98      2392925.00     13640825.00
      2392124.95     13640825.00
#Sta/Elev= 30
  4082.1  289.44  4185.3  285.67  4295.3  279.88  4368.9  277.43  4397.9  274.54
  4438.7  273.09  4543.9  268.58  4667.0  266.50  4814.1  263.64  4814.5  263.14
  4818.6  263.64  4824.3  264.69  4870.7  264.42  4896.7  265.50  4970.3  263.84
  5080.0  263.86  5097.1  264.60  5170.0  265.01  5220.0  267.11  5338.2  269.02
  5450.0  271.58  5490.0  273.72  5530.0  273.59  5630.0  275.93  5690.0  278.96
  5710.0  277.96  5740.0  278.76  5760.0  280.27  5770.0  279.54  5800.0  281.31
#Mann=8,-1,0
  4082.1    0.07       0  4438.7    0.12       0  4667.0    0.07       0
  4814.1    0.05       0  4818.6    0.07       0  4870.7    0.12       0
  5097.1    0.07       0  5338.2    0.05       0
Bank Sta=4814.1,4818.6
Exp/Cntr=0.3,0.1

Type RM Length L Ch R = 1,1905,633,633,633
BEGIN DESCRIPTION:
Stream0667 2.0
END DESCRIPTION:
XS GIS Cut Line= 3
      2393375.00     13641424.98      2393275.00     13640625.00
      2392925.02     13640375.01
#Sta/Elev= 30
  4193.8  280.43  4304.6  275.59  4365.1  271.91  4496.1  267.15  4617.0  265.12
  4634.7  265.08  4639.7  265.88  4667.4  264.74  4752.5  263.98  4818.6  263.52
  4833.5  262.58  4851.8  262.96  4881.6  264.13  4899.2  262.54  4909.3  263.59
  4969.8  263.06  4979.8  262.74  4987.7  259.97  4988.0  259.47  4992.2  259.97
  5003.1  260.07  5007.4  261.07  5022.1  260.86  5058.5  263.25  5114.3  266.67
  5143.8  266.86  5185.6  268.41  5194.2  268.02  5351.5  274.04  5430.1  274.89
#Mann=7,-1,0
  4193.8    0.07       0  4752.5     0.1       0  4833.5    0.07       0
  4851.8    0.12       0  4987.7    0.05       0  4992.2    0.12       0
  5058.5    0.07       0
Bank Sta=4987.7,4992.2
Exp/Cntr=0.3,0.1

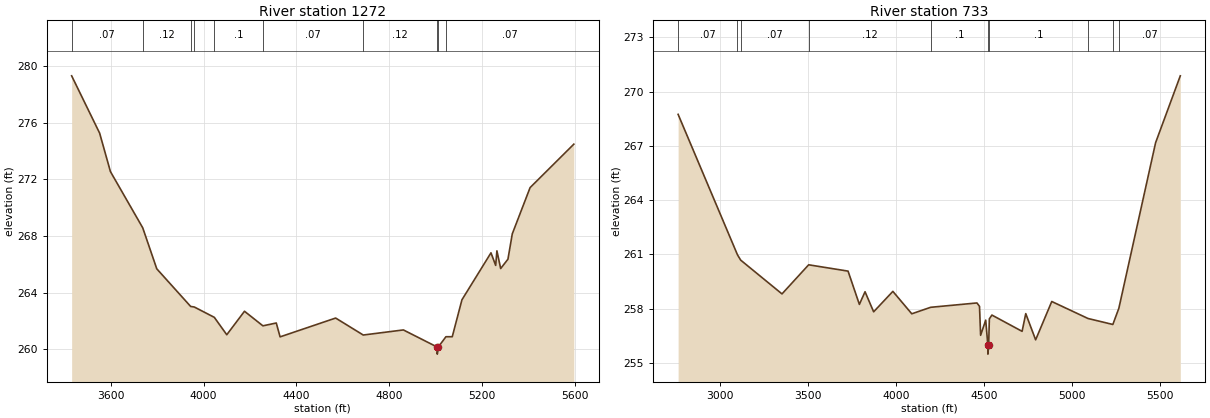
Type RM Length L Ch R = 1,1272,539,539,539
BEGIN DESCRIPTION:
Stream0667 1.0
END DESCRIPTION:
XS GIS Cut Line= 4
      2393725.00     13641575.00      2394011.11     13640628.47
      2393705.56     13640239.58      2393052.79     13640045.14
#Sta/Elev= 30
  3431.1  279.32  3551.7  275.27  3598.3  272.55  3737.4  268.58  3798.0  265.68
  3944.0  263.02  3959.8  262.98  4046.0  262.25  4099.7  261.02  4176.1  262.68
  4255.4  261.65  4313.1  261.85  4329.5  260.87  4569.0  262.20  4687.9  261.00
  4860.9  261.36  5006.7  260.15  5007.0  259.65  5011.2  260.15  5044.3  260.88
  5071.6  260.88  5113.3  263.49  5238.5  266.81  5258.8  265.92  5264.0  266.95
  5280.3  265.70  5311.6  266.36  5330.3  268.15  5407.1  271.42  5595.6  274.49
#Mann=10,-1,0
  3431.1    0.07       0  3737.4    0.12       0  3944.0    0.07       0
  3959.8    0.12       0  4046.0     0.1       0  4255.4    0.07       0
  4687.9    0.12       0  5006.7    0.05       0  5011.2    0.12       0
  5044.3    0.07       0
Bank Sta=5006.7,5011.2
Exp/Cntr=0.3,0.1

Type RM Length L Ch R = 1,733,0,0,0
BEGIN DESCRIPTION:
E21247
END DESCRIPTION:
XS GIS Cut Line= 5
      2393943.51     13641505.40      2394344.54     13640468.97
      2393776.83     13639750.22      2393433.08     13639651.26
      2393016.46     13639864.78
#Sta/Elev= 30
  2762.5  268.74  3099.4  260.98  3117.8  260.68  3352.7  258.81  3504.2  260.42
  3728.0  260.07  3792.3  258.23  3824.5  258.93  3873.3  257.82  3982.6  258.95
  4090.0  257.71  4197.5  258.07  4460.3  258.31  4474.8  258.12  4481.1  256.52
  4510.0  257.36  4522.2  255.98  4522.5  255.48  4526.7  255.98  4530.8  257.43
  4545.3  257.64  4716.8  256.74  4737.6  257.72  4793.7  256.27  4885.3  258.39
  5091.4  257.45  5232.4  257.12  5266.6  258.02  5475.2  267.17  5615.6  270.87
#Mann=10,-1,0
  2762.5    0.07       0  3099.4    0.12       0  3117.8    0.07       0
  3504.2    0.12       0  4197.5     0.1       0  4522.2    0.05       0
  4526.7     0.1       0  5091.4    0.07       0  5232.4    0.12       0
  5266.6    0.07       0
Bank Sta=4522.2,4526.7
Exp/Cntr=0.3,0.1

Chan Stop Cuts=-1