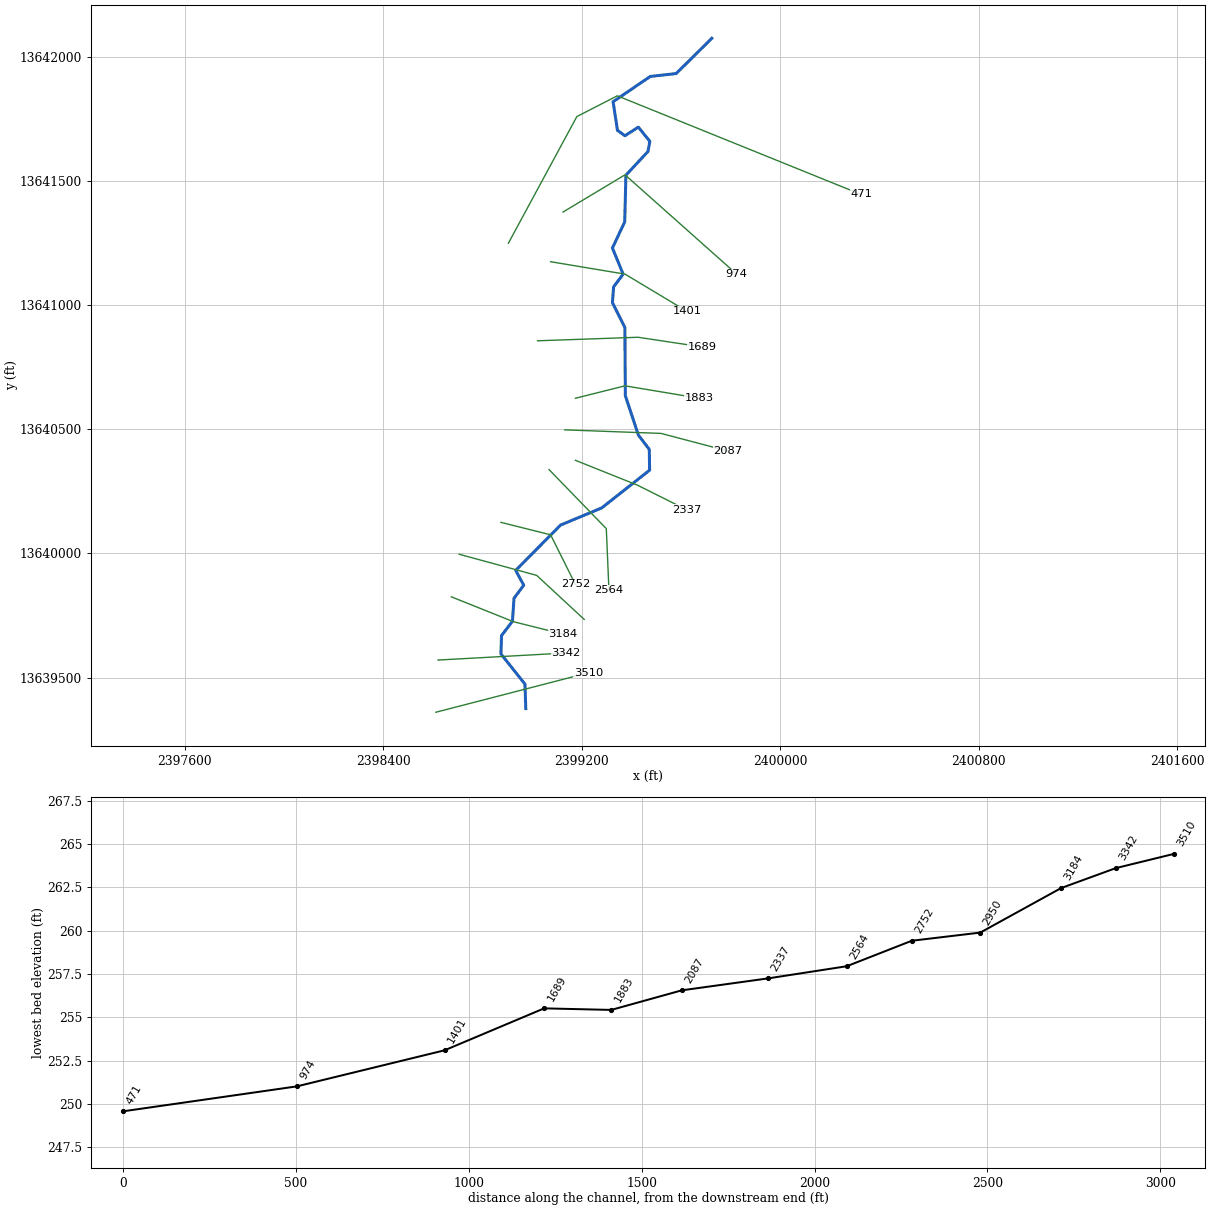
--- Stream0668.prj (project) ---

Proj Title=Stream0668 Base Level Engineering
Current Plan=p01
Default Exp/Contr=0.3,0.1
English Units
Geom File=g01
Flow File=f01
Plan File=p01
BEGIN DESCRIPTION:
Stream0668
END DESCRIPTION:

--- Stream0668.p01 (plan) ---

Plan Title=Multiple Run
Short Identifier=Multiple
Geom File=g01
Flow File=f01
Subcritical Flow
K Sum by GR= 0
Std Step Tol= 0.01
Critical Tol= 0.01
Num of Std Step Trials= 20
Max Error Tol= 0.3
Flow Tol Ratio= 0.001
Split Flow NTrial= 30
Split Flow Tol= 0.02
Split Flow Ratio= 0.02
Log Output Level= 0
Friction Slope Method= 1
Unsteady Friction Slope Method= 2
Unsteady Bridges Friction Slope Method= 1
Parabolic Critical Depth
Global Vel Dist=  1 , 1 , 1
Global Log Level= 0
CheckData=True
Encroach Param= -1, 0, 0, 0
BEGIN DESCRIPTION:
Multiple Run
END DESCRIPTION:

--- Stream0668.f01 (steady flow) ---

Flow Title=Multiple
Number of Profiles=7
Profile Names=10-year,25-year,50-year,1pct_min,100-year,1pct_plu,500-year
River Rch & RM= Stream0668,Reach-1,3510
     251     382     493     310     618    1233     957
Boundary for River Rch & Prof#=Stream0668,Reach-1,1
Up Type=0
Dn Type=3
Dn Slope=0.005
Boundary for River Rch & Prof#=Stream0668,Reach-1,2
Up Type=0
Dn Type=3
Dn Slope=0.005
Boundary for River Rch & Prof#=Stream0668,Reach-1,3
Up Type=0
Dn Type=3
Dn Slope=0.005
Boundary for River Rch & Prof#=Stream0668,Reach-1,4
Up Type=0
Dn Type=3
Dn Slope=0.005
Boundary for River Rch & Prof#=Stream0668,Reach-1,5
Up Type=0
Dn Type=3
Dn Slope=0.005
Boundary for River Rch & Prof#=Stream0668,Reach-1,6
Up Type=0
Dn Type=3
Dn Slope=0.005
Boundary for River Rch & Prof#=Stream0668,Reach-1,7
Up Type=0
Dn Type=3
Dn Slope=0.005

--- Stream0668.g01 (geometry) ---

Geom Title=Existing Conditions

River Reach=Stream0668,Reach-1
Reach XY= 30
      2398975.00     13639375.00      2398971.61     13639473.59
      2398874.79     13639595.05      2398877.16     13639669.02
      2398921.14     13639726.60      2398927.54     13639819.11
      2398966.71     13639871.78      2398934.30     13639931.67
      2399115.32     13640114.24      2399281.05     13640183.16
      2399474.13     13640335.33      2399472.84     13640419.02
      2399428.86     13640476.60      2399376.22     13640635.50
      2399374.48     13640909.78      2399324.31     13641009.94
      2399328.94     13641073.50      2399367.43     13641125.00
      2399324.22     13641230.02      2399373.78     13641335.50
      2399378.55     13641523.53      2399467.52     13641619.00
      2399475.11     13641659.91      2399428.65     13641717.10
      2399374.76     13641682.47      2399344.58     13641703.95
      2399326.88     13641819.28      2399476.58     13641921.17
      2399581.17     13641932.86      2399725.00     13642075.00

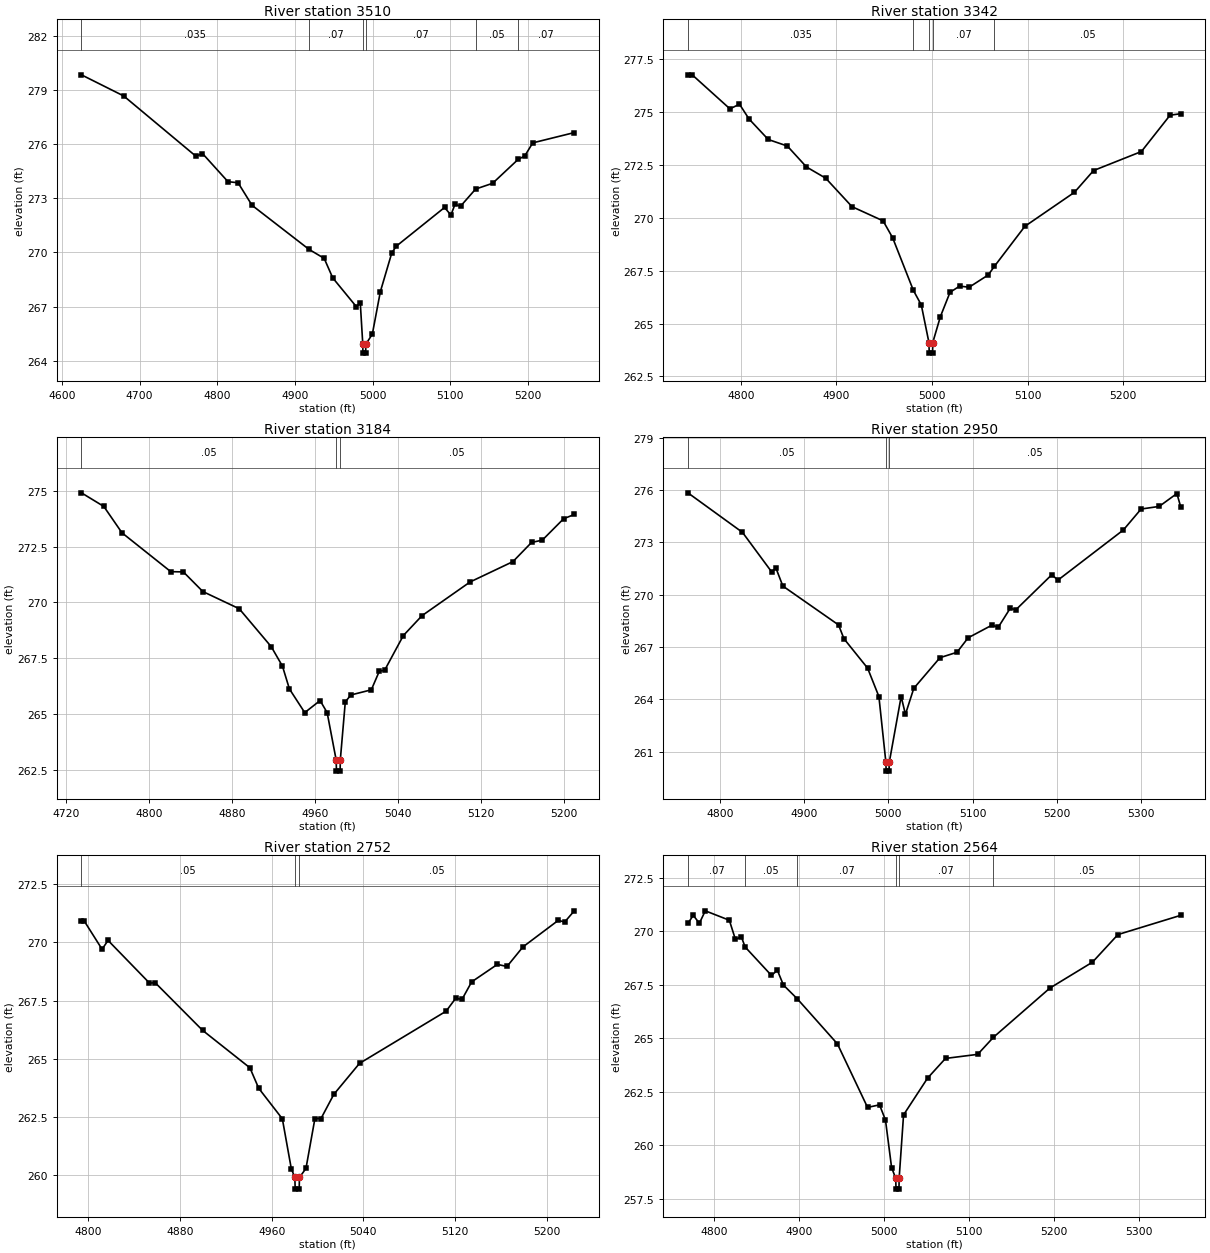
Type RM Length L Ch R = 1,3510,168,168,168
BEGIN DESCRIPTION:
XS7435
END DESCRIPTION:
XS GIS Cut Line= 2
      2398612.32     13639360.13      2399226.82     13639518.98
#Sta/Elev= 30
  4625.0  279.84  4679.4  278.67  4772.4  275.33  4780.9  275.48  4813.7  273.92
  4826.7  273.86  4844.7  272.61  4918.0  270.17  4937.6  269.67  4948.6  268.59
  4978.9  267.00  4984.1  267.20  4987.3  264.92  4987.5  264.42  4991.0  264.42
  4991.3  264.92  4999.6  265.47  5009.9  267.82  5024.7  269.98  5030.6  270.35
  5092.6  272.49  5100.8  272.07  5106.0  272.66  5113.2  272.56  5132.6  273.51
  5154.5  273.83  5187.5  275.16  5195.8  275.34  5206.2  276.07  5259.7  276.64
#Mann=6,-1,0
  4625.0   0.035       0  4918.0    0.07       0  4987.3    0.05       0
  4991.3    0.07       0  5132.6    0.05       0  5187.5    0.07       0
Bank Sta=4987.3,4991.3
Exp/Cntr=0.3,0.1

Type RM Length L Ch R = 1,3342,158,158,158
BEGIN DESCRIPTION:
E21252
END DESCRIPTION:
XS GIS Cut Line= 2
      2398621.06     13639570.40      2399136.17     13639598.82
#Sta/Elev= 30
  4744.5  276.77  4749.0  276.77  4788.5  275.16  4798.5  275.38  4808.5  274.68
  4828.6  273.71  4848.6  273.40  4868.6  272.41  4888.7  271.88  4916.3  270.53
  4948.8  269.86  4958.8  269.06  4980.5  266.57  4988.8  265.88  4996.8  264.10
  4997.1  263.60  5000.6  263.60  5000.8  264.10  5008.8  265.33  5018.9  266.48
  5028.9  266.77  5038.9  266.72  5058.9  267.30  5065.2  267.70  5097.2  269.60
  5149.1  271.21  5169.1  272.24  5219.2  273.14  5249.2  274.86  5260.4  274.93
#Mann=5,-1,0
  4744.5   0.035       0  4980.5    0.07       0  4996.8    0.05       0
  5000.8    0.07       0  5065.2    0.05       0
Bank Sta=4996.8,5000.8
Exp/Cntr=0.3,0.1

Type RM Length L Ch R = 1,3184,234,234,234
BEGIN DESCRIPTION:
Stream0668 7.0
END DESCRIPTION:
XS GIS Cut Line= 3
      2398674.98     13639825.01      2398925.00     13639725.00
      2399124.97     13639675.01
#Sta/Elev= 30
  4734.9  274.91  4756.5  274.30  4774.0  273.12  4821.1  271.38  4833.2  271.37
  4852.0  270.49  4887.1  269.72  4918.0  268.02  4928.8  267.15  4935.5  266.13
  4950.3  265.07  4965.1  265.61  4971.9  265.07  4980.6  262.95  4980.9  262.45
  4984.4  262.45  4984.6  262.95  4989.4  265.55  4994.8  265.86  5014.5  266.09
  5022.2  266.92  5027.4  266.97  5045.4  268.52  5063.4  269.41  5109.8  270.92
  5151.1  271.83  5169.1  272.69  5179.4  272.79  5200.0  273.75  5210.3  273.94
#Mann=3,-1,0
  4734.9    0.05       0  4980.6    0.05       0  4984.6    0.05       0
Bank Sta=4980.6,4984.6
Exp/Cntr=0.3,0.1

Type RM Length L Ch R = 1,2950,198,198,198
BEGIN DESCRIPTION:
E21251
END DESCRIPTION:
XS GIS Cut Line= 3
      2398706.31     13639996.71      2399018.93     13639911.45
      2399210.41     13639734.14
#Sta/Elev= 30
  4762.2  275.85  4827.0  273.58  4861.5  271.32  4866.7  271.53  4874.9  270.50
  4941.0  268.27  4947.4  267.48  4975.5  265.79  4988.9  264.16  4997.2  260.38
  4997.5  259.88  5001.0  259.88  5001.2  260.38  5015.3  264.16  5020.4  263.14
  5030.3  264.63  5061.4  266.39  5081.6  266.70  5094.8  267.53  5123.2  268.26
  5130.5  268.13  5144.7  269.22  5151.5  269.14  5194.1  271.15  5201.4  270.84
  5279.1  273.72  5300.1  274.92  5321.6  275.07  5342.6  275.81  5347.2  275.03
#Mann=3,-1,0
  4762.2    0.05       0  4997.2    0.05       0  5001.2    0.05       0
Bank Sta=4997.2,5001.2
Exp/Cntr=0.3,0.1

Type RM Length L Ch R = 1,2752,188,188,188
BEGIN DESCRIPTION:
Stream0668 6.0
END DESCRIPTION:
XS GIS Cut Line= 3
      2398875.01     13640125.00      2399075.00     13640075.00
      2399175.02     13639874.96
#Sta/Elev= 30
  4794.1  270.91  4796.7  270.91  4812.1  269.71  4817.3  270.09  4853.4  268.26
  4858.5  268.27  4899.7  266.23  4941.0  264.62  4948.7  263.74  4969.3  262.43
  4977.1  260.29  4980.2  259.91  4980.5  259.41  4984.0  259.41  4984.2  259.91
  4989.9  260.30  4997.7  262.44  5003.0  262.44  5014.2  263.48  5036.6  264.81
  5112.1  267.05  5120.4  267.60  5126.0  267.56  5134.4  268.31  5156.8  269.06
  5165.2  268.97  5179.1  269.81  5209.9  270.95  5215.5  270.88  5223.9  271.36
#Mann=3,-1,0
  4794.1    0.05       0  4980.2    0.05       0  4984.2    0.05       0
Bank Sta=4980.2,4984.2
Exp/Cntr=0.3,0.1

Type RM Length L Ch R = 1,2564,227,227,227
BEGIN DESCRIPTION:
E21250
END DESCRIPTION:
XS GIS Cut Line= 3
      2399068.69     13640337.74      2399299.58     13640099.74
      2399310.24     13639851.07
#Sta/Elev= 30
  4768.8  270.36  4775.1  270.74  4782.3  270.37  4789.3  270.95  4817.6  270.51
  4824.8  269.61  4831.7  269.74  4836.2  269.26  4867.2  267.93  4874.2  268.17
  4881.3  267.48  4897.8  266.83  4944.9  264.73  4980.4  261.76  4994.5  261.88
  5001.5  261.17  5008.7  258.95  5013.6  258.44  5013.9  257.94  5017.4  257.94
  5017.6  258.44  5022.8  261.41  5051.1  263.13  5072.2  264.05  5110.1  264.24
  5128.7  265.04  5195.2  267.34  5245.3  268.55  5275.3  269.84  5349.3  270.74
#Mann=6,-1,0
  4768.8    0.07       0  4836.2    0.05       0  4897.8    0.07       0
  5013.6    0.05       0  5017.6    0.07       0  5128.7    0.05       0
Bank Sta=5013.6,5017.6
Exp/Cntr=0.3,0.1

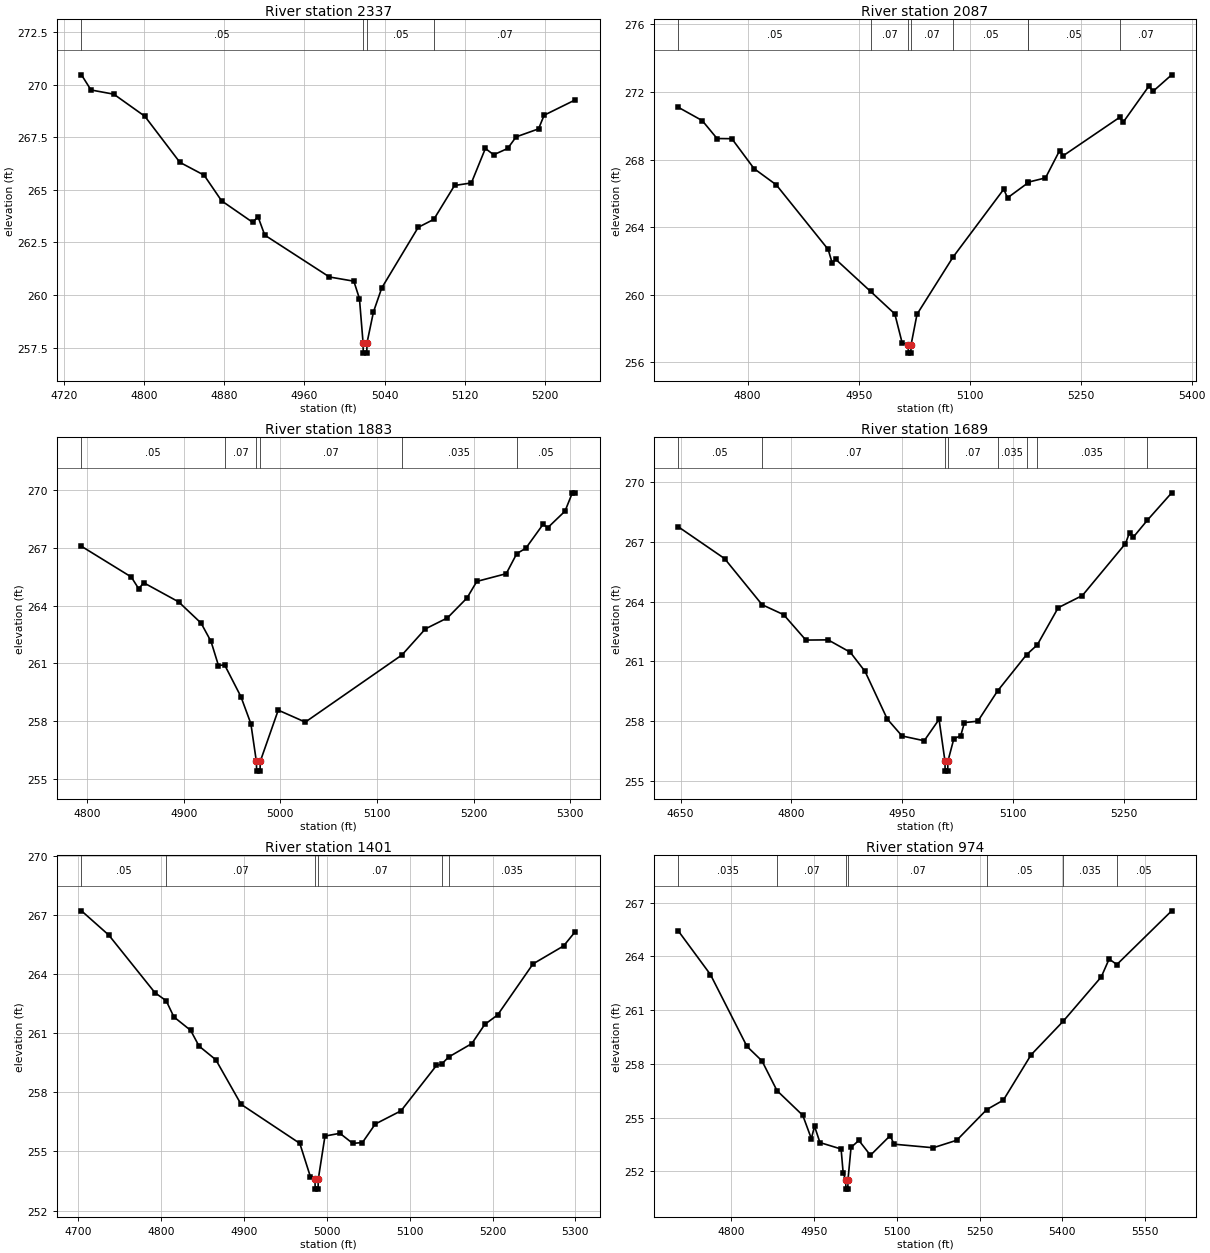
Type RM Length L Ch R = 1,2337,250,250,250
BEGIN DESCRIPTION:
Stream0668 5.0
END DESCRIPTION:
XS GIS Cut Line= 3
      2399174.97     13640375.01      2399425.00     13640275.00
      2399625.00     13640175.00
#Sta/Elev= 30
  4737.2  270.47  4746.7  269.75  4769.5  269.55  4800.5  268.50  4835.5  266.31
  4859.7  265.70  4877.2  264.48  4908.2  263.46  4913.6  263.72  4920.3  262.85
  4984.9  260.86  5009.3  260.66  5014.9  259.83  5018.5  257.74  5018.7  257.24
  5022.2  257.24  5022.5  257.74  5028.9  259.20  5037.2  260.34  5073.6  263.22
  5089.2  263.60  5109.9  265.21  5126.7  265.33  5140.7  266.97  5149.0  266.67
  5163.0  266.97  5171.4  267.52  5193.8  267.90  5199.4  268.55  5230.1  269.27
#Mann=4,-1,0
  4737.2    0.05       0  5018.5    0.05       0  5022.5    0.05       0
  5089.2    0.07       0
Bank Sta=5018.5,5022.5
Exp/Cntr=0.3,0.1

Type RM Length L Ch R = 1,2087,204,204,204
BEGIN DESCRIPTION:
E21249
END DESCRIPTION:
XS GIS Cut Line= 3
      2399132.65     13640497.63      2399519.85     13640483.42
      2399789.89     13640412.36
#Sta/Elev= 30
  4706.3  271.10  4738.7  270.31  4758.7  269.25  4778.7  269.24  4808.7  267.47
  4838.7  266.51  4908.8  262.69  4914.1  261.91  4919.1  262.10  4966.2  260.20
  4998.9  258.87  5008.9  257.14  5016.9  257.05  5017.1  256.55  5020.6  256.55
  5020.9  257.05  5028.9  258.85  5077.5  262.23  5146.1  266.25  5151.2  265.74
  5178.6  266.62  5179.4  266.67  5202.5  266.92  5221.5  268.53  5226.7  268.24
  5302.9  270.51  5307.4  270.21  5342.5  272.37  5347.7  272.04  5373.0  273.02
#Mann=8,-1,0
  4706.3    0.05       0  4966.2    0.07       0  5016.9    0.05       0
  5020.9    0.07       0  5077.5    0.05       0  5178.6    0.07       0
  5179.4    0.05       0  5302.9    0.07       0
Bank Sta=5016.9,5020.9
Exp/Cntr=0.3,0.1

Type RM Length L Ch R = 1,1883,194,194,194
BEGIN DESCRIPTION:
Stream0668 4.0
END DESCRIPTION:
XS GIS Cut Line= 3
      2399175.04     13640625.01      2399375.00     13640675.00
      2399675.04     13640624.99
#Sta/Elev= 30
  4794.3  267.07  4845.8  265.48  4853.5  264.87  4858.7  265.18  4894.8  264.19
  4918.0  263.09  4928.3  262.14  4936.0  260.89  4942.3  260.93  4959.2  259.28
  4969.5  257.88  4975.2  255.92  4975.5  255.42  4979.0  255.42  4979.2  255.92
  4997.8  258.58  5025.8  257.96  5125.8  261.44  5150.0  262.79  5172.8  263.36
  5193.0  264.39  5203.2  265.25  5233.6  265.65  5244.5  266.69  5253.9  266.97
  5271.6  268.20  5276.7  268.04  5294.4  268.89  5302.0  269.84  5304.6  269.84
#Mann=6,-1,0
  4794.3    0.05       0  4942.3    0.07       0  4975.2    0.05       0
  4979.2    0.07       0  5125.8   0.035       0  5244.5    0.05       0
Bank Sta=4975.2,4979.2
Exp/Cntr=0.3,0.1

Type RM Length L Ch R = 1,1689,288,288,288
BEGIN DESCRIPTION:
E21248
END DESCRIPTION:
XS GIS Cut Line= 3
      2399022.46     13640856.45      2399427.48     13640870.66
      2399686.78     13640831.58
#Sta/Elev= 30
  4646.9  267.74  4709.5  266.15  4760.3  263.84  4789.5  263.34  4819.5  262.07
  4849.6  262.08  4879.6  261.46  4899.6  260.50  4929.6  258.12  4949.6  257.27
  4979.6  257.03  4999.7  258.10  5007.7  256.01  5007.9  255.51  5011.4  255.51
  5011.7  256.01  5019.7  257.13  5029.0  257.28  5034.0  257.94  5052.2  258.01
  5078.8  259.52  5118.1  261.34  5132.6  261.83  5160.9  263.69  5193.6  264.30
  5251.9  266.90  5257.4  267.45  5262.5  267.22  5281.5  268.07  5314.4  269.44
#Mann=8,-1,0
  4646.9    0.05       0  4760.3    0.07       0  5007.7    0.05       0
  5011.7    0.07       0  5078.8   0.035       0  5118.1    0.07       0
  5132.6   0.035       0  5281.5    0.05       0
Bank Sta=5007.7,5011.7
Exp/Cntr=0.3,0.1

Type RM Length L Ch R = 1,1401,427,427,427
BEGIN DESCRIPTION:
Stream0668 3.0
END DESCRIPTION:
XS GIS Cut Line= 3
      2399074.96     13641175.01      2399375.00     13641125.00
      2399624.98     13640975.01
#Sta/Elev= 30
  4703.7  267.20  4736.7  265.97  4792.4  263.05  4806.0  262.64  4815.3  261.82
  4835.5  261.14  4845.7  260.34  4865.9  259.65  4896.4  257.39  4967.3  255.41
  4980.0  253.73  4985.6  253.59  4985.9  253.09  4989.4  253.09  4989.6  253.59
  4997.7  255.78  5015.7  255.92  5031.2  255.41  5042.9  255.45  5058.4  256.39
  5089.5  257.06  5132.3  259.36  5138.5  259.43  5147.1  259.79  5175.0  260.47
  5190.6  261.44  5206.1  261.92  5248.9  264.51  5285.8  265.42  5299.4  266.12
#Mann=6,-1,0
  4703.7    0.05       0  4806.0    0.07       0  4985.6    0.05       0
  4989.6    0.07       0  5138.5    0.05       0  5147.1   0.035       0
Bank Sta=4985.6,4989.6
Exp/Cntr=0.3,0.1

Type RM Length L Ch R = 1,974,503,503,503
BEGIN DESCRIPTION:
Stream0668 2.0
END DESCRIPTION:
XS GIS Cut Line= 3
      2399125.01     13641375.01      2399375.00     13641525.00
      2399824.99     13641125.01
#Sta/Elev= 30
  4704.3  265.43  4762.6  262.99  4828.7  258.98  4855.9  258.17  4883.1  256.51
  4929.8  255.13  4945.3  253.83  4951.1  254.52  4960.9  253.61  4999.2  253.25
  5002.9  251.93  5007.6  251.51  5007.9  251.01  5011.4  251.01  5011.6  251.51
  5017.2  253.34  5031.4  253.73  5052.3  252.90  5088.2  254.00  5094.9  253.52
  5166.0  253.32  5208.7  253.74  5262.9  255.45  5293.1  255.98  5343.3  258.51
  5401.3  260.38  5470.4  262.86  5484.6  263.86  5498.6  263.55  5597.9  266.55
#Mann=7,-1,0
  4704.3   0.035       0  4883.1    0.07       0  5007.6    0.05       0
  5011.6    0.07       0  5262.9    0.05       0  5401.3   0.035       0
  5498.6    0.05       0
Bank Sta=5007.6,5011.6
Exp/Cntr=0.3,0.1

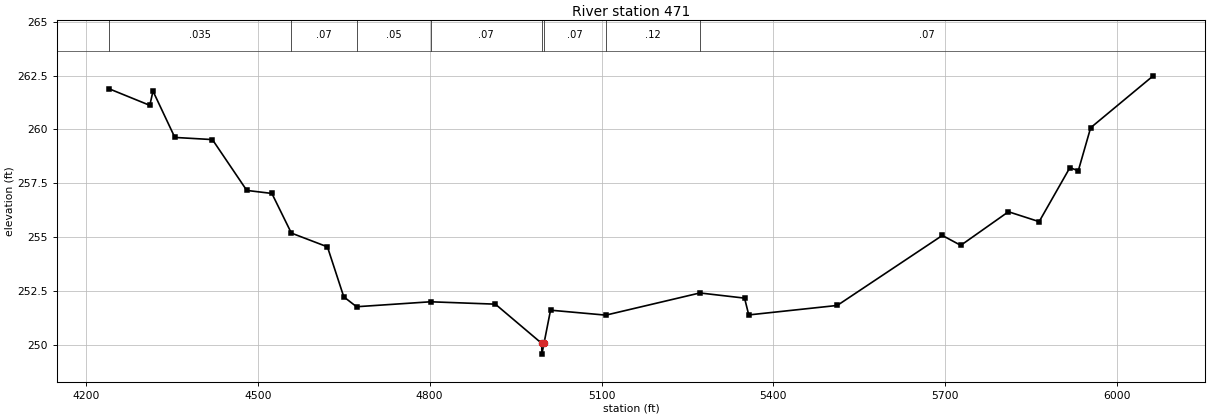
Type RM Length L Ch R = 1,471,0,0,0
BEGIN DESCRIPTION:
Stream0668 1.0
END DESCRIPTION:
XS GIS Cut Line= 4
      2398904.93     13641249.65      2399180.82     13641759.63
      2399343.85     13641843.24      2400326.27     13641446.09
#Sta/Elev= 30
  4240.3  261.89  4311.5  261.12  4317.1  261.78  4355.2  259.63  4420.8  259.53
  4480.8  257.17  4524.6  257.03  4558.6  255.19  4621.6  254.55  4650.1  252.23
  4672.4  251.77  4801.5  252.00  4914.7  251.89  4995.6  250.07  4995.9  249.57
  4999.6  250.07  5011.0  251.61  5107.5  251.38  5271.7  252.41  5349.7  252.17
  5357.0  251.39  5511.5  251.83  5694.9  255.08  5727.1  254.62  5810.3  256.18
  5863.9  255.72  5917.6  258.23  5932.2  258.08  5953.8  260.08  6063.0  262.49
#Mann=8,-1,0
  4240.3   0.035       0  4558.6    0.07       0  4672.4    0.05       0
  4801.5    0.07       0  4995.6    0.05       0  4999.6    0.07       0
  5107.5    0.12       0  5271.7    0.07       0
Bank Sta=4995.6,4999.6
Exp/Cntr=0.3,0.1

Chan Stop Cuts=-1