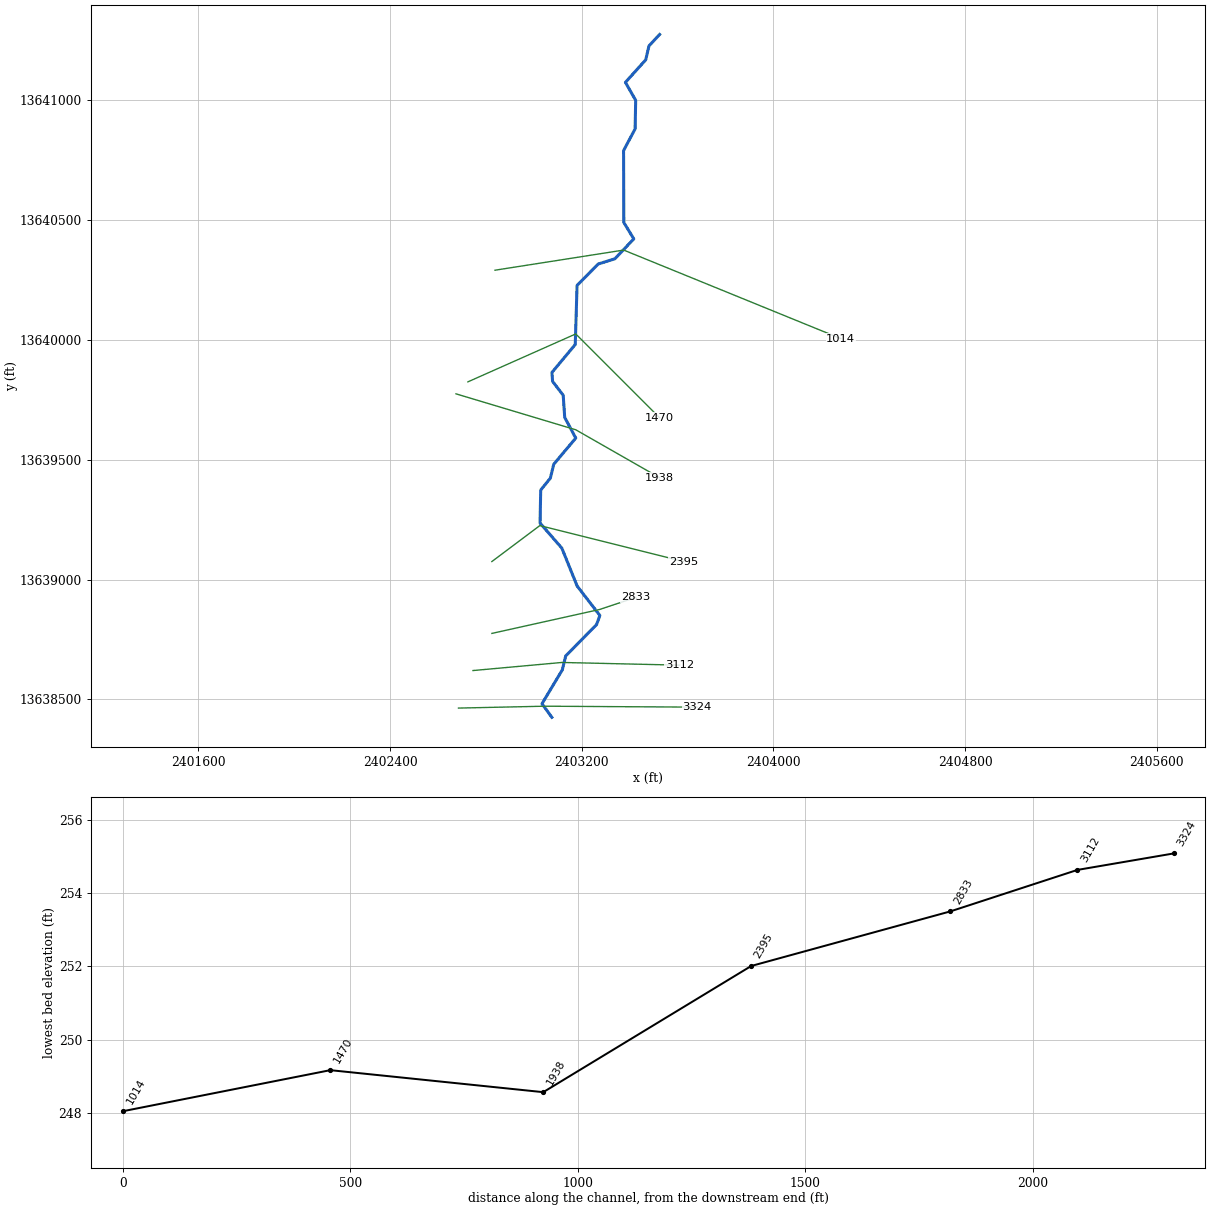
--- Stream0669.prj (project) ---

Proj Title=Stream0669 Base Level Engineering
Current Plan=p01
Default Exp/Contr=0.3,0.1
English Units
Geom File=g01
Flow File=f01
Plan File=p01
BEGIN DESCRIPTION:
Stream0669
END DESCRIPTION:

--- Stream0669.p01 (plan) ---

Plan Title=Multiple Run
Short Identifier=Multiple
Geom File=g01
Flow File=f01
Subcritical Flow
K Sum by GR= 0
Std Step Tol= 0.01
Critical Tol= 0.01
Num of Std Step Trials= 20
Max Error Tol= 0.3
Flow Tol Ratio= 0.001
Split Flow NTrial= 30
Split Flow Tol= 0.02
Split Flow Ratio= 0.02
Log Output Level= 0
Friction Slope Method= 1
Unsteady Friction Slope Method= 2
Unsteady Bridges Friction Slope Method= 1
Parabolic Critical Depth
Global Vel Dist=  1 , 1 , 1
Global Log Level= 0
CheckData=True
Encroach Param= -1, 0, 0, 0
BEGIN DESCRIPTION:
Multiple Run
END DESCRIPTION:

--- Stream0669.f01 (steady flow) ---

Flow Title=Multiple
Number of Profiles=7
Profile Names=10-year,25-year,50-year,1pct_min,100-year,1pct_plu,500-year
River Rch & RM= Stream0669,Reach-1,3324
     726    1174    1578    1025    2046    4083    3411
Boundary for River Rch & Prof#=Stream0669,Reach-1,1
Up Type=0
Dn Type=3
Dn Slope=0.005
Boundary for River Rch & Prof#=Stream0669,Reach-1,2
Up Type=0
Dn Type=3
Dn Slope=0.005
Boundary for River Rch & Prof#=Stream0669,Reach-1,3
Up Type=0
Dn Type=3
Dn Slope=0.005
Boundary for River Rch & Prof#=Stream0669,Reach-1,4
Up Type=0
Dn Type=3
Dn Slope=0.005
Boundary for River Rch & Prof#=Stream0669,Reach-1,5
Up Type=0
Dn Type=3
Dn Slope=0.005
Boundary for River Rch & Prof#=Stream0669,Reach-1,6
Up Type=0
Dn Type=3
Dn Slope=0.005
Boundary for River Rch & Prof#=Stream0669,Reach-1,7
Up Type=0
Dn Type=3
Dn Slope=0.005

--- Stream0669.g01 (geometry) ---

Geom Title=Existing Conditions

River Reach=Stream0669,Reach-1
Reach XY= 30
      2403075.00     13638425.00      2403034.14     13638481.51
      2403118.89     13638622.81      2403133.14     13638681.06
      2403261.89     13638811.79      2403275.59     13638850.00
      2403180.85     13638972.71      2403116.84     13639131.05
      2403026.04     13639235.44      2403028.74     13639373.44
      2403068.86     13639422.83      2403083.16     13639481.05
      2403175.04     13639590.34      2403128.89     13639676.58
      2403122.62     13639769.03      2403078.34     13639826.75
      2403075.60     13639864.38      2403172.93     13639980.86
      2403180.45     13640227.47      2403268.93     13640316.85
      2403338.27     13640338.63      2403417.21     13640421.57
      2403375.66     13640490.16      2403374.57     13640790.18
      2403422.75     13640880.94      2403425.13     13641000.11
      2403382.33     13641075.10      2403466.91     13641168.91
      2403480.70     13641227.35      2403525.00     13641275.00

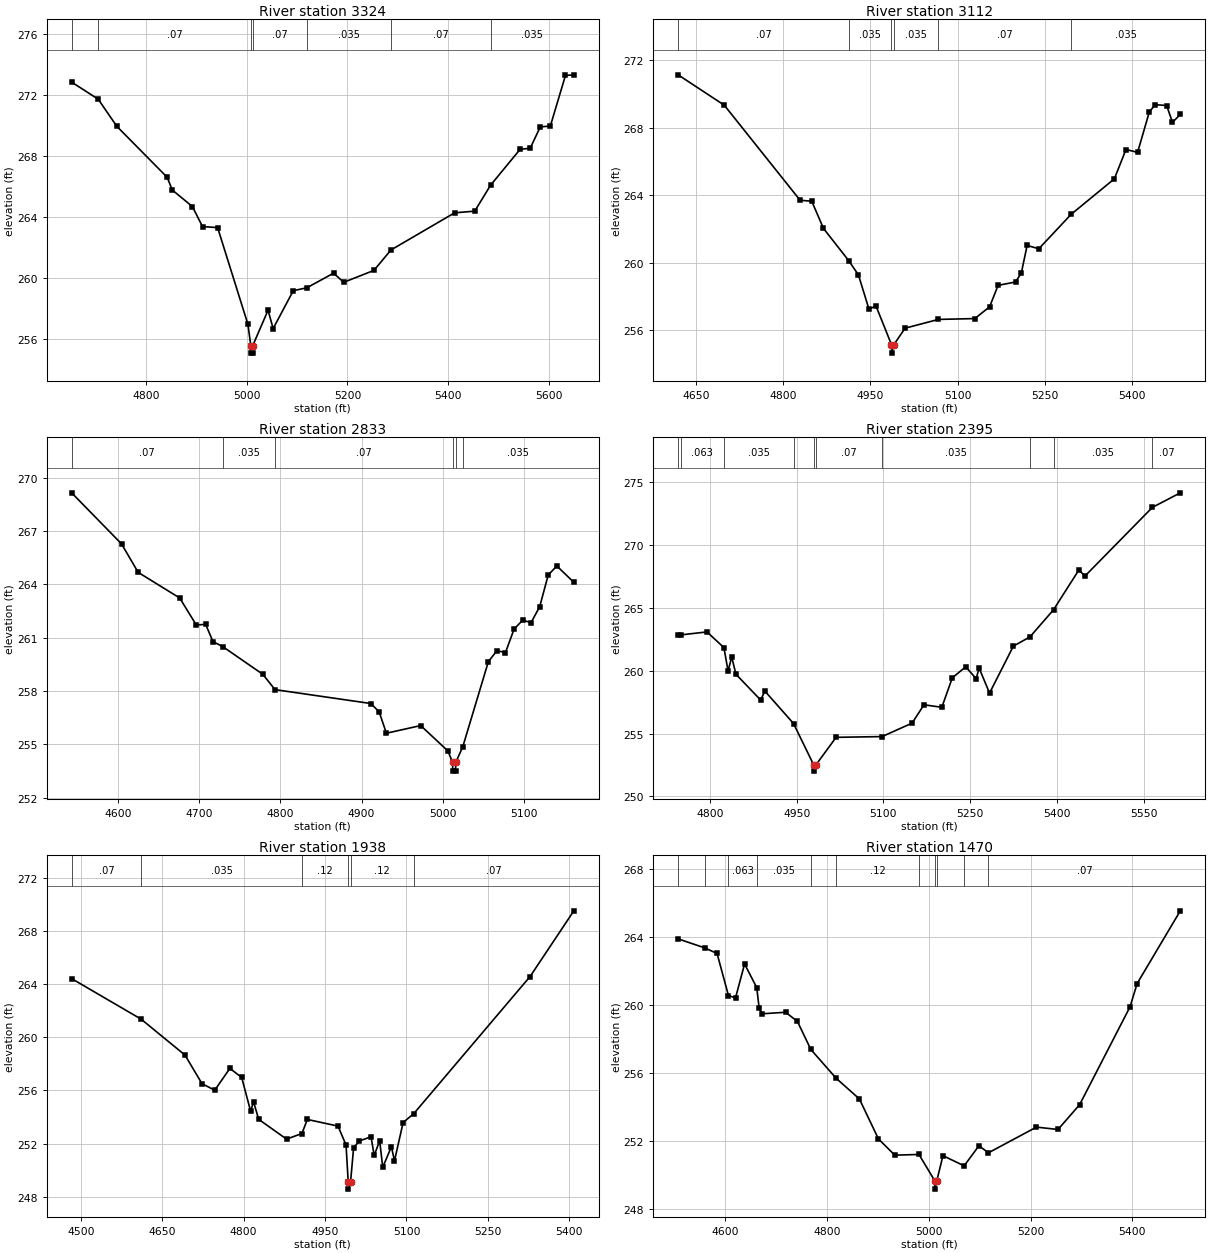
Type RM Length L Ch R = 1,3324,212,212,212
BEGIN DESCRIPTION:
Stream0669 7.0
END DESCRIPTION:
XS GIS Cut Line= 3
      2402685.43     13638463.34      2403045.44     13638471.16
      2403681.63     13638467.26
#Sta/Elev= 30
  4652.9  272.87  4705.6  271.75  4742.5  269.97  4842.5  266.62  4852.5  265.79
  4892.5  264.70  4912.5  263.39  4942.5  263.32  5002.6  256.97  5008.3  255.58
  5008.5  255.08  5012.0  255.08  5012.3  255.58  5042.6  257.90  5052.6  256.69
  5092.6  259.18  5119.5  259.37  5172.6  260.33  5192.6  259.73  5252.6  260.51
  5286.3  261.85  5412.6  264.29  5452.6  264.40  5483.9  266.10  5542.6  268.46
  5562.6  268.53  5582.6  269.93  5602.6  269.99  5632.6  273.31  5649.2  273.35
#Mann=7,-1,0
  4652.9    0.05       0  4705.6    0.07       0  5008.3    0.05       0
  5012.3    0.07       0  5119.5   0.035       0  5286.3    0.07       0
  5483.9   0.035       0
Bank Sta=5008.3,5012.3
Exp/Cntr=0.3,0.1

Type RM Length L Ch R = 1,3112,279,279,279
BEGIN DESCRIPTION:
E21253
END DESCRIPTION:
XS GIS Cut Line= 3
      2402745.94     13638620.00      2403117.24     13638653.75
      2403608.48     13638642.50
#Sta/Elev= 30
  4619.2  271.14  4698.6  269.34  4829.1  263.70  4849.2  263.64  4869.3  262.03
  4912.7  260.12  4929.5  259.27  4947.6  257.24  4959.7  257.43  4986.4  255.13
  4986.6  254.63  4990.4  255.13  5009.8  256.11  5067.2  256.63  5129.8  256.68
  5155.3  257.38  5169.8  258.65  5199.8  258.85  5209.8  259.38  5219.8  261.02
  5239.9  260.82  5295.7  262.87  5369.9  264.97  5389.9  266.71  5409.9  266.54
  5429.9  268.92  5439.9  269.37  5459.9  269.32  5469.9  268.32  5483.4  268.79
#Mann=6,-1,0
  4619.2    0.07       0  4912.7   0.035       0  4986.4   0.035       0
  4990.4   0.035       0  5067.2    0.07       0  5295.7   0.035       0
Bank Sta=4986.4,4990.4
Exp/Cntr=0.3,0.1

Type RM Length L Ch R = 1,2833,438,438,438
BEGIN DESCRIPTION:
Stream0669 6.0
END DESCRIPTION:
XS GIS Cut Line= 3
      2402824.95     13638774.99      2403275.00     13638875.00
      2403424.96     13638924.99
#Sta/Elev= 30
  4542.6  269.14  4604.1  266.27  4624.6  264.67  4675.8  263.23  4696.3  261.71
  4707.8  261.75  4716.8  260.78  4728.8  260.50  4778.3  258.94  4793.3  258.08
  4911.4  257.30  4921.7  256.83  4930.6  255.63  4972.9  256.06  5006.3  254.64
  5012.2  254.00  5012.4  253.50  5015.9  253.50  5016.2  254.00  5024.8  254.87
  5056.3  259.65  5066.9  260.27  5077.4  260.16  5088.0  261.48  5098.5  261.98
  5109.0  261.85  5119.6  262.74  5130.1  264.52  5140.7  265.03  5161.7  264.11
#Mann=6,-1,0
  4542.6    0.07       0  4728.8   0.035       0  4793.3    0.07       0
  5012.2    0.05       0  5016.2    0.07       0  5024.8   0.035       0
Bank Sta=5012.2,5016.2
Exp/Cntr=0.3,0.1

Type RM Length L Ch R = 1,2395,457,457,457
BEGIN DESCRIPTION:
Stream0669 5.0
END DESCRIPTION:
XS GIS Cut Line= 3
      2402825.01     13639075.01      2403025.00     13639225.00
      2403625.04     13639074.99
#Sta/Elev= 30
  4745.0  262.83  4749.2  262.85  4795.0  263.09  4824.2  261.84  4831.4  259.98
  4837.7  261.09  4845.0  259.72  4887.7  257.67  4895.0  258.38  4944.6  255.80
  4979.4  252.51  4979.7  252.01  4983.4  252.51  5018.2  254.70  5097.8  254.76
  5149.6  255.83  5170.2  257.29  5201.1  257.09  5219.2  259.44  5242.4  260.31
  5260.4  259.37  5265.6  260.21  5283.6  258.22  5324.8  261.96  5353.4  262.69
  5394.2  264.85  5438.2  268.03  5448.5  267.53  5565.2  273.00  5613.5  274.16
#Mann=10,-1,0
  4745.0    0.07       0  4749.2   0.063       0  4824.2   0.035       0
  4944.6    0.07       0  4979.4    0.05       0  4983.4    0.07       0
  5097.8   0.035       0  5353.4    0.07       0  5394.2   0.035       0
  5565.2    0.07       0
Bank Sta=4979.4,4983.4
Exp/Cntr=0.3,0.1

Type RM Length L Ch R = 1,1938,468,468,468
BEGIN DESCRIPTION:
Stream0669 4.0
END DESCRIPTION:
XS GIS Cut Line= 3
      2402674.99     13639775.00      2403175.00     13639625.00
      2403524.97     13639425.02
#Sta/Elev= 30
  4483.2  264.40  4611.3  261.35  4692.0  258.65  4723.3  256.50  4746.8  256.01
  4774.7  257.65  4796.4  256.97  4812.9  254.43  4818.2  255.15  4827.7  253.82
  4879.1  252.33  4907.3  252.75  4917.4  253.81  4973.9  253.31  4988.7  251.88
  4992.7  249.07  4992.9  248.57  4996.9  249.07  5002.6  251.68  5013.1  252.19
  5034.7  252.51  5040.5  251.10  5050.6  252.21  5056.3  250.21  5072.2  251.76
  5077.9  250.70  5093.8  253.58  5113.5  254.25  5327.7  264.56  5408.3  269.50
#Mann=6,-1,0
  4483.2    0.07       0  4611.3   0.035       0  4907.3    0.12       0
  4992.7    0.05       0  4996.9    0.12       0  5113.5    0.07       0
Bank Sta=4992.7,4996.9
Exp/Cntr=0.3,0.1

Type RM Length L Ch R = 1,1470,456,456,456
BEGIN DESCRIPTION:
Stream0669 3.0
END DESCRIPTION:
XS GIS Cut Line= 3
      2402724.97     13639824.99      2403175.00     13640025.00
      2403525.03     13639674.97
#Sta/Elev= 30
  4506.9  263.90  4559.1  263.37  4583.5  263.04  4605.9  260.56  4619.8  260.43
  4637.6  262.42  4661.5  261.03  4666.3  259.81  4671.8  259.49  4718.3  259.58
  4741.5  259.04  4767.9  257.39  4817.8  255.69  4863.3  254.48  4900.9  252.12
  4933.0  251.17  4980.5  251.21  5011.4  249.67  5011.7  249.17  5015.6  249.67
  5027.7  251.14  5069.3  250.54  5098.4  251.72  5117.2  251.31  5211.5  252.82
  5253.9  252.68  5296.4  254.14  5395.4  259.89  5409.5  261.27  5494.4  265.55
#Mann=11,-1,0
  4506.9    0.07       0  4559.1   0.035       0  4605.9   0.063       0
  4661.5   0.035       0  4767.9    0.07       0  4817.8    0.12       0
  4980.5    0.07       0  5011.4    0.05       0  5015.6    0.07       0
  5069.3    0.12       0  5117.2    0.07       0
Bank Sta=5011.4,5015.6
Exp/Cntr=0.3,0.1

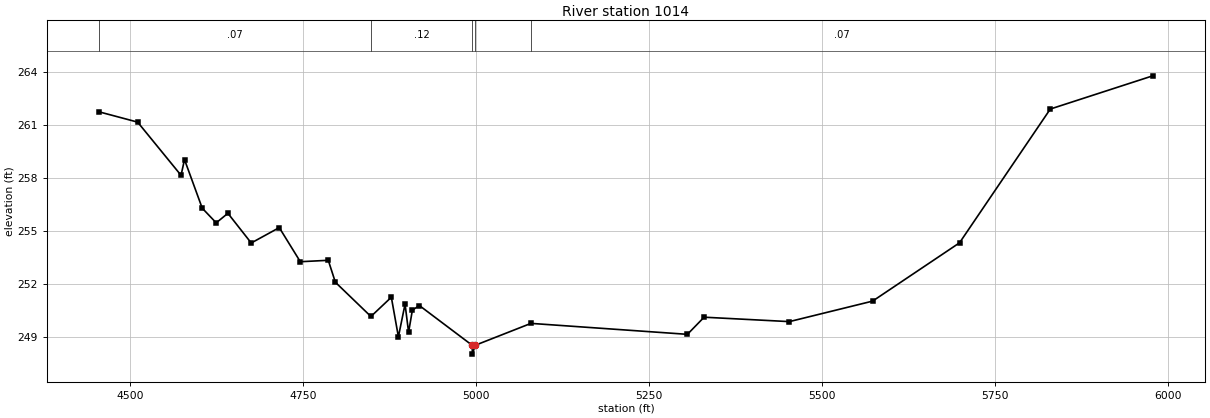
Type RM Length L Ch R = 1,1014,0,0,0
BEGIN DESCRIPTION:
Stream0669 2.0
END DESCRIPTION:
XS GIS Cut Line= 3
      2402838.04     13640290.99      2403375.00     13640375.00
      2404281.05     13640005.74
#Sta/Elev= 30
  4455.9  261.76  4511.4  261.18  4574.1  258.17  4579.1  259.06  4604.7  256.31
  4624.9  255.48  4641.8  256.02  4675.5  254.34  4716.0  255.21  4746.4  253.28
  4786.8  253.36  4797.0  252.12  4848.4  250.18  4877.9  251.27  4888.1  249.03
  4897.7  250.88  4902.8  249.29  4908.3  250.54  4918.4  250.80  4994.7  248.55
  4995.0  248.05  4999.0  248.55  5079.6  249.79  5305.6  249.17  5329.7  250.14
  5452.9  249.89  5573.1  251.05  5698.7  254.35  5829.8  261.92  5977.8  263.80
#Mann=5,-1,0
  4455.9    0.07       0  4848.4    0.12       0  4994.7    0.05       0
  4999.0    0.12       0  5079.6    0.07       0
Bank Sta=4994.7,4999
Exp/Cntr=0.3,0.1

Chan Stop Cuts=-1