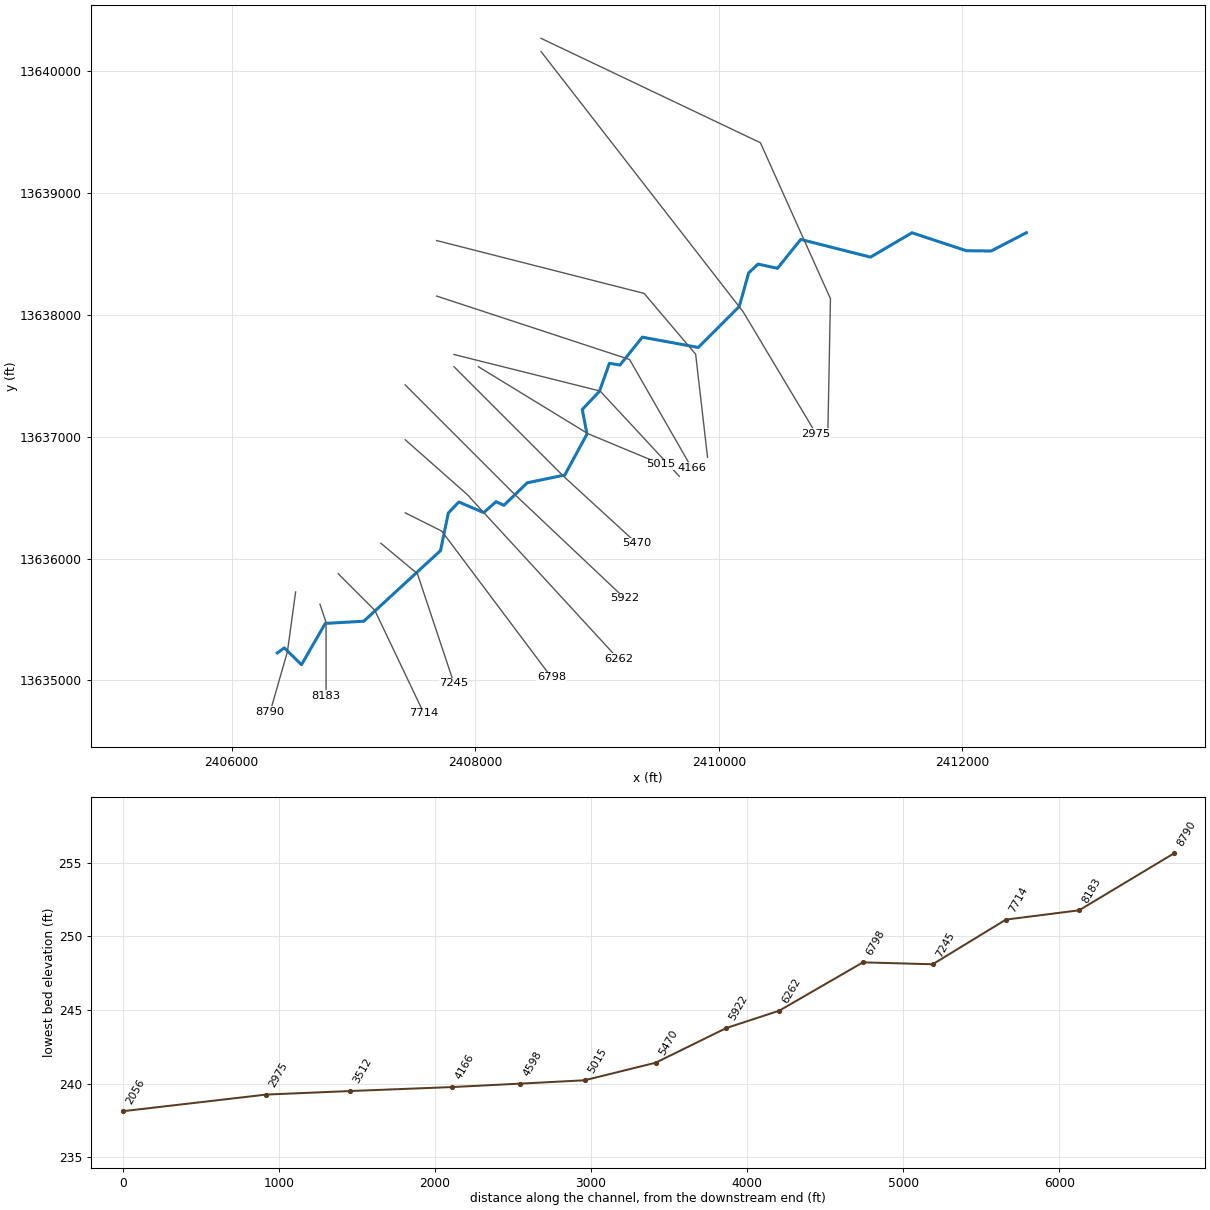
--- Stream0670.prj (project) ---

Proj Title=Stream0670 Base Level Engineering
Current Plan=p01
Default Exp/Contr=0.3,0.1
English Units
Geom File=g01
Flow File=f01
Plan File=p01
BEGIN DESCRIPTION:
Stream0670
END DESCRIPTION:

--- Stream0670.p01 (plan) ---

Plan Title=Multiple Run
Short Identifier=Multiple
Geom File=g01
Flow File=f01
Subcritical Flow
K Sum by GR= 0
Std Step Tol= 0.01
Critical Tol= 0.01
Num of Std Step Trials= 20
Max Error Tol= 0.3
Flow Tol Ratio= 0.001
Split Flow NTrial= 30
Split Flow Tol= 0.02
Split Flow Ratio= 0.02
Log Output Level= 0
Friction Slope Method= 1
Unsteady Friction Slope Method= 2
Unsteady Bridges Friction Slope Method= 1
Parabolic Critical Depth
Global Vel Dist=  1 , 1 , 1
Global Log Level= 0
CheckData=True
Encroach Param= -1, 0, 0, 0
BEGIN DESCRIPTION:
Multiple Run
END DESCRIPTION:

--- Stream0670.f01 (steady flow) ---

Flow Title=Multiple
Number of Profiles=7
Profile Names=10-year,25-year,50-year,1pct_min,100-year,1pct_plu,500-year
River Rch & RM= Stream0670,Reach-1,8790
     566     903    1205     778    1552    3096    2552
River Rch & RM= Stream0670,Reach-1,4598
     847    1376    1856    1209    2413    4814    4044
Boundary for River Rch & Prof#=Stream0670,Reach-1,1
Up Type=0
Dn Type=3
Dn Slope=0.005
Boundary for River Rch & Prof#=Stream0670,Reach-1,2
Up Type=0
Dn Type=3
Dn Slope=0.005
Boundary for River Rch & Prof#=Stream0670,Reach-1,3
Up Type=0
Dn Type=3
Dn Slope=0.005
Boundary for River Rch & Prof#=Stream0670,Reach-1,4
Up Type=0
Dn Type=3
Dn Slope=0.005
Boundary for River Rch & Prof#=Stream0670,Reach-1,5
Up Type=0
Dn Type=3
Dn Slope=0.005
Boundary for River Rch & Prof#=Stream0670,Reach-1,6
Up Type=0
Dn Type=3
Dn Slope=0.005
Boundary for River Rch & Prof#=Stream0670,Reach-1,7
Up Type=0
Dn Type=3
Dn Slope=0.005

--- Stream0670.g01 (geometry) ---

Geom Title=Existing Conditions

River Reach=Stream0670,Reach-1
Reach XY= 30
      2406375.00     13635225.00      2406432.04     13635266.38
      2406573.54     13635128.00      2406768.48     13635467.32
      2407084.68     13635485.20      2407714.65     13636064.88
      2407778.61     13636373.53      2407864.97     13636464.05
      2408069.11     13636376.98      2408171.67     13636466.98
      2408235.00     13636436.24      2408426.46     13636621.46
      2408735.00     13636685.63      2408917.18     13637021.58
      2408878.53     13637223.53      2409019.48     13637372.57
      2409101.29     13637602.64      2409188.36     13637588.64
      2409371.57     13637817.21      2409831.19     13637732.81
      2410167.18     13638068.81      2410244.78     13638345.18
      2410321.57     13638417.21      2410481.17     13638382.76
      2410672.30     13638619.65      2411245.08     13638474.33
      2411585.62     13638674.40      2412030.86     13638527.07
      2412235.19     13638524.54      2412525.00     13638675.00

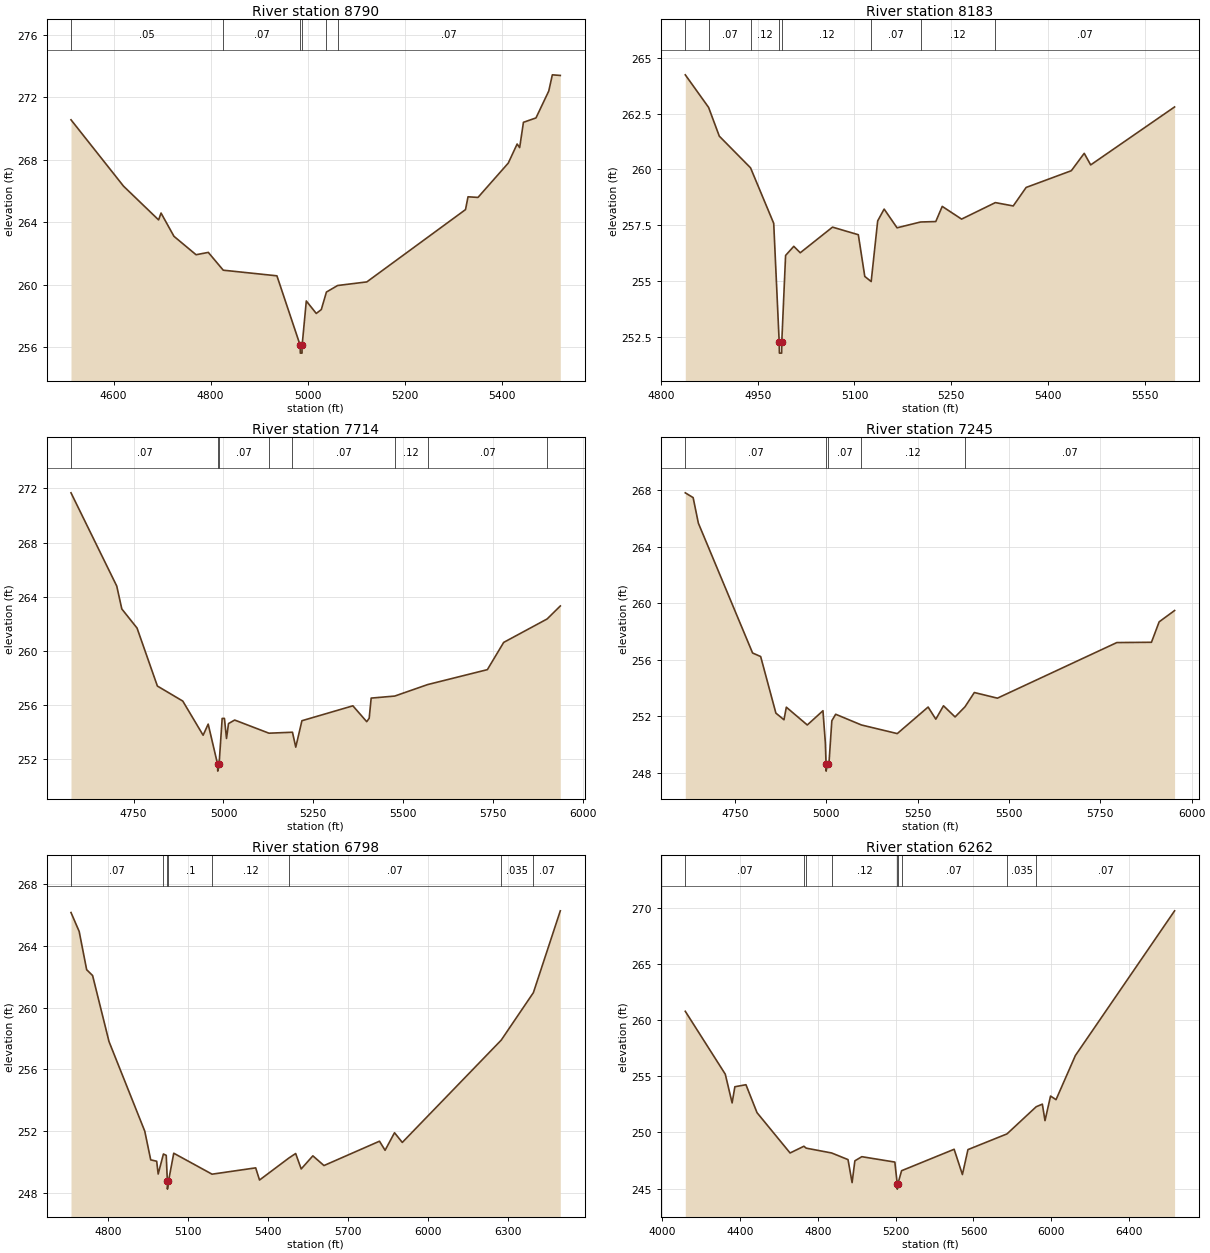
Type RM Length L Ch R = 1,8790,607,607,607
BEGIN DESCRIPTION:
Stream0670 18.0
END DESCRIPTION:
XS GIS Cut Line= 3
      2406525.01     13635725.04      2406457.63     13635233.76
      2406316.09     13634742.11
#Sta/Elev= 30
  4512.5  270.56  4620.7  266.31  4692.9  264.15  4697.9  264.59  4724.5  263.10
  4770.0  261.92  4795.2  262.07  4826.0  260.93  4936.5  260.57  4984.4  256.12
  4984.7  255.62  4988.2  255.62  4988.4  256.12  4997.0  258.96  5017.5  258.16
  5027.9  258.41  5038.4  259.53  5061.5  259.95  5121.6  260.18  5324.8  264.81
  5330.0  265.63  5350.5  265.59  5412.9  267.79  5431.1  269.01  5436.3  268.78
  5444.1  270.40  5469.9  270.68  5496.2  272.40  5503.6  273.44  5520.0  273.40
#Mann=6,-1,0
  4512.5    0.05       0  4826.0    0.07       0  4984.4    0.05       0
  4988.4    0.07       0  5038.4    0.12       0  5061.5    0.07       0
Bank Sta=4984.4,4988.4
Exp/Cntr=0.3,0.1

Type RM Length L Ch R = 1,8183,469,469,469
BEGIN DESCRIPTION:
Stream0670 17.0
END DESCRIPTION:
XS GIS Cut Line= 3
      2406725.01     13635624.96      2406775.00     13635475.00
      2406775.00     13634874.97
#Sta/Elev= 30
  4837.9  264.24  4874.0  262.78  4890.6  261.49  4939.0  260.07  4974.9  257.58
  4983.4  252.26  4983.7  251.76  4987.2  251.76  4987.4  252.26  4993.3  256.14
  5006.0  256.55  5016.0  256.26  5066.0  257.41  5106.0  257.07  5116.0  255.20
  5125.9  254.97  5136.0  257.69  5146.0  258.22  5166.0  257.38  5202.4  257.64
  5226.0  257.66  5236.0  258.34  5266.0  257.77  5318.3  258.51  5346.0  258.36
  5366.0  259.19  5436.0  259.94  5456.0  260.72  5466.0  260.20  5596.0  262.80
#Mann=8,-1,0
  4837.9    0.05       0  4874.0    0.07       0  4939.0    0.12       0
  4983.4    0.05       0  4987.4    0.12       0  5125.9    0.07       0
  5202.4    0.12       0  5318.3    0.07       0
Bank Sta=4983.4,4987.4
Exp/Cntr=0.3,0.1

Type RM Length L Ch R = 1,7714,469,469,469
BEGIN DESCRIPTION:
Stream0670 16.0
END DESCRIPTION:
XS GIS Cut Line= 3
      2406875.01     13635874.99      2407175.00     13635575.00
      2407578.16     13634728.57
#Sta/Elev= 30
  4575.7  271.67  4703.0  264.79  4717.1  263.10  4759.5  261.69  4816.1  257.41
  4886.8  256.30  4943.4  253.78  4957.5  254.60  4983.8  251.63  4984.1  251.13
  4987.8  251.63  4996.4  255.02  5002.7  255.02  5008.5  253.54  5014.1  254.64
  5031.2  254.90  5126.6  253.93  5192.1  254.00  5201.2  252.90  5218.4  254.85
  5360.2  255.95  5398.7  254.78  5405.6  255.03  5411.1  256.52  5476.7  256.67
  5568.6  257.52  5734.5  258.62  5779.9  260.63  5900.8  262.36  5937.5  263.32
#Mann=8,-1,0
  4575.7    0.07       0  4983.8    0.05       0  4987.8    0.07       0
  5126.6    0.12       0  5192.1    0.07       0  5476.7    0.12       0
  5568.6    0.07       0  5900.8   0.035       0
Bank Sta=4983.8,4987.8
Exp/Cntr=0.3,0.1

Type RM Length L Ch R = 1,7245,447,447,447
BEGIN DESCRIPTION:
Stream0670 15.0
END DESCRIPTION:
XS GIS Cut Line= 3
      2407225.00     13636125.00      2407525.00     13635875.00
      2407825.00     13634974.99
#Sta/Elev= 30
  4614.1  267.82  4635.6  267.48  4649.9  265.67  4798.3  256.47  4820.4  256.22
  4862.1  252.21  4884.2  251.74  4890.7  252.63  4948.0  251.37  4990.9  252.38
  4997.5  250.09  4999.4  248.60  4999.6  248.10  5003.4  248.60  5007.2  248.60
  5015.2  251.67  5025.7  252.13  5096.2  251.37  5194.3  250.76  5278.7  252.64
  5299.8  251.78  5320.8  252.73  5352.5  251.94  5379.7  252.66  5405.2  253.67
  5468.4  253.27  5795.2  257.21  5890.0  257.23  5911.1  258.68  5953.3  259.48
#Mann=5,-1,0
  4614.1    0.07       0  4999.4    0.05       0  5003.4    0.07       0
  5096.2    0.12       0  5379.7    0.07       0
Bank Sta=4999.4,5003.4
Exp/Cntr=0.3,0.1

Type RM Length L Ch R = 1,6798,536,536,536
BEGIN DESCRIPTION:
Stream0670 14.0
END DESCRIPTION:
XS GIS Cut Line= 3
      2407425.04     13636374.98      2407725.00     13636225.00
      2408625.02     13635024.97
#Sta/Elev= 30
  4659.7  266.18  4690.4  264.95  4718.4  262.47  4740.7  262.09  4802.2  257.81
  4936.4  251.99  4958.7  250.13  4981.1  250.04  4986.7  249.21  5006.4  250.51
  5016.9  250.42  5021.2  248.73  5021.4  248.23  5025.2  248.73  5045.1  250.56
  5188.8  249.20  5352.4  249.61  5366.9  248.82  5477.1  250.25  5502.4  250.54
  5523.2  249.54  5566.9  250.39  5608.6  249.76  5816.9  251.34  5837.8  250.75
  5873.2  251.89  5902.4  251.26  6273.5  257.90  6394.1  260.98  6495.1  266.29
#Mann=8,-1,0
  4659.7    0.07       0  5006.4     0.1       0  5021.2    0.05       0
  5025.2     0.1       0  5188.8    0.12       0  5477.1    0.07       0
  6273.5   0.035       0  6394.1    0.07       0
Bank Sta=5021.2,5025.2
Exp/Cntr=0.3,0.1

Type RM Length L Ch R = 1,6262,340,340,340
BEGIN DESCRIPTION:
Stream0670 13.0
END DESCRIPTION:
XS GIS Cut Line= 3
      2407425.00     13636975.00      2407932.16     13636527.19
      2409175.03     13635174.97
#Sta/Elev= 30
  4119.8  260.79  4325.2  255.19  4360.3  252.63  4374.5  254.07  4431.4  254.25
  4488.3  251.76  4658.1  248.17  4729.1  248.77  4740.7  248.60  4871.6  248.17
  4955.6  247.58  4976.6  245.53  4990.8  247.47  5026.5  247.84  5196.1  247.36
  5208.3  245.45  5208.5  244.95  5212.3  245.45  5230.7  246.59  5500.7  248.50
  5543.2  246.25  5571.6  248.47  5772.2  249.87  5922.3  252.29  5953.8  252.52
  5967.4  251.05  5995.8  253.24  6024.1  252.92  6123.4  256.85  6633.0  269.74
#Mann=9,-1,0
  4119.8    0.07       0  4729.1    0.12       0  4740.7     0.1       0
  4871.6    0.12       0  5208.3    0.05       0  5212.3    0.12       0
  5230.7    0.07       0  5772.2   0.035       0  5922.3    0.07       0
Bank Sta=5208.3,5212.3
Exp/Cntr=0.3,0.1

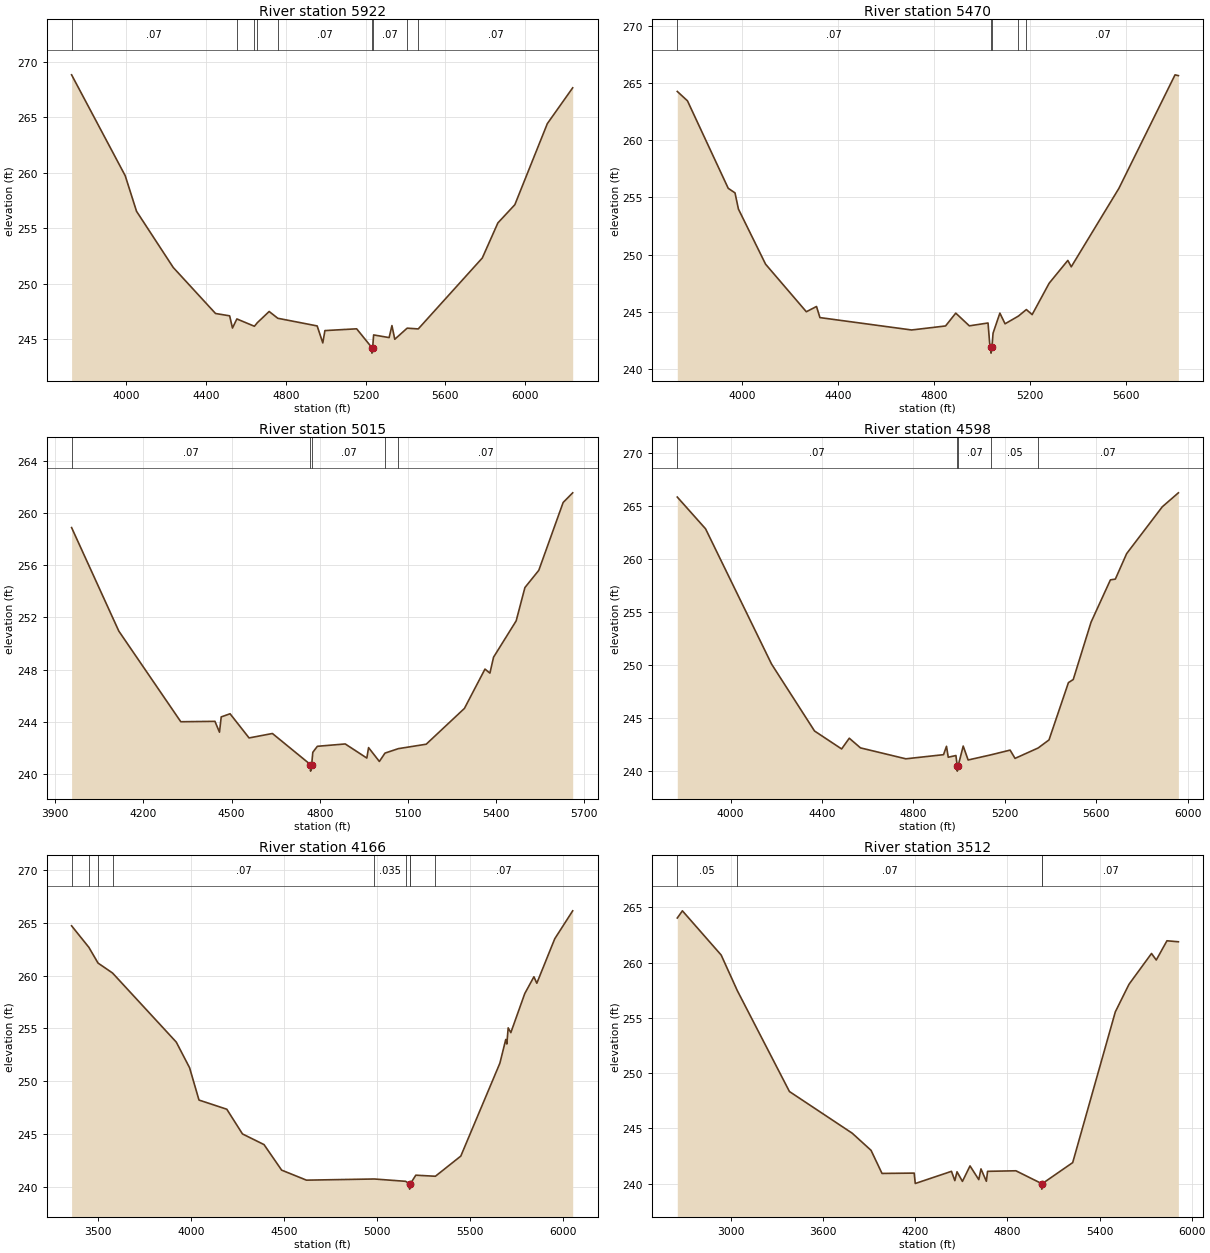
Type RM Length L Ch R = 1,5922,452,452,452
BEGIN DESCRIPTION:
Stream0670 12.0
END DESCRIPTION:
XS GIS Cut Line= 3
      2407425.01     13637424.99      2408325.00     13636525.00
      2409224.98     13635675.02
#Sta/Elev= 30
  3727.2  268.84  3995.9  259.75  4052.5  256.55  4236.3  251.49  4448.4  247.34
  4519.1  247.13  4533.3  246.03  4555.3  246.85  4643.1  246.19  4658.3  246.52
  4717.1  247.52  4760.3  246.91  4957.6  246.22  4985.8  244.69  4996.4  245.80
  5155.5  245.96  5231.6  244.27  5231.9  243.77  5235.6  244.27  5240.5  245.41
  5318.2  245.17  5332.3  246.25  5346.5  245.02  5408.6  246.02  5464.1  245.95
  5785.0  252.34  5863.1  255.50  5948.1  257.14  6110.7  264.44  6237.9  267.67
#Mann=9,-1,0
  3727.2    0.07       0  4555.3    0.12       0  4643.1    0.07       0
  4658.3    0.12       0  4760.3    0.07       0  5231.6    0.05       0
  5235.6    0.07       0  5408.6   0.035       0  5464.1    0.07       0
Bank Sta=5231.6,5235.6
Exp/Cntr=0.3,0.1

Type RM Length L Ch R = 1,5470,455,455,455
BEGIN DESCRIPTION:
Stream0670 11.0
END DESCRIPTION:
XS GIS Cut Line= 3
      2407824.99     13637575.01      2408725.00     13636675.00
      2409325.04     13636124.97
#Sta/Elev= 30
  3731.8  264.25  3774.2  263.43  3943.9  255.80  3972.2  255.40  3986.4  253.99
  4099.5  249.18  4269.2  245.03  4311.6  245.49  4325.8  244.52  4707.6  243.44
  4849.0  243.79  4891.5  244.91  4948.0  243.80  5025.9  244.05  5032.7  242.27
  5038.1  241.92  5038.3  241.42  5042.1  241.92  5046.8  243.16  5075.2  244.91
  5096.8  243.98  5152.3  244.65  5185.5  245.22  5209.6  244.78  5280.5  247.52
  5358.2  249.51  5372.4  248.95  5571.0  255.80  5804.7  265.70  5818.6  265.63
#Mann=5,-1,0
  3731.8    0.07       0  5038.1    0.05       0  5042.1    0.07       0
  5152.3   0.035       0  5185.5    0.07       0
Bank Sta=5038.1,5042.1
Exp/Cntr=0.3,0.1

Type RM Length L Ch R = 1,5015,417,417,417
BEGIN DESCRIPTION:
Stream0670 10.0
END DESCRIPTION:
XS GIS Cut Line= 3
      2408025.02     13637574.99      2408925.00     13637025.00
      2409524.97     13636775.01
#Sta/Elev= 30
  3955.6  258.87  4116.2  250.95  4327.1  244.01  4443.3  244.04  4458.7  243.21
  4464.6  244.38  4494.7  244.62  4559.4  242.77  4638.8  243.11  4768.3  240.73
  4768.6  240.23  4772.3  240.73  4776.2  241.67  4791.7  242.13  4886.5  242.31
  4960.0  241.23  4965.9  242.03  5002.6  240.97  5021.8  241.61  5067.1  241.95
  5162.0  242.29  5292.0  245.03  5361.9  248.04  5378.7  247.73  5391.1  248.95
  5468.0  251.73  5497.8  254.28  5545.0  255.60  5627.8  260.79  5660.3  261.53
#Mann=5,-1,0
  3955.6    0.07       0  4768.3    0.05       0  4772.3    0.07       0
  5021.8    0.05       0  5067.1    0.07       0
Bank Sta=4768.3,4772.3
Exp/Cntr=0.3,0.1

Type RM Length L Ch R = 1,4598,432,432,432
BEGIN DESCRIPTION:
Stream0670 9.0
END DESCRIPTION:
XS GIS Cut Line= 3
      2407825.04     13637674.99      2409025.00     13637375.00
      2409674.97     13636675.03
#Sta/Elev= 30
  3767.1  265.82  3890.8  262.83  4179.4  250.09  4367.5  243.78  4486.0  242.09
  4519.5  243.10  4568.5  242.19  4766.9  241.16  4931.8  241.55  4944.7  242.34
  4952.4  241.31  4986.0  241.47  4991.7  240.50  4991.9  240.00  4995.7  240.50
  5017.9  242.36  5039.4  241.05  5138.2  241.53  5223.1  241.98  5244.6  241.20
  5345.6  242.18  5393.2  242.94  5478.2  248.34  5499.2  248.63  5577.1  254.03
  5661.9  258.02  5683.4  258.09  5732.8  260.49  5888.6  264.90  5959.2  266.22
#Mann=5,-1,0
  3767.1    0.07       0  4991.7    0.05       0  4995.7    0.07       0
  5138.2    0.05       0  5345.6    0.07       0
Bank Sta=4991.7,4995.7
Exp/Cntr=0.3,0.1

Type RM Length L Ch R = 1,4166,654,654,654
BEGIN DESCRIPTION:
Stream0670 8.0
END DESCRIPTION:
XS GIS Cut Line= 3
      2407682.56     13638154.81      2409266.80     13637633.97
      2409776.78     13636744.22
#Sta/Elev= 30
  3357.8  264.72  3450.7  262.68  3499.9  261.19  3577.8  260.25  3920.5  253.70
  3992.0  251.27  4042.5  248.21  4192.0  247.34  4276.2  245.00  4392.0  243.99
  4486.7  241.57  4620.1  240.62  4984.9  240.73  5153.1  240.51  5174.2  240.27
  5174.5  239.77  5178.3  240.27  5207.9  241.09  5313.1  240.99  5449.6  242.90
  5659.6  251.70  5691.3  253.95  5697.0  253.52  5704.3  255.05  5718.6  254.60
  5793.4  258.30  5842.6  259.89  5858.2  259.28  5954.5  263.49  6051.0  266.14
#Mann=9,-1,0
  3357.8    0.05       0  3450.7    0.07       0  3499.9    0.05       0
  3577.8    0.07       0  4984.9   0.035       0  5153.1    0.05       0
  5174.2   0.035       0  5178.3    0.05       0  5313.1    0.07       0
Bank Sta=5174.2,5178.3
Exp/Cntr=0.3,0.1

Type RM Length L Ch R = 1,3512,537,537,537
BEGIN DESCRIPTION:
XS7438
END DESCRIPTION:
XS GIS Cut Line= 4
      2407682.62     13638610.52      2409386.16     13638176.50
      2409809.33     13637677.37      2409906.99     13636831.02
#Sta/Elev= 30
  2649.6  264.03  2683.0  264.68  2935.5  260.68  3040.6  257.46  3380.2  248.33
  3789.1  244.56  3911.8  243.01  3983.2  240.92  4192.8  240.95  4200.0  240.01
  4435.7  241.11  4457.7  240.27  4471.9  241.07  4507.1  240.20  4556.5  241.60
  4613.6  240.36  4627.9  241.33  4663.0  240.21  4670.8  241.11  4855.3  241.16
  5023.5  240.00  5023.8  239.50  5027.7  240.00  5225.4  241.90  5503.1  255.54
  5592.0  258.03  5738.8  260.82  5769.8  260.23  5839.4  261.97  5913.9  261.88
#Mann=4,-1,0
  2649.6    0.05       0  3040.6    0.07       0  5023.5    0.05       0
  5027.7    0.07       0
Bank Sta=5023.5,5027.7
Exp/Cntr=0.3,0.1

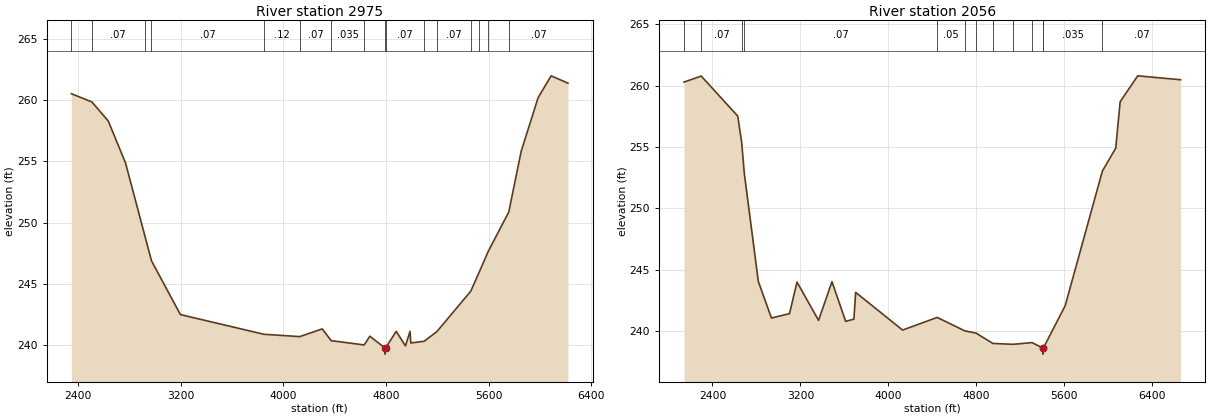
Type RM Length L Ch R = 1,2975,919,919,919
BEGIN DESCRIPTION:
XS7437
END DESCRIPTION:
XS GIS Cut Line= 3
      2408539.78     13640162.20      2410199.96     13638024.59
      2410796.73     13637026.35
#Sta/Elev= 30
  2348.1  260.53  2507.8  259.86  2635.7  258.30  2770.5  254.86  2919.1  248.99
  2972.1  246.89  3197.7  242.49  3848.7  240.88  4127.8  240.69  4302.8  241.32
  4372.8  240.36  4629.5  240.01  4673.9  240.72  4792.0  239.76  4792.3  239.26
  4796.5  239.76  4879.3  241.12  4951.7  239.93  4987.0  241.12  4993.4  240.17
  5097.0  240.31  5196.4  241.10  5460.5  244.40  5522.9  245.88  5596.0  247.64
  5756.6  250.87  5853.0  255.82  5985.3  260.21  6086.5  261.99  6217.7  261.39
#Mann=16,-1,0
  2348.1    0.05       0  2507.8    0.07       0  2919.1    0.12       0
  2972.1    0.07       0  3848.7    0.12       0  4127.8    0.07       0
  4372.8   0.035       0  4629.5    0.07       0  4792.0    0.05       0
  4796.5    0.07       0  5097.0   0.035       0  5196.4    0.07       0
  5460.5   0.035       0  5522.9    0.07       0  5596.0   0.035       0
  5756.6    0.07       0
Bank Sta=4792,4796.5
Exp/Cntr=0.3,0.1

Type RM Length L Ch R = 1,2056,0,0,0
BEGIN DESCRIPTION:
XS7436
END DESCRIPTION:
XS GIS Cut Line= 4
      2408539.82     13640270.68      2410341.02     13639413.48
      2410916.11     13638133.10      2410894.40     13637015.48
#Sta/Elev= 30
  2141.0  260.29  2297.6  260.78  2629.9  257.52  2666.2  255.33  2689.4  252.86
  2817.1  244.05  2936.2  241.07  3100.7  241.43  3168.8  244.00  3364.9  240.88
  3486.8  244.03  3611.4  240.80  3686.1  240.98  3702.2  243.16  4129.1  240.09
  4443.9  241.12  4693.6  240.03  4797.5  239.84  4950.3  239.00  5137.1  238.93
  5305.5  239.07  5404.2  238.63  5404.6  238.13  5409.5  238.63  5607.5  242.07
  5946.1  253.04  6067.6  254.91  6107.6  258.69  6267.6  260.80  6657.2  260.48
#Mann=13,-1,0
  2141.0    0.05       0  2297.6    0.07       0  2666.2    0.12       0
  2689.4    0.07       0  4443.9    0.05       0  4693.6   0.035       0
  4797.5    0.05       0  4950.3   0.035       0  5137.1    0.07       0
  5305.5   0.035       0  5404.2   0.035       0  5409.5   0.035       0
  5946.1    0.07       0
Bank Sta=5404.2,5409.5
Exp/Cntr=0.3,0.1

Chan Stop Cuts=-1