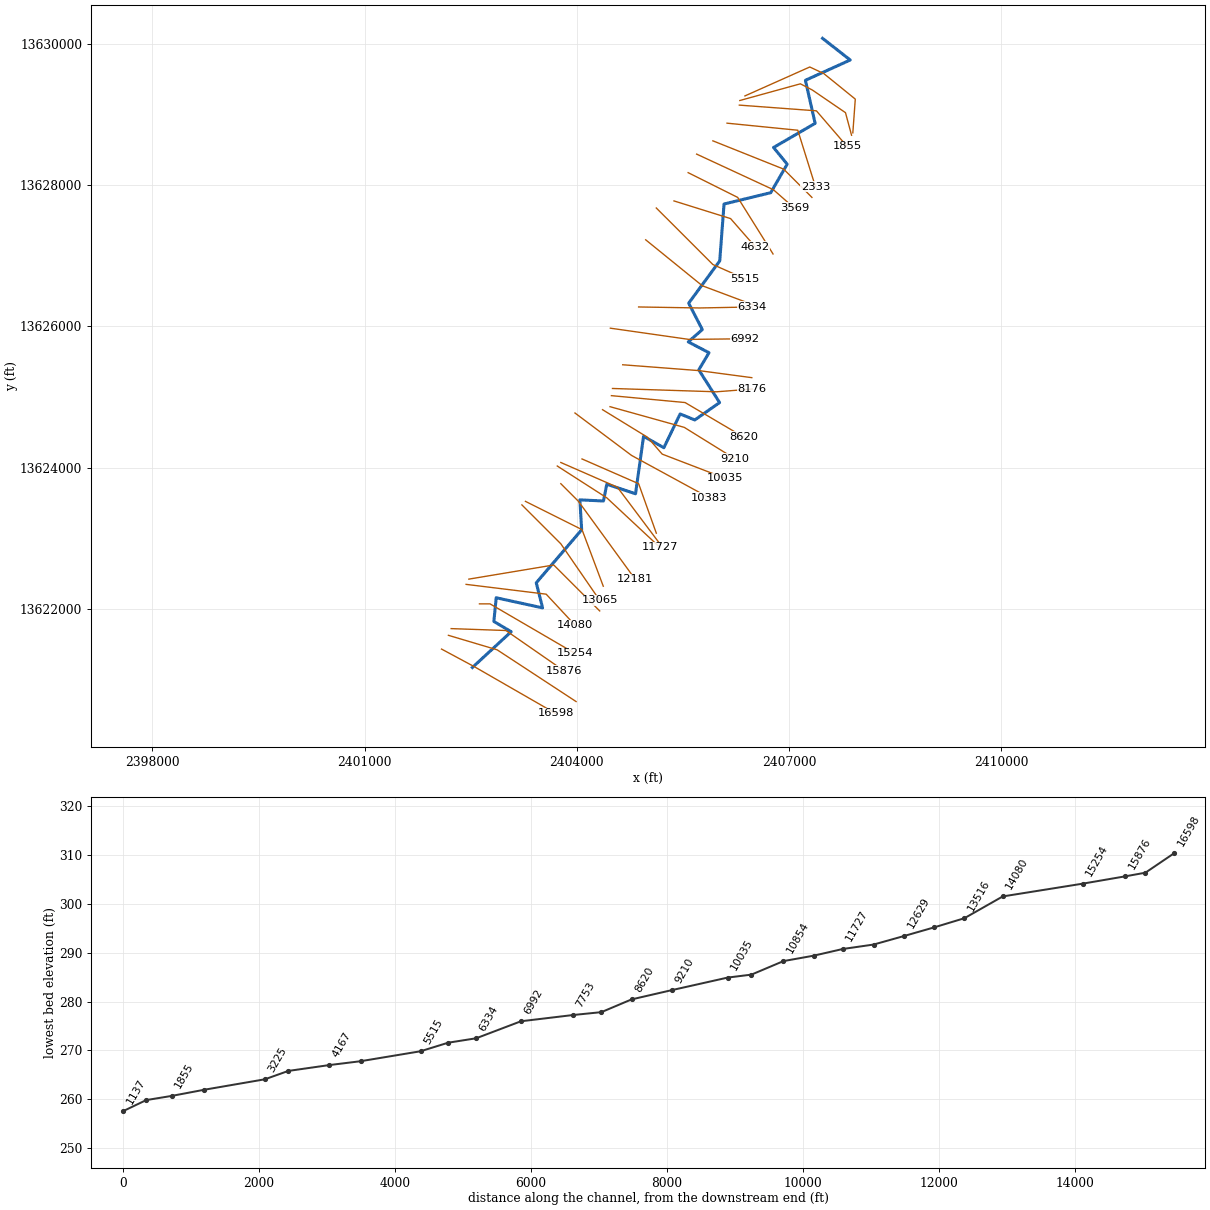
--- Stream0672.prj (project) ---

Proj Title=Stream0672 Base Level Engineering
Current Plan=p01
Default Exp/Contr=0.3,0.1
English Units
Geom File=g01
Flow File=f01
Plan File=p01
BEGIN DESCRIPTION:
Stream0672
END DESCRIPTION:

--- Stream0672.p01 (plan) ---

Plan Title=Multiple Run
Short Identifier=Multiple
Geom File=g01
Flow File=f01
Subcritical Flow
K Sum by GR= 0
Std Step Tol= 0.01
Critical Tol= 0.01
Num of Std Step Trials= 20
Max Error Tol= 0.3
Flow Tol Ratio= 0.001
Split Flow NTrial= 30
Split Flow Tol= 0.02
Split Flow Ratio= 0.02
Log Output Level= 0
Friction Slope Method= 1
Unsteady Friction Slope Method= 2
Unsteady Bridges Friction Slope Method= 1
Parabolic Critical Depth
Global Vel Dist=  1 , 1 , 1
Global Log Level= 0
CheckData=True
Encroach Param= -1, 0, 0, 0
BEGIN DESCRIPTION:
Multiple Run
END DESCRIPTION:

--- Stream0672.f01 (steady flow) ---

Flow Title=Multiple
Number of Profiles=7
Profile Names=10-year,25-year,50-year,1pct_min,100-year,1pct_plu,500-year
River Rch & RM= Stream0672,Reach-1,16598
     637    1027    1379     896    1788    3568    2980
River Rch & RM= Stream0672,Reach-1,14080
     885    1446    1956    1279    2552    5092    4309
River Rch & RM= Stream0672,Reach-1,2333
     882    1437    1942    1268    2530    5047    4258
Boundary for River Rch & Prof#=Stream0672,Reach-1,1
Up Type=0
Dn Type=3
Dn Slope=0.005
Boundary for River Rch & Prof#=Stream0672,Reach-1,2
Up Type=0
Dn Type=3
Dn Slope=0.005
Boundary for River Rch & Prof#=Stream0672,Reach-1,3
Up Type=0
Dn Type=3
Dn Slope=0.005
Boundary for River Rch & Prof#=Stream0672,Reach-1,4
Up Type=0
Dn Type=3
Dn Slope=0.005
Boundary for River Rch & Prof#=Stream0672,Reach-1,5
Up Type=0
Dn Type=3
Dn Slope=0.005
Boundary for River Rch & Prof#=Stream0672,Reach-1,6
Up Type=0
Dn Type=3
Dn Slope=0.005
Boundary for River Rch & Prof#=Stream0672,Reach-1,7
Up Type=0
Dn Type=3
Dn Slope=0.005

--- Stream0672.g01 (geometry) ---

Geom Title=Existing Conditions

River Reach=Stream0672,Reach-1
Reach XY= 30
      2402525.00     13621175.00      2403073.43     13621681.09
      2402828.44     13621826.22      2402861.76     13622161.41
      2403517.50     13622018.29      2403427.94     13622373.24
      2404069.59     13623122.58      2404044.76     13623546.03
      2404378.02     13623530.46      2404424.87     13623767.68
      2404831.39     13623632.34      2404944.78     13624445.18
      2405231.65     13624283.97      2405461.59     13624761.50
      2405668.89     13624676.79      2406019.61     13624922.56
      2405725.55     13625385.64      2405869.63     13625627.92
      2405576.56     13625781.09      2405775.46     13625954.75
      2405582.58     13626328.32      2406021.47     13626926.28
      2406082.34     13627731.33      2406742.21     13627891.21
      2406975.22     13628295.06      2406782.45     13628531.03
      2407370.01     13628872.45      2407232.67     13629481.52
      2407866.12     13629768.47      2407475.00     13630075.00

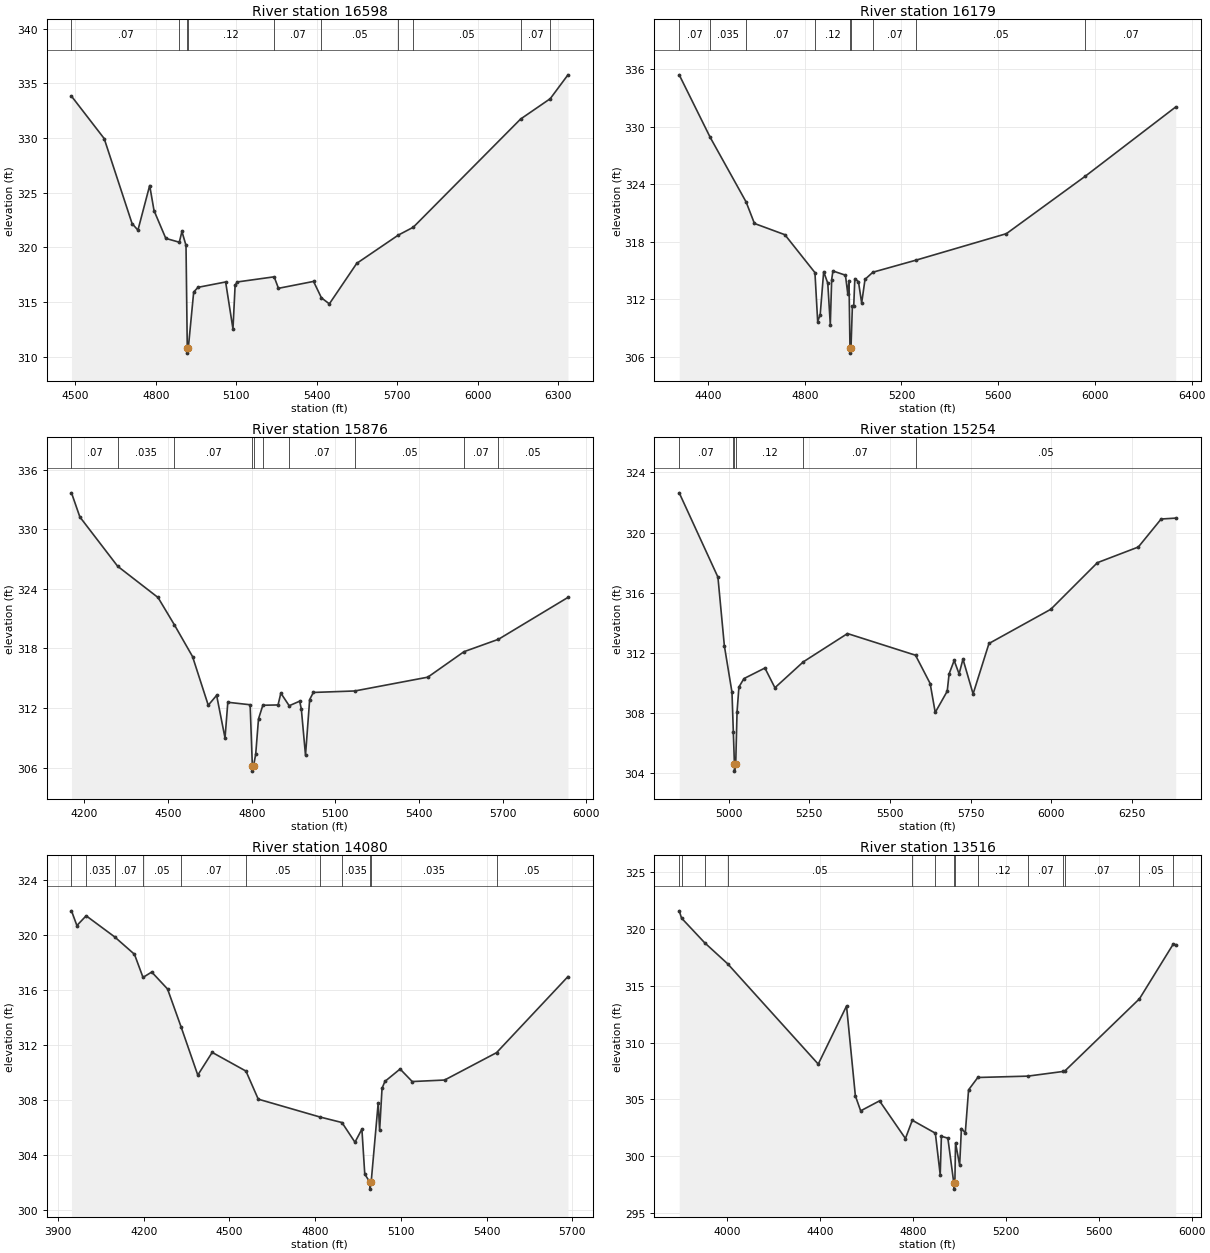
Type RM Length L Ch R = 1,16598,419,419,419
BEGIN DESCRIPTION:
XS7447
END DESCRIPTION:
XS GIS Cut Line= 3
      2402089.03     13621435.65      2402554.32     13621185.65
      2403700.08     13620525.97
#Sta/Elev= 30
  4485.6  333.82  4607.4  329.95  4711.3  322.19  4733.2  321.58  4777.0  325.66
  4793.3  323.36  4837.1  320.83  4887.4  320.48  4897.2  321.46  4912.4  320.19
  4917.1  310.85  4917.3  310.35  4921.1  310.85  4941.0  315.93  4957.2  316.36
  5060.1  316.85  5087.4  312.56  5095.4  316.54  5103.2  316.85  5240.9  317.32
  5256.9  316.27  5387.7  316.90  5417.1  315.40  5446.6  314.85  5548.7  318.55
  5703.5  321.13  5759.4  321.85  6159.3  331.73  6269.8  333.59  6335.9  335.77
#Mann=10,-1,0
  4485.6    0.07       0  4887.4    0.12       0  4917.1    0.05       0
  4921.1    0.12       0  5240.9    0.07       0  5417.1    0.05       0
  5703.5    0.07       0  5759.4    0.05       0  6159.3    0.07       0
  6269.8    0.12       0
Bank Sta=4917.1,4921.1
Exp/Cntr=0.3,0.1

Type RM Length L Ch R = 1,16179,303,303,303
BEGIN DESCRIPTION:
Stream0672 23.0
END DESCRIPTION:
XS GIS Cut Line= 3
      2402186.22     13621630.10      2402875.00     13621425.00
      2403990.88     13620693.20
#Sta/Elev= 30
  4281.1  335.40  4409.3  328.88  4557.8  322.15  4592.2  319.91  4718.0  318.74
  4842.4  314.79  4853.7  309.69  4864.1  310.41  4878.5  314.89  4895.4  313.69
  4905.9  309.36  4911.6  314.07  4916.8  314.96  4968.5  314.52  4978.0  312.61
  4983.2  313.96  4987.3  306.90  4987.5  306.40  4991.4  306.90  4997.2  311.29
  5002.8  311.29  5007.3  314.16  5022.4  313.84  5035.6  311.62  5049.5  314.09
  5081.9  314.83  5261.9  316.10  5634.2  318.85  5959.5  324.82  6334.2  332.05
#Mann=9,-1,0
  4281.1    0.07       0  4409.3   0.035       0  4557.8    0.07       0
  4842.4    0.12       0  4987.3    0.05       0  4991.4    0.12       0
  5081.9    0.07       0  5261.9    0.05       0  5959.5    0.07       0
Bank Sta=4987.3,4991.4
Exp/Cntr=0.3,0.1

Type RM Length L Ch R = 1,15876,622,622,622
BEGIN DESCRIPTION:
Stream0672 22.0
END DESCRIPTION:
XS GIS Cut Line= 3
      2402224.97     13621725.00      2402998.76     13621698.15
      2403824.98     13621125.01
#Sta/Elev= 30
  4154.0  333.69  4184.0  331.26  4319.5  326.29  4464.2  323.14  4523.0  320.38
  4587.9  317.19  4644.3  312.28  4674.3  313.28  4704.4  308.98  4714.4  312.58
  4794.4  312.33  4802.4  306.14  4802.6  305.64  4806.5  306.14  4814.4  307.35
  4824.4  310.90  4840.0  312.28  4894.5  312.31  4904.5  313.50  4934.4  312.23
  4972.0  312.69  4978.0  311.89  4992.9  307.24  5007.8  312.85  5021.0  313.57
  5169.8  313.72  5431.3  315.11  5561.2  317.68  5684.7  318.93  5933.8  323.15
#Mann=10,-1,0
  4154.0    0.07       0  4319.5   0.035       0  4523.0    0.07       0
  4802.4    0.05       0  4806.5    0.07       0  4840.0    0.12       0
  4934.4    0.07       0  5169.8    0.05       0  5561.2    0.07       0
  5684.7    0.05       0
Bank Sta=4802.4,4806.5
Exp/Cntr=0.3,0.1

Type RM Length L Ch R = 1,15254,1174,1174,1174
BEGIN DESCRIPTION:
Stream0672 21.0
END DESCRIPTION:
XS GIS Cut Line= 3
      2402625.05     13622075.00      2402775.00     13622075.00
      2403975.00     13621375.00
#Sta/Elev= 30
  4846.5  322.64  4966.5  317.04  4986.5  312.47  5010.1  309.39  5014.3  306.74
  5017.6  304.65  5017.8  304.15  5021.7  304.65  5025.8  308.08  5031.6  309.74
  5047.3  310.30  5112.2  311.00  5143.2  309.69  5231.2  311.41  5368.2  313.29
  5579.1  311.85  5624.5  309.97  5640.2  308.05  5677.4  309.46  5683.2  310.61
  5698.9  311.50  5714.2  310.61  5726.2  311.59  5757.6  309.28  5806.8  312.63
  5998.3  314.90  6143.0  318.00  6269.9  319.04  6340.6  320.90  6385.7  320.96
#Mann=6,-1,0
  4846.5    0.07       0  5014.3    0.12       0  5017.6    0.05       0
  5021.7    0.12       0  5231.2    0.07       0  5579.1    0.05       0
Bank Sta=5017.6,5021.7
Exp/Cntr=0.3,0.1

Type RM Length L Ch R = 1,14080,564,564,564
BEGIN DESCRIPTION:
Stream0672 20.0
END DESCRIPTION:
XS GIS Cut Line= 3
      2402436.27     13622350.92      2403568.21     13622212.04
      2403975.01     13621774.99
#Sta/Elev= 30
  3947.4  321.77  3966.3  320.70  3998.7  321.41  4098.2  319.88  4167.8  318.61
  4197.7  316.93  4228.2  317.32  4283.5  316.09  4331.0  313.33  4389.4  309.83
  4439.8  311.48  4558.0  310.12  4601.0  308.08  4815.7  306.79  4894.0  306.38
  4939.4  304.95  4963.7  305.90  4973.8  302.63  4991.8  302.04  4992.1  301.54
  4996.1  302.04  5020.8  307.82  5025.8  305.83  5034.2  308.87  5044.3  309.37
  5097.4  310.27  5139.9  309.36  5253.2  309.47  5435.0  311.46  5684.9  316.99
#Mann=11,-1,0
  3947.4    0.05       0  3998.7   0.035       0  4098.2    0.07       0
  4197.7    0.05       0  4331.0    0.07       0  4558.0    0.05       0
  4815.7    0.07       0  4894.0   0.035       0  4991.8    0.05       0
  4996.1   0.035       0  5435.0    0.05       0
Bank Sta=4991.8,4996.1
Exp/Cntr=0.3,0.1

Type RM Length L Ch R = 1,13516,451,451,451
BEGIN DESCRIPTION:
Stream0672 19.0
END DESCRIPTION:
XS GIS Cut Line= 3
      2402474.99     13622425.00      2403675.00     13622625.00
      2404325.00     13621975.00
#Sta/Elev= 30
  3795.6  321.61  3805.6  320.97  3904.9  318.80  4004.1  316.94  4393.7  308.10
  4515.4  313.22  4553.4  305.30  4576.2  303.98  4657.3  304.86  4768.8  301.54
  4798.3  303.15  4897.5  302.01  4918.4  298.34  4923.5  301.74  4951.3  301.57
  4977.1  297.58  4977.3  297.08  4981.4  297.58  4984.3  301.16  5002.0  299.19
  5009.6  302.42  5026.3  302.04  5040.4  305.83  5080.1  306.92  5295.4  307.04
  5446.6  307.45  5453.8  307.48  5775.7  313.86  5920.0  318.65  5931.4  318.63
#Mann=14,-1,0
  3795.6    0.05       0  3805.6    0.07       0  3904.9   0.035       0
  4004.1    0.05       0  4798.3   0.035       0  4897.5     0.1       0
  4977.1    0.05       0  4981.4     0.1       0  5080.1    0.12       0
  5295.4    0.07       0  5446.6    0.12       0  5453.8    0.07       0
  5775.7    0.05       0  5920.0    0.07       0
Bank Sta=4977.1,4981.4
Exp/Cntr=0.3,0.1

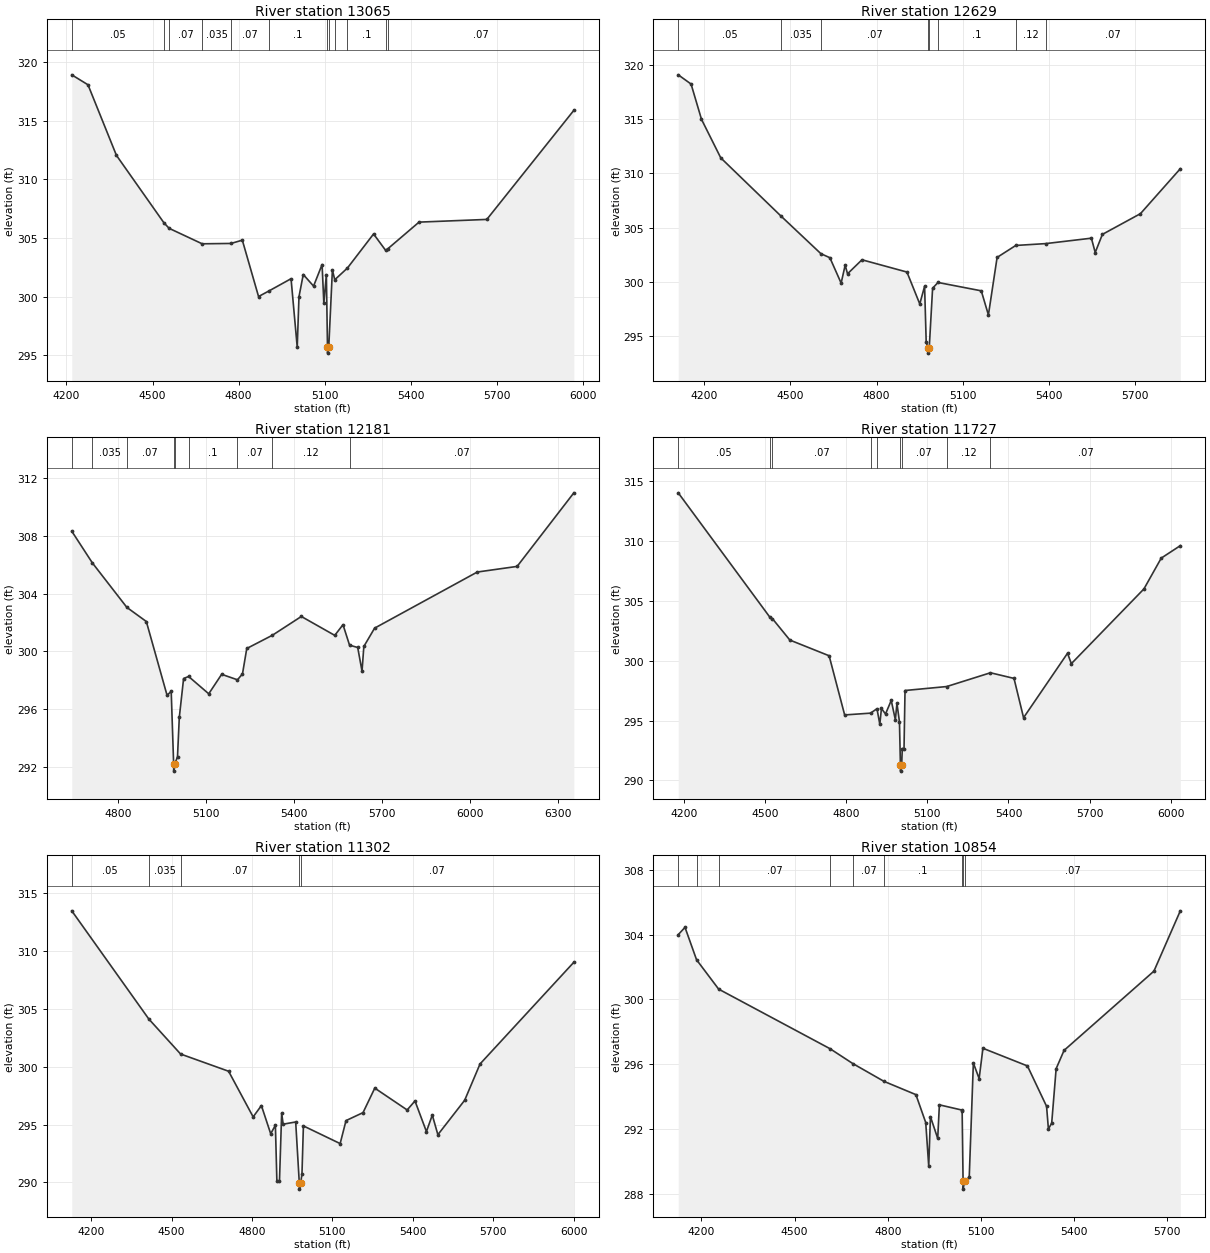
Type RM Length L Ch R = 1,13065,436,436,436
BEGIN DESCRIPTION:
Stream0672 18.0
END DESCRIPTION:
XS GIS Cut Line= 3
      2403225.01     13623474.99      2403775.00     13622925.00
      2404324.99     13622125.02
#Sta/Elev= 30
  4218.7  318.93  4275.2  318.08  4374.2  312.06  4539.4  306.31  4557.8  305.83
  4672.8  304.51  4773.2  304.54  4812.7  304.82  4869.2  300.01  4904.2  300.47
  4982.4  301.53  5003.9  295.69  5010.0  299.99  5024.9  301.89  5060.8  300.90
  5090.5  302.74  5096.6  299.43  5105.4  301.88  5109.3  295.68  5109.6  295.18
  5113.7  295.68  5126.4  302.28  5134.6  301.44  5178.7  302.44  5269.8  305.35
  5312.1  303.94  5320.1  304.10  5428.1  306.36  5664.2  306.59  5967.3  315.90
#Mann=12,-1,0
  4218.7    0.05       0  4539.4   0.035       0  4557.8    0.07       0
  4672.8   0.035       0  4773.2    0.07       0  4904.2     0.1       0
  5109.3    0.05       0  5113.7     0.1       0  5134.6    0.12       0
  5178.7     0.1       0  5312.1    0.12       0  5320.1    0.07       0
Bank Sta=5109.3,5113.7
Exp/Cntr=0.3,0.1

Type RM Length L Ch R = 1,12629,448,448,448
BEGIN DESCRIPTION:
Stream0672 17.0
END DESCRIPTION:
XS GIS Cut Line= 3
      2403275.02     13623524.99      2404075.00     13623125.00
      2404375.00     13622325.00
#Sta/Elev= 30
  4109.4  319.08  4154.1  318.23  4190.4  314.98  4257.5  311.43  4466.8  306.08
  4606.4  302.60  4637.6  302.23  4676.8  299.89  4690.8  301.54  4699.1  300.75
  4749.4  302.04  4906.0  300.91  4950.7  297.97  4967.5  299.60  4973.1  294.45
  4979.2  293.94  4979.5  293.44  4983.7  293.94  4995.4  299.42  5014.1  299.95
  5164.9  299.18  5189.8  296.96  5220.1  302.26  5285.1  303.36  5389.2  303.53
  5548.5  304.03  5561.8  302.71  5586.8  304.38  5719.4  306.29  5858.2  310.43
#Mann=8,-1,0
  4109.4    0.05       0  4466.8   0.035       0  4606.4    0.07       0
  4979.2    0.05       0  4983.7    0.07       0  5014.1     0.1       0
  5285.1    0.12       0  5389.2    0.07       0
Bank Sta=4979.2,4983.7
Exp/Cntr=0.3,0.1

Type RM Length L Ch R = 1,12181,454,454,454
BEGIN DESCRIPTION:
Stream0672 16.0
END DESCRIPTION:
XS GIS Cut Line= 3
      2403775.02     13623774.98      2404025.00     13623525.00
      2404825.02     13622424.98
#Sta/Elev= 30
  4641.4  308.32  4711.8  306.12  4829.4  303.04  4895.9  302.06  4966.6  296.95
  4980.8  297.22  4989.1  292.19  4989.4  291.69  4993.6  292.19  5002.3  292.70
  5008.4  295.41  5023.1  298.11  5040.2  298.25  5108.9  297.05  5153.0  298.40
  5207.0  298.02  5224.1  298.43  5238.7  300.19  5326.3  301.11  5425.0  302.41
  5539.0  301.10  5567.2  301.84  5589.5  300.42  5617.4  300.26  5632.1  298.62
  5638.3  300.33  5675.0  301.60  6025.5  305.49  6161.5  305.88  6355.1  310.98
#Mann=9,-1,0
  4641.4    0.05       0  4711.8   0.035       0  4829.4    0.07       0
  4989.1    0.05       0  4993.6    0.07       0  5040.2     0.1       0
  5207.0    0.07       0  5326.3    0.12       0  5589.5    0.07       0
Bank Sta=4989.1,4993.6
Exp/Cntr=0.3,0.1

Type RM Length L Ch R = 1,11727,425,425,425
BEGIN DESCRIPTION:
Stream0672 15.0
END DESCRIPTION:
XS GIS Cut Line= 3
      2403724.97     13624025.02      2404425.00     13623575.00
      2405174.99     13622875.01
#Sta/Elev= 30
  4177.9  314.01  4516.3  303.65  4526.7  303.50  4591.0  301.72  4736.3  300.41
  4793.8  295.47  4889.6  295.62  4913.4  295.99  4923.9  294.69  4929.9  296.01
  4945.0  295.55  4966.2  296.68  4981.4  295.07  4987.3  296.44  4996.6  294.89
  5000.2  291.28  5000.6  290.78  5004.8  291.28  5007.1  292.66  5013.5  292.66
  5017.2  297.51  5171.5  297.84  5333.4  298.99  5420.5  298.52  5455.9  295.24
  5618.6  300.62  5632.7  299.75  5901.4  305.99  5965.4  308.56  6036.0  309.60
#Mann=9,-1,0
  4177.9    0.05       0  4516.3   0.035       0  4526.7    0.07       0
  4889.6     0.1       0  4913.4    0.07       0  5000.2    0.05       0
  5004.8    0.07       0  5171.5    0.12       0  5333.4    0.07       0
Bank Sta=5000.2,5004.8
Exp/Cntr=0.3,0.1

Type RM Length L Ch R = 1,11302,448,448,448
BEGIN DESCRIPTION:
Stream0672 14.0
END DESCRIPTION:
XS GIS Cut Line= 3
      2403775.03     13624074.99      2404575.00     13623725.00
      2405175.01     13622924.98
#Sta/Elev= 30
  4127.6  313.50  4415.0  304.14  4533.6  301.11  4712.7  299.62  4804.3  295.67
  4835.1  296.65  4869.8  294.21  4887.3  294.95  4892.8  290.16  4902.5  290.10
  4910.7  296.00  4916.2  295.04  4963.0  295.23  4976.6  289.92  4977.0  289.42
  4981.2  289.92  4986.4  290.70  4991.8  294.89  5128.9  293.36  5150.8  295.35
  5214.3  296.04  5258.1  298.16  5378.9  296.27  5408.1  297.05  5450.8  294.40
  5472.7  295.83  5493.5  294.13  5593.5  297.11  5650.8  300.25  6000.8  309.05
#Mann=5,-1,0
  4127.6    0.05       0  4415.0   0.035       0  4533.6    0.07       0
  4976.6    0.05       0  4981.2    0.07       0
Bank Sta=4976.6,4981.2
Exp/Cntr=0.3,0.1

Type RM Length L Ch R = 1,10854,471,471,471
BEGIN DESCRIPTION:
Stream0672 13.0
END DESCRIPTION:
XS GIS Cut Line= 3
      2404075.01     13624124.99      2404875.00     13623775.00
      2405125.00     13623075.00
#Sta/Elev= 30
  4125.4  304.00  4147.2  304.45  4184.4  302.45  4255.5  300.64  4614.4  296.96
  4687.2  296.05  4787.7  294.95  4890.6  294.13  4922.2  292.41  4931.9  289.72
  4937.4  292.77  4960.8  291.43  4966.2  293.50  5038.3  293.18  5039.5  293.09
  5042.5  288.80  5042.8  288.30  5047.1  288.80  5062.3  289.03  5075.6  296.08
  5094.2  295.12  5106.4  296.99  5249.7  295.90  5311.3  293.41  5317.2  292.01
  5327.8  292.37  5342.1  295.73  5367.6  296.86  5657.0  301.75  5741.9  305.47
#Mann=9,-1,0
  4125.4    0.05       0  4184.4   0.035       0  4255.5    0.07       0
  4614.4    0.12       0  4687.2    0.07       0  4787.7     0.1       0
  5038.3    0.07       0  5042.5    0.05       0  5047.1    0.07       0
Bank Sta=5042.5,5047.1
Exp/Cntr=0.3,0.1

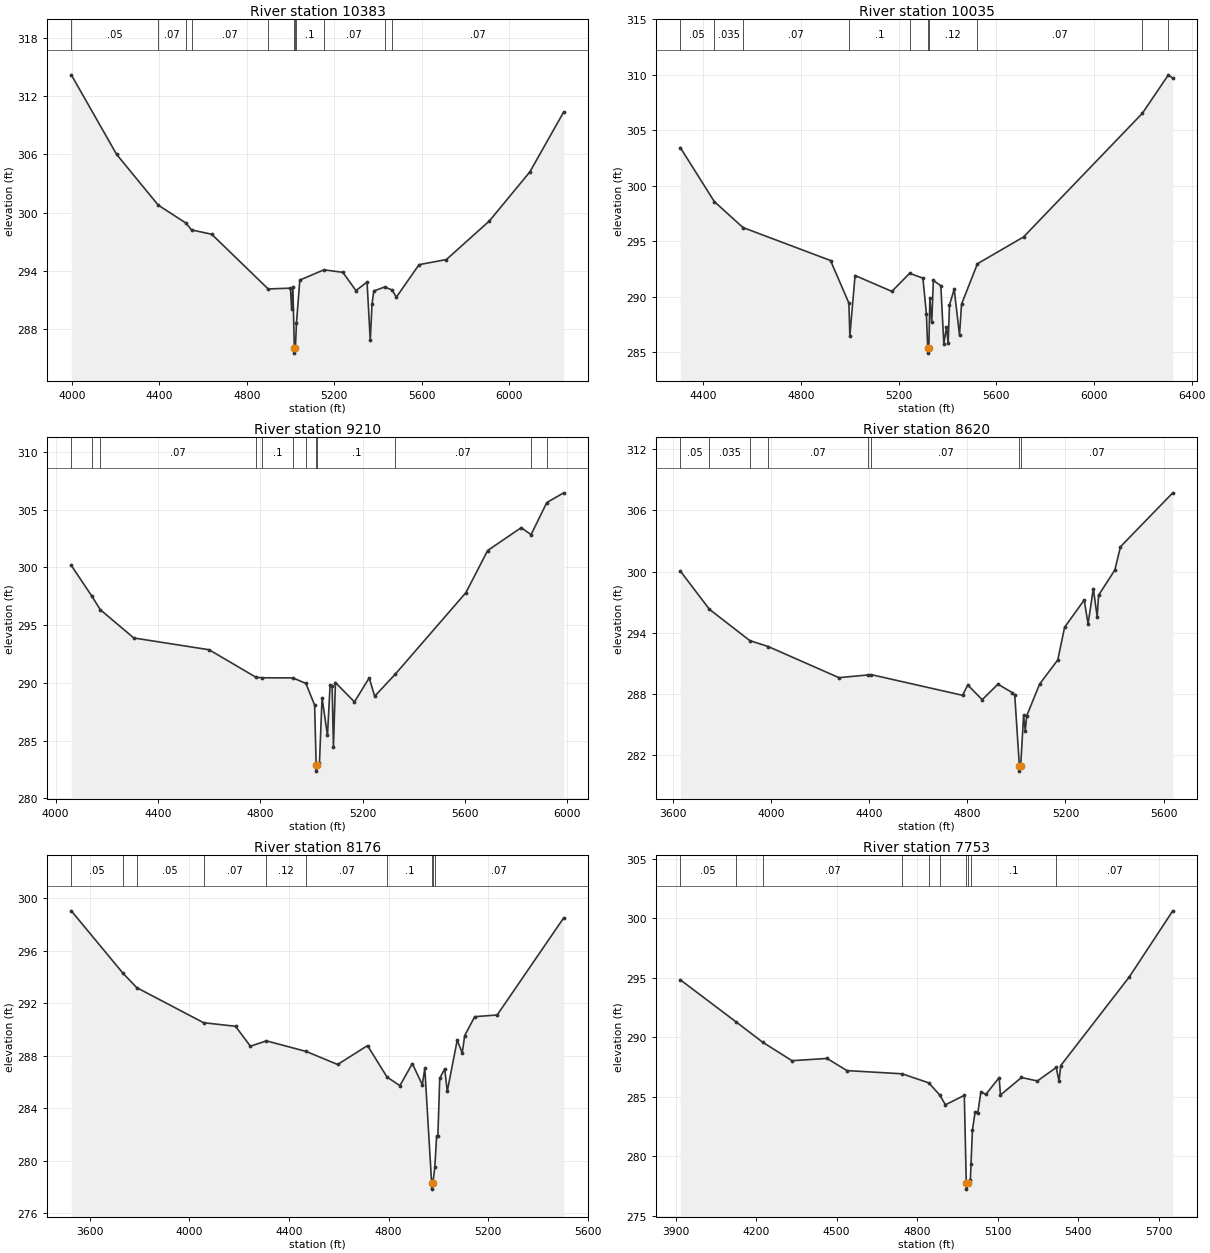
Type RM Length L Ch R = 1,10383,348,348,348
BEGIN DESCRIPTION:
Stream0672 12.0
END DESCRIPTION:
XS GIS Cut Line= 3
      2403975.02     13624774.98      2404775.00     13624175.00
      2405875.03     13623574.99
#Sta/Elev= 30
  3996.5  314.19  4203.8  306.00  4394.4  300.77  4520.1  298.94  4546.7  298.22
  4639.2  297.77  4897.2  292.14  4999.3  292.22  5004.5  290.08  5010.2  292.32
  5017.0  286.03  5017.3  285.53  5021.6  286.03  5026.8  288.65  5042.0  293.05
  5152.2  294.11  5239.0  293.85  5298.8  291.97  5349.6  292.85  5364.3  286.85
  5372.4  290.58  5380.4  291.93  5430.1  292.34  5463.5  292.04  5483.9  291.30
  5587.4  294.64  5712.7  295.17  5909.2  299.14  6094.3  304.19  6249.5  310.37
#Mann=11,-1,0
  3996.5    0.05       0  4394.4    0.07       0  4520.1   0.035       0
  4546.7    0.07       0  4897.2     0.1       0  5017.0    0.05       0
  5021.6     0.1       0  5026.8     0.1       0  5152.2    0.07       0
  5430.1    0.12       0  5463.5    0.07       0
Bank Sta=5017,5021.6
Exp/Cntr=0.3,0.1

Type RM Length L Ch R = 1,10035,825,825,825
BEGIN DESCRIPTION:
XS7446
END DESCRIPTION:
XS GIS Cut Line= 4
      2404365.32     13624821.61      2405001.04     13624431.59
      2405207.76     13624193.67      2406100.51     13623850.61
#Sta/Elev= 30
  4305.2  303.44  4444.4  298.58  4561.9  296.24  4920.5  293.27  4995.8  289.44
  4999.8  286.50  5021.1  291.92  5171.9  290.49  5244.7  292.12  5299.1  291.68
  5313.4  288.45  5318.6  285.43  5319.0  284.93  5323.3  285.43  5327.6  289.85
  5335.2  287.70  5341.9  291.48  5372.5  291.00  5384.7  285.77  5395.4  287.25
  5402.5  285.85  5407.9  289.26  5427.2  290.68  5449.0  286.55  5457.2  289.34
  5522.5  292.98  5711.2  295.39  6198.2  306.53  6304.8  309.99  6322.6  309.68
#Mann=10,-1,0
  4305.2    0.05       0  4444.4   0.035       0  4561.9    0.07       0
  4995.8     0.1       0  5244.7    0.12       0  5318.6    0.05       0
  5323.3    0.12       0  5522.5    0.07       0  6198.2   0.035       0
  6304.8    0.07       0
Bank Sta=5318.6,5323.3
Exp/Cntr=0.3,0.1

Type RM Length L Ch R = 1,9210,590,590,590
BEGIN DESCRIPTION:
XS7445
END DESCRIPTION:
XS GIS Cut Line= 3
      2404470.63     13624864.51      2405519.78     13624572.00
      2406229.62     13624131.27
#Sta/Elev= 30
  4061.5  300.18  4142.3  297.50  4174.9  296.34  4305.9  293.89  4600.1  292.87
  4783.7  290.48  4807.1  290.44  4928.0  290.43  4978.5  289.95  5012.6  288.07
  5018.5  282.85  5018.9  282.35  5023.7  282.85  5031.5  283.08  5041.6  288.71
  5062.7  285.45  5073.0  289.80  5080.9  289.74  5086.1  284.41  5093.8  290.03
  5168.1  288.35  5225.9  290.43  5247.2  288.84  5327.2  290.74  5603.8  297.82
  5688.8  301.47  5819.9  303.45  5858.5  302.85  5920.0  305.63  5986.2  306.47
#Mann=12,-1,0
  4061.5    0.05       0  4142.3   0.035       0  4174.9    0.07       0
  4783.7    0.12       0  4807.1     0.1       0  4928.0    0.07       0
  4978.5     0.1       0  5018.5    0.05       0  5023.7     0.1       0
  5327.2    0.07       0  5858.5   0.035       0  5920.0    0.07       0
Bank Sta=5018.5,5023.7
Exp/Cntr=0.3,0.1

Type RM Length L Ch R = 1,8620,444,444,444
BEGIN DESCRIPTION:
XS7444
END DESCRIPTION:
XS GIS Cut Line= 3
      2404490.07     13625020.54      2405531.48     13624923.02
      2406358.38     13624435.47
#Sta/Elev= 30
  3631.3  300.07  3749.8  296.32  3914.5  293.25  3989.2  292.67  4277.3  289.62
  4394.6  289.88  4409.9  289.91  4780.8  287.89  4802.3  288.90  4860.9  287.46
  4925.2  288.98  4983.8  288.15  4993.6  287.91  5012.4  280.96  5012.9  280.46
  5017.7  280.96  5029.6  285.95  5036.5  284.44  5042.3  285.88  5095.1  289.00
  5168.9  291.36  5196.5  294.55  5276.5  297.23  5292.2  294.88  5313.6  298.34
  5329.3  295.60  5335.1  297.70  5401.1  300.16  5424.3  302.45  5637.2  307.73
#Mann=8,-1,0
  3631.3    0.05       0  3749.8   0.035       0  3914.5    0.05       0
  3989.2    0.07       0  4394.6    0.12       0  4409.9    0.07       0
  5012.4    0.05       0  5017.7    0.07       0
Bank Sta=5012.4,5017.7
Exp/Cntr=0.3,0.1

Type RM Length L Ch R = 1,8176,423,423,423
BEGIN DESCRIPTION:
Stream0672 11.0
END DESCRIPTION:
XS GIS Cut Line= 3
      2404505.75     13625121.94      2405975.00     13625075.00
      2406481.60     13625114.02
#Sta/Elev= 30
  3525.5  299.04  3733.5  294.28  3788.5  293.19  4057.0  290.52  4185.1  290.25
  4245.1  288.73  4309.1  289.14  4469.5  288.33  4595.3  287.34  4715.4  288.78
  4793.9  286.38  4845.4  285.73  4895.4  287.41  4935.5  285.79  4945.5  287.05
  4972.8  278.35  4973.2  277.85  4978.1  278.35  4985.8  279.51  4993.0  281.90
  4998.0  281.90  5005.5  286.29  5025.6  287.01  5035.6  285.29  5075.7  289.19
  5095.8  288.22  5105.8  289.54  5145.9  290.98  5236.2  291.11  5503.6  298.51
#Mann=10,-1,0
  3525.5    0.05       0  3733.5   0.035       0  3788.5    0.05       0
  4057.0    0.07       0  4309.1    0.12       0  4469.5    0.07       0
  4793.9     0.1       0  4972.8    0.05       0  4978.1     0.1       0
  4985.8    0.07       0
Bank Sta=4972.8,4978.1
Exp/Cntr=0.3,0.1

Type RM Length L Ch R = 1,7753,761,761,761
BEGIN DESCRIPTION:
Stream0672 10.0
END DESCRIPTION:
XS GIS Cut Line= 3
      2404649.99     13625457.37      2405725.00     13625375.00
      2406475.00     13625275.00
#Sta/Elev= 30
  3917.6  294.82  4125.8  291.28  4224.6  289.58  4333.8  288.03  4464.2  288.22
  4538.5  287.20  4744.1  286.93  4843.4  286.17  4883.8  285.16  4905.5  284.33
  4975.7  285.12  4983.1  277.75  4983.5  277.25  4988.4  277.75  4998.3  278.02
  5000.7  279.34  5005.9  282.20  5015.9  283.71  5026.0  283.65  5037.4  285.40
  5056.3  285.21  5105.5  286.61  5110.5  285.15  5188.7  286.62  5248.0  286.33
  5318.1  287.46  5328.7  286.32  5335.0  287.62  5591.0  295.08  5752.4  300.61
#Mann=10,-1,0
  3917.6    0.05       0  4125.8   0.035       0  4224.6    0.07       0
  4744.1    0.12       0  4843.4     0.1       0  4883.8    0.12       0
  4983.1    0.05       0  4988.4    0.12       0  5000.7     0.1       0
  5318.1    0.07       0
Bank Sta=4983.1,4988.4
Exp/Cntr=0.3,0.1

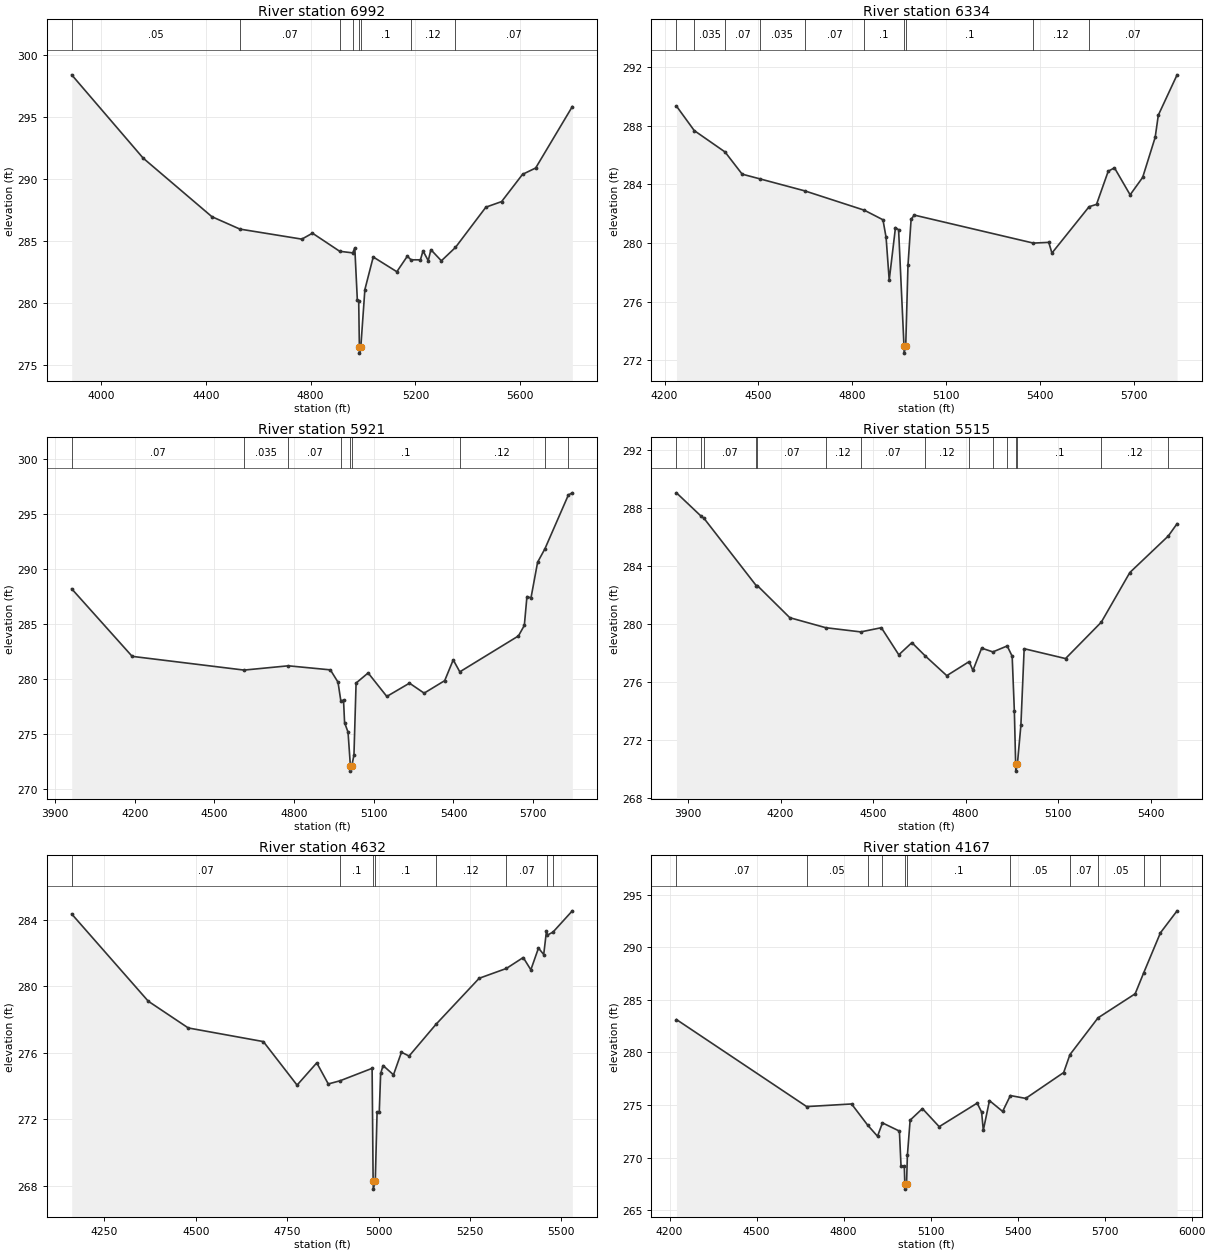
Type RM Length L Ch R = 1,6992,658,658,658
BEGIN DESCRIPTION:
Stream0672 9.0
END DESCRIPTION:
XS GIS Cut Line= 3
      2404475.04     13625974.99      2405586.09     13625816.19
      2406375.00     13625825.00
#Sta/Elev= 30
  3887.7  298.44  4160.4  291.72  4423.0  286.99  4529.9  285.99  4766.3  285.18
  4806.9  285.66  4910.8  284.20  4960.5  284.07  4968.5  284.47  4978.3  280.23
  4983.4  280.21  4986.0  276.48  4986.4  275.98  4991.5  276.48  5007.0  281.11
  5038.9  283.74  5129.0  282.55  5169.0  283.80  5183.4  283.51  5219.0  283.51
  5229.0  284.23  5249.0  283.44  5259.0  284.33  5299.0  283.43  5352.8  284.51
  5469.0  287.76  5529.0  288.21  5609.0  290.41  5659.0  290.92  5799.0  295.88
#Mann=8,-1,0
  3887.7    0.05       0  4529.9    0.07       0  4910.8    0.12       0
  4960.5     0.1       0  4986.0    0.05       0  4991.5     0.1       0
  5183.4    0.12       0  5352.8    0.07       0
Bank Sta=4986,4991.5
Exp/Cntr=0.3,0.1

Type RM Length L Ch R = 1,6334,413,413,413
BEGIN DESCRIPTION:
Stream0672 8.0
END DESCRIPTION:
XS GIS Cut Line= 3
      2404874.98     13626275.00      2405738.20     13626260.82
      2406475.03     13626275.00
#Sta/Elev= 30
  4238.1  289.34  4295.0  287.67  4393.5  286.21  4448.1  284.70  4504.6  284.38
  4648.3  283.56  4838.9  282.24  4898.2  281.59  4908.2  280.39  4918.2  277.47
  4938.2  281.06  4948.2  280.91  4965.4  273.00  4965.9  272.50  4971.0  273.00
  4978.2  278.49  4988.2  281.62  4998.2  281.91  5379.0  280.00  5428.3  280.05
  5438.3  279.32  5557.1  282.48  5580.9  282.64  5618.3  284.90  5638.3  285.13
  5688.3  283.29  5728.4  284.48  5768.4  287.21  5778.4  288.72  5838.4  291.47
#Mann=10,-1,0
  4238.1    0.07       0  4295.0   0.035       0  4393.5    0.07       0
  4504.6   0.035       0  4648.3    0.07       0  4838.9     0.1       0
  4965.4    0.05       0  4971.0     0.1       0  5379.0    0.12       0
  5557.1    0.07       0
Bank Sta=4965.4,4971
Exp/Cntr=0.3,0.1

Type RM Length L Ch R = 1,5921,406,406,406
BEGIN DESCRIPTION:
Stream0672 7.0
END DESCRIPTION:
XS GIS Cut Line= 3
      2404974.97     13627225.02      2405775.00     13626575.00
      2406574.99     13626275.00
#Sta/Elev= 30
  3962.4  288.19  4190.1  282.04  4611.5  280.79  4778.1  281.18  4936.5  280.81
  4965.2  279.69  4976.0  277.97  4986.0  278.06  4990.0  276.00  5003.0  275.14
  5011.8  272.09  5012.2  271.59  5017.4  272.09  5025.3  273.07  5033.3  279.61
  5078.7  280.53  5149.0  278.39  5234.4  279.60  5289.6  278.69  5367.0  279.83
  5399.1  281.72  5423.9  280.63  5644.7  283.90  5666.9  284.86  5676.7  287.49
  5691.9  287.36  5716.8  290.61  5744.3  291.83  5832.8  296.74  5847.6  296.93
#Mann=9,-1,0
  3962.4    0.07       0  4611.5   0.035       0  4778.1    0.07       0
  4976.0     0.1       0  5011.8    0.05       0  5017.4     0.1       0
  5423.9    0.12       0  5744.3    0.07       0  5832.8    0.12       0
Bank Sta=5011.8,5017.4
Exp/Cntr=0.3,0.1

Type RM Length L Ch R = 1,5515,883,883,883
BEGIN DESCRIPTION:
Stream0672 6.0
END DESCRIPTION:
XS GIS Cut Line= 3
      2405125.03     13627674.97      2405925.00     13626875.00
      2406375.02     13626674.99
#Sta/Elev= 30
  3862.4  289.05  3940.8  287.47  3952.1  287.28  4121.0  282.65  4124.6  282.65
  4230.1  280.43  4346.7  279.74  4460.2  279.45  4527.0  279.74  4583.6  277.87
  4626.0  278.71  4668.5  277.81  4739.2  276.43  4811.8  277.40  4824.0  276.79
  4852.3  278.33  4888.7  278.07  4935.2  278.48  4951.3  277.77  4958.4  273.99
  4962.6  270.34  4963.1  269.84  4968.3  270.34  4979.6  273.01  4990.2  278.29
  5124.4  277.61  5240.3  280.12  5333.0  283.55  5457.7  286.07  5486.2  286.92
#Mann=15,-1,0
  3862.4    0.07       0  3940.8   0.035       0  3952.1    0.07       0
  4121.0   0.035       0  4124.6    0.07       0  4346.7    0.12       0
  4460.2    0.07       0  4668.5    0.12       0  4811.8     0.1       0
  4888.7    0.07       0  4935.2     0.1       0  4962.6    0.05       0
  4968.3     0.1       0  5240.3    0.12       0  5457.7    0.07       0
Bank Sta=4962.6,4968.3
Exp/Cntr=0.3,0.1

Type RM Length L Ch R = 1,4632,465,465,465
BEGIN DESCRIPTION:
Stream0672 5.0
END DESCRIPTION:
XS GIS Cut Line= 3
      2405375.00     13627775.00      2406175.00     13627525.00
      2406525.03     13627124.97
#Sta/Elev= 30
  4160.3  284.36  4369.8  279.11  4479.3  277.50  4684.7  276.68  4776.9  274.06
  4830.8  275.40  4862.3  274.13  4894.3  274.32  4982.2  275.07  4985.0  268.30
  4985.5  267.80  4990.9  268.30  4995.8  272.44  5001.8  272.44  5005.6  274.76
  5012.2  275.24  5040.7  274.68  5062.5  276.04  5083.4  275.81  5156.6  277.71
  5275.1  280.49  5349.4  281.08  5395.7  281.74  5416.5  281.00  5437.4  282.31
  5451.7  281.92  5459.2  283.32  5461.8  283.09  5477.1  283.27  5530.0  284.55
#Mann=8,-1,0
  4160.3    0.07       0  4894.3     0.1       0  4985.0    0.05       0
  4990.9     0.1       0  5156.6    0.12       0  5349.4    0.07       0
  5461.8    0.05       0  5477.1   0.035       0
Bank Sta=4985,4990.9
Exp/Cntr=0.3,0.1

Type RM Length L Ch R = 1,4167,598,598,598
BEGIN DESCRIPTION:
Stream0672 4.0
END DESCRIPTION:
XS GIS Cut Line= 3
      2405574.96     13628175.02      2406275.00     13627825.00
      2406775.02     13627024.97
#Sta/Elev= 30
  4223.7  283.13  4672.7  274.85  4827.5  275.10  4882.9  273.09  4916.9  272.03
  4934.0  273.30  4992.4  272.52  4998.0  269.19  5009.3  269.17  5011.1  267.50
  5011.6  267.00  5017.0  267.50  5019.9  270.20  5029.4  273.56  5071.8  274.66
  5129.6  272.94  5260.5  275.18  5275.8  274.33  5281.7  272.60  5302.9  275.42
  5348.3  274.39  5375.0  275.90  5427.9  275.63  5558.8  278.09  5580.3  279.79
  5677.2  283.29  5805.3  285.58  5834.8  287.58  5892.4  291.38  5949.8  293.47
#Mann=11,-1,0
  4223.7    0.07       0  4672.7    0.05       0  4882.9    0.07       0
  4934.0     0.1       0  5011.1    0.05       0  5017.0     0.1       0
  5375.0    0.05       0  5580.3    0.07       0  5677.2    0.05       0
  5834.8    0.07       0  5892.4   0.035       0
Bank Sta=5011.1,5017
Exp/Cntr=0.3,0.1

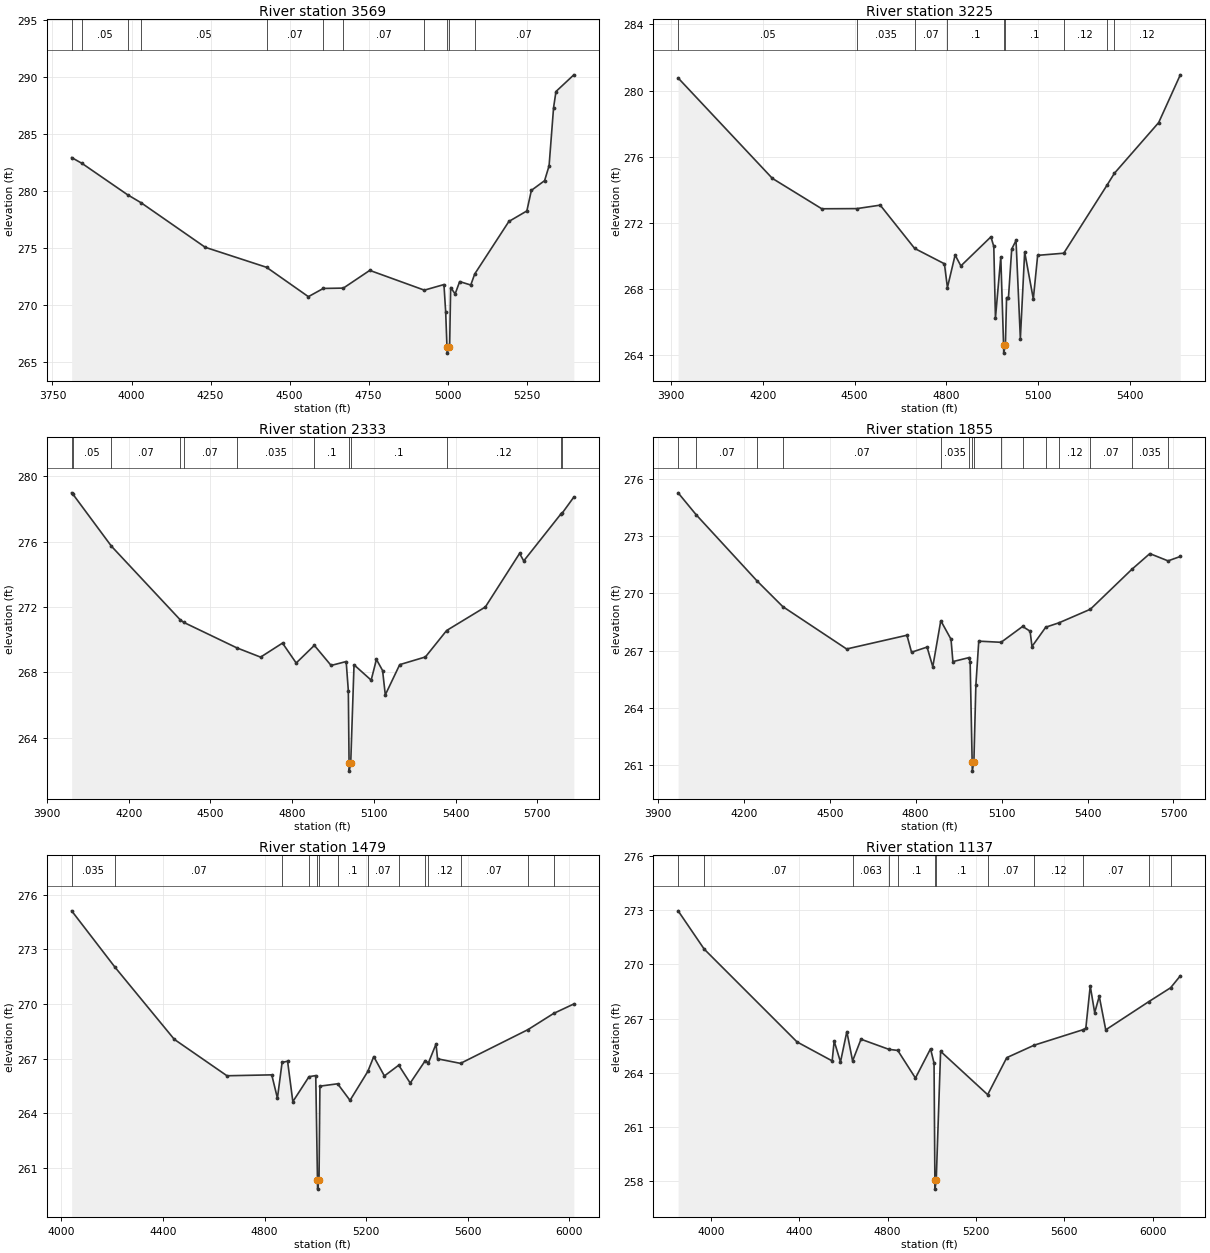
Type RM Length L Ch R = 1,3569,344,344,344
BEGIN DESCRIPTION:
Stream0672 3.0
END DESCRIPTION:
XS GIS Cut Line= 3
      2405695.27     13628437.19      2406779.57     13627934.04
      2407075.02     13627674.98
#Sta/Elev= 30
  3810.7  282.92  3843.5  282.41  3987.4  279.67  4030.2  278.97  4233.2  275.07
  4427.1  273.32  4559.4  270.75  4606.6  271.47  4670.1  271.50  4753.6  273.05
  4926.2  271.32  4988.2  271.81  4993.7  269.40  4997.8  266.31  4998.3  265.81
  5003.8  266.31  5006.1  266.31  5009.4  271.55  5023.6  270.99  5037.9  272.07
  5073.0  271.77  5085.6  272.74  5193.5  277.33  5250.4  278.25  5264.7  280.05
  5306.5  280.90  5320.7  282.20  5334.9  287.29  5342.5  288.70  5399.0  290.16
#Mann=11,-1,0
  3810.7   0.035       0  3843.5    0.05       0  3987.4    0.07       0
  4030.2    0.05       0  4427.1    0.07       0  4606.6   0.035       0
  4670.1    0.07       0  4926.2     0.1       0  4997.8    0.05       0
  5003.8     0.1       0  5085.6    0.07       0
Bank Sta=4997.8,5003.8
Exp/Cntr=0.3,0.1

Type RM Length L Ch R = 1,3225,892,892,892
BEGIN DESCRIPTION:
Stream0672 2.0
END DESCRIPTION:
XS GIS Cut Line= 3
      2405924.97     13628625.01      2406925.00     13628225.00
      2407324.97     13627825.03
#Sta/Elev= 30
  3922.7  280.76  4231.0  274.68  4392.6  272.84  4507.3  272.85  4583.8  273.06
  4696.4  270.44  4793.8  269.51  4803.6  268.07  4828.8  270.04  4847.6  269.38
  4945.9  271.14  4955.3  270.56  4960.7  266.22  4978.2  269.92  4987.3  264.60
  4987.8  264.10  4993.3  264.60  4997.1  267.46  5003.3  267.46  5013.9  270.40
  5028.0  270.92  5042.2  264.98  5056.3  270.22  5084.6  267.38  5098.8  270.02
  5184.2  270.15  5325.0  274.25  5349.9  274.99  5494.7  278.06  5565.4  280.95
#Mann=9,-1,0
  3922.7    0.05       0  4507.3   0.035       0  4696.4    0.07       0
  4803.6     0.1       0  4987.3    0.05       0  4993.3     0.1       0
  5184.2    0.12       0  5325.0    0.07       0  5349.9    0.12       0
Bank Sta=4987.3,4993.3
Exp/Cntr=0.3,0.1

Type RM Length L Ch R = 1,2333,478,478,478
BEGIN DESCRIPTION:
Stream0672 1.0
END DESCRIPTION:
XS GIS Cut Line= 3
      2406124.97     13628875.00      2407125.00     13628775.00
      2407375.01     13627974.97
#Sta/Elev= 30
  3990.8  279.00  3995.3  278.92  4136.9  275.73  4388.4  271.24  4401.9  271.07
  4596.8  269.51  4684.3  268.94  4764.7  269.80  4814.9  268.58  4881.6  269.66
  4943.1  268.43  4998.4  268.67  5006.3  266.89  5009.0  262.46  5009.5  261.96
  5015.1  262.46  5027.2  268.47  5090.1  267.53  5109.5  268.80  5132.0  268.12
  5142.0  266.63  5194.9  268.48  5289.2  268.95  5367.1  270.57  5509.2  272.01
  5634.9  275.29  5650.1  274.83  5785.3  277.68  5790.5  277.74  5834.0  278.74
#Mann=12,-1,0
  3990.8   0.063       0  3995.3    0.05       0  4136.9    0.07       0
  4388.4    0.05       0  4401.9    0.07       0  4596.8   0.035       0
  4881.6     0.1       0  5009.0    0.05       0  5015.1     0.1       0
  5367.1    0.12       0  5785.3    0.07       0  5790.5    0.12       0
Bank Sta=5009,5015.1
Exp/Cntr=0.3,0.1

Type RM Length L Ch R = 1,1855,376,376,376
BEGIN DESCRIPTION:
XS7443
END DESCRIPTION:
XS GIS Cut Line= 3
      2406298.32     13629130.37      2407388.02     13629049.52
      2407819.25     13628549.22
#Sta/Elev= 30
  3970.7  275.26  4033.9  274.11  4246.9  270.64  4335.9  269.31  4559.0  267.09
  4769.6  267.81  4785.6  266.92  4839.8  267.19  4859.8  266.16  4887.7  268.57
  4923.4  267.60  4930.0  266.43  4986.6  266.64  4990.2  266.39  4997.2  261.20
  4997.7  260.70  5003.3  261.20  5010.2  265.20  5020.3  267.50  5098.2  267.44
  5173.5  268.27  5199.5  268.02  5206.1  267.22  5254.1  268.23  5300.4  268.46
  5410.0  269.17  5554.2  271.25  5617.5  272.08  5681.1  271.70  5723.9  271.93
#Mann=15,-1,0
  3970.7   0.035       0  4033.9    0.07       0  4246.9   0.035       0
  4335.9    0.07       0  4887.7   0.035       0  4986.6   0.063       0
  4997.2    0.05       0  5003.3   0.063       0  5098.2    0.07       0
  5173.5   0.063       0  5254.1    0.07       0  5300.4    0.12       0
  5410.0    0.07       0  5554.2   0.035       0  5681.1    0.07       0
Bank Sta=4997.2,5003.3
Exp/Cntr=0.3,0.1

Type RM Length L Ch R = 1,1479,342,342,342
BEGIN DESCRIPTION:
XS7442
END DESCRIPTION:
XS GIS Cut Line= 5
      2406305.56     13629195.41      2407161.80     13629431.75
      2407333.41     13629342.04      2407799.24     13629023.50
      2407884.92     13628703.91
#Sta/Elev= 30
  4040.7  275.11  4211.7  272.01  4444.7  268.06  4652.2  266.06  4828.5  266.11
  4850.8  264.83  4869.2  266.79  4890.8  266.86  4911.5  264.64  4975.2  266.01
  5001.7  266.07  5008.5  260.34  5009.0  259.84  5014.6  260.34  5018.1  265.49
  5087.9  265.62  5136.6  264.71  5206.8  266.30  5230.0  267.11  5272.0  266.05
  5328.4  266.64  5373.6  265.66  5432.9  266.89  5445.4  266.77  5475.2  267.80
  5481.2  266.99  5571.6  266.74  5837.0  268.59  5938.3  269.48  6017.8  270.00
#Mann=14,-1,0
  4040.7   0.035       0  4211.7    0.07       0  4869.2   0.063       0
  4975.2   0.035       0  5008.5   0.035       0  5014.6   0.035       0
  5087.9     0.1       0  5206.8    0.07       0  5328.4    0.12       0
  5432.9    0.07       0  5445.4    0.12       0  5571.6    0.07       0
  5837.0    0.12       0  5938.3   0.035       0
Bank Sta=5008.5,5014.6
Exp/Cntr=0.3,0.1

Type RM Length L Ch R = 1,1137,609,609,609
BEGIN DESCRIPTION:
XS7441
END DESCRIPTION:
XS GIS Cut Line= 5
      2406377.88     13629260.48      2407294.41     13629669.67
      2407493.32     13629576.06      2407937.76     13629215.41
      2407903.11     13628738.18
#Sta/Elev= 30
  3851.0  272.97  3969.1  270.85  4389.7  265.71  4548.7  264.66  4557.7  265.76
  4586.4  264.60  4615.1  266.28  4641.2  264.66  4679.3  265.86  4805.6  265.30
  4845.7  265.24  4925.8  263.71  4994.2  265.33  5010.1  264.54  5013.9  258.06
  5014.4  257.56  5020.0  258.06  5039.8  265.19  5253.0  262.79  5339.4  264.84
  5463.6  265.53  5685.6  266.39  5697.5  266.47  5717.5  268.81  5737.6  267.33
  5758.3  268.24  5787.7  266.38  5982.5  267.94  6081.5  268.71  6125.4  269.37
#Mann=12,-1,0
  3851.0   0.035       0  3969.1    0.07       0  4641.2   0.063       0
  4805.6   0.035       0  4845.7     0.1       0  5013.9    0.05       0
  5020.0     0.1       0  5253.0    0.07       0  5463.6    0.12       0
  5685.6    0.07       0  5982.5    0.12       0  6081.5   0.035       0
Bank Sta=5013.9,5020
Exp/Cntr=0.3,0.1