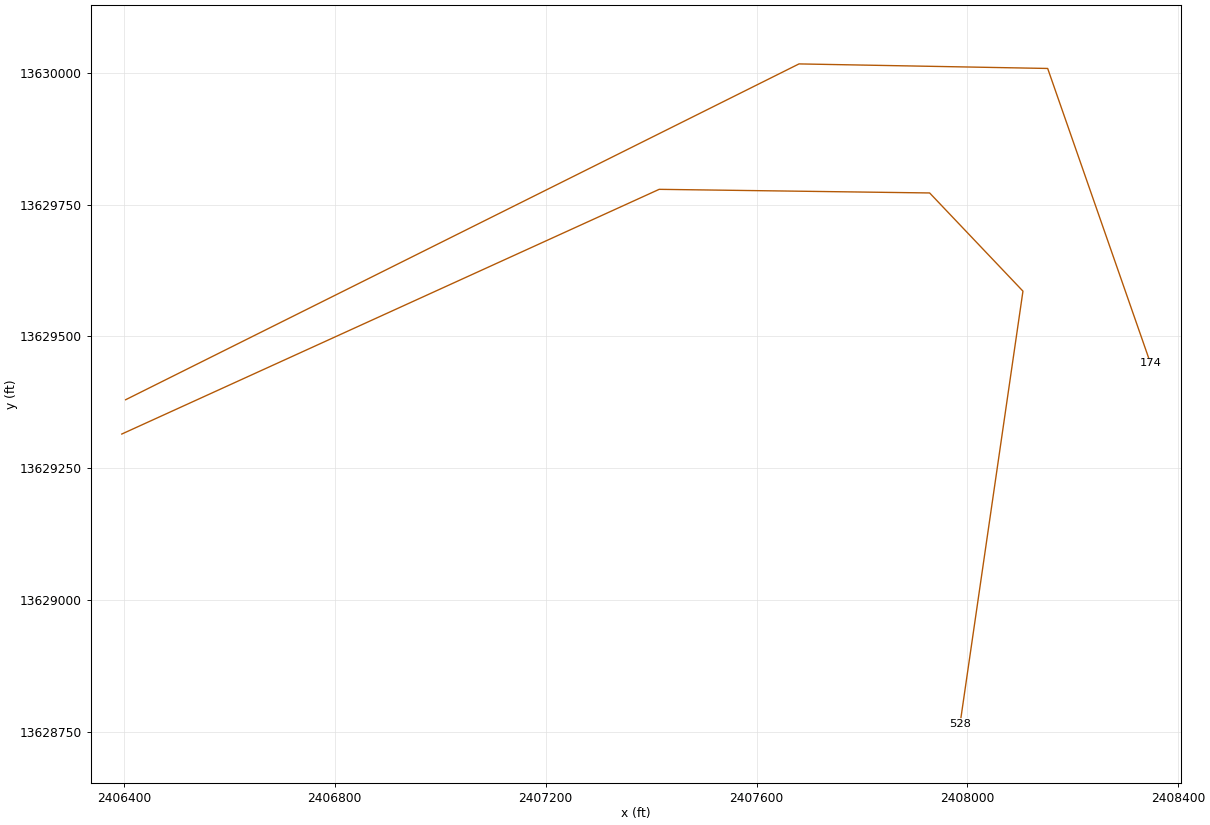
HEC-RAS study Stream0672.prj: Stream0672 Base Level Engineering

--- Stream0672.g01 (geometry) --- (continued)

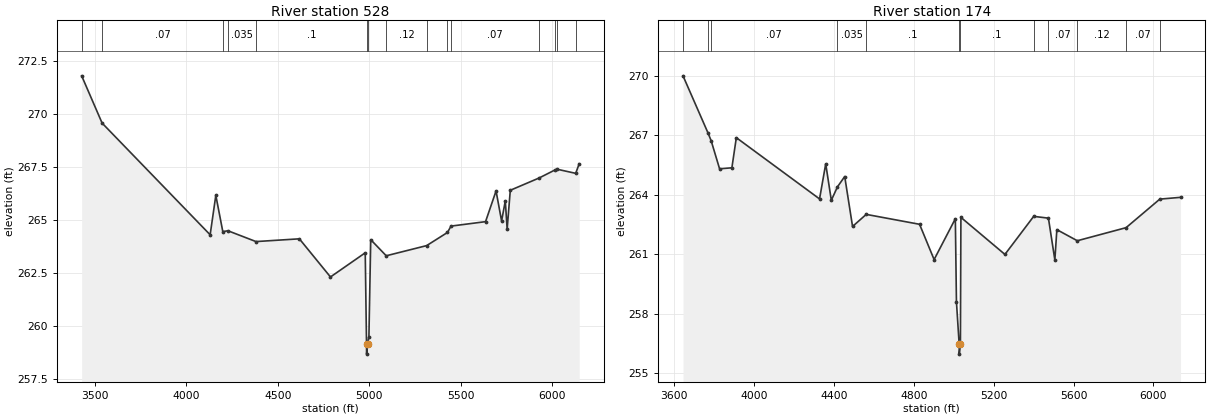
Type RM Length L Ch R = 1,528,354,354,354
BEGIN DESCRIPTION:
XS7440
END DESCRIPTION:
XS GIS Cut Line= 5
      2406395.91     13629314.67      2407415.32     13629778.87
      2407928.36     13629772.00      2408105.37     13629585.74
      2407986.11     13628765.34
#Sta/Elev= 30
  3427.5  271.79  3539.2  269.56  4129.7  264.29  4160.7  266.15  4198.9  264.44
  4227.0  264.48  4380.3  263.97  4617.3  264.10  4787.3  262.30  4977.3  263.44
  4984.3  259.16  4984.8  258.66  4990.5  259.16  4997.4  259.49  5007.4  264.06
  5092.1  263.30  5313.0  263.78  5426.8  264.40  5446.1  264.70  5634.9  264.91
  5692.3  266.36  5722.6  264.94  5742.8  265.89  5752.9  264.56  5770.1  266.39
  5927.6  266.97  6016.8  267.36  6027.5  267.38  6127.5  267.19  6146.7  267.64
#Mann=15,-1,0
  3427.5   0.035       0  3539.2    0.07       0  4198.9   0.063       0
  4227.0   0.035       0  4380.3     0.1       0  4984.3    0.05       0
  4990.5     0.1       0  5092.1    0.12       0  5313.0    0.07       0
  5426.8    0.12       0  5446.1    0.07       0  5927.6    0.12       0
  6016.8    0.07       0  6027.5    0.12       0  6127.5   0.035       0
Bank Sta=4984.3,4990.5
Exp/Cntr=0.3,0.1

Type RM Length L Ch R = 1,174,0,0,0
BEGIN DESCRIPTION:
XS7439
END DESCRIPTION:
XS GIS Cut Line= 4
      2406403.18     13629379.74      2407680.54     13630016.79
      2408152.28     13630008.16      2408347.23     13629449.21
#Sta/Elev= 30
  3644.7  270.01  3768.9  267.15  3785.5  266.74  3827.8  265.32  3889.4  265.37
  3911.7  266.89  4328.4  263.80  4359.3  265.57  4387.3  263.73  4418.1  264.41
  4454.4  264.93  4493.6  262.41  4562.1  263.02  4829.2  262.52  4902.0  260.74
  5008.3  262.80  5013.8  258.61  5027.5  256.47  5028.0  255.97  5033.7  256.47
  5036.2  262.87  5256.6  261.00  5400.6  262.92  5474.4  262.83  5506.6  260.72
  5516.6  262.25  5619.0  261.69  5863.2  262.35  6032.2  263.79  6135.9  263.88
#Mann=12,-1,0
  3644.7    0.07       0  3768.9   0.035       0  3785.5    0.07       0
  4418.1   0.035       0  4562.1     0.1       0  5027.5    0.05       0
  5033.7     0.1       0  5400.6    0.12       0  5474.4    0.07       0
  5619.0    0.12       0  5863.2    0.07       0  6032.2    0.12       0
Bank Sta=5027.5,5033.7
Exp/Cntr=0.3,0.1

Chan Stop Cuts=-1