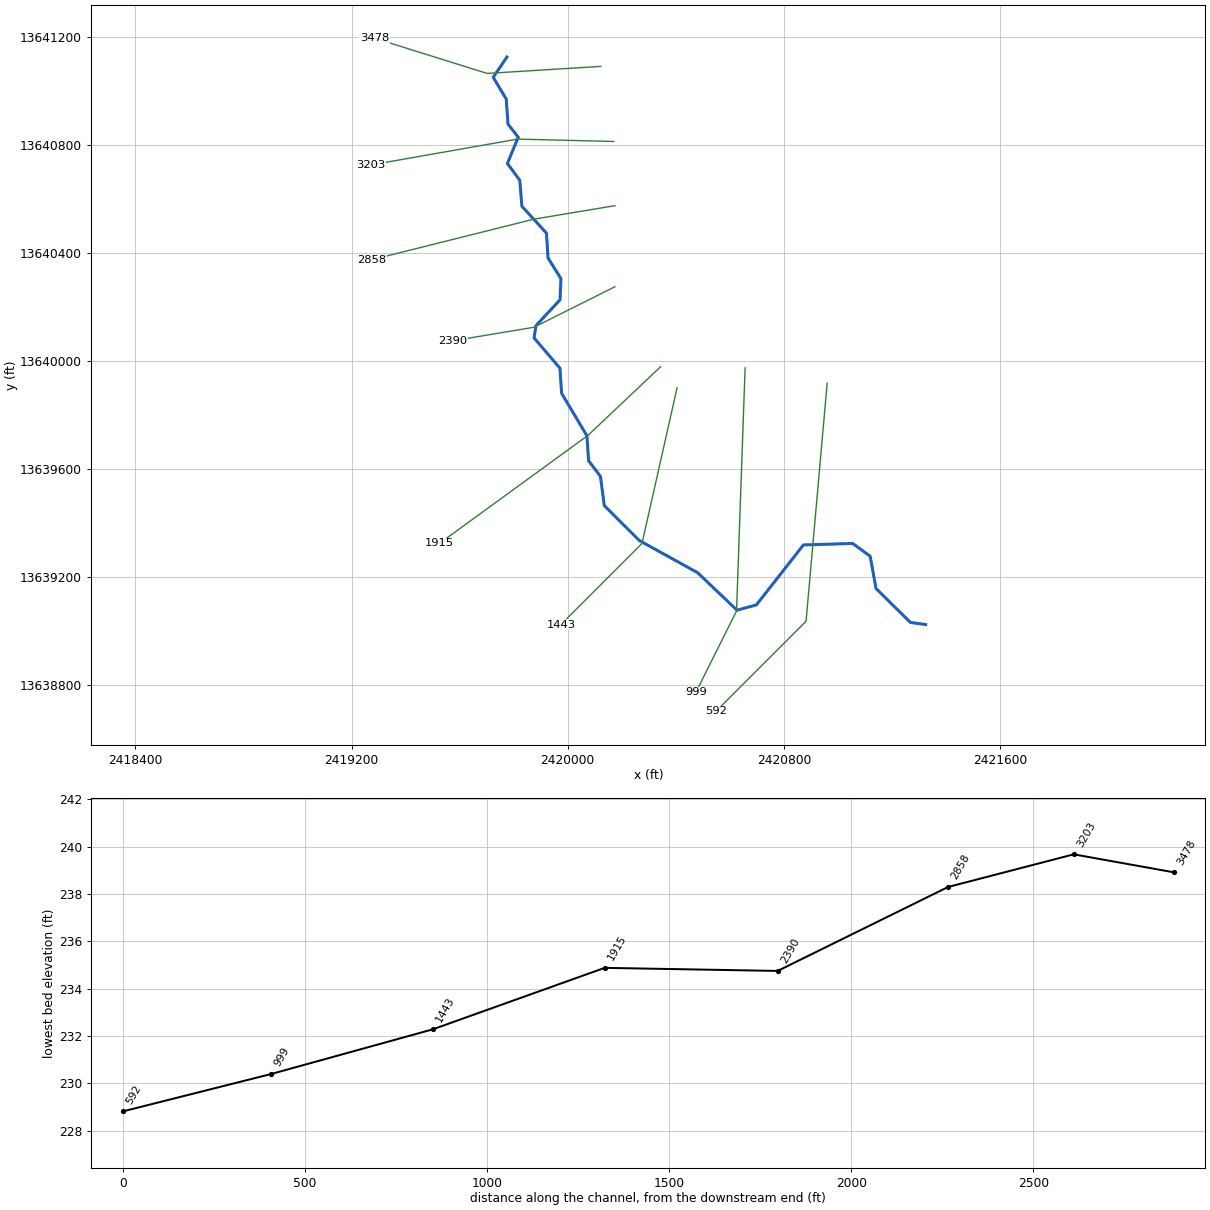
--- Stream0677.prj (project) ---

Proj Title=Stream0677 Base Level Engineering
Current Plan=p01
Default Exp/Contr=0.3,0.1
English Units
Geom File=g01
Flow File=f01
Plan File=p01
BEGIN DESCRIPTION:
Stream0677
END DESCRIPTION:

--- Stream0677.p01 (plan) ---

Plan Title=Multiple Run
Short Identifier=Multiple
Geom File=g01
Flow File=f01
Subcritical Flow
K Sum by GR= 0
Std Step Tol= 0.01
Critical Tol= 0.01
Num of Std Step Trials= 20
Max Error Tol= 0.3
Flow Tol Ratio= 0.001
Split Flow NTrial= 30
Split Flow Tol= 0.02
Split Flow Ratio= 0.02
Log Output Level= 0
Friction Slope Method= 1
Unsteady Friction Slope Method= 2
Unsteady Bridges Friction Slope Method= 1
Parabolic Critical Depth
Global Vel Dist=  1 , 1 , 1
Global Log Level= 0
CheckData=True
Encroach Param= -1, 0, 0, 0
BEGIN DESCRIPTION:
Multiple Run
END DESCRIPTION:

--- Stream0677.f01 (steady flow) ---

Flow Title=Multiple
Number of Profiles=7
Profile Names=10-year,25-year,50-year,1pct_min,100-year,1pct_plu,500-year
River Rch & RM= Stream0677,Reach-1,3478
     432     683     904     580    1158    2310    1882
Boundary for River Rch & Prof#=Stream0677,Reach-1,1
Up Type=0
Dn Type=3
Dn Slope=0.005
Boundary for River Rch & Prof#=Stream0677,Reach-1,2
Up Type=0
Dn Type=3
Dn Slope=0.005
Boundary for River Rch & Prof#=Stream0677,Reach-1,3
Up Type=0
Dn Type=3
Dn Slope=0.005
Boundary for River Rch & Prof#=Stream0677,Reach-1,4
Up Type=0
Dn Type=3
Dn Slope=0.005
Boundary for River Rch & Prof#=Stream0677,Reach-1,5
Up Type=0
Dn Type=3
Dn Slope=0.005
Boundary for River Rch & Prof#=Stream0677,Reach-1,6
Up Type=0
Dn Type=3
Dn Slope=0.005
Boundary for River Rch & Prof#=Stream0677,Reach-1,7
Up Type=0
Dn Type=3
Dn Slope=0.005

--- Stream0677.g01 (geometry) ---

Geom Title=Existing Conditions

River Reach=Stream0677,Reach-1
Reach XY= 30
      2419775.00     13641125.00      2419724.39     13641049.95
      2419772.64     13640969.04      2419779.09     13640876.50
      2419816.90     13640828.29      2419776.86     13640731.13
      2419822.62     13640669.03      2419830.54     13640572.58
      2419921.38     13640473.50      2419927.36     13640380.98
      2419975.10     13640304.90      2419971.53     13640226.50
      2419882.48     13640131.04      2419875.56     13640085.64
      2419971.38     13639973.50      2419977.33     13639880.97
      2420071.17     13639723.42      2420077.35     13639630.97
      2420121.14     13639573.40      2420135.52     13639465.21
      2420265.32     13639335.78      2420481.05     13639216.84
      2420626.65     13639078.10      2420698.51     13639097.68
      2420872.53     13639319.55      2421055.13     13639325.09
      2421119.59     13639277.71      2421141.46     13639158.25
      2421268.79     13639032.76      2421325.00     13639025.00

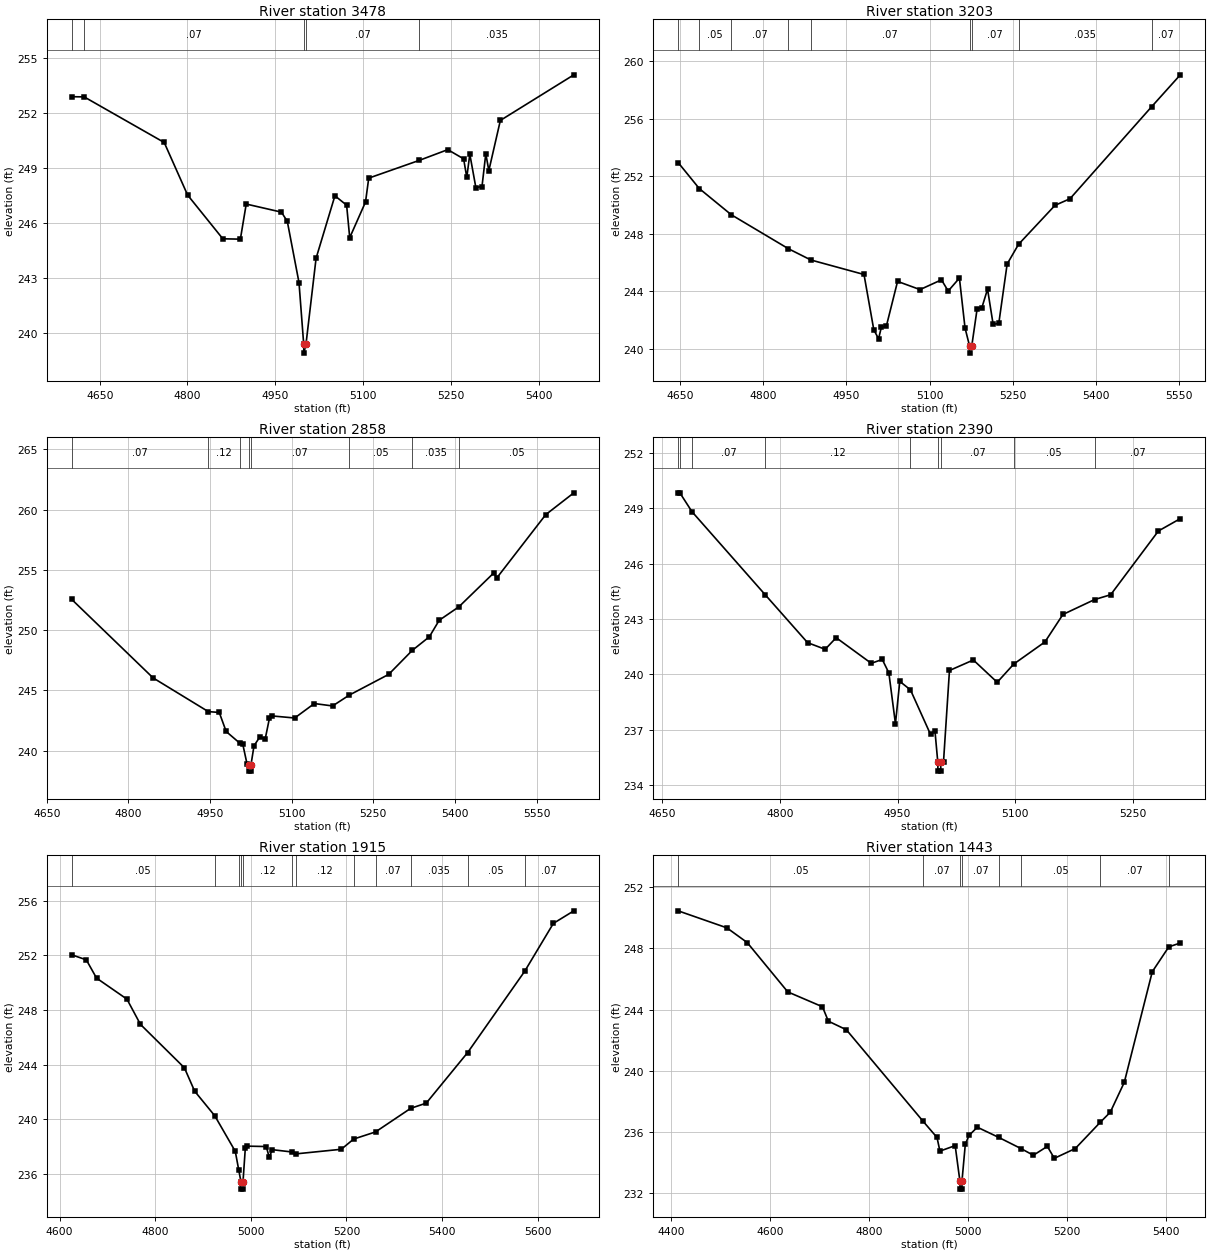
Type RM Length L Ch R = 1,3478,275,275,275
BEGIN DESCRIPTION:
XS7456
END DESCRIPTION:
XS GIS Cut Line= 3
      2420122.87     13641090.37      2419701.82     13641064.32
      2419285.15     13641194.53
#Sta/Elev= 30
  4602.0  252.87  4623.4  252.86  4760.2  250.38  4800.2  247.52  4860.4  245.14
  4890.4  245.12  4900.4  247.03  4960.6  246.59  4970.6  246.09  4990.6  242.76
  4998.6  239.42  4998.9  238.92  5002.6  239.42  5019.8  244.08  5052.0  247.48
  5072.0  246.97  5077.3  245.20  5104.3  247.14  5109.8  248.44  5196.5  249.41
  5244.9  249.99  5272.0  249.49  5277.4  248.48  5282.6  249.74  5292.9  247.93
  5303.4  247.98  5309.9  249.77  5315.1  248.85  5334.8  251.58  5460.4  254.06
#Mann=5,-1,0
  4602.0    0.05       0  4623.4    0.07       0  4998.6    0.05       0
  5002.6    0.07       0  5196.5   0.035       0
Bank Sta=4998.6,5002.6
Exp/Cntr=0.3,0.1

Type RM Length L Ch R = 1,3203,345,345,345
BEGIN DESCRIPTION:
Stream0677 7.0
END DESCRIPTION:
XS GIS Cut Line= 3
      2420170.58     13640812.59      2419814.67     13640821.27
      2419272.13     13640725.78
#Sta/Elev= 30
  4646.0  252.94  4684.2  251.13  4741.9  249.31  4845.3  246.94  4885.7  246.16
  4981.7  245.15  4999.4  241.30  5008.0  240.68  5013.1  241.49  5022.0  241.55
  5042.3  244.67  5082.9  244.10  5121.6  244.78  5133.7  244.00  5154.0  244.90
  5164.1  241.44  5172.3  240.18  5172.5  239.68  5176.3  240.18  5186.0  242.77
  5194.6  242.85  5204.8  244.13  5214.9  241.68  5225.1  241.75  5240.2  245.88
  5260.8  247.25  5326.6  249.96  5353.7  250.42  5501.3  256.83  5552.9  259.04
#Mann=9,-1,0
  4646.0    0.07       0  4684.2    0.05       0  4741.9    0.07       0
  4845.3    0.12       0  4885.7    0.07       0  5172.3    0.05       0
  5176.3    0.07       0  5260.8   0.035       0  5501.3    0.07       0
Bank Sta=5172.3,5176.3
Exp/Cntr=0.3,0.1

Type RM Length L Ch R = 1,2858,468,468,468
BEGIN DESCRIPTION:
Stream0677 6.0
END DESCRIPTION:
XS GIS Cut Line= 3
      2420175.05     13640575.01      2419875.00     13640525.00
      2419274.95     13640374.99
#Sta/Elev= 30
  4695.8  252.56  4845.4  246.04  4946.9  243.24  4967.0  243.17  4979.7  241.59
  5004.5  240.63  5010.3  240.52  5018.0  238.90  5021.2  238.80  5021.4  238.30
  5024.9  238.30  5025.2  238.80  5030.9  240.41  5041.2  241.11  5051.5  240.99
  5059.3  242.71  5064.4  242.88  5105.6  242.71  5141.7  243.91  5175.2  243.71
  5205.9  244.61  5278.3  246.33  5321.6  248.32  5353.0  249.45  5371.1  250.82
  5407.3  251.94  5471.6  254.76  5476.7  254.32  5566.9  259.59  5618.5  261.40
#Mann=8,-1,0
  4695.8    0.07       0  4946.9    0.12       0  5004.5    0.07       0
  5021.2    0.05       0  5025.2    0.07       0  5205.9    0.05       0
  5321.6   0.035       0  5407.3    0.05       0
Bank Sta=5021.2,5025.2
Exp/Cntr=0.3,0.1

Type RM Length L Ch R = 1,2390,475,475,475
BEGIN DESCRIPTION:
Stream0677 5.0
END DESCRIPTION:
XS GIS Cut Line= 3
      2420175.04     13640275.02      2419875.00     13640125.00
      2419574.99     13640075.00
#Sta/Elev= 30
  4670.5  249.85  4672.7  249.85  4688.1  248.83  4781.2  244.33  4835.4  241.72
  4857.8  241.36  4871.8  241.99  4916.5  240.60  4930.5  240.81  4938.9  240.08
  4947.3  237.32  4952.8  239.62  4966.4  239.16  4992.0  236.74  4997.6  236.94
  5001.2  235.25  5001.4  234.75  5004.9  234.75  5005.2  235.25  5008.5  235.25
  5016.1  240.21  5046.5  240.78  5076.9  239.57  5098.0  240.56  5137.7  241.76
  5160.6  243.25  5201.0  244.06  5221.4  244.32  5282.2  247.78  5310.1  248.45
#Mann=9,-1,0
  4670.5    0.07       0  4672.7   0.035       0  4688.1    0.07       0
  4781.2    0.12       0  4966.4    0.07       0  5001.2    0.05       0
  5005.2    0.07       0  5098.0    0.05       0  5201.0    0.07       0
Bank Sta=5001.2,5005.2
Exp/Cntr=0.3,0.1

Type RM Length L Ch R = 1,1915,472,472,472
BEGIN DESCRIPTION:
Stream0677 4.0
END DESCRIPTION:
XS GIS Cut Line= 3
      2420344.18     13639979.25      2420075.00     13639725.00
      2419525.04     13639325.03
#Sta/Elev= 30
  4625.4  252.05  4656.0  251.68  4677.5  250.34  4741.0  248.80  4769.3  246.95
  4861.2  243.77  4882.6  242.06  4924.8  240.25  4967.6  237.65  4975.0  236.26
  4979.7  235.38  4980.0  234.88  4983.5  234.88  4983.7  235.38  4988.6  237.88
  4992.2  238.03  5032.4  238.00  5038.6  237.22  5045.1  237.77  5086.5  237.60
  5093.7  237.46  5189.3  237.80  5215.3  238.55  5260.9  239.07  5334.5  240.80
  5367.0  241.18  5453.7  244.89  5572.9  250.84  5632.9  254.35  5675.7  255.27
#Mann=12,-1,0
  4625.4    0.05       0  4924.8    0.07       0  4975.0    0.12       0
  4979.7    0.05       0  4983.7    0.12       0  5086.5    0.07       0
  5093.7    0.12       0  5215.3   0.035       0  5260.9    0.07       0
  5334.5   0.035       0  5453.7    0.05       0  5572.9    0.07       0
Bank Sta=4979.7,4983.7
Exp/Cntr=0.3,0.1

Type RM Length L Ch R = 1,1443,444,444,444
BEGIN DESCRIPTION:
Stream0677 3.0
END DESCRIPTION:
XS GIS Cut Line= 3
      2420404.95     13639901.13      2420275.00     13639325.00
      2419974.98     13639024.98
#Sta/Elev= 30
  4413.8  250.44  4512.3  249.33  4553.4  248.37  4635.4  245.15  4705.5  244.18
  4717.4  243.24  4753.8  242.68  4908.8  236.71  4937.0  235.65  4942.9  234.76
  4973.7  235.12  4983.4  232.78  4983.6  232.28  4987.1  232.28  4987.4  232.78
  4994.2  235.21  5001.8  235.79  5018.5  236.32  5062.1  235.65  5107.1  234.92
  5131.7  234.49  5160.0  235.07  5174.1  234.29  5216.5  234.93  5266.6  236.63
  5287.2  237.30  5315.5  239.25  5372.1  246.47  5405.5  248.09  5428.7  248.34
#Mann=8,-1,0
  4413.8    0.05       0  4908.8    0.07       0  4983.4    0.05       0
  4987.4    0.07       0  5062.1    0.12       0  5107.1    0.05       0
  5266.6    0.07       0  5405.5    0.05       0
Bank Sta=4983.4,4987.4
Exp/Cntr=0.3,0.1

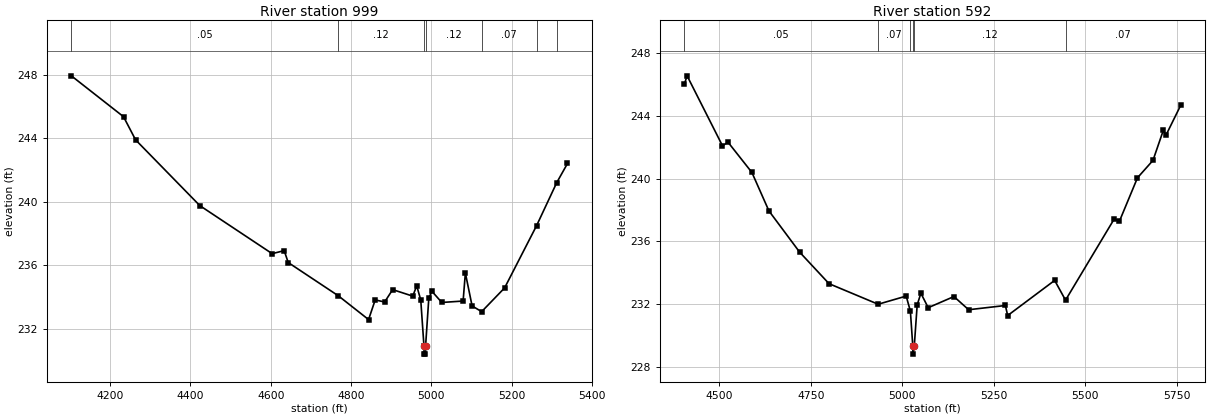
Type RM Length L Ch R = 1,999,407,407,407
BEGIN DESCRIPTION:
Stream0677 2.0
END DESCRIPTION:
XS GIS Cut Line= 3
      2420656.68     13639974.90      2420625.00     13639075.00
      2420474.98     13638774.97
#Sta/Elev= 30
  4103.4  247.95  4233.4  245.37  4263.4  243.91  4423.5  239.76  4603.6  236.73
  4633.6  236.92  4643.6  236.17  4768.5  234.07  4843.8  232.57  4860.3  233.81
  4883.8  233.68  4903.8  234.46  4953.8  234.05  4963.8  234.70  4973.8  233.80
  4981.8  230.89  4982.1  230.39  4985.6  230.39  4985.8  230.89  4993.8  233.91
  5001.4  234.36  5026.2  233.65  5079.3  233.74  5084.9  235.51  5101.7  233.43
  5125.5  233.07  5182.7  234.57  5262.4  238.50  5312.5  241.21  5339.3  242.42
#Mann=7,-1,0
  4103.4    0.05       0  4768.5    0.12       0  4981.8    0.05       0
  4985.8    0.12       0  5125.5    0.07       0  5262.4    0.05       0
  5312.5    0.07       0
Bank Sta=4981.8,4985.8
Exp/Cntr=0.3,0.1

Type RM Length L Ch R = 1,592,0,0,0
BEGIN DESCRIPTION:
Stream0677 1.0
END DESCRIPTION:
XS GIS Cut Line= 3
      2420960.51     13639918.53      2420882.38     13639037.41
      2420549.10     13638704.14
#Sta/Elev= 30
  4404.6  246.04  4411.8  246.55  4508.5  242.09  4523.6  242.32  4588.9  240.39
  4635.4  237.94  4719.4  235.31  4799.7  233.30  4933.9  231.99  5010.5  232.51
  5022.0  231.55  5028.6  229.31  5028.8  228.81  5032.6  229.31  5040.6  231.95
  5050.7  232.69  5070.7  231.77  5141.0  232.48  5181.2  231.64  5281.6  231.91
  5287.9  231.27  5416.3  233.51  5446.0  232.25  5578.9  237.42  5593.1  237.27
  5642.6  240.05  5685.0  241.16  5713.3  243.08  5720.4  242.76  5760.5  244.66
#Mann=6,-1,0
  4404.6    0.05       0  4933.9    0.07       0  5022.0    0.12       0
  5028.6    0.05       0  5032.6    0.12       0  5446.0    0.07       0
Bank Sta=5028.6,5032.6
Exp/Cntr=0.3,0.1

Chan Stop Cuts=-1