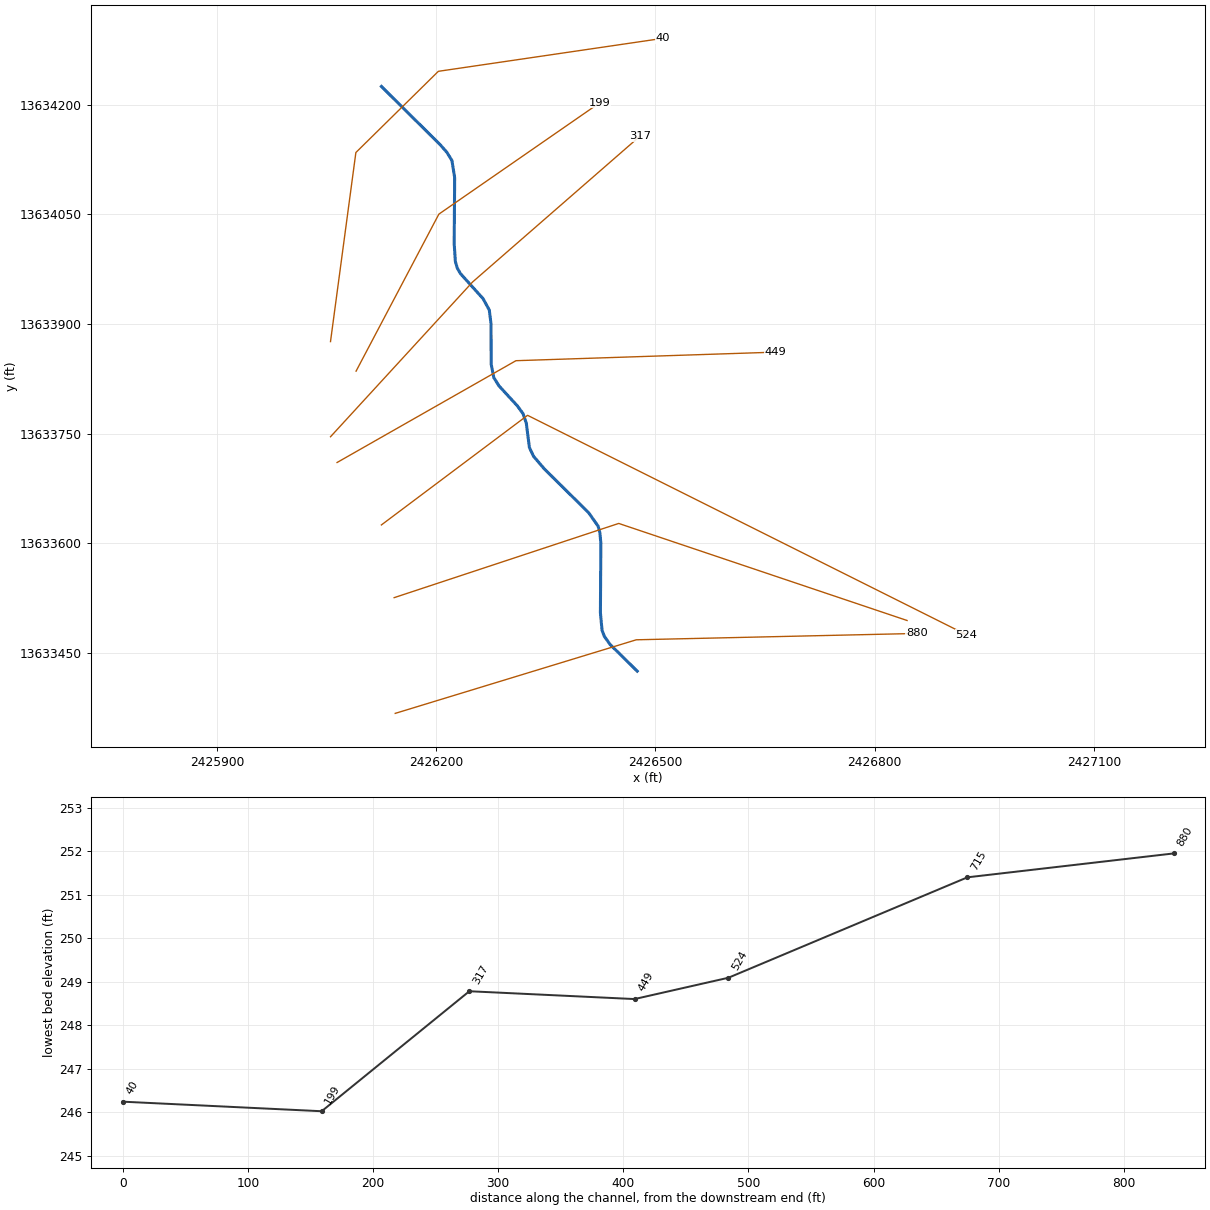
--- Stream0679.prj (project) ---

Proj Title=Stream0679 Base Level Engineering
Current Plan=p01
Default Exp/Contr=0.3,0.1
English Units
Geom File=g01
Flow File=f01
Plan File=p01
BEGIN DESCRIPTION:
Stream0679
END DESCRIPTION:

--- Stream0679.p01 (plan) ---

Plan Title=Multiple Run
Short Identifier=Multiple
Geom File=g01
Flow File=f01
Subcritical Flow
K Sum by GR= 0
Std Step Tol= 0.01
Critical Tol= 0.01
Num of Std Step Trials= 20
Max Error Tol= 0.3
Flow Tol Ratio= 0.001
Split Flow NTrial= 30
Split Flow Tol= 0.02
Split Flow Ratio= 0.02
Log Output Level= 0
Friction Slope Method= 1
Unsteady Friction Slope Method= 2
Unsteady Bridges Friction Slope Method= 1
Parabolic Critical Depth
Global Vel Dist=  1 , 1 , 1
Global Log Level= 0
CheckData=True
Encroach Param= -1, 0, 0, 0
BEGIN DESCRIPTION:
Multiple Run
END DESCRIPTION:

--- Stream0679.f01 (steady flow) ---

Flow Title=Multiple
Number of Profiles=7
Profile Names=10-year,25-year,50-year,1pct_min,100-year,1pct_plu,500-year
River Rch & RM= Stream0679,Reach-1,880
     188     283     362     226     451     900     691
Boundary for River Rch & Prof#=Stream0679,Reach-1,1
Up Type=0
Dn Type=3
Dn Slope=0.005
Boundary for River Rch & Prof#=Stream0679,Reach-1,2
Up Type=0
Dn Type=3
Dn Slope=0.005
Boundary for River Rch & Prof#=Stream0679,Reach-1,3
Up Type=0
Dn Type=3
Dn Slope=0.005
Boundary for River Rch & Prof#=Stream0679,Reach-1,4
Up Type=0
Dn Type=3
Dn Slope=0.005
Boundary for River Rch & Prof#=Stream0679,Reach-1,5
Up Type=0
Dn Type=3
Dn Slope=0.005
Boundary for River Rch & Prof#=Stream0679,Reach-1,6
Up Type=0
Dn Type=3
Dn Slope=0.005
Boundary for River Rch & Prof#=Stream0679,Reach-1,7
Up Type=0
Dn Type=3
Dn Slope=0.005

--- Stream0679.g01 (geometry) ---

Geom Title=Existing Conditions

River Reach=Stream0679,Reach-1
Reach XY= 30
      2426475.00     13633425.00      2426437.92     13633461.50
      2426430.15     13633472.42      2426426.91     13633480.79
      2426424.68     13633504.87      2426425.28     13633600.11
      2426423.94     13633614.56      2426421.45     13633623.53
      2426408.54     13633641.75      2426348.06     13633701.55
      2426333.16     13633718.95      2426327.50     13633731.04
      2426323.28     13633764.29      2426318.86     13633777.17
      2426310.95     13633788.04      2426285.84     13633815.35
      2426278.83     13633826.58      2426275.23     13633845.09
      2426275.00     13633900.00      2426272.64     13633919.02
      2426264.11     13633934.63      2426233.14     13633968.94
      2426228.79     13633976.57      2426226.23     13633985.51
      2426224.61     13634009.84      2426225.27     13634100.11
      2426221.51     13634123.55      2426214.61     13634134.84
      2426205.50     13634145.21      2426125.00     13634225.00

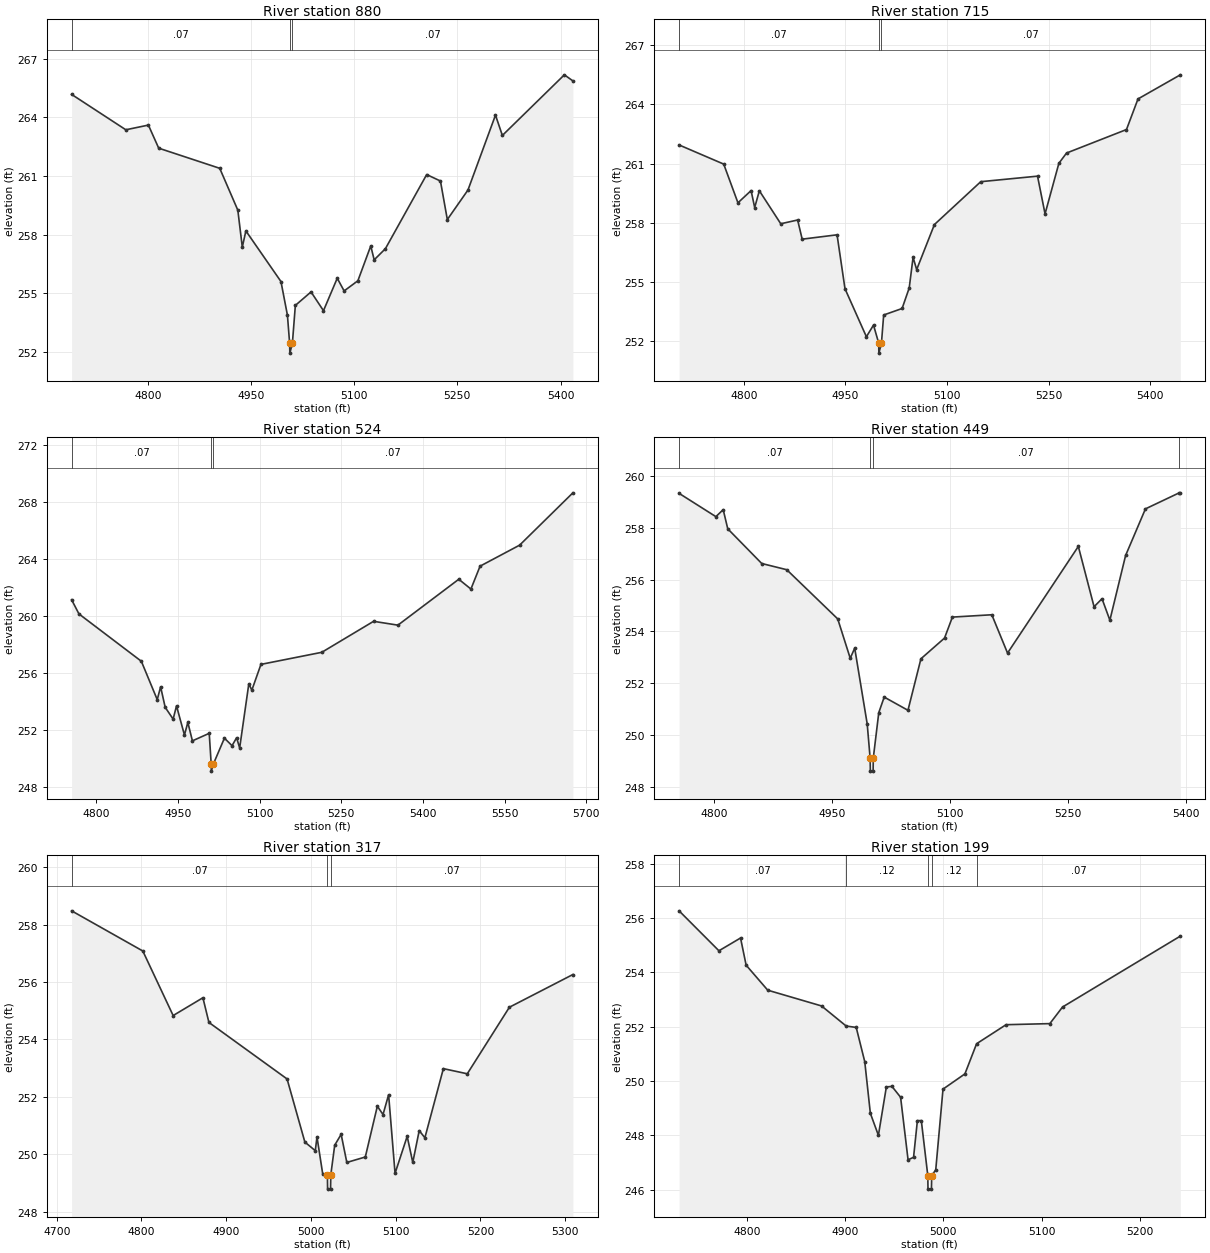
Type RM Length L Ch R = 1,880,165,165,165
BEGIN DESCRIPTION:
XS7459
END DESCRIPTION:
XS GIS Cut Line= 3
      2426143.95     13633367.20      2426473.78     13633467.88
      2426857.43     13633476.56
#Sta/Elev= 30
  4689.3  265.18  4768.1  263.37  4800.9  263.61  4815.9  262.43  4904.6  261.40
  4930.9  259.26  4937.4  257.37  4942.6  258.20  4993.6  255.61  5003.0  253.89
  5006.2  252.45  5006.5  251.95  5010.2  252.45  5014.5  254.39  5037.3  255.08
  5055.4  254.12  5075.4  255.78  5085.4  255.13  5105.4  255.65  5124.1  257.43
  5129.1  256.72  5145.4  257.29  5205.4  261.08  5225.4  260.75  5235.4  258.78
  5265.4  260.29  5305.4  264.12  5315.4  263.08  5405.5  266.18  5417.9  265.87
#Mann=3,-1,0
  4689.3    0.07       0  5006.2    0.05       0  5010.2    0.07       0
Bank Sta=5006.2,5010.2
Exp/Cntr=0.3,0.1

Type RM Length L Ch R = 1,715,191,191,191
BEGIN DESCRIPTION:
E21257
END DESCRIPTION:
XS GIS Cut Line= 3
      2426142.45     13633525.52      2426449.74     13633627.08
      2426844.25     13633494.28
#Sta/Elev= 30
  4704.4  261.94  4770.3  260.97  4791.3  259.01  4810.7  259.63  4816.0  258.77
  4822.9  259.62  4854.5  257.95  4879.4  258.14  4886.1  257.17  4937.6  257.39
  4949.3  254.66  4980.9  252.23  4991.4  252.82  4999.1  251.90  4999.3  251.40
  5003.1  251.90  5006.4  253.33  5033.6  253.66  5044.1  254.70  5049.8  256.25
  5055.1  255.63  5081.3  257.91  5149.7  260.08  5233.5  260.36  5244.6  258.45
  5265.0  261.01  5276.3  261.53  5364.8  262.72  5381.8  264.27  5444.3  265.49
#Mann=3,-1,0
  4704.4    0.07       0  4999.1    0.05       0  5003.1    0.07       0
Bank Sta=4999.1,5003.1
Exp/Cntr=0.3,0.1

Type RM Length L Ch R = 1,524,75,75,75
BEGIN DESCRIPTION:
Stream0679 1.0
END DESCRIPTION:
XS GIS Cut Line= 3
      2426125.00     13633625.00      2426325.00     13633775.00
      2426924.99     13633475.01
#Sta/Elev= 30
  4754.8  261.15  4768.3  260.15  4882.9  256.82  4912.1  254.12  4918.3  255.02
  4926.7  253.58  4941.3  252.75  4947.5  253.68  4962.1  251.63  4968.3  252.52
  4976.7  251.22  5007.6  251.75  5011.2  249.59  5011.4  249.09  5015.2  249.59
  5035.5  251.41  5049.5  250.88  5057.9  251.44  5063.5  250.72  5080.3  255.23
  5085.9  254.79  5102.6  256.60  5214.4  257.45  5309.5  259.63  5354.2  259.36
  5466.0  262.59  5488.3  261.90  5505.1  263.51  5577.8  264.99  5675.6  268.67
#Mann=3,-1,0
  4754.8    0.07       0  5011.2    0.05       0  5015.2    0.07       0
Bank Sta=5011.2,5015.2
Exp/Cntr=0.3,0.1

Type RM Length L Ch R = 1,449,132,132,132
BEGIN DESCRIPTION:
E21256
END DESCRIPTION:
XS GIS Cut Line= 3
      2426064.35     13633710.43      2426309.11     13633849.74
      2426664.59     13633861.46
#Sta/Elev= 30
  4755.1  259.33  4801.9  258.43  4811.2  258.70  4817.0  257.96  4860.2  256.62
  4892.0  256.38  4956.8  254.48  4972.7  252.96  4978.4  253.35  4994.3  250.42
  4998.0  249.10  4998.3  248.60  5001.8  248.60  5002.0  249.10  5009.0  250.86
  5015.9  251.46  5046.1  250.95  5062.6  252.94  5092.6  253.74  5102.6  254.55
  5152.7  254.64  5172.7  253.16  5262.7  257.28  5282.7  254.95  5292.8  255.26
  5302.8  254.43  5322.8  256.93  5348.0  258.73  5391.0  259.35  5392.4  259.35
#Mann=4,-1,0
  4755.1    0.07       0  4998.0    0.05       0  5002.0    0.07       0
  5391.0   0.035       0
Bank Sta=4998,5002
Exp/Cntr=0.3,0.1

Type RM Length L Ch R = 1,317,118,118,118
BEGIN DESCRIPTION:
XS7458
END DESCRIPTION:
XS GIS Cut Line= 3
      2426055.40     13633745.68      2426249.83     13633957.47
      2426478.96     13634157.09
#Sta/Elev= 30
  4717.6  258.48  4801.6  257.08  4837.4  254.83  4872.5  255.45  4879.6  254.59
  4971.8  252.62  4992.8  250.42  5005.1  250.12  5007.1  250.60  5013.8  249.32
  5019.4  249.28  5019.6  248.78  5023.1  248.78  5023.4  249.28  5028.0  250.31
  5035.6  250.69  5042.3  249.71  5064.1  249.90  5078.3  251.67  5085.0  251.38
  5091.6  252.07  5099.2  249.33  5113.5  250.62  5120.1  249.71  5127.7  250.82
  5134.4  250.57  5156.2  252.98  5184.4  252.80  5234.1  255.12  5309.0  256.26
#Mann=3,-1,0
  4717.6    0.07       0  5019.4    0.05       0  5023.4    0.07       0
Bank Sta=5019.4,5023.4
Exp/Cntr=0.3,0.1

Type RM Length L Ch R = 1,199,159,159,159
BEGIN DESCRIPTION:
E21255
END DESCRIPTION:
XS GIS Cut Line= 3
      2426090.37     13633835.43      2426203.65     13634050.26
      2426423.69     13634202.60
#Sta/Elev= 30
  4730.9  256.26  4771.5  254.79  4793.5  255.26  4799.2  254.26  4821.2  253.34
  4876.0  252.76  4901.1  252.02  4911.3  251.97  4920.0  250.71  4925.7  248.81
  4933.9  248.00  4942.0  249.78  4947.7  249.80  4956.5  249.40  4964.1  247.10
  4969.7  247.19  4973.6  248.54  4977.6  248.54  4984.2  246.52  4984.4  246.02
  4987.9  246.02  4988.2  246.52  4992.3  246.73  4999.7  249.70  5022.0  250.26
  5033.9  251.37  5063.9  252.07  5108.5  252.11  5121.4  252.72  5241.4  255.33
#Mann=5,-1,0
  4730.9    0.07       0  4901.1    0.12       0  4984.2    0.05       0
  4988.2    0.12       0  5033.9    0.07       0
Bank Sta=4984.2,4988.2
Exp/Cntr=0.3,0.1

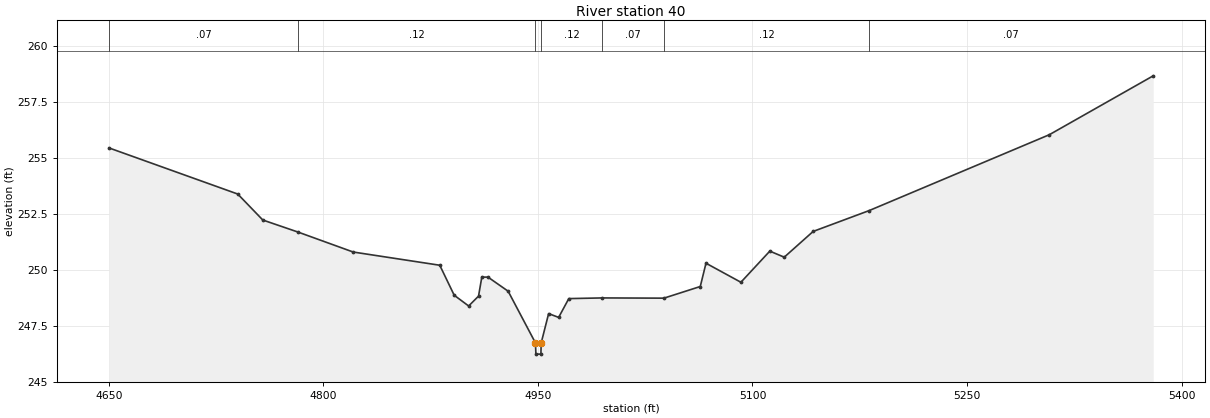
Type RM Length L Ch R = 1,40,0,0,0
BEGIN DESCRIPTION:
XS7457
END DESCRIPTION:
XS GIS Cut Line= 4
      2426055.38     13633875.84      2426090.10     13634134.55
      2426202.95     13634245.66      2426510.16     13634290.79
#Sta/Elev= 30
  4650.2  255.45  4740.2  253.39  4757.7  252.23  4782.4  251.69  4820.9  250.80
  4881.4  250.21  4891.5  248.87  4901.6  248.39  4908.5  248.83  4910.8  249.68
  4915.1  249.68  4929.2  249.05  4948.3  246.74  4948.6  246.24  4952.1  246.24
  4952.3  246.74  4957.5  248.05  4964.5  247.88  4971.6  248.72  4994.9  248.75
  5038.1  248.74  5063.5  249.26  5067.5  250.30  5091.9  249.45  5112.1  250.84
  5122.2  250.57  5142.4  251.72  5181.5  252.65  5307.5  256.04  5380.1  258.67
#Mann=7,-1,0
  4650.2    0.07       0  4782.4    0.12       0  4948.3    0.05       0
  4952.3    0.12       0  4994.9    0.07       0  5038.1    0.12       0
  5181.5    0.07       0
Bank Sta=4948.3,4952.3
Exp/Cntr=0.3,0.1

Chan Stop Cuts=-1