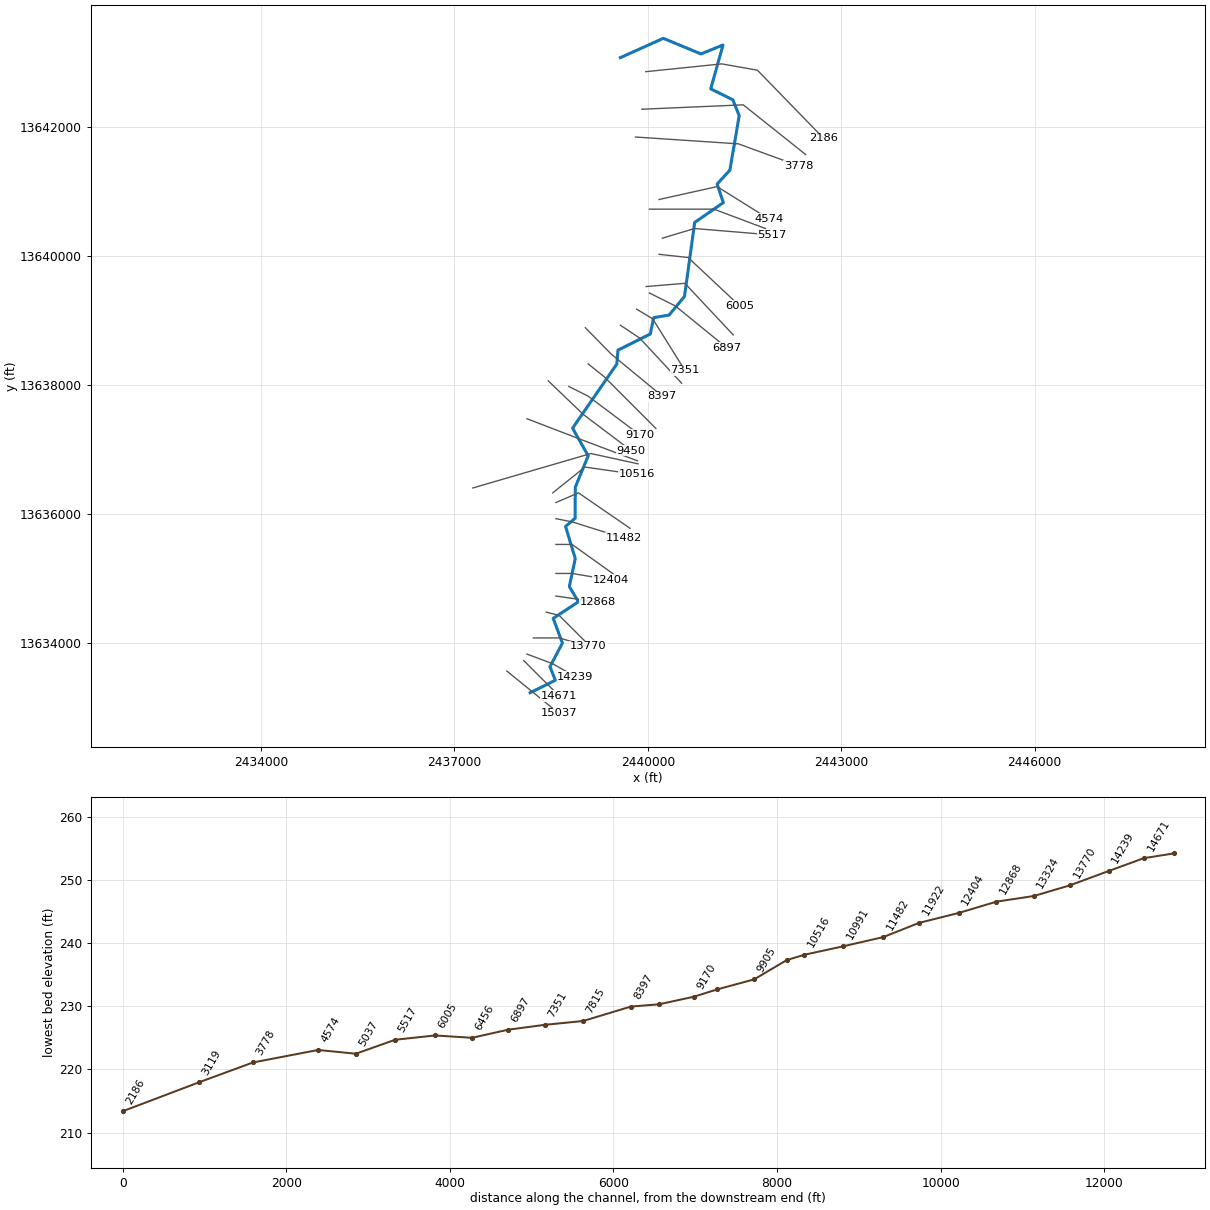
--- Stream0683.prj (project) ---

Proj Title=Stream0683 Base Level Engineering
Current Plan=p01
Default Exp/Contr=0.3,0.1
English Units
Geom File=g01
Flow File=f01
Plan File=p01
Y Axis Title=Elevation
X Axis Title(PF)=Main Channel Distance
X Axis Title(XS)=Station
BEGIN DESCRIPTION:
Stream0683
END DESCRIPTION:
DSS Export Rating Curves= 0
DSS Export Rating Curve Sorted= 0
DSS Export Volume Flow Curves= 0
DXF OffsetX= 0
DXF OffsetY= 0
DXF ScaleX= 1
DXF ScaleY= 10

--- Stream0683.p01 (plan) ---

Plan Title=Multiple Run
Short Identifier=Multiple
Geom File=g01
Flow File=f01
Subcritical Flow
K Sum by GR= 0
Std Step Tol= 0.01
Critical Tol= 0.01
Num of Std Step Trials= 20
Max Error Tol= 0.3
Flow Tol Ratio= 0.001
Split Flow NTrial= 30
Split Flow Tol= 0.02
Split Flow Ratio= 0.02
Log Output Level= 0
Friction Slope Method= 1
Unsteady Friction Slope Method= 2
Unsteady Bridges Friction Slope Method= 1
Parabolic Critical Depth
Global Vel Dist=  1 , 1 , 1
Global Log Level= 0
CheckData=True
Encroach Param= -1, 0, 0, 0
BEGIN DESCRIPTION:
Multiple Run
END DESCRIPTION:

--- Stream0683.f01 (steady flow) ---

Flow Title=Multiple
Number of Profiles=7
Profile Names=10-year,25-year,50-year,1pct_min,100-year,1pct_plu,500-year
River Rch & RM= Stream0683,Reach-1,15037
     752    1217    1637    1066    2126    4242    3553
River Rch & RM= Stream0683,Reach-1,9905
    1111    1836    2506    1653    3298    6581    5661
River Rch & RM= Stream0683,Reach-1,9450
    1287    2133    2915    1923    3837    7656    6593
Boundary for River Rch & Prof#=Stream0683,Reach-1,1
Up Type=0
Dn Type=3
Dn Slope=0.005
Boundary for River Rch & Prof#=Stream0683,Reach-1,2
Up Type=0
Dn Type=3
Dn Slope=0.005
Boundary for River Rch & Prof#=Stream0683,Reach-1,3
Up Type=0
Dn Type=3
Dn Slope=0.005
Boundary for River Rch & Prof#=Stream0683,Reach-1,4
Up Type=0
Dn Type=3
Dn Slope=0.005
Boundary for River Rch & Prof#=Stream0683,Reach-1,5
Up Type=0
Dn Type=3
Dn Slope=0.005
Boundary for River Rch & Prof#=Stream0683,Reach-1,6
Up Type=0
Dn Type=3
Dn Slope=0.005
Boundary for River Rch & Prof#=Stream0683,Reach-1,7
Up Type=0
Dn Type=3
Dn Slope=0.005

--- Stream0683.g01 (geometry) ---

Geom Title=Existing Conditions
Program Version=4.10

River Reach=Stream0683      ,Reach-1
Reach XY= 30
        2438175.       13633225.      2438565.88     13633418.24
      2438482.79     13633628.42       2438675.6     13633995.05
      2438532.68     13634378.71       2438924.3      13634635.7
      2438783.04     13634871.68      2438874.95     13635304.96
      2438724.56     13635804.97      2438873.01     13635930.68
       2438875.6     13636414.38      2439075.32     13636900.12
      2438833.07     13637328.31      2439519.19     13638322.71
      2439537.99     13638538.56      2440038.25     13638788.61
      2440091.03     13639042.14      2440331.21      13639082.8
       2440569.6     13639372.57      2440727.06     13640519.15
      2441171.48     13640826.46      2441075.55     13641114.36
      2441273.03     13641330.89      2441417.67      13642175.1
      2441319.96     13642419.92      2440975.64     13642590.84
      2441167.09      13643272.1        2440825.      13643132.5
      2440240.21     13643374.49        2439575.       13643075.

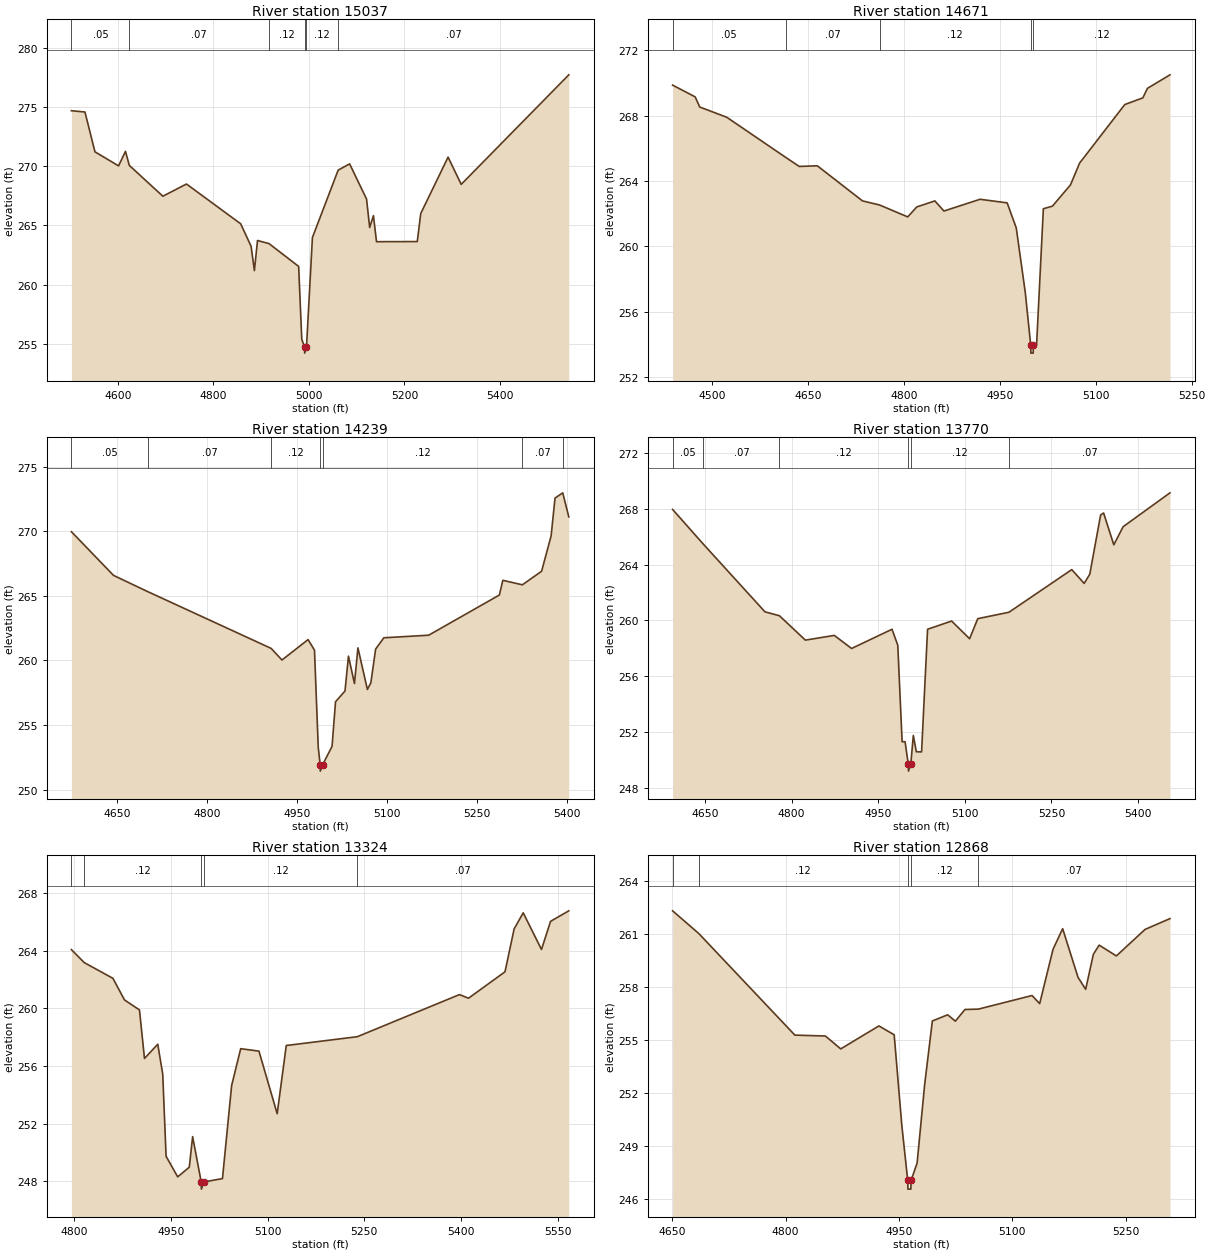
Type RM Length L Ch R = 1 ,15037   ,366,366,366
BEGIN DESCRIPTION:
XS7471
END DESCRIPTION:
XS GIS Cut Line= 2
        2437813.     13633562.07      2438621.17     13632904.96
#Sta/Elev= 30
  4502.5  274.69  4530.9  274.58  4551.8  271.22  4601.3  270.03  4615.7  271.26
  4623.8  270.07    4694  267.47  4743.5   268.5    4857  265.14  4878.8  263.24
  4885.7  261.19  4892.2  263.73  4916.3  263.47  4978.4  261.54  4984.9   255.4
  4990.7  254.72    4991  254.22  4994.8  254.72  5007.2  263.98  5061.1  269.67
  5085.1   270.2  5120.6  267.23  5127.1  264.83    5135  265.83  5141.4  263.63
  5226.8  263.64  5234.1  266.01  5291.3  270.77  5318.8  268.47  5544.1  277.72
#Mann= 6 ,-1 , 0
  4502.5     .05       0  4623.8     .07       0  4916.3     .12       0
  4990.7     .05       0  4994.8     .12       0  5061.1     .07       0
Bank Sta=4990.7,4994.8
XS Rating Curve= 0 ,0
Exp/Cntr=0.3,0.1

Type RM Length L Ch R = 1 ,14671   ,432,432,432
BEGIN DESCRIPTION:
Stream0683 29.0
END DESCRIPTION:
XS GIS Cut Line= 3
      2438075.01     13633724.99        2438475.       13633325.
        2438625.       13633175.
#Sta/Elev= 30
  4438.2  269.88  4473.5  269.16  4480.6  268.54    4523  267.91  4614.9  265.46
  4636.2   264.9  4664.5  264.94  4735.2  262.79  4761.9  262.54  4805.9  261.81
    4820  262.42  4848.3  262.79  4862.5  262.17    4919  262.89  4961.4  262.67
  4975.6  261.14  4989.7  257.19  4998.2  253.97  4998.5  253.47  5002.1  253.47
  5002.4  253.97  5007.4  253.97    5018  262.31  5032.2  262.47  5060.4  263.77
  5074.6   265.1  5145.3  268.69  5173.6   269.1  5180.7  269.68    5216  270.51
#Mann= 5 ,-1 , 0
  4438.2     .05       0  4614.9     .07       0  4761.9     .12       0
  4998.2     .05       0  5002.4     .12       0
Bank Sta=4998.2,5002.4
XS Rating Curve= 0 ,0
Exp/Cntr=0.3,0.1

Type RM Length L Ch R = 1 ,14239   ,469,469,469
BEGIN DESCRIPTION:
Stream0683 28.0
END DESCRIPTION:
XS GIS Cut Line= 3
      2438125.01       13633825.        2438525.       13633675.
        2438875.       13633475.
#Sta/Elev= 30
  4573.2  269.96  4643.5  266.58  4700.3  265.33  4906.6  260.93  4924.7  260.03
  4968.3  261.61    4979  260.79  4985.3  253.24  4988.5  251.93  4988.7  251.43
  4992.7  251.93  5008.3  253.35  5014.1   256.8  5029.9  257.63  5035.7  260.33
  5045.7  258.21  5051.5  260.97  5067.3  257.75  5073.1  258.27    5081  260.87
  5094.7  261.75  5169.6  261.95  5287.6  265.06  5293.4   266.2    5326  265.85
  5358.1   266.9    5374  269.64  5380.5  272.56  5393.4  272.97  5403.5  271.11
#Mann= 7 ,-1 , 0
  4573.2     .05       0  4700.3     .07       0  4906.6     .12       0
  4988.5     .05       0  4992.7     .12       0    5326     .07       0
  5393.4     .12       0
Bank Sta=4988.5,4992.7
XS Rating Curve= 0 ,0
Exp/Cntr=0.3,0.1

Type RM Length L Ch R = 1 ,13770   ,446,446,446
BEGIN DESCRIPTION:
Stream0683 27.0
END DESCRIPTION:
XS GIS Cut Line= 3
      2438225.01       13634075.        2438625.       13634075.
      2439068.53     13633947.77
#Sta/Elev= 30
  4593.9  267.96  4647.1  265.47  4753.9  260.61  4778.9  260.33  4823.9  258.58
  4873.9  258.92  4903.9  257.98  4973.9  259.36  4983.9  258.21  4991.4  251.29
  4996.5  251.29  5002.1  249.68  5002.4  249.18  5006.4  249.68  5010.8  251.74
    5016  250.57  5025.1  250.56  5035.5  259.36  5077.1  259.95  5108.3  258.68
  5122.4  260.12  5176.4  260.58  5285.2  263.64  5306.7  262.65  5316.4  263.31
  5335.2  267.56  5340.4   267.7    5358  265.42  5374.2  266.72  5455.3  269.15
#Mann= 6 ,-1 , 0
  4593.9     .05       0  4647.1     .07       0  4778.9     .12       0
  5002.1     .05       0  5006.4     .12       0  5176.4     .07       0
Bank Sta=5002.1,5006.4
XS Rating Curve= 0 ,0
Exp/Cntr=0.3,0.1

Type RM Length L Ch R = 1 ,13324   ,456,456,456
BEGIN DESCRIPTION:
Stream0683 26.0
END DESCRIPTION:
XS GIS Cut Line= 3
      2438425.03     13634474.99        2438625.       13634425.
      2439024.99     13634025.01
#Sta/Elev= 30
  4795.7  264.08  4815.6  263.18  4860.1  262.09  4878.1  260.59  4901.3   259.9
  4909.1  256.53  4929.7  257.52  4937.4  255.45  4942.6  249.75  4960.6  248.32
  4978.6  248.99  4983.8  251.11  4997.1  247.97  4997.4  247.47  5001.4  247.97
  5030.1   248.2  5044.3  254.65  5058.4  257.21  5086.7  257.04    5115   252.7
  5129.1  257.43  5239.3  258.04  5397.8  260.96  5411.9  260.71  5468.5  262.54
  5482.7  265.52  5496.8  266.63  5525.1  264.09  5539.2  266.04  5567.5  266.77
#Mann= 5 ,-1 , 0
  4795.7     .07       0  4815.6     .12       0  4997.1     .05       0
  5001.4     .12       0  5239.3     .07       0
Bank Sta=4997.1,5001.4
XS Rating Curve= 0 ,0
Exp/Cntr=0.3,0.1

Type RM Length L Ch R = 1 ,12868   ,464,464,464
BEGIN DESCRIPTION:
Stream0683 25.0
END DESCRIPTION:
XS GIS Cut Line= 3
      2438574.95     13634725.01        2438925.       13634675.
      2439224.96     13634625.01
#Sta/Elev= 30
  4650.7  262.32  4685.5  261.03  4812.4  255.29  4852.8  255.24    4873  254.51
  4923.5  255.81  4943.7  255.31  4953.8  250.19  4961.6  247.08  4961.9  246.58
  4965.8  246.58  4966.1  247.08    4974  248.05  4984.1  252.53  4994.2  256.09
  5014.4  256.44  5024.6  256.08  5037.3  256.74    5055  256.76    5126  257.53
  5136.1  257.07  5153.8  260.15  5166.5  261.31  5186.8  258.56  5196.9  257.88
  5207.1  259.86  5214.7  260.38  5237.5  259.77  5275.5  261.27  5308.4  261.88
#Mann= 5 ,-1 , 0
  4650.7     .07       0  4685.5     .12       0  4961.6     .05       0
  4966.1     .12       0    5055     .07       0
Bank Sta=4961.6,4966.1
XS Rating Curve= 0 ,0
Exp/Cntr=0.3,0.1

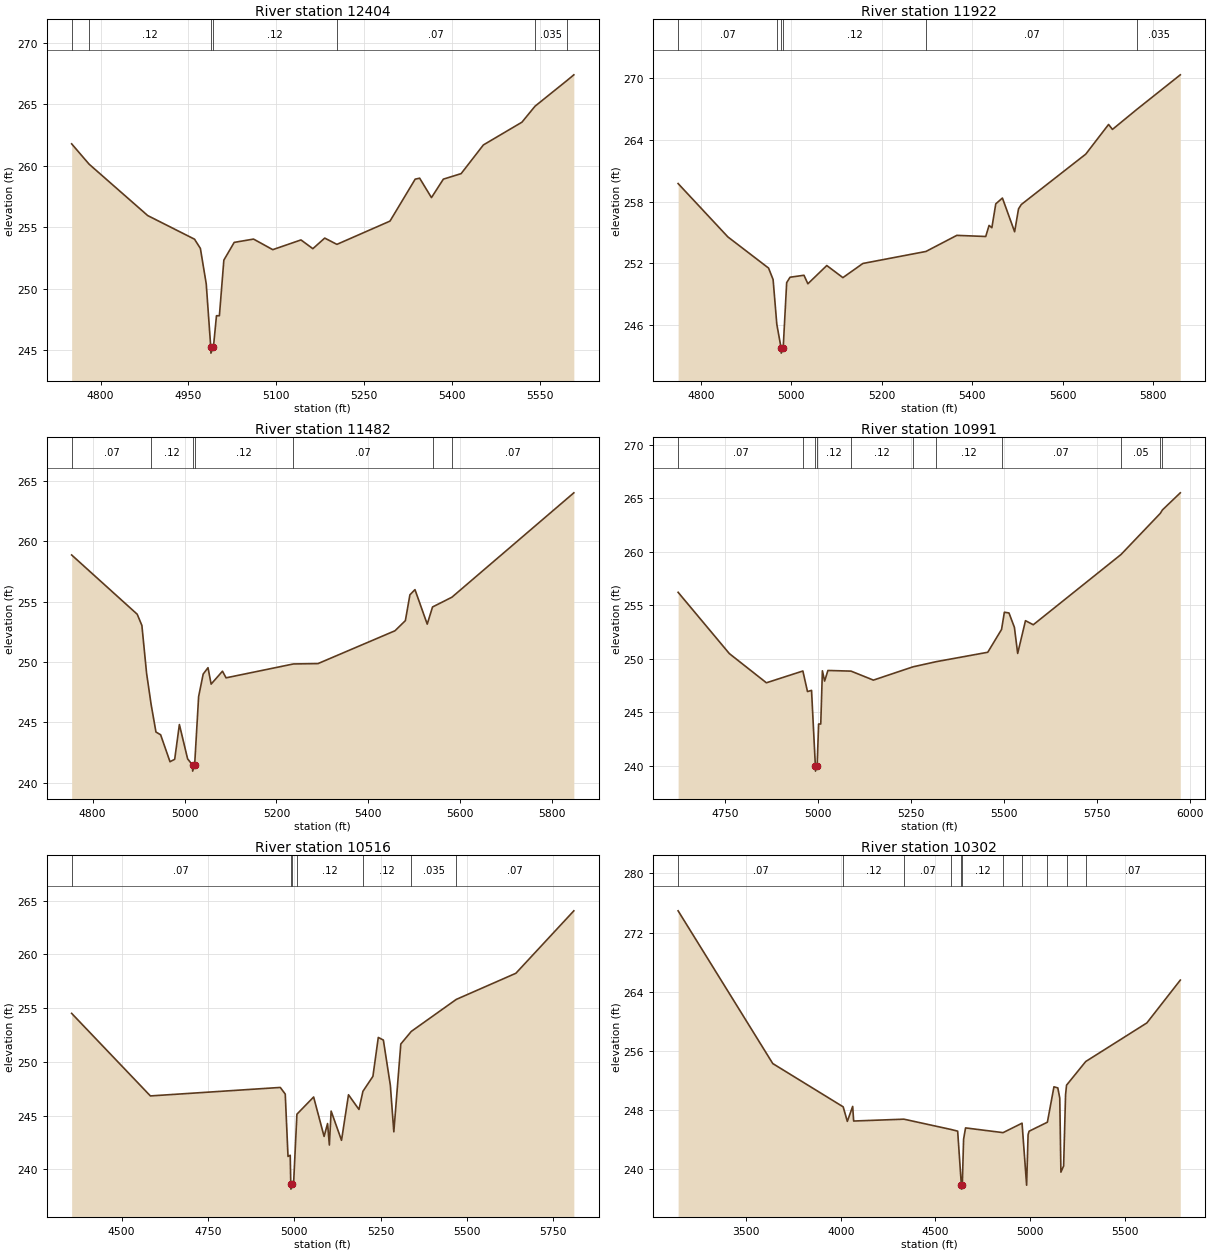
Type RM Length L Ch R = 1 ,12404   ,482,482,482
BEGIN DESCRIPTION:
Stream0683 24.0
END DESCRIPTION:
XS GIS Cut Line= 3
      2438575.03       13635075.        2438825.       13635075.
      2439424.95     13634975.01
#Sta/Elev= 30
  4750.4  261.79  4780.2  260.14  4880.4  255.96  4960.4  254.04  4970.4  253.29
  4980.4  250.41  4988.1  245.28  4988.4  244.78  4992.7  245.28  4997.9  247.82
  5002.9  247.82  5010.5  252.34  5028.2  253.78  5061.2  254.05  5094.1  253.19
  5142.3  253.98  5162.6  253.27  5182.9  254.13  5203.7  253.62  5294.4  255.51
  5337.5  258.92  5345.1     259  5365.3  257.42  5385.6  258.92    5416  259.37
    5454   261.7  5519.9  263.55  5542.3  264.85  5597.2  266.95  5608.6   267.4
#Mann= 7 ,-1 , 0
  4750.4     .07       0  4780.2     .12       0  4988.1     .05       0
  4992.7     .12       0  5203.7     .07       0  5542.3    .035       0
  5597.2     .07       0
Bank Sta=4988.1,4992.7
XS Rating Curve= 0 ,0
Exp/Cntr=0.3,0.1

Type RM Length L Ch R = 1 ,11922   ,440,440,440
BEGIN DESCRIPTION:
Stream0683 23.0
END DESCRIPTION:
XS GIS Cut Line= 3
      2438574.98       13635525.        2438825.       13635525.
      2439525.04     13635024.97
#Sta/Elev= 30
  4749.5  259.75  4859.5  254.55  4949.5  251.51  4959.5  250.39  4967.7  246.04
  4977.2  243.72  4977.5  243.22  4981.8  243.72  4989.5  250.09    4997  250.62
  5027.8  250.81  5036.4  249.98  5078.2  251.76  5113.8  250.58    5158  251.96
  5297.4  253.13  5365.7   254.7  5429.6  254.59    5437  255.67  5443.2  255.45
  5451.8  257.77  5466.5  258.34  5493.5  255.05  5502.1  257.28  5508.3  257.71
  5650.8  262.62  5701.2  265.51  5709.8  265.03  5763.7  266.98  5859.8  270.35
#Mann= 6 ,-1 , 0
  4749.5     .07       0  4967.7     .12       0  4977.2     .05       0
  4981.8     .12       0  5297.4     .07       0  5763.7    .035       0
Bank Sta=4977.2,4981.8
XS Rating Curve= 0 ,0
Exp/Cntr=0.3,0.1

Type RM Length L Ch R = 1 ,11482   ,491,491,491
BEGIN DESCRIPTION:
Stream0683 22.0
END DESCRIPTION:
XS GIS Cut Line= 3
      2438575.04     13635924.99        2438825.       13635875.
      2439625.03     13635624.99
#Sta/Elev= 30
  4754.3  258.87    4897  253.96  4907.2  253.03  4917.4  249.07  4927.2  246.51
  4937.8   244.2    4948  243.97  4968.4  241.74  4978.6  241.94  4988.8  244.82
  5006.7  241.98  5017.4  241.46  5017.7  240.96    5022  241.46  5030.7  247.14
  5040.6     249  5051.1  249.53  5057.9  248.17  5082.6  249.24  5090.4  248.69
    5237  249.84  5290.5  249.87  5458.1  252.59  5480.7  253.43  5490.6  255.57
  5501.6     256  5528.3  253.14  5539.8  254.56    5582  255.37  5847.4  264.02
#Mann= 7 ,-1 , 0
  4754.3     .07       0  4927.2     .12       0  5017.4     .05       0
    5022     .12       0    5237     .07       0  5539.8     .12       0
    5582     .07       0
Bank Sta=5017.4,5022
XS Rating Curve= 0 ,0
Exp/Cntr=0.3,0.1

Type RM Length L Ch R = 1 ,10991   ,475,475,475
BEGIN DESCRIPTION:
Stream0683 21.0
END DESCRIPTION:
XS GIS Cut Line= 3
      2438574.97     13636174.99        2438925.       13636325.
      2439724.96     13635775.03
#Sta/Elev= 30
  4623.3   256.2  4761.1  250.48  4860.9  247.75  4959.1  248.85  4971.5  246.93
  4982.4  247.04  4992.7     240    4993   239.5  4997.5     240  5001.4   243.9
  5007.2   243.9  5011.6  248.87  5017.6  247.91  5026.5   248.9  5088.6  248.84
  5148.9     248  5255.5  249.24  5317.7  249.72  5456.7   250.6  5493.8  252.73
  5501.4  254.34  5513.8  254.27  5528.4  252.93  5537.2  250.49  5558.2  253.55
  5579.2  253.17  5815.3  259.73    5921  263.57  5926.7  263.89  5974.9  265.49
#Mann= 11 ,-1 , 0
  4623.3     .07       0  4959.1     .12       0  4992.7     .05       0
  4997.5     .12       0  5088.6     .12       0  5255.5     .12       0
  5317.7     .12       0  5493.8     .07       0  5815.3     .05       0
    5921     .07       0  5926.7     .05       0
Bank Sta=4992.7,4997.5
XS Rating Curve= 0 ,0
Exp/Cntr=0.3,0.1

Type RM Length L Ch R = 1 ,10516   ,214,214,214
BEGIN DESCRIPTION:
Stream0683 20.0
END DESCRIPTION:
XS GIS Cut Line= 3
      2438525.02     13636325.02        2439025.       13636725.
      2439831.19     13636610.21
#Sta/Elev= 30
  4355.4  254.51  4583.5  246.83  4959.7  247.62  4974.1     247  4982.1   241.2
  4988.5  241.31  4990.1  238.66  4990.4  238.16  4994.9  238.66  4998.2  238.66
  5007.9  245.13  5056.3  246.73  5086.6  243.06  5096.7  244.26  5101.9  242.26
    5107  245.42  5137.1   242.7  5157.3  246.94  5187.6  245.57  5199.1  247.26
    5228  248.65  5243.6  252.27  5258.3  252.03  5278.5  247.83  5288.6  243.49
  5308.8  251.66  5339.1  252.83  5469.5  255.81  5642.1  258.24    5810  264.05
#Mann= 7 ,-1 , 0
  4355.4     .07       0  4990.1     .05       0  4994.9     .07       0
  5007.9     .12       0  5199.1     .12       0  5339.1    .035       0
  5469.5     .07       0
Bank Sta=4990.1,4994.9
XS Rating Curve= 0 ,0
Exp/Cntr=0.3,0.1

Type RM Length L Ch R = 1 ,10302   ,397,397,397
BEGIN DESCRIPTION:
E21258
END DESCRIPTION:
XS GIS Cut Line= 3
      2437286.01     13636400.73      2439116.72     13636935.19
      2439847.74     13636775.48
#Sta/Elev= 30
  3139.5  274.95  3640.1  254.29  4012.3  248.44  4034.3  246.47  4062.5   248.5
  4067.7  246.52  4333.6  246.77  4583.9  245.37  4617.7  245.15  4637.3  237.81
  4637.6  237.31  4642.1  237.81    4649  244.06  4659.4  245.59  4857.9  244.95
  4958.1  246.23  4982.3  237.84    4990  244.67  4995.2  245.14  5092.1  246.36
  5126.8  251.15  5147.2     251  5157.5  249.63  5163.6  239.61  5177.9  240.44
  5188.2  250.08  5193.4  251.37  5294.8  254.57  5618.1  259.79  5794.9  265.58
#Mann= 11 ,-1 , 0
  3139.5     .07       0  4012.3     .12       0  4333.6     .07       0
  4583.9     .12       0  4637.3     .05       0  4642.1     .12       0
  4857.9     .12       0  4958.1     .12       0  5092.1     .05       0
  5193.4    .035       0  5294.8     .07       0
Bank Sta=4637.3,4642.1
XS Rating Curve= 0 ,0
Exp/Cntr=0.3,0.1

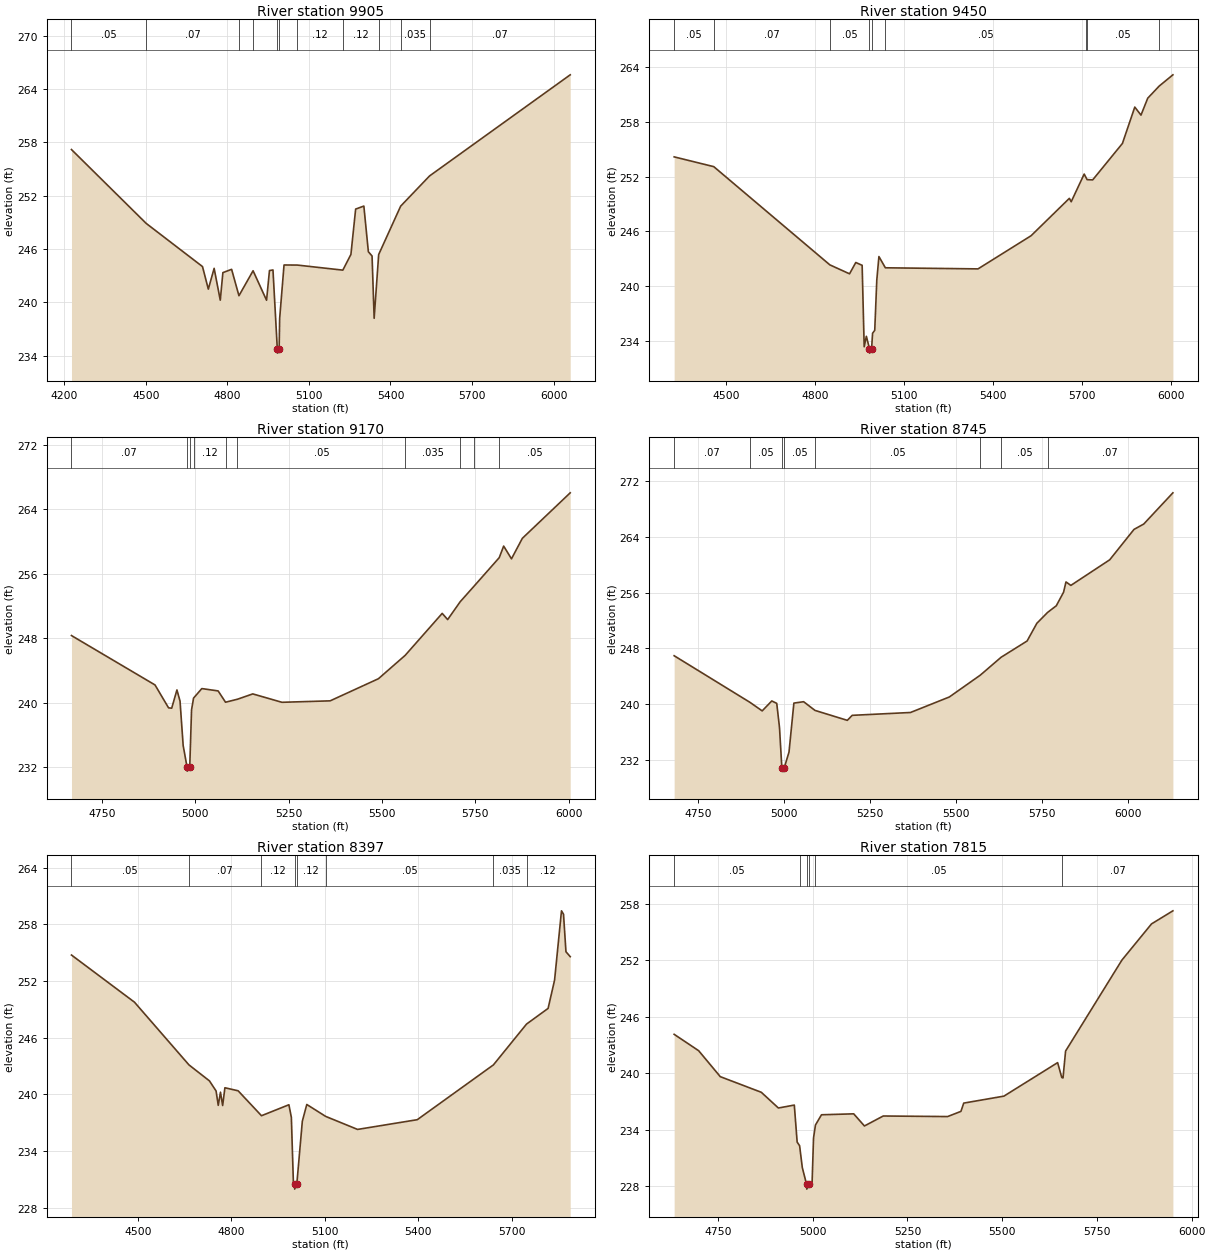
Type RM Length L Ch R = 1 ,9905    ,455,455,455
BEGIN DESCRIPTION:
Stream0683 19.0
END DESCRIPTION:
XS GIS Cut Line= 3
      2438125.04     13637474.98      2438977.75     13637147.03
      2439839.95     13636821.82
#Sta/Elev= 30
  4226.3  257.18  4501.2  248.87  4708.4  244.01  4729.8  241.47  4751.2  243.81
  4773.8  240.23  4783.4  243.33  4815.5   243.7  4842.5  240.73  4894.5  243.54
  4944.1  240.22  4954.8  243.56  4967.7  243.63  4983.6  234.77  4984.1  234.27
  4990.4  234.77  4992.3  238.17  5008.4  244.19  5057.2  244.18  5224.8  243.61
  5254.5  245.38  5271.9  250.48  5302.1  250.82  5318.7  245.68  5332.3   245.2
    5340  238.19  5356.6  245.36  5437.5  250.81  5543.8  254.21  6061.4  265.59
#Mann= 11 ,-1 , 0
  4226.3     .05       0  4501.2     .07       0  4842.5     .12       0
  4894.5     .12       0  4983.6     .05       0  4990.4     .12       0
  5057.2     .12       0  5224.8     .12       0  5356.6     .05       0
  5437.5    .035       0  5543.8     .07       0
Bank Sta=4983.6,4990.4
XS Rating Curve= 0 ,0
Exp/Cntr=0.3,0.1

Type RM Length L Ch R = 1 ,9450    ,280,280,280
BEGIN DESCRIPTION:
Stream0683 18.0
END DESCRIPTION:
XS GIS Cut Line= 3
      2438455.91     13638062.17      2439000.44     13637540.32
      2439740.85     13636981.23
#Sta/Elev= 30
  4323.5  254.15  4457.1  253.08  4848.6  242.33    4915  241.35  4936.1  242.59
  4957.5  242.28  4964.4  233.37  4971.7  234.51  4982.3  233.17  4982.8  232.67
  4989.4  233.17  4992.7  234.85    5000  235.16  5006.9  240.66  5014.1  243.24
  5035.8  242.01  5348.3  241.89  5527.3  245.52  5656.3  249.61  5662.6  249.24
  5706.3  252.27  5712.9  251.86  5716.1  251.66    5735  251.63  5835.3  255.62
    5877   259.6  5897.9  258.72  5920.6  260.57    5959  261.89  6005.5  263.13
#Mann= 9 ,-1 , 0
  4323.5     .05       0  4457.1     .07       0  4848.6     .05       0
  4982.3     .05       0  4989.4     .05       0  5035.8     .05       0
  5712.9     .07       0  5716.1     .05       0    5959     .07       0
Bank Sta=4982.3,4989.4
XS Rating Curve= 0 ,0
Exp/Cntr=0.3,0.1

Type RM Length L Ch R = 1 ,9170    ,425,425,425
BEGIN DESCRIPTION:
Stream0683 17.0
END DESCRIPTION:
XS GIS Cut Line= 3
      2438774.96     13637975.02        2439075.       13637825.
      2439875.03     13637224.97
#Sta/Elev= 30
  4668.5  248.33  4892.2  242.21  4928.5  239.37  4936.9  239.33  4950.9  241.59
  4959.2  240.21  4967.6  234.69    4978  232.03  4978.5  231.53  4985.2  232.03
    4990  239.12  4995.4  240.58  5017.5  241.76  5061.2  241.47    5081  240.07
    5113  240.44    5154   241.1  5232.1  240.06  5361.2  240.24  5490.4  242.98
  5562.1  245.88  5661.2  251.08  5675.8  250.31  5709.5  252.53  5745.5   254.4
    5814  257.99  5825.8  259.42  5846.7  257.84  5875.8  260.38    6004  266.02
#Mann= 10 ,-1 , 0
  4668.5     .07       0    4978     .05       0  4985.2     .07       0
  4995.4     .12       0    5081     .07       0    5113     .05       0
  5562.1    .035       0  5709.5     .05       0  5745.5     .07       0
    5814     .05       0
Bank Sta=4978,4985.2
XS Rating Curve= 0 ,0
Exp/Cntr=0.3,0.1

Type RM Length L Ch R = 1 ,8745    ,348,348,348
BEGIN DESCRIPTION:
Stream0683 16.0
END DESCRIPTION:
XS GIS Cut Line= 3
      2439074.97     13638325.02        2439325.       13638125.
      2440125.03     13637324.97
#Sta/Elev= 30
  4679.8  246.92  4900.1  240.23    4936  238.99    4964  240.42  4978.4  240.07
  4986.4  236.61  4993.2  230.83  4993.7  230.33  5000.4  230.83  5014.1  233.07
  5028.3  240.11  5056.6  240.31  5089.7  239.06  5183.8  237.63    5198  238.35
  5367.7  238.76  5480.8  240.99  5570.9  244.13  5631.4   246.7  5707.1  249.04
  5735.4  251.58  5766.8  253.15    5792   254.1  5813.2  256.05  5820.2  257.53
  5834.4  257.03  5947.5  260.71  6018.2  265.08  6046.5  265.85  6131.4  270.34
#Mann= 8 ,-1 , 0
  4679.8     .07       0  4900.1     .05       0  4993.2     .05       0
  5000.4     .05       0  5089.7     .05       0  5570.9    .035       0
  5631.4     .05       0  5766.8     .07       0
Bank Sta=4993.2,5000.4
XS Rating Curve= 0 ,0
Exp/Cntr=0.3,0.1

Type RM Length L Ch R = 1 ,8397    ,582,582,582
BEGIN DESCRIPTION:
Stream0683 15.0
END DESCRIPTION:
XS GIS Cut Line= 3
      2439030.68     13638886.59      2439431.55     13638478.16
        2440225.       13637825.
#Sta/Elev= 30
  4287.2  254.74  4489.3  249.75  4664.1  243.11  4729.8  241.42  4751.1  240.35
  4758.1  238.83  4765.2  240.22  4772.2  238.81  4779.4  240.69  4821.8  240.37
  4896.8  237.73  4984.7  238.89  4992.6  237.56  4999.1  230.66  5002.8  230.46
  5003.3  229.96    5010  230.46  5027.8  237.15  5042.1  238.92  5102.6  237.66
    5205  236.28  5396.5  237.31  5640.8  243.11    5747  247.43  5816.2  249.09
    5837  252.08  5859.2  259.42  5865.7  259.06  5873.5  255.09  5887.2  254.57
#Mann= 8 ,-1 , 0
  4287.2     .05       0  4664.1     .07       0  4896.8     .12       0
  5002.8     .05       0    5010     .12       0  5102.6     .05       0
  5640.8    .035       0    5747     .12       0
Bank Sta=5002.8,5010
XS Rating Curve= 0 ,0
Exp/Cntr=0.3,0.1

Type RM Length L Ch R = 1 ,7815    ,464,464,464
BEGIN DESCRIPTION:
Stream0683 14.0
END DESCRIPTION:
XS GIS Cut Line= 3
      2439574.96     13638925.02        2439875.       13638725.
      2440524.97     13638025.03
#Sta/Elev= 30
  4634.7  244.13  4699.3  242.39  4756.4  239.63  4864.6  237.97  4909.7   236.3
  4951.7  236.61  4959.2  232.68  4965.7  232.29  4972.8  229.97  4984.1  228.18
  4984.6  227.68  4991.4  228.18  4998.7  228.47  5002.4  233.11  5007.5  234.49
  5023.4  235.58  5108.4  235.68  5136.7  234.39  5186.3  235.45  5356.1  235.39
  5391.3  235.94  5398.7  236.82  5504.7  237.56  5646.4  241.12  5657.3  239.54
  5660.6  239.49  5667.4  242.35  5815.9  252.01  5894.1  255.86  5950.5  257.25
#Mann= 6 ,-1 , 0
  4634.7     .05       0  4965.7     .12       0  4984.1     .05       0
  4991.4     .12       0  5007.5     .05       0  5657.3     .07       0
Bank Sta=4984.1,4991.4
XS Rating Curve= 0 ,0
Exp/Cntr=0.3,0.1

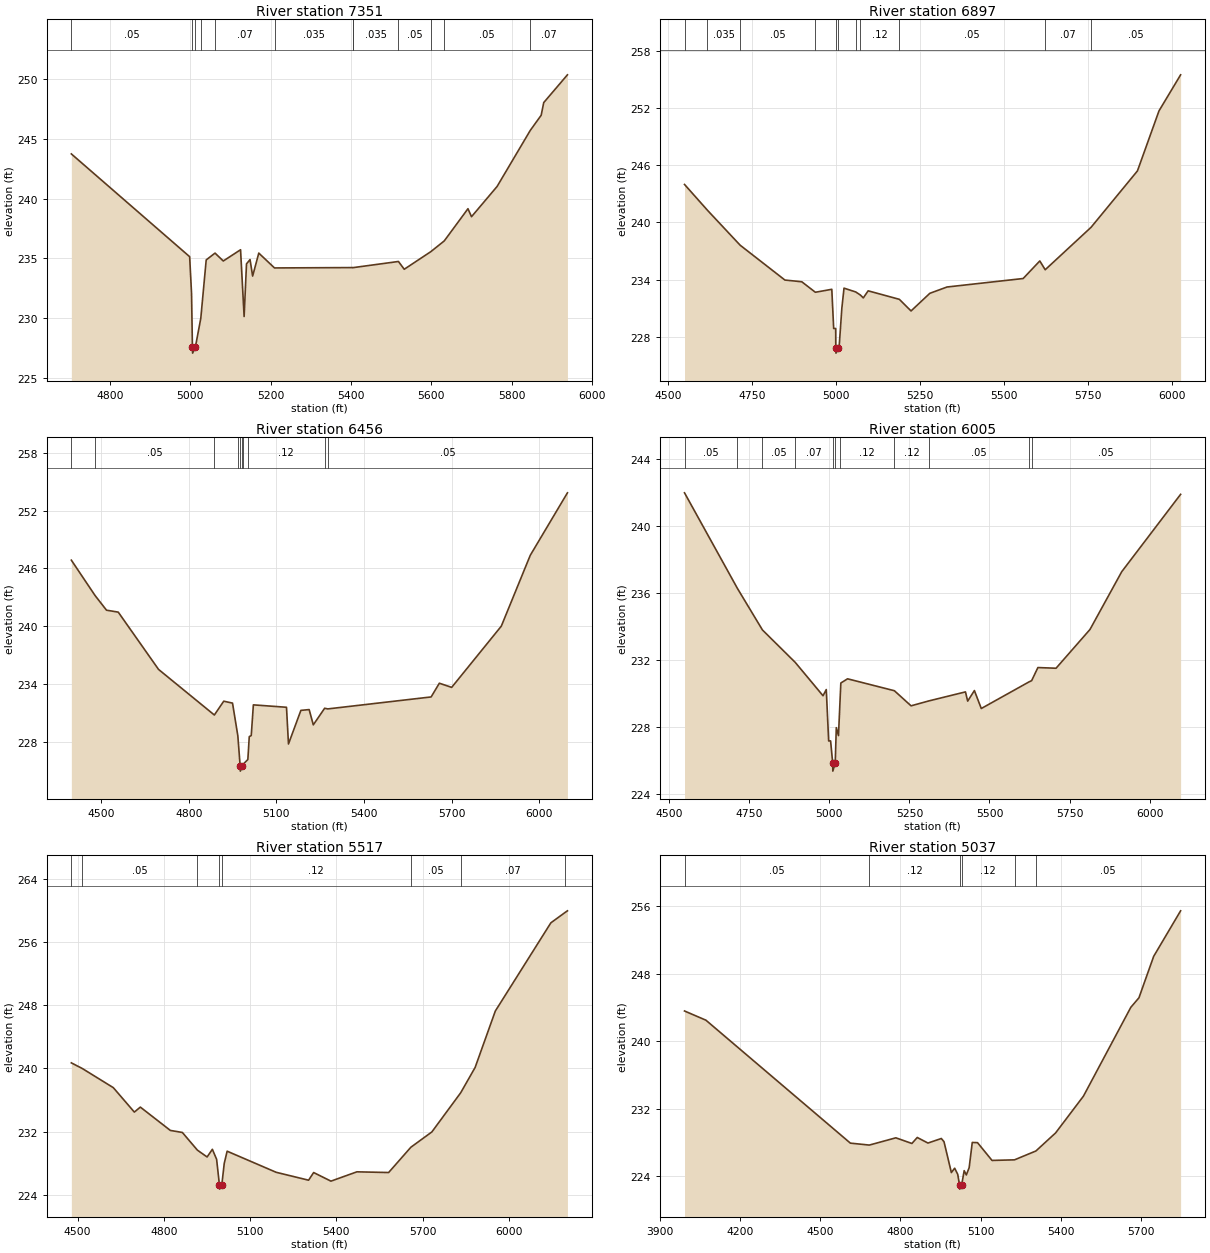
Type RM Length L Ch R = 1 ,7351    ,454,454,454
BEGIN DESCRIPTION:
Stream0683 13.0
END DESCRIPTION:
XS GIS Cut Line= 3
      2439825.03     13639174.98        2440075.       13639025.
      2440574.99     13638225.01
#Sta/Elev= 30
  4704.2  243.73  4998.7  235.14  5003.4  232.07  5005.6  227.58  5006.1  227.08
  5012.9  227.58  5026.4  229.98  5039.9  234.87  5061.9  235.44  5082.4  234.78
  5125.4  235.72  5134.3  230.14  5140.2  234.54    5149   234.9  5155.5  233.52
  5170.8  235.44  5209.9   234.2  5404.3  234.23  5404.5  234.22  5518.4  234.74
  5532.9  234.09    5599  235.56  5632.5  236.46  5691.5  239.15  5700.3  238.48
    5764  241.01  5846.5  245.69  5873.7  246.96  5880.1  248.02  5939.1  250.34
#Mann= 12 ,-1 , 0
  4704.2     .05       0  5005.6     .05       0  5012.9     .05       0
  5026.4    .035       0  5061.9     .07       0  5209.9    .035       0
  5404.3     .05       0  5404.5    .035       0  5518.4     .05       0
    5599    .035       0  5632.5     .05       0  5846.5     .07       0
Bank Sta=5005.6,5012.9
XS Rating Curve= 0 ,0
Exp/Cntr=0.3,0.1

Type RM Length L Ch R = 1 ,6897    ,441,441,441
BEGIN DESCRIPTION:
Stream0683 12.0
END DESCRIPTION:
XS GIS Cut Line= 3
      2440025.01       13639425.        2440425.       13639225.
      2441225.02     13638574.99
#Sta/Elev= 30
  4548.2  243.98  4616.4  241.28    4714  237.61  4847.3  233.96  4897.6  233.78
    4938  232.68    4987  232.99  4992.6  228.88  4998.6  228.88  4998.9   226.8
  4999.4   226.3  5006.2   226.8    5009  227.02    5017  231.03  5023.4  233.11
  5058.4  232.71  5072.1  232.39  5080.9  232.09  5095.3  232.83  5188.2  231.94
  5223.1  230.72  5279.1  232.57  5330.2  233.23  5557.1  234.12  5606.7  235.96
  5622.8  235.04  5759.5  239.49  5897.6   245.4  5961.8  251.69  6026.2  255.47
#Mann= 11 ,-1 , 0
  4548.2     .05       0  4616.4    .035       0    4714     .05       0
    4938     .12       0  4998.9     .05       0  5006.2     .12       0
  5058.4     .12       0  5072.1     .12       0  5188.2     .05       0
  5622.8     .07       0  5759.5     .05       0
Bank Sta=4998.9,5006.2
XS Rating Curve= 0 ,0
Exp/Cntr=0.3,0.1

Type RM Length L Ch R = 1 ,6456    ,451,451,451
BEGIN DESCRIPTION:
Stream0683 11.0
END DESCRIPTION:
XS GIS Cut Line= 3
      2439974.98       13639525.        2440575.       13639575.
      2441325.01     13638774.99
#Sta/Elev= 30
  4398.1  246.86  4479.3   243.2  4518.5  241.68  4558.7  241.48  4696.7  235.55
  4887.8  230.83  4919.9  232.26    4950  232.06  4968.2  228.68  4976.2  225.52
  4976.7  225.02  4984.1  225.52  4986.3  225.73  5002.5  226.22  5007.3  228.59
  5014.1   228.7  5021.4  231.88  5134.8  231.63  5141.6  227.83  5184.1  231.31
  5212.4  231.39  5226.6  229.81  5265.5  231.53  5276.1  231.46  5630.1   232.7
  5658.2  234.12  5700.4  233.69  5870.4  240.03  5969.5  247.36  6096.8  253.83
#Mann= 10 ,-1 , 0
  4398.1    .035       0  4479.3     .05       0  4887.8     .12       0
  4968.2     .07       0  4976.2     .05       0  4984.1     .07       0
  4986.3     .12       0  5002.5     .12       0  5265.5     .07       0
  5276.1     .05       0
Bank Sta=4976.2,4984.1
XS Rating Curve= 0 ,0
Exp/Cntr=0.3,0.1

Type RM Length L Ch R = 1 ,6005    ,488,488,488
BEGIN DESCRIPTION:
Stream0683 10.0
END DESCRIPTION:
XS GIS Cut Line= 3
      2440175.02       13640025.        2440625.       13639975.
      2441424.98     13639225.02
#Sta/Elev= 30
  4547.7  241.97  4712.8  236.28  4791.1   233.8  4893.4  231.87  4980.3  229.88
  4990.4  230.25  4997.9  227.19  5003.9  227.19  5010.4  225.89  5010.9  225.39
  5018.4  225.89  5021.7  227.98  5028.5  227.51    5033  229.41  5035.9  230.64
  5056.9  230.89  5203.1  230.18  5255.2  229.28  5310.2  229.57  5425.1  230.11
    5432  229.56    5453  230.19  5474.5  229.12    5623   230.7  5631.8  230.78
  5651.3  231.56    5708  231.52    5814  233.83  5913.1  237.27    6097  241.88
#Mann= 11 ,-1 , 0
  4547.7     .05       0  4712.8     .07       0  4791.1     .05       0
  4893.4     .07       0  5010.4     .05       0  5018.4     .07       0
    5033     .12       0  5203.1     .12       0  5310.2     .05       0
    5623     .07       0  5631.8     .05       0
Bank Sta=5010.4,5018.4
XS Rating Curve= 0 ,0
Exp/Cntr=0.3,0.1

Type RM Length L Ch R = 1 ,5517    ,480,480,480
BEGIN DESCRIPTION:
Stream0683 9.0
END DESCRIPTION:
XS GIS Cut Line= 3
      2440225.02     13640275.01        2440725.       13640425.
      2441925.05       13640325.
#Sta/Elev= 30
  4478.1  240.69  4516.4  239.97  4624.2  237.55  4697.3  234.46  4718.2  235.09
  4822.6  232.14  4864.4  231.88  4916.8  229.64  4950.5  228.78  4968.8  229.75
  4983.6  228.48  4993.5  225.21    4994  224.71  5001.5  225.21  5010.1  227.96
  5020.2  229.51  5190.8  226.84  5303.6  225.84  5321.2  226.81  5381.4  225.72
  5471.7   226.9  5582.1  226.81  5659.5  230.01  5732.6  231.95  5832.8   236.9
  5883.1  240.11  5953.4  247.25  6146.6  258.41  6196.4  259.73  6204.3  259.93
#Mann= 8 ,-1 , 0
  4478.1     .07       0  4516.4     .05       0  4916.8     .12       0
  4993.5     .05       0  5001.5     .12       0  5659.5     .05       0
  5832.8     .07       0  6196.4    .035       0
Bank Sta=4993.5,5001.5
XS Rating Curve= 0 ,0
Exp/Cntr=0.3,0.1

Type RM Length L Ch R = 1 ,5037    ,463,463,463
BEGIN DESCRIPTION:
Stream0683 8.0
END DESCRIPTION:
XS GIS Cut Line= 3
      2440025.04       13640725.        2441025.       13640725.
      2441825.03     13640424.99
#Sta/Elev= 30
  3992.7  243.61  4072.7  242.52  4612.7  227.95  4683.5  227.72  4782.7  228.58
  4842.7  227.91  4862.7  228.62  4902.7  227.96  4952.7   228.5  4962.7  228.12
  4990.2  224.46  5002.5  224.98    5014  224.25  5020.7     223  5021.2   222.5
  5028.7     223  5038.1  224.69  5046.1  224.18  5056.7  225.04  5068.3  228.03
  5087.9  228.01  5142.2   225.9  5226.2  225.97  5306.2  227.02  5379.8  229.16
  5483.9  233.52  5661.1  244.05  5691.3  245.17  5746.5  250.09  5847.1  255.48
#Mann= 6 ,-1 , 0
  3992.7     .05       0  4683.5     .12       0  5020.7     .05       0
  5028.7     .12       0  5226.2     .07       0  5306.2     .05       0
Bank Sta=5020.7,5028.7
XS Rating Curve= 0 ,0
Exp/Cntr=0.3,0.1

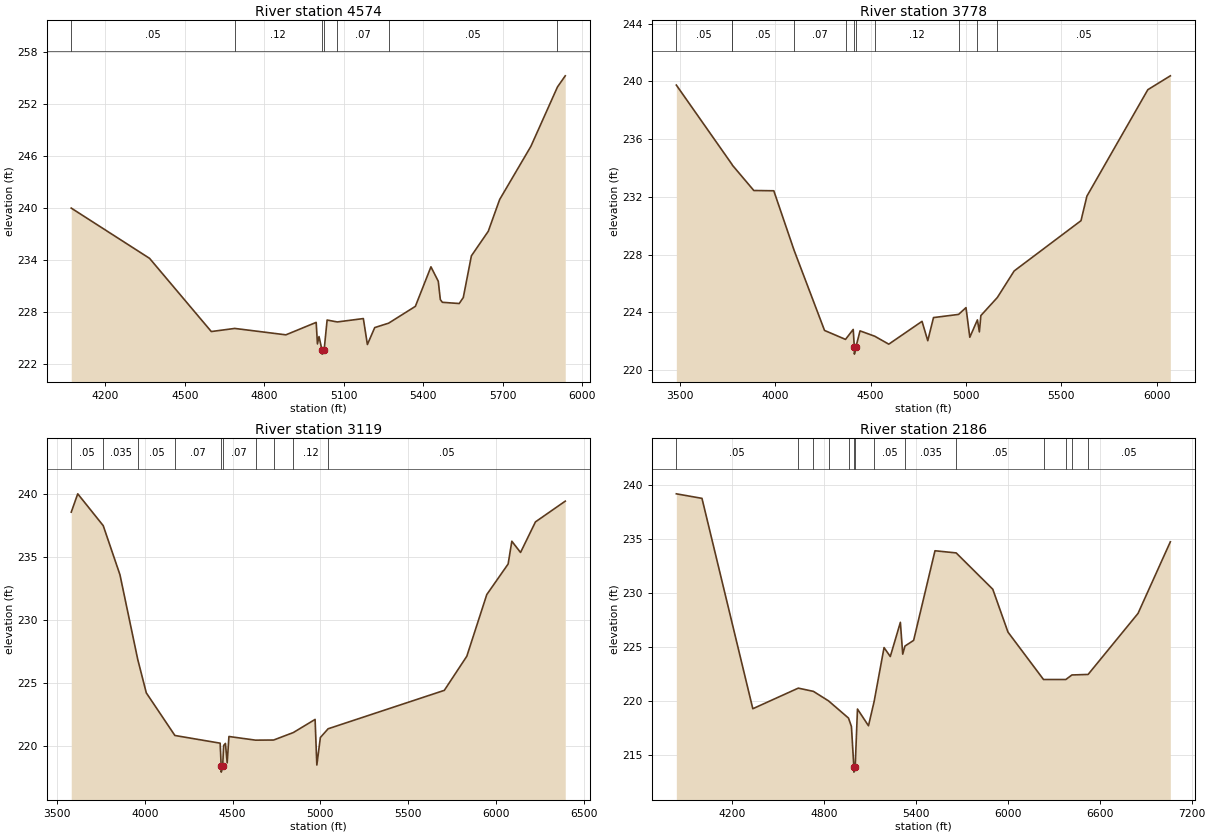
Type RM Length L Ch R = 1 ,4574    ,796,796,796
BEGIN DESCRIPTION:
Stream0683 7.0
END DESCRIPTION:
XS GIS Cut Line= 3
      2440174.96     13640874.99        2441075.       13641075.
      2441875.01     13640574.99
#Sta/Elev= 30
  4070.9  239.97  4366.7  234.16  4599.8   225.7  4688.3  226.06  4881.5  225.32
  4995.8  226.76  5000.6  224.27  5006.5  225.12  5017.6  223.59  5018.1  223.09
  5025.9  223.59  5037.1  227.03  5075.5  226.81  5173.9   227.2  5189.2   224.2
  5216.9  226.16  5269.5  226.67  5370.3  228.61  5429.2  233.18  5456.9  231.51
  5464.6   229.4  5472.3  229.08  5535.9  228.94  5551.3  229.63  5581.9  234.45
  5645.6  237.29  5688.6  240.96  5806.6  247.11  5906.9  253.97  5936.3  255.26
#Mann= 7 ,-1 , 0
  4070.9     .05       0  4688.3     .12       0  5017.6     .05       0
  5025.9     .12       0  5075.5     .07       0  5269.5     .05       0
  5906.9     .07       0
Bank Sta=5017.6,5025.9
XS Rating Curve= 0 ,0
Exp/Cntr=0.3,0.1

Type RM Length L Ch R = 1 ,3778    ,659,659,659
BEGIN DESCRIPTION:
XS7470
END DESCRIPTION:
XS GIS Cut Line= 3
      2439809.73     13641843.81      2441405.55     13641737.92
      2442335.82     13641397.58
#Sta/Elev= 30
  3481.3  239.74  3773.6  234.24  3775.4  234.19  3887.5  232.44  3992.3  232.42
  4098.7   228.3  4258.3  222.75  4368.2  222.13  4408.6  222.82  4414.4  221.61
  4414.9  221.11  4422.8  221.61  4444.4  222.72  4521.3  222.35  4595.1   221.8
  4769.4  223.38  4799.5  222.04  4829.5  223.64    4961  223.86  4999.9  224.33
  5019.9  222.28  5059.8  223.48  5070.1  222.65  5077.9  223.78  5164.2  225.03
  5252.5  226.87  5602.8  230.35  5633.8  232.05  5953.2  239.42  6071.2  240.38
#Mann= 11 ,-1 , 0
  3481.3     .05       0  3773.6    .035       0  3775.4     .05       0
  4098.7     .07       0  4368.2     .12       0  4414.4     .05       0
  4422.8     .12       0  4521.3     .12       0    4961     .07       0
  5059.8     .12       0  5164.2     .05       0
Bank Sta=4414.4,4422.8
XS Rating Curve= 0 ,0
Exp/Cntr=0.3,0.1

Type RM Length L Ch R = 1 ,3119    ,933,933,933
BEGIN DESCRIPTION:
XS7469
END DESCRIPTION:
XS GIS Cut Line= 3
      2439907.99     13642274.91      2441481.19     13642342.98
      2442449.25     13641571.56
#Sta/Elev= 30
  3581.8  238.54  3618.8  239.99    3764  237.47  3859.1  233.59  3960.7  226.87
  4009.2  224.24  4171.9  220.87  4429.6  220.26  4435.4  218.47  4435.9  217.97
  4443.9  218.47  4449.6  220.08  4459.6  220.24  4469.6   218.7  4479.6  220.79
  4631.1   220.5    4734  220.51    4846   221.1  4970.1  222.14  4980.1  218.53
  5000.1  220.71  5044.3   221.4  5705.8  224.44  5833.9  227.14  5947.6  232.02
  6069.2  234.44  6090.2  236.24  6139.8  235.35  6224.7  237.77  6394.3  239.41
#Mann= 10 ,-1 , 0
  3581.8     .05       0    3764    .035       0  3960.7     .05       0
  4171.9     .07       0  4435.4     .05       0  4443.9     .07       0
  4631.1     .12       0    4734     .07       0    4846     .12       0
  5044.3     .05       0
Bank Sta=4435.4,4443.9
XS Rating Curve= 0 ,0
Exp/Cntr=0.3,0.1

Type RM Length L Ch R = 1 ,2186    ,0,0,0
BEGIN DESCRIPTION:
XS7468
END DESCRIPTION:
XS GIS Cut Line= 4
      2439968.57     13642857.29       2441148.4     13642978.29
      2441700.52     13642879.97       2442729.1     13641821.14
#Sta/Elev= 30
  3837.5   239.2  4004.8  238.78  4336.5  219.27  4633.1  221.18  4731.7  220.88
  4830.3     220  4960.9   218.4  4979.9  217.62  4995.6  213.89  4996.1  213.39
  5004.4  213.89  5019.3  219.24  5091.2  217.69  5128.1  219.95  5192.7  224.94
  5233.4  224.11  5299.2  227.28  5314.6  224.33    5329  225.08  5385.7  225.61
    5525  233.92  5663.3  233.72  5902.1  230.35  6001.1  226.38  6233.1  221.98
  6378.6  221.98  6418.2   222.4  6524.1  222.45  6849.7  228.11  7060.5  234.75
#Mann= 14 ,-1 , 0
  3837.5     .05       0  4633.1     .07       0  4731.7     .12       0
  4830.3     .05       0  4960.9     .07       0  4995.6     .05       0
  5004.4     .07       0  5128.1     .05       0    5329    .035       0
  5663.3     .05       0  6233.1    .035       0  6378.6     .05       0
  6418.2    .035       0  6524.1     .05       0
Bank Sta=4995.6,5004.4
XS Rating Curve= 0 ,0
Exp/Cntr=0.3,0.1

Chan Stop Cuts=-1
Use User Specified Reach Order=0
Composite Channel Slope=5