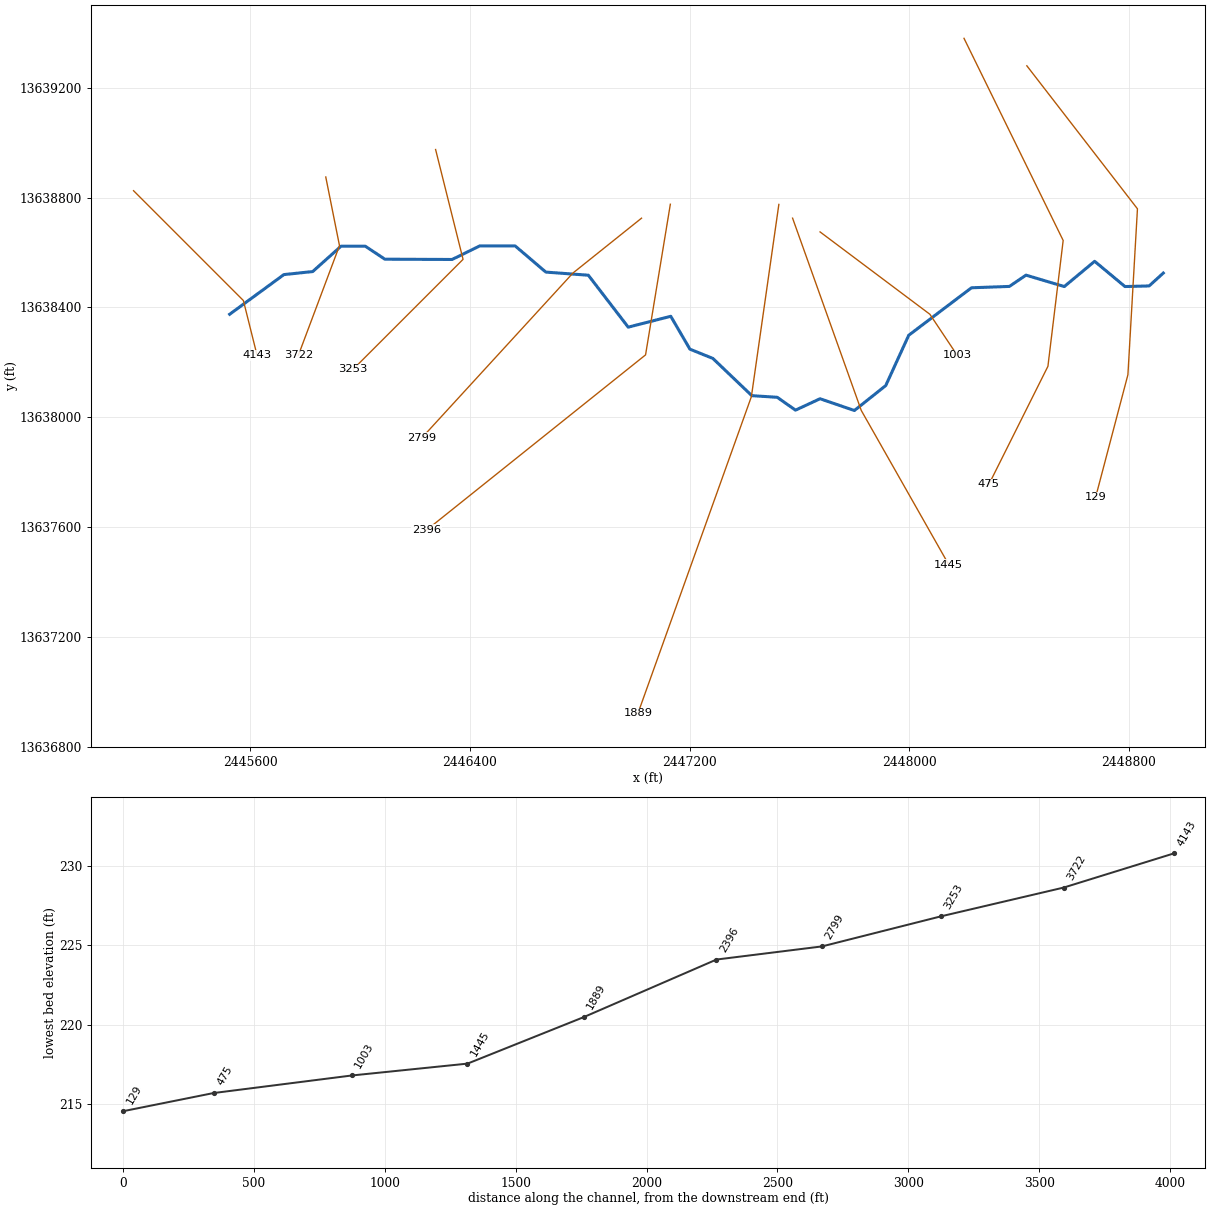
--- Stream0686.prj (project) ---

Proj Title=Stream0686 Base Level Engineering
Current Plan=p01
Default Exp/Contr=0.3,0.1
English Units
Geom File=g01
Flow File=f01
Plan File=p01
BEGIN DESCRIPTION:
Stream0686
END DESCRIPTION:

--- Stream0686.p01 (plan) ---

Plan Title=Multiple Run
Short Identifier=Multiple
Geom File=g01
Flow File=f01
Subcritical Flow
K Sum by GR= 0
Std Step Tol= 0.01
Critical Tol= 0.01
Num of Std Step Trials= 20
Max Error Tol= 0.3
Flow Tol Ratio= 0.001
Split Flow NTrial= 30
Split Flow Tol= 0.02
Split Flow Ratio= 0.02
Log Output Level= 0
Friction Slope Method= 1
Unsteady Friction Slope Method= 2
Unsteady Bridges Friction Slope Method= 1
Parabolic Critical Depth
Global Vel Dist=  1 , 1 , 1
Global Log Level= 0
CheckData=True
Encroach Param= -1, 0, 0, 0
BEGIN DESCRIPTION:
Multiple Run
END DESCRIPTION:

--- Stream0686.f01 (steady flow) ---

Flow Title=Multiple
Number of Profiles=7
Profile Names=10-year,25-year,50-year,1pct_min,100-year,1pct_plu,500-year
River Rch & RM= Stream0686,Reach-1,4143
     809    1317    1779    1162    2319    4627    3905
Boundary for River Rch & Prof#=Stream0686,Reach-1,1
Up Type=0
Dn Type=3
Dn Slope=0.005
Boundary for River Rch & Prof#=Stream0686,Reach-1,2
Up Type=0
Dn Type=3
Dn Slope=0.005
Boundary for River Rch & Prof#=Stream0686,Reach-1,3
Up Type=0
Dn Type=3
Dn Slope=0.005
Boundary for River Rch & Prof#=Stream0686,Reach-1,4
Up Type=0
Dn Type=3
Dn Slope=0.005
Boundary for River Rch & Prof#=Stream0686,Reach-1,5
Up Type=0
Dn Type=3
Dn Slope=0.005
Boundary for River Rch & Prof#=Stream0686,Reach-1,6
Up Type=0
Dn Type=3
Dn Slope=0.005
Boundary for River Rch & Prof#=Stream0686,Reach-1,7
Up Type=0
Dn Type=3
Dn Slope=0.005

--- Stream0686.g01 (geometry) ---

Geom Title=Existing Conditions

River Reach=Stream0686,Reach-1
Reach XY= 30
      2445525.00     13638375.00      2445722.58     13638519.46
      2445827.42     13638530.54      2445930.89     13638623.03
      2446019.02     13638622.84      2446090.22     13638575.52
      2446335.19     13638574.55      2446435.51     13638623.79
      2446564.56     13638623.96      2446676.47     13638528.56
      2446831.21     13638517.19      2446976.42     13638328.04
      2447131.34     13638367.63      2447201.17     13638247.87
      2447284.66     13638214.21      2447426.50     13638078.61
      2447519.03     13638072.62      2447585.71     13638025.81
      2447674.99     13638067.40      2447800.04     13638024.51
      2447914.25     13638115.29      2447997.99     13638298.52
      2448226.47     13638471.45      2448364.56     13638476.40
      2448425.00     13638517.44      2448564.52     13638475.95
      2448675.00     13638567.90      2448785.46     13638475.93
      2448873.59     13638478.18      2448925.00     13638525.00

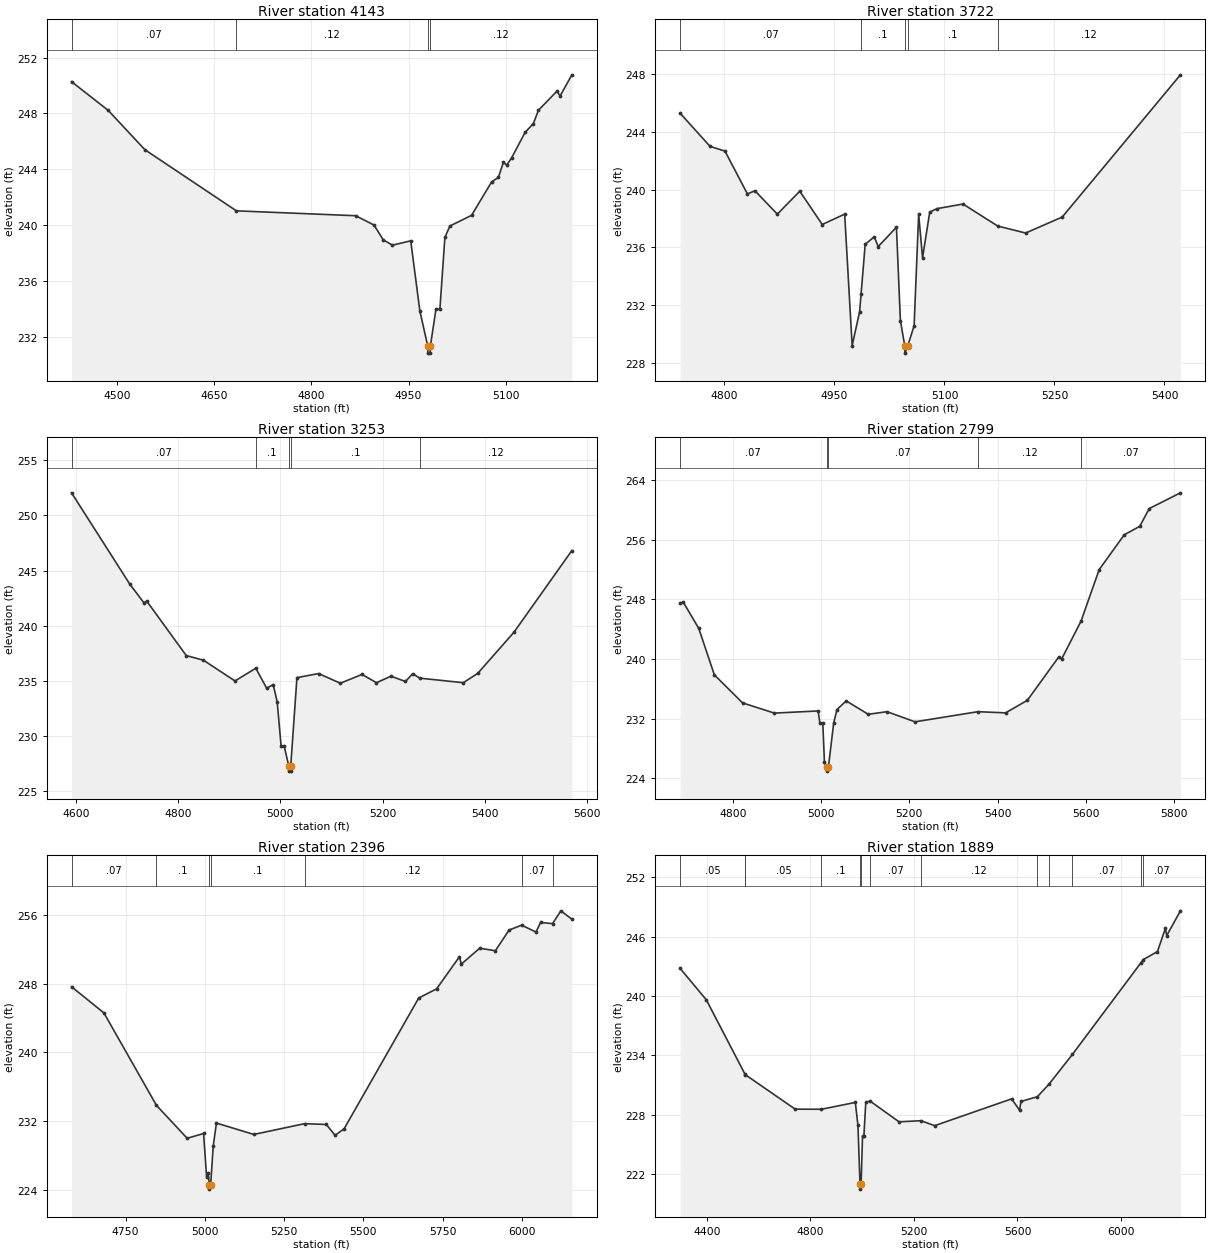
Type RM Length L Ch R = 1,4143,421,421,421
BEGIN DESCRIPTION:
Stream0686 8.0
END DESCRIPTION:
XS GIS Cut Line= 3
      2445174.99     13638825.01      2445575.00     13638425.00
      2445625.01     13638224.96
#Sta/Elev= 30
  4430.0  250.28  4486.6  248.22  4543.2  245.40  4684.3  241.02  4868.4  240.67
  4896.7  240.00  4910.9  238.94  4925.0  238.56  4953.3  238.87  4967.4  233.84
  4979.6  231.32  4979.8  230.82  4983.3  230.82  4983.6  231.32  4992.2  233.97
  4998.3  233.97  5006.0  239.11  5013.7  239.93  5047.2  240.70  5078.2  243.10
  5088.5  243.41  5096.2  244.49  5101.4  244.30  5109.1  244.83  5129.7  246.64
  5142.6  247.28  5150.3  248.23  5178.7  249.59  5183.8  249.26  5201.9  250.77
#Mann=4,-1,0
  4430.0    0.07       0  4684.3    0.12       0  4979.6    0.05       0
  4983.6    0.12       0
Bank Sta=4979.6,4983.6
Exp/Cntr=0.3,0.1

Type RM Length L Ch R = 1,3722,469,469,469
BEGIN DESCRIPTION:
Stream0686 7.0
END DESCRIPTION:
XS GIS Cut Line= 3
      2445875.00     13638875.02      2445925.00     13638625.00
      2445774.99     13638224.97
#Sta/Elev= 30
  4739.5  245.30  4780.3  243.00  4800.7  242.67  4831.3  239.70  4841.5  239.92
  4872.1  238.30  4902.7  239.89  4933.3  237.58  4963.9  238.30  4974.1  229.18
  4984.3  231.54  4986.3  232.77  4991.9  236.21  5004.3  236.73  5009.6  236.05
  5034.5  237.39  5039.9  230.90  5045.9  229.16  5046.1  228.66  5049.9  229.16
  5058.6  230.56  5064.8  238.30  5070.1  235.27  5079.9  238.44  5089.7  238.68
  5125.3  239.00  5172.7  237.47  5210.7  236.99  5260.6  238.10  5421.7  247.96
#Mann=5,-1,0
  4739.5    0.07       0  4986.3     0.1       0  5045.9    0.05       0
  5049.9     0.1       0  5172.7    0.12       0
Bank Sta=5045.9,5049.9
Exp/Cntr=0.3,0.1

Type RM Length L Ch R = 1,3253,454,454,454
BEGIN DESCRIPTION:
Stream0686 6.0
END DESCRIPTION:
XS GIS Cut Line= 3
      2446275.01     13638974.97      2446375.00     13638575.00
      2445974.98     13638174.98
#Sta/Elev= 30
  4591.9  252.05  4705.3  243.81  4733.6  242.07  4738.8  242.25  4816.1  237.31
  4849.6  236.89  4911.4  235.01  4952.1  236.16  4973.3  234.35  4986.1  234.68
  4993.9  233.11  5001.6  229.08  5007.7  229.08  5016.3  227.34  5016.5  226.84
  5020.1  226.84  5020.4  227.34  5032.5  235.31  5074.9  235.68  5117.3  234.80
  5159.7  235.60  5188.0  234.85  5216.3  235.44  5244.6  234.96  5258.7  235.66
  5272.9  235.26  5357.7  234.85  5386.0  235.70  5456.7  239.42  5569.9  246.82
#Mann=5,-1,0
  4591.9    0.07       0  4952.1     0.1       0  5016.3    0.05       0
  5020.4     0.1       0  5272.9    0.12       0
Bank Sta=5016.3,5020.4
Exp/Cntr=0.3,0.1

Type RM Length L Ch R = 1,2799,403,403,403
BEGIN DESCRIPTION:
Stream0686 5.0
END DESCRIPTION:
XS GIS Cut Line= 3
      2447024.97     13638724.97      2446775.00     13638525.00
      2446224.97     13637924.97
#Sta/Elev= 30
  4680.4  247.46  4687.6  247.63  4722.8  244.09  4758.0  237.87  4822.0  234.10
  4894.1  232.73  4993.3  233.02  4997.3  231.38  5003.9  231.38  5007.6  226.14
  5012.3  225.44  5012.6  224.94  5016.5  225.44  5028.6  231.42  5036.0  233.21
  5056.9  234.37  5106.9  232.57  5149.4  232.92  5212.9  231.56  5355.6  232.92
  5418.3  232.76  5467.6  234.45  5538.5  240.25  5545.3  240.00  5589.3  245.08
  5630.4  251.99  5687.1  256.66  5722.3  257.80  5743.9  260.19  5814.5  262.30
#Mann=5,-1,0
  4680.4    0.07       0  5012.3    0.05       0  5016.5    0.07       0
  5355.6    0.12       0  5589.3    0.07       0
Bank Sta=5012.3,5016.5
Exp/Cntr=0.3,0.1

Type RM Length L Ch R = 1,2396,507,507,507
BEGIN DESCRIPTION:
Stream0686 4.0
END DESCRIPTION:
XS GIS Cut Line= 3
      2447129.85     13638775.65      2447039.58     13638227.08
      2446242.11     13637589.11
#Sta/Elev= 30
  4579.9  247.64  4681.9  244.60  4847.6  233.85  4944.4  230.02  4996.1  230.58
  5005.6  225.54  5010.7  226.00  5014.2  224.61  5014.5  224.11  5018.4  224.61
  5026.5  229.12  5036.6  231.79  5154.5  230.47  5314.3  231.72  5383.0  231.63
  5410.6  230.37  5439.0  231.12  5674.3  246.33  5730.8  247.40  5802.4  251.12
  5808.8  250.28  5866.4  252.12  5916.0  251.83  5959.2  254.24  5999.0  254.80
  6044.1  254.00  6058.5  255.12  6096.2  254.98  6122.5  256.47  6157.1  255.50
#Mann=7,-1,0
  4579.9    0.07       0  4847.6     0.1       0  5014.2    0.05       0
  5018.4     0.1       0  5314.3    0.12       0  5999.0    0.07       0
  6096.2    0.12       0
Bank Sta=5014.2,5018.4
Exp/Cntr=0.3,0.1

Type RM Length L Ch R = 1,1889,444,444,444
BEGIN DESCRIPTION:
Stream0686 3.0
END DESCRIPTION:
XS GIS Cut Line= 3
      2447525.00     13638774.99      2447425.00     13638075.00
      2447011.82     13636921.57
#Sta/Elev= 30
  4297.0  242.80  4398.0  239.63  4548.2  232.07  4548.6  232.05  4741.5  228.56
  4842.9  228.55  4973.8  229.24  4983.9  226.92  4991.9  220.97  4992.1  220.47
  4996.1  220.97  5001.6  225.84  5006.8  225.84  5014.2  229.25  5030.7  229.38
  5142.5  227.28  5227.0  227.39  5280.3  226.89  5577.4  229.60  5608.1  228.45
  5613.4  229.34  5677.1  229.82  5722.8  231.12  5812.3  234.10  6075.9  243.33
  6086.0  243.69  6140.6  244.50  6171.3  246.84  6176.6  246.12  6229.3  248.62
#Mann=13,-1,0
  4297.0    0.05       0  4548.2    0.07       0  4548.6    0.05       0
  4842.9     0.1       0  4991.9    0.05       0  4996.1     0.1       0
  5030.7    0.07       0  5227.0    0.12       0  5677.1    0.07       0
  5722.8    0.12       0  5812.3    0.07       0  6075.9    0.12       0
  6086.0    0.07       0
Bank Sta=4991.9,4996.1
Exp/Cntr=0.3,0.1

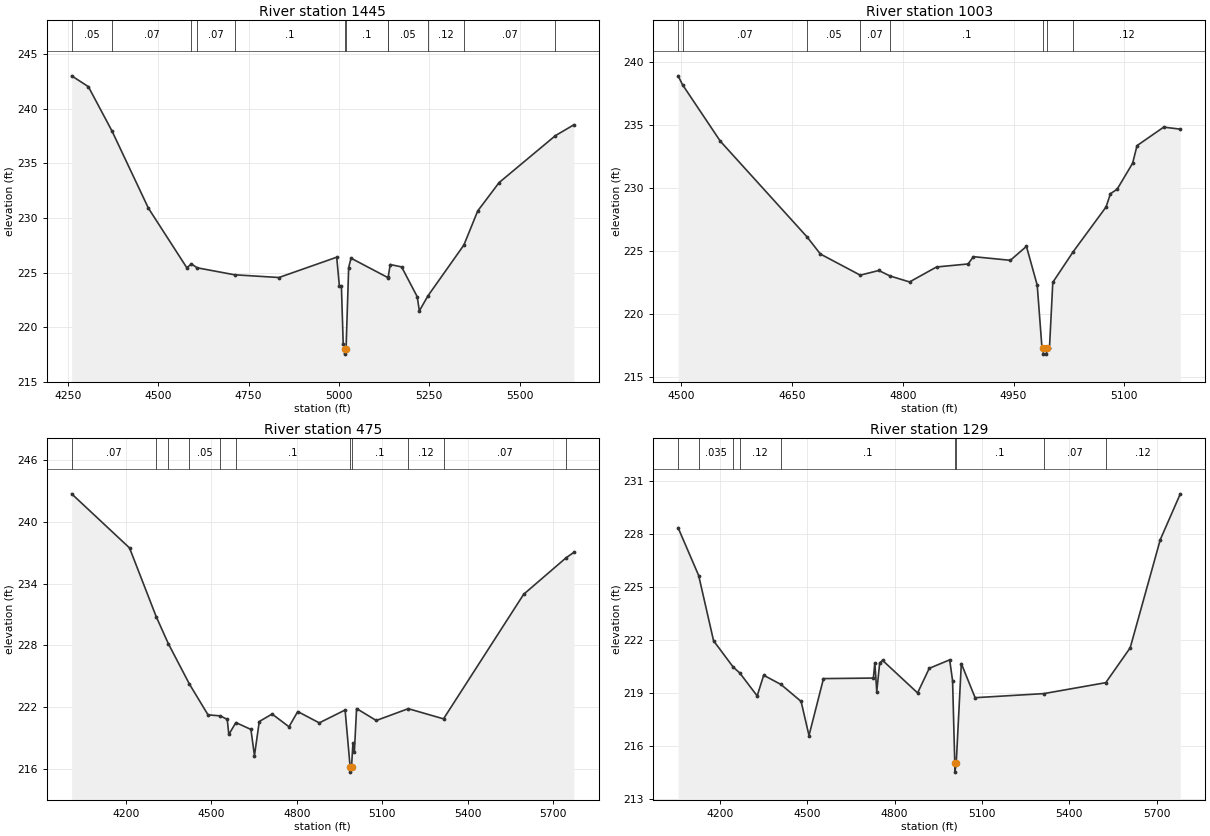
Type RM Length L Ch R = 1,1445,442,442,442
BEGIN DESCRIPTION:
Stream0686 2.0
END DESCRIPTION:
XS GIS Cut Line= 3
      2447575.01     13638724.98      2447825.00     13638025.00
      2448143.74     13637463.21
#Sta/Elev= 30
  4260.5  243.03  4306.7  242.04  4372.0  237.98  4472.9  230.90  4579.0  225.45
  4591.9  225.79  4607.7  225.44  4711.2  224.80  4833.9  224.55  4993.7  226.41
  5001.1  223.78  5006.7  223.78  5011.7  218.48  5015.4  218.03  5015.6  217.53
  5019.6  218.03  5026.8  225.46  5033.4  226.32  5134.3  224.56  5135.6  224.49
  5141.8  225.74  5173.3  225.52  5216.5  222.79  5222.3  221.49  5246.1  222.87
  5345.6  227.53  5383.8  230.65  5443.0  233.25  5598.7  237.55  5649.7  238.54
#Mann=12,-1,0
  4260.5    0.05       0  4372.0    0.07       0  4591.9    0.05       0
  4607.7    0.07       0  4711.2     0.1       0  5015.4    0.05       0
  5019.6     0.1       0  5134.3    0.12       0  5135.6    0.05       0
  5246.1    0.12       0  5345.6    0.07       0  5598.7    0.05       0
Bank Sta=5015.4,5019.6
Exp/Cntr=0.3,0.1

Type RM Length L Ch R = 1,1003,528,528,528
BEGIN DESCRIPTION:
Stream0686 1.0
END DESCRIPTION:
XS GIS Cut Line= 3
      2447675.04     13638674.97      2448075.00     13638375.00
      2448174.98     13638225.03
#Sta/Elev= 30
  4495.6  238.91  4501.6  238.20  4552.8  233.71  4670.4  226.09  4688.3  224.74
  4742.3  223.06  4767.4  223.43  4782.8  222.99  4809.1  222.52  4845.6  223.71
  4888.3  223.95  4895.6  224.53  4945.6  224.24  4967.4  225.35  4982.0  222.26
  4988.3  217.38  4990.0  217.28  4990.4  216.78  4994.5  216.78  4994.9  217.28
  4998.6  217.28  5003.1  222.49  5030.8  224.93  5075.2  228.48  5081.2  229.54
  5090.2  229.89  5111.2  231.96  5117.2  233.36  5153.3  234.83  5175.8  234.67
#Mann=8,-1,0
  4495.6    0.05       0  4501.6    0.07       0  4670.4    0.05       0
  4742.3    0.07       0  4782.8     0.1       0  4990.0    0.05       0
  4994.9     0.1       0  5030.8    0.12       0
Bank Sta=4990,4994.9
Exp/Cntr=0.3,0.1

Type RM Length L Ch R = 1,475,346,346,346
BEGIN DESCRIPTION:
XS7474
END DESCRIPTION:
XS GIS Cut Line= 4
      2448199.31     13639379.85      2448560.42     13638643.75
      2448504.86     13638185.42      2448289.79     13637755.27
#Sta/Elev= 30
  4009.4  242.73  4212.5  237.47  4306.3  230.78  4348.6  228.17  4422.6  224.24
  4488.0  221.24  4530.8  221.14  4555.5  220.80  4561.0  219.33  4585.8  220.49
  4638.6  219.82  4651.0  217.28  4667.9  220.59  4712.9  221.32  4772.2  220.08
  4802.9  221.56  4878.4  220.46  4969.1  221.71  4986.8  216.17  4987.1  215.67
  4991.7  216.17  4996.6  218.52  5001.6  217.61  5009.4  221.85  5078.5  220.69
  5190.8  221.84  5314.5  220.85  5595.7  232.96  5744.2  236.50  5771.9  237.04
#Mann=11,-1,0
  4009.4    0.07       0  4306.3    0.05       0  4348.6    0.12       0
  4422.6    0.05       0  4530.8    0.12       0  4585.8     0.1       0
  4986.8    0.05       0  4991.7     0.1       0  5190.8    0.12       0
  5314.5    0.07       0  5744.2    0.05       0
Bank Sta=4986.8,4991.7
Exp/Cntr=0.3,0.1

Type RM Length L Ch R = 1,129,0,0,0
BEGIN DESCRIPTION:
XS7474x
END DESCRIPTION:
XS GIS Cut Line= 4
      2448428.15     13639279.84      2448830.90     13638759.04
      2448796.18     13638154.87      2448678.52     13637708.45
#Sta/Elev= 30
  4056.3  228.34  4126.9  225.64  4178.1  221.95  4245.6  220.46  4268.0  220.13
  4327.9  218.83  4350.2  220.00  4409.4  219.48  4478.8  218.52  4505.9  216.59
  4555.7  219.81  4727.1  219.84  4732.1  220.71  4738.7  219.08  4748.8  220.70
  4758.8  220.84  4879.0  219.00  4919.0  220.39  4989.2  220.87  4999.2  219.69
  5006.7  215.02  5007.1  214.52  5011.7  215.02  5029.2  220.66  5076.6  218.73
  5312.3  218.96  5525.4  219.58  5609.3  221.55  5712.7  227.67  5781.5  230.26
#Mann=9,-1,0
  4056.3    0.05       0  4126.9   0.035       0  4245.6    0.07       0
  4268.0    0.12       0  4409.4     0.1       0  5006.7    0.05       0
  5011.7     0.1       0  5312.3    0.07       0  5525.4    0.12       0
Bank Sta=5006.7,5011.7
Exp/Cntr=0.3,0.1

Chan Stop Cuts=-1