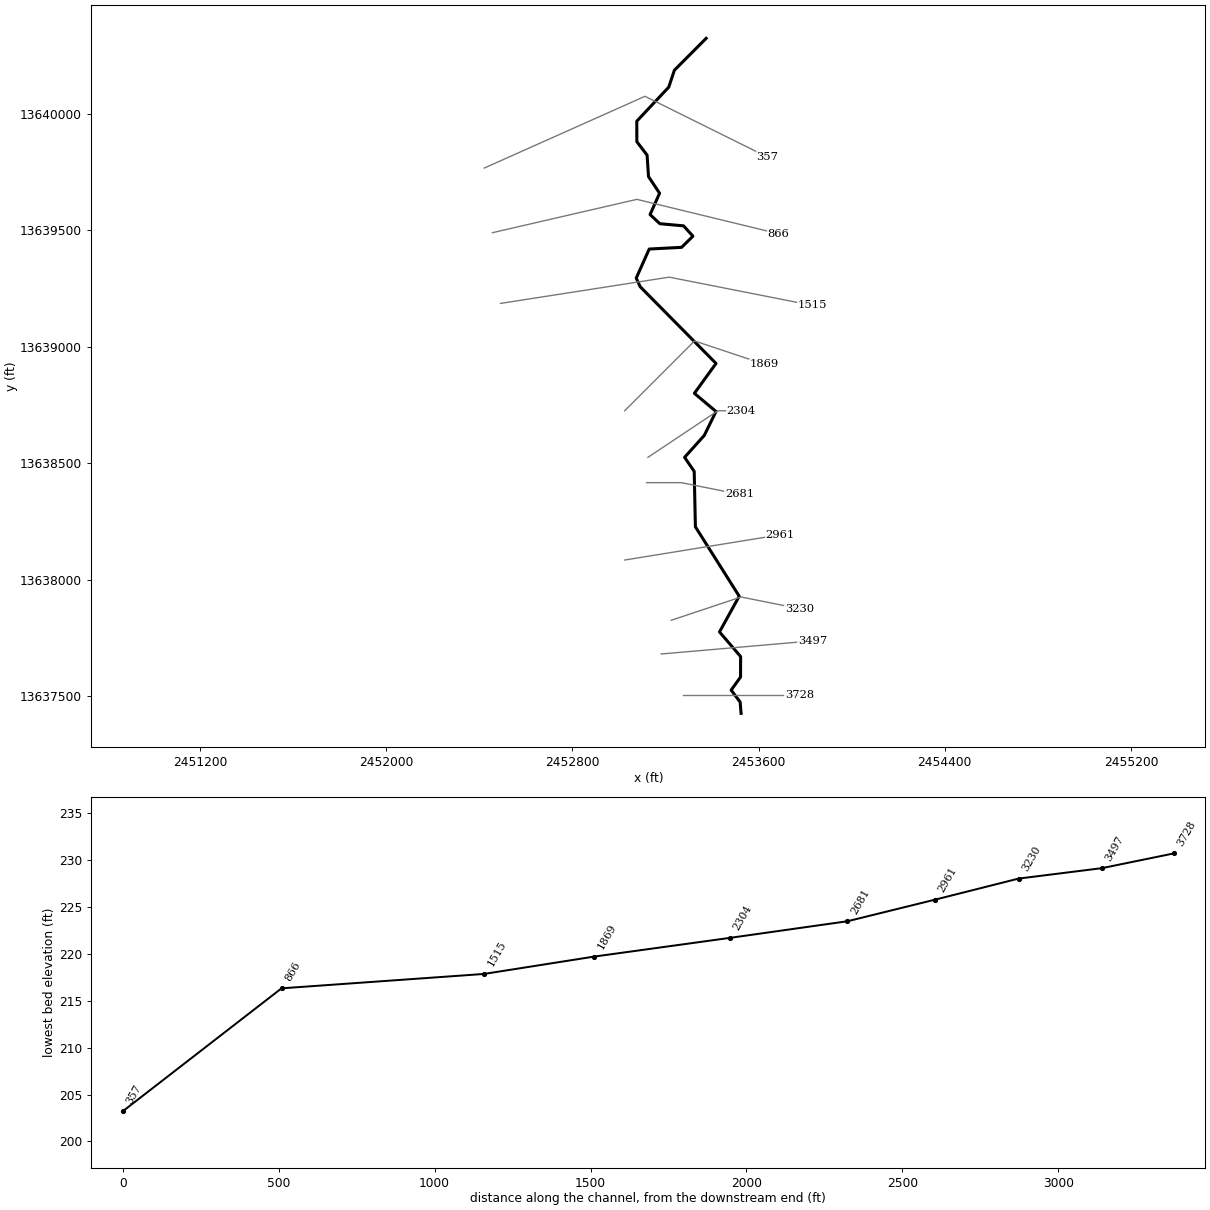
--- Stream0687.prj (project) ---

Proj Title=Stream0687 Base Level Engineering
Current Plan=p01
Default Exp/Contr=0.3,0.1
English Units
Geom File=g01
Flow File=f01
Plan File=p01
BEGIN DESCRIPTION:
Stream0687
END DESCRIPTION:

--- Stream0687.p01 (plan) ---

Plan Title=Multiple Run
Short Identifier=Multiple
Geom File=g01
Flow File=f01
Subcritical Flow
K Sum by GR= 0
Std Step Tol= 0.01
Critical Tol= 0.01
Num of Std Step Trials= 20
Max Error Tol= 0.3
Flow Tol Ratio= 0.001
Split Flow NTrial= 30
Split Flow Tol= 0.02
Split Flow Ratio= 0.02
Log Output Level= 0
Friction Slope Method= 1
Unsteady Friction Slope Method= 2
Unsteady Bridges Friction Slope Method= 1
Parabolic Critical Depth
Global Vel Dist=  1 , 1 , 1
Global Log Level= 0
CheckData=True
Encroach Param= -1, 0, 0, 0
BEGIN DESCRIPTION:
Multiple Run
END DESCRIPTION:

--- Stream0687.f01 (steady flow) ---

Flow Title=Multiple
Number of Profiles=7
Profile Names=10-year,25-year,50-year,1pct_min,100-year,1pct_plu,500-year
River Rch & RM= Stream0687,Reach-1,3728
     255     388     501     315     629    1255     978
Boundary for River Rch & Prof#=Stream0687,Reach-1,1
Up Type=0
Dn Type=3
Dn Slope=0.005
Boundary for River Rch & Prof#=Stream0687,Reach-1,2
Up Type=0
Dn Type=3
Dn Slope=0.005
Boundary for River Rch & Prof#=Stream0687,Reach-1,3
Up Type=0
Dn Type=3
Dn Slope=0.005
Boundary for River Rch & Prof#=Stream0687,Reach-1,4
Up Type=0
Dn Type=3
Dn Slope=0.005
Boundary for River Rch & Prof#=Stream0687,Reach-1,5
Up Type=0
Dn Type=3
Dn Slope=0.005
Boundary for River Rch & Prof#=Stream0687,Reach-1,6
Up Type=0
Dn Type=3
Dn Slope=0.005
Boundary for River Rch & Prof#=Stream0687,Reach-1,7
Up Type=0
Dn Type=3
Dn Slope=0.005

--- Stream0687.g01 (geometry) ---

Geom Title=Existing Conditions

River Reach=Stream0687,Reach-1
Reach XY= 30
      2453525.00     13637425.00      2453521.00     13637473.64
      2453482.32     13637524.96      2453522.65     13637580.89
      2453523.01     13637669.11      2453432.30     13637774.92
      2453516.98     13637928.31      2453328.75     13638226.55
      2453323.61     13638464.57      2453282.33     13638525.10
      2453366.84     13638618.95      2453417.21     13638721.94
      2453324.40     13638799.92      2453417.40     13638928.34
      2453091.22     13639258.32      2453074.59     13639295.14
      2453130.41     13639419.82      2453269.55     13639427.08
      2453318.13     13639475.00      2453278.00     13639519.46
      2453176.03     13639528.61      2453134.01     13639567.94
      2453174.85     13639659.58      2453127.38     13639730.97
      2453121.14     13639823.40      2453077.16     13639880.98
      2453076.96     13639969.11      2453214.22     13640115.32
      2453238.63     13640188.21      2453375.00     13640325.00

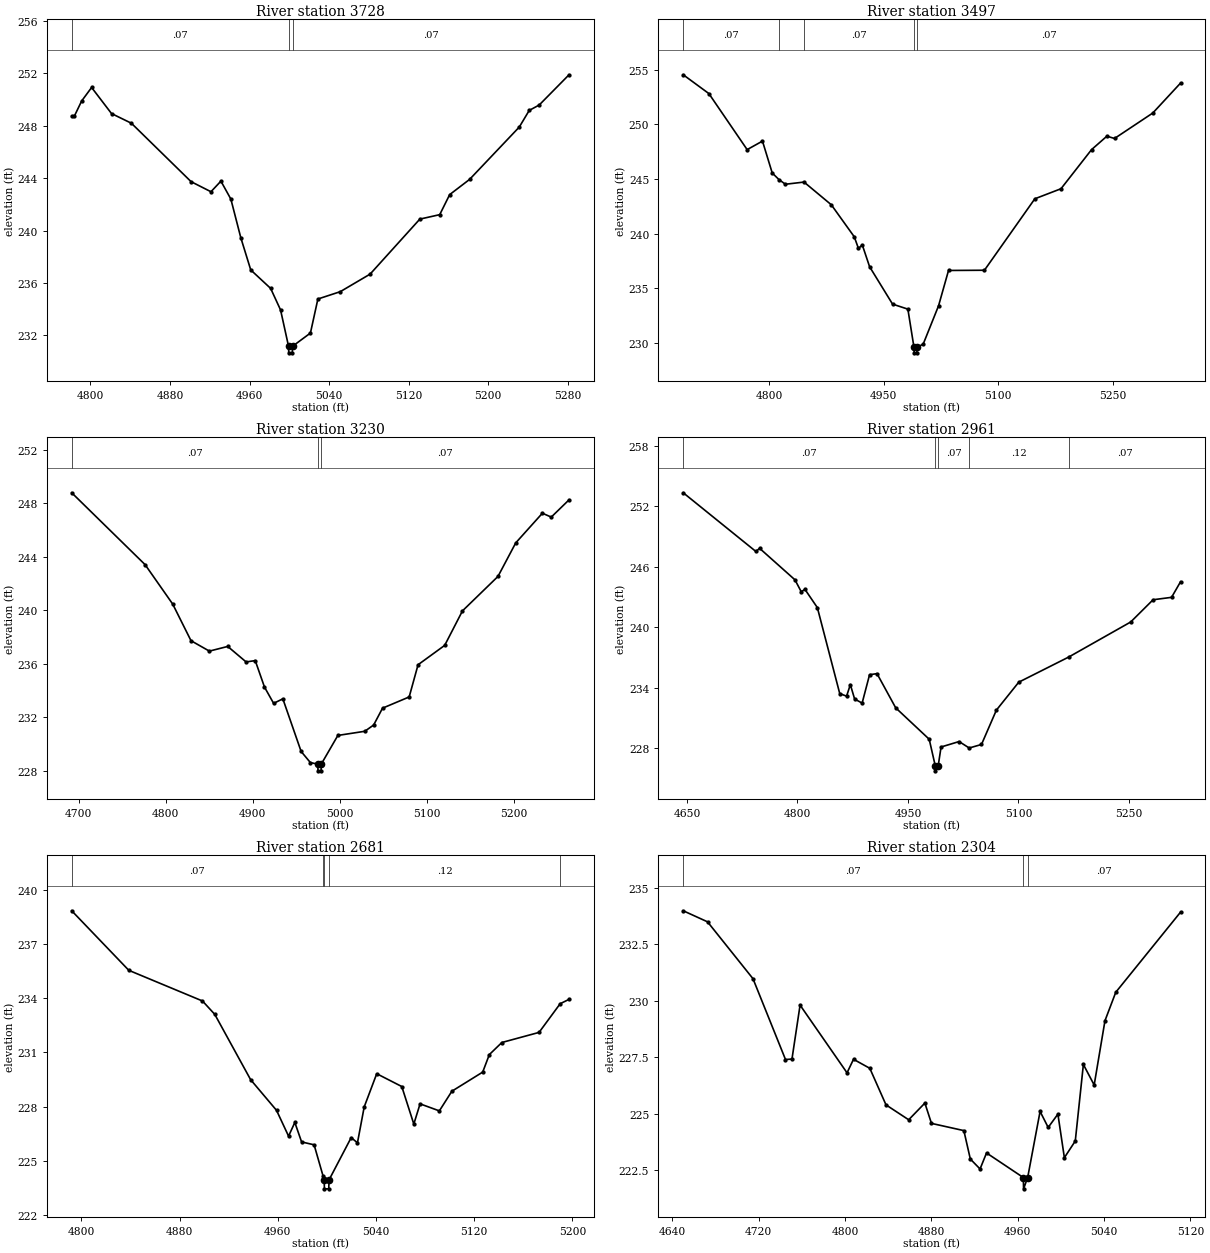
Type RM Length L Ch R = 1,3728,231,231,231
BEGIN DESCRIPTION:
Stream0687 8.0
END DESCRIPTION:
XS GIS Cut Line= 3
      2453275.03     13637505.56      2453525.00     13637505.56
      2453775.03     13637505.56
#Sta/Elev= 30
  4781.2  248.71  4783.7  248.71  4791.2  249.89  4801.2  250.92  4821.2  248.93
  4841.2  248.19  4901.2  243.73  4921.2  242.96  4931.2  243.77  4941.2  242.40
  4951.2  239.45  4961.2  236.99  4981.2  235.58  4991.2  233.93  4999.2  231.16
  4999.4  230.66  5002.9  230.66  5003.2  231.16  5021.2  232.17  5028.7  234.77
  5051.2  235.33  5081.2  236.67  5131.2  240.87  5151.2  241.21  5161.2  242.74
  5181.2  243.90  5231.2  247.90  5241.2  249.17  5251.2  249.58  5281.2  251.89
#Mann=3,-1,0
  4781.2    0.07       0  4999.2    0.05       0  5003.2    0.07       0
Bank Sta=4999.2,5003.2
Exp/Cntr=0.3,0.1

Type RM Length L Ch R = 1,3497,267,267,267
BEGIN DESCRIPTION:
XS7476
END DESCRIPTION:
XS GIS Cut Line= 2
      2453181.50     13637680.12      2453831.26     13637736.43
#Sta/Elev= 30
  4687.0  254.54  4720.6  252.82  4770.8  247.69  4790.9  248.47  4803.7  245.55
  4812.5  244.95  4821.0  244.52  4845.4  244.72  4881.2  242.64  4911.3  239.71
  4916.8  238.64  4921.8  238.97  4931.4  236.97  4961.5  233.55  4981.6  233.09
  4989.6  229.59  4989.9  229.09  4993.4  229.09  4993.6  229.59  5001.7  229.89
  5021.8  233.39  5034.9  236.63  5082.0  236.65  5148.1  243.19  5182.4  244.11
  5222.5  247.69  5242.6  248.92  5252.6  248.71  5302.8  251.04  5339.2  253.78
#Mann=5,-1,0
  4687.0    0.07       0  4812.5    0.12       0  4845.4    0.07       0
  4989.6    0.05       0  4993.6    0.07       0
Bank Sta=4989.6,4993.6
Exp/Cntr=0.3,0.1

Type RM Length L Ch R = 1,3230,269,269,269
BEGIN DESCRIPTION:
Stream0687 7.0
END DESCRIPTION:
XS GIS Cut Line= 3
      2453224.99     13637825.00      2453525.00     13637925.00
      2453775.01     13637875.00
#Sta/Elev= 30
  4692.1  248.79  4776.4  243.41  4808.1  240.46  4829.1  237.72  4850.2  236.94
  4871.3  237.29  4892.4  236.13  4902.9  236.23  4913.5  234.25  4924.0  233.03
  4934.6  233.37  4955.6  229.43  4966.2  228.60  4974.7  228.48  4975.0  227.98
  4978.5  227.98  4978.7  228.48  4997.8  230.63  5028.7  230.94  5038.9  231.41
  5049.1  232.67  5079.7  233.51  5089.9  235.92  5120.5  237.37  5140.9  239.95
  5181.7  242.53  5202.1  245.04  5232.7  247.26  5242.9  246.97  5263.3  248.26
#Mann=3,-1,0
  4692.1    0.07       0  4974.7    0.05       0  4978.7    0.07       0
Bank Sta=4974.7,4978.7
Exp/Cntr=0.3,0.1

Type RM Length L Ch R = 1,2961,280,280,280
BEGIN DESCRIPTION:
XS7475
END DESCRIPTION:
XS GIS Cut Line= 2
      2453025.27     13638083.77      2453691.84     13638191.98
#Sta/Elev= 30
  4644.9  253.36  4743.5  247.53  4748.6  247.84  4796.6  244.71  4805.1  243.53
  4810.2  243.76  4827.0  241.95  4857.4  233.41  4866.7  233.15  4871.8  234.30
  4877.6  232.87  4887.8  232.46  4897.9  235.28  4908.0  235.39  4933.4  231.99
  4978.9  228.87  4987.1  226.23  4987.3  225.73  4991.1  226.23  4995.0  228.10
  5019.5  228.64  5033.2  228.00  5049.9  228.35  5070.1  231.76  5100.5  234.54
  5168.4  237.04  5252.5  240.52  5282.9  242.73  5308.0  242.97  5320.2  244.52
#Mann=5,-1,0
  4644.9    0.07       0  4987.1    0.05       0  4991.1    0.07       0
  5033.2    0.12       0  5168.4    0.07       0
Bank Sta=4987.1,4991.1
Exp/Cntr=0.3,0.1

Type RM Length L Ch R = 1,2681,377,377,377
BEGIN DESCRIPTION:
Stream0687 6.0
END DESCRIPTION:
XS GIS Cut Line= 3
      2453118.54     13638416.15      2453268.58     13638416.15
      2453518.59     13638366.14
#Sta/Elev= 30
  4792.2  238.85  4838.7  235.55  4898.7  233.85  4908.7  233.11  4937.9  229.49
  4959.0  227.79  4968.8  226.36  4973.9  227.12  4979.4  226.04  4989.6  225.88
  4996.9  224.15  4997.8  223.94  4998.0  223.44  5001.5  223.44  5001.8  223.94
  5019.8  226.28  5024.9  225.99  5030.4  227.98  5040.6  229.82  5061.0  229.11
  5070.8  227.03  5075.9  228.15  5091.6  227.76  5101.8  228.85  5126.9  229.91
  5132.3  230.88  5142.5  231.55  5172.8  232.11  5190.0  233.70  5197.2  233.94
#Mann=5,-1,0
  4792.2    0.07       0  4996.9    0.12       0  4997.8    0.05       0
  5001.8    0.12       0  5190.0   0.035       0
Bank Sta=4997.8,5001.8
Exp/Cntr=0.3,0.1

Type RM Length L Ch R = 1,2304,435,435,435
BEGIN DESCRIPTION:
Stream0687 5.0
END DESCRIPTION:
XS GIS Cut Line= 3
      2453125.00     13638525.00      2453425.00     13638725.00
      2453525.04     13638725.00
#Sta/Elev= 30
  4650.3  233.99  4672.8  233.50  4714.9  230.98  4745.0  227.40  4751.0  227.42
  4758.5  229.81  4802.0  226.81  4808.0  227.41  4823.1  227.01  4838.1  225.39
  4859.1  224.73  4874.1  225.47  4880.2  224.57  4910.2  224.25  4916.2  222.99
  4925.2  222.55  4931.2  223.26  4965.3  222.17  4965.5  221.67  4969.3  222.17
  4980.8  225.10  4988.3  224.39  4997.3  224.98  5003.3  223.05  5013.4  223.79
  5020.9  227.18  5030.9  226.27  5040.9  229.12  5050.9  230.38  5110.9  233.93
#Mann=3,-1,0
  4650.3    0.07       0  4965.3    0.05       0  4969.3    0.07       0
Bank Sta=4965.3,4969.3
Exp/Cntr=0.3,0.1

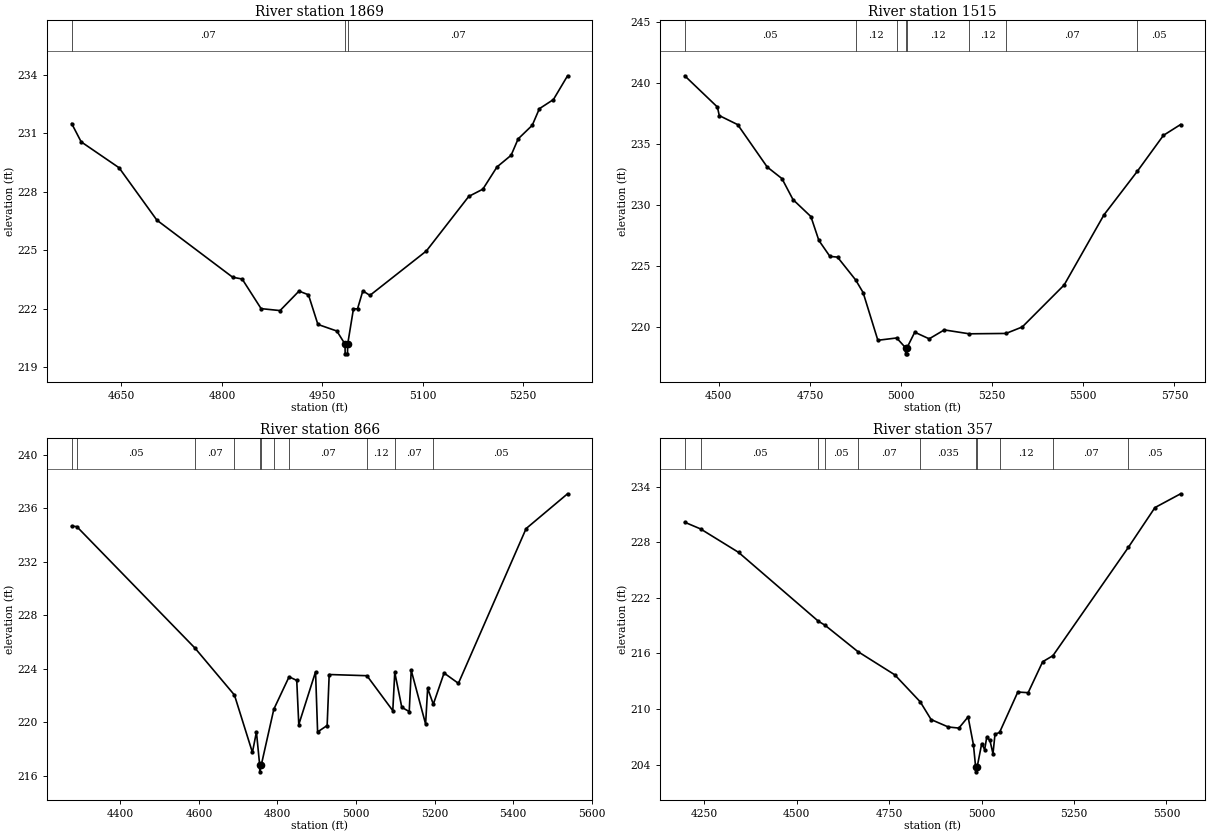
Type RM Length L Ch R = 1,1869,354,354,354
BEGIN DESCRIPTION:
Stream0687 4.0
END DESCRIPTION:
XS GIS Cut Line= 3
      2453024.97     13638724.97      2453325.00     13639025.00
      2453624.97     13638925.01
#Sta/Elev= 30
  4575.6  231.50  4589.8  230.56  4646.4  229.23  4702.9  226.54  4816.1  223.61
  4830.2  223.52  4858.5  222.00  4886.8  221.90  4915.1  222.90  4929.2  222.71
  4943.3  221.19  4971.6  220.85  4983.8  220.18  4984.0  219.68  4987.5  219.68
  4987.8  220.18  4996.4  221.99  5002.5  221.99  5010.4  222.91  5021.0  222.68
  5105.3  224.96  5168.6  227.76  5189.6  228.13  5210.7  229.27  5231.8  229.87
  5242.3  230.71  5263.4  231.41  5274.0  232.26  5295.0  232.73  5316.1  233.95
#Mann=3,-1,0
  4575.6    0.07       0  4983.8    0.05       0  4987.8    0.07       0
Bank Sta=4983.8,4987.8
Exp/Cntr=0.3,0.1

Type RM Length L Ch R = 1,1515,649,649,649
BEGIN DESCRIPTION:
Stream0687 3.0
END DESCRIPTION:
XS GIS Cut Line= 3
      2452491.39     13639186.20      2453216.23     13639299.05
      2453831.32     13639177.76
#Sta/Elev= 30
  4406.5  240.60  4496.2  238.04  4501.3  237.34  4551.8  236.60  4632.8  233.13
  4673.3  232.18  4703.6  230.46  4752.7  229.07  4774.5  227.12  4804.8  225.81
  4825.7  225.75  4875.5  223.88  4895.9  222.85  4936.4  218.94  4988.0  219.13
  5012.3  218.33  5012.5  217.83  5016.0  217.83  5016.3  218.33  5037.6  219.60
  5077.2  219.06  5118.6  219.79  5187.1  219.47  5287.9  219.50  5332.5  220.03
  5447.5  223.47  5556.7  229.21  5648.5  232.79  5719.8  235.72  5767.0  236.61
#Mann=8,-1,0
  4406.5    0.05       0  4875.5    0.12       0  4988.0    0.12       0
  5012.3    0.05       0  5016.3    0.12       0  5187.1    0.12       0
  5287.9    0.07       0  5648.5    0.05       0
Bank Sta=5012.3,5016.3
Exp/Cntr=0.3,0.1

Type RM Length L Ch R = 1,866,509,509,509
BEGIN DESCRIPTION:
Stream0687 2.0
END DESCRIPTION:
XS GIS Cut Line= 3
      2452456.72     13639490.02      2453077.34     13639633.25
      2453684.94     13639485.69
#Sta/Elev= 30
  4276.1  234.65  4289.1  234.62  4590.1  225.54  4690.4  222.04  4736.2  217.75
  4746.4  219.28  4754.7  216.80  4754.9  216.30  4758.7  216.80  4790.7  220.98
  4829.5  223.40  4849.0  223.13  4854.2  219.83  4896.9  223.77  4902.1  219.28
  4926.4  219.76  4931.6  223.57  5027.7  223.48  5093.5  220.87  5098.5  223.73
  5116.4  221.12  5135.3  220.80  5140.4  223.88  5177.0  219.87  5182.2  222.54
  5196.6  221.35  5224.0  223.68  5260.5  222.91  5432.8  234.47  5538.3  237.07
#Mann=11,-1,0
  4276.1   0.035       0  4289.1    0.05       0  4590.1    0.07       0
  4690.4    0.05       0  4754.7    0.05       0  4758.7    0.05       0
  4790.7    0.12       0  4829.5    0.07       0  5027.7    0.12       0
  5098.5    0.07       0  5196.6    0.05       0
Bank Sta=4754.7,4758.7
Exp/Cntr=0.3,0.1

Type RM Length L Ch R = 1,357,0,0,0
BEGIN DESCRIPTION:
Stream0687 1.0
END DESCRIPTION:
XS GIS Cut Line= 3
      2452421.96     13639767.79      2453112.07     13640075.95
      2453637.26     13639815.53
#Sta/Elev= 30
  4196.5  230.15  4239.3  229.43  4342.2  226.90  4558.5  219.46  4575.8  219.05
  4664.9  216.20  4764.9  213.69  4833.9  210.77  4863.3  208.86  4909.7  208.06
  4938.4  207.94  4963.4  209.15  4977.9  206.12  4983.8  203.72  4984.1  203.22
  4987.8  203.72  5000.2  206.26  5008.2  205.61  5013.8  206.95  5022.5  206.61
  5030.7  205.17  5036.2  207.28  5048.5  207.47  5097.9  211.83  5125.9  211.76
  5165.2  215.10  5192.9  215.75  5396.9  227.43  5469.0  231.73  5538.5  233.22
#Mann=11,-1,0
  4196.5   0.035       0  4239.3    0.05       0  4558.5    0.07       0
  4575.8    0.05       0  4664.9    0.07       0  4833.9   0.035       0
  4983.8   0.035       0  4987.8   0.035       0  5048.5    0.12       0
  5192.9    0.07       0  5396.9    0.05       0
Bank Sta=4983.8,4987.8
Exp/Cntr=0.3,0.1

Chan Stop Cuts=-1