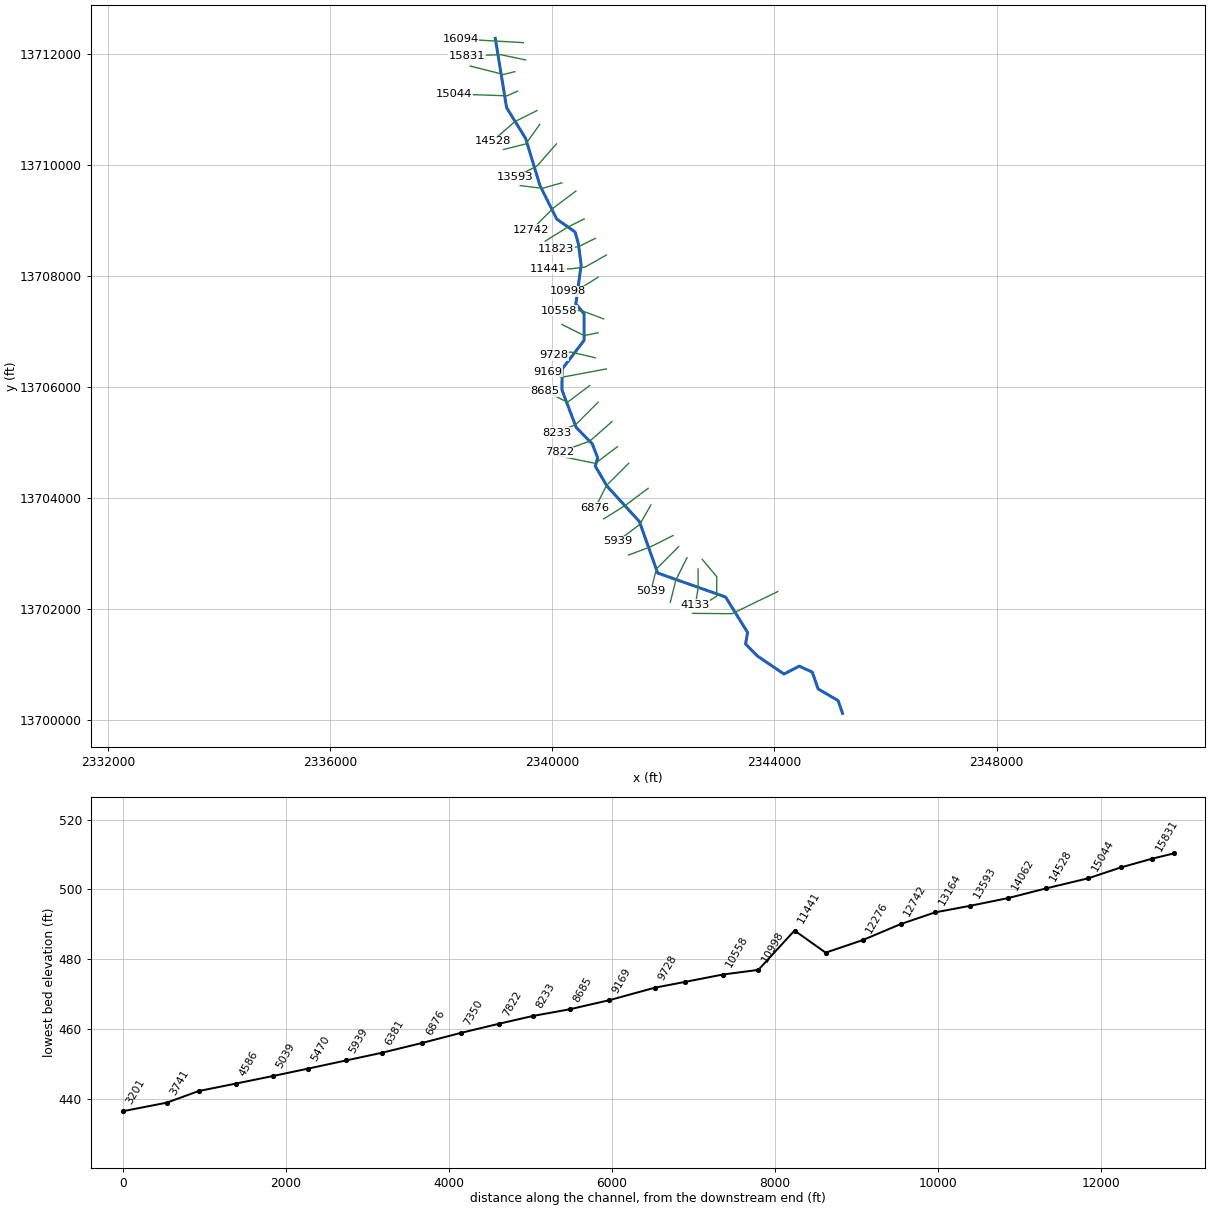
--- TIDWELL CREEK.prj (project) ---

Proj Title=TIDWELL CREEK Base Level Engineering
Current Plan=p01
Default Exp/Contr=0.3,0.1
English Units
Geom File=g01
Flow File=f01
Plan File=p01
Y Axis Title=Elevation
X Axis Title(PF)=Main Channel Distance
X Axis Title(XS)=Station
BEGIN DESCRIPTION:
TIDWELL CREEK
END DESCRIPTION:
DSS Export Rating Curves= 0
DSS Export Rating Curve Sorted= 0
DSS Export Volume Flow Curves= 0
DXF OffsetX= 0
DXF OffsetY= 0
DXF ScaleX= 1
DXF ScaleY= 10

--- TIDWELL CREEK.p01 (plan) ---

Plan Title=Multiple Run
Short Identifier=Multiple
Geom File=g01
Flow File=f01
Subcritical Flow
K Sum by GR= 0
Std Step Tol= 0.01
Critical Tol= 0.01
Num of Std Step Trials= 20
Max Error Tol= 0.3
Flow Tol Ratio= 0.001
Split Flow NTrial= 30
Split Flow Tol= 0.02
Split Flow Ratio= 0.02
Log Output Level= 0
Friction Slope Method= 1
Unsteady Friction Slope Method= 2
Unsteady Bridges Friction Slope Method= 1
Parabolic Critical Depth
Global Vel Dist=  1 , 1 , 1
Global Log Level= 0
CheckData=True
Encroach Param= -1, 0, 0, 0
BEGIN DESCRIPTION:
Multiple Run
END DESCRIPTION:

--- TIDWELL CREEK.f01 (steady flow) ---

Flow Title=Multiple
Number of Profiles=7
Profile Names=10-year,25-year,50-year,1pct_min,100-year,1pct_plu,500-year
River Rch & RM= TIDWELL CREEK,Reach-1,16094
    1050    1769    2448    1640    3272    6529    5794
River Rch & RM= TIDWELL CREEK,Reach-1,14062
    1059    1778    2452    1636    3265    6514    5740
River Rch & RM= TIDWELL CREEK,Reach-1,6876
    1612    2764    3865    2611    5210   10395    9392
River Rch & RM= TIDWELL CREEK,Reach-1,3201
    2115    3666    5164    3511    7005   13976   12792
Boundary for River Rch & Prof#=TIDWELL CREEK,Reach-1,1
Up Type=0
Dn Type=3
Dn Slope=0.005
Boundary for River Rch & Prof#=TIDWELL CREEK,Reach-1,2
Up Type=0
Dn Type=3
Dn Slope=0.005
Boundary for River Rch & Prof#=TIDWELL CREEK,Reach-1,3
Up Type=0
Dn Type=3
Dn Slope=0.005
Boundary for River Rch & Prof#=TIDWELL CREEK,Reach-1,4
Up Type=0
Dn Type=3
Dn Slope=0.005
Boundary for River Rch & Prof#=TIDWELL CREEK,Reach-1,5
Up Type=0
Dn Type=3
Dn Slope=0.005
Boundary for River Rch & Prof#=TIDWELL CREEK,Reach-1,6
Up Type=0
Dn Type=3
Dn Slope=0.005
Boundary for River Rch & Prof#=TIDWELL CREEK,Reach-1,7
Up Type=0
Dn Type=3
Dn Slope=0.005

--- TIDWELL CREEK.g01 (geometry) ---

Geom Title=Existing Conditions
Program Version=4.10

River Reach=TIDWELL CREEK   ,Reach-1
Reach XY= 30
        2338975.       13712275.      2339178.75     13711026.55
      2339521.17     13710473.42      2339778.75     13709626.55
      2340080.83      13709022.7      2340411.77     13708788.67
      2340472.74     13708569.06      2340520.22     13708194.59
      2340424.77     13707495.37      2340572.76     13707319.07
      2340574.48     13706840.22      2340178.55     13706323.53
      2340175.07     13705945.03      2340430.83      13705272.7
      2340721.52     13704973.73      2340817.72     13704725.09
        2340775.       13704575.      2340985.78     13704215.32
      2341569.17      13703577.3      2341897.67     13702650.98
      2343119.89     13702219.73      2343515.87     13701581.74
      2343480.45     13701372.55      2343691.51     13701157.96
      2344171.77     13700832.84       2344445.1      13700975.1
      2344681.33     13700866.96      2344785.35     13700564.88
      2345145.51     13700355.27        2345225.       13700125.

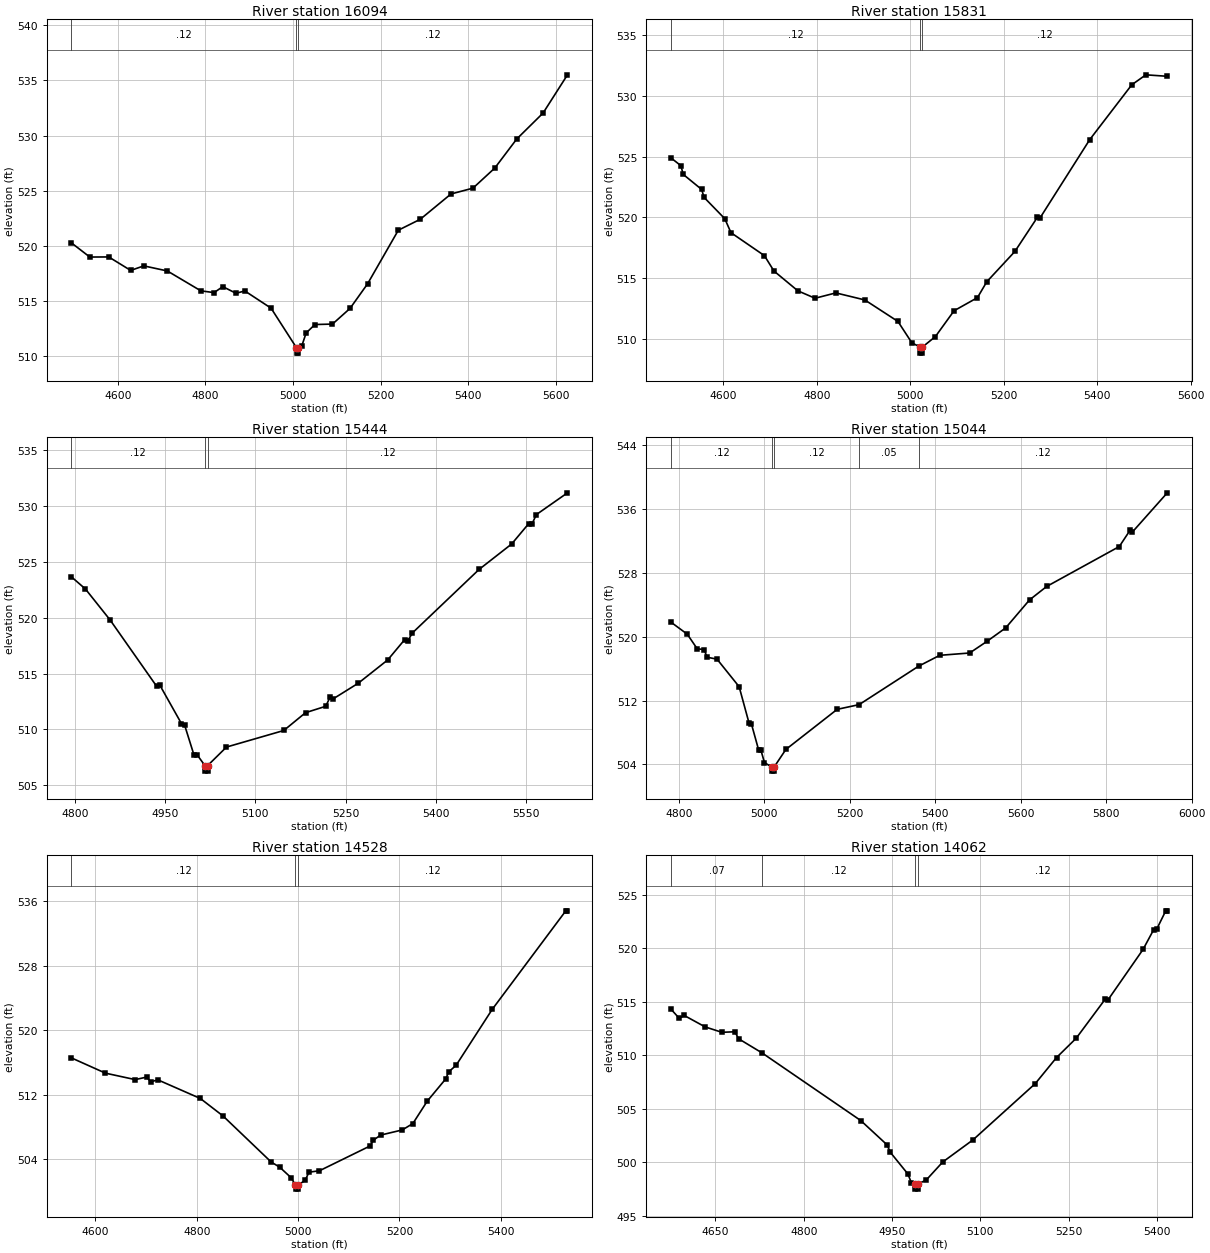
Type RM Length L Ch R = 1 ,16094   ,263,263,263
BEGIN DESCRIPTION:
XS7845
END DESCRIPTION:
XS GIS Cut Line= 2
      2339479.94     13712197.48      2338349.42      13712262.7
#Sta/Elev= 30
  4494.2  520.28  4536.1     519  4579.3  519.01  4629.4  517.79  4659.4   518.2
  4713.1  517.74  4789.6  515.94  4819.7  515.78  4839.7  516.32  4869.8  515.72
    4890  515.93  4949.9  514.37  5007.7   510.8    5008   510.3  5011.9   510.3
  5012.2   510.8    5020  510.95    5030  512.13  5050.1  512.89  5090.1  512.93
  5130.2  514.35  5170.3  516.58  5240.4  521.43  5290.5  522.42  5360.6  524.71
  5410.9  525.24  5460.7  527.06  5510.8  529.69  5570.9  532.04  5626.6   535.5
#Mann= 3 ,-1 , 0
  4494.2     .12       0  5007.7     .05       0  5012.2     .12       0
Bank Sta=5007.7,5012.2
XS Rating Curve= 0 ,0
Exp/Cntr=0.3,0.1

Type RM Length L Ch R = 1 ,15831   ,387,387,387
BEGIN DESCRIPTION:
TIDWELL CREEK 35.0
END DESCRIPTION:
XS GIS Cut Line= 3
      2339519.87     13711885.67      2339077.52     13711979.94
      2338469.17     13711961.84
#Sta/Elev= 30
  4488.8  524.87  4509.3  524.25  4514.4  523.53  4553.8  522.29  4558.9  521.64
  4603.3  519.88  4616.5  518.73    4688  516.84  4708.5  515.57  4759.6  513.94
  4796.4  513.33  4840.8  513.77  4902.8  513.19  4973.6  511.42  5003.6  509.65
  5021.3  509.31  5021.6  508.81  5025.6  508.81  5025.9  509.31  5053.7  510.17
  5093.7   512.3  5143.7  513.38  5163.7  514.69  5223.7  517.18    5272     520
    5277  519.91  5383.8  526.39  5473.8  530.91  5503.9  531.73  5549.7  531.61
#Mann= 3 ,-1 , 0
  4488.8     .12       0  5021.3     .05       0  5025.9     .12       0
Bank Sta=5021.3,5025.9
XS Rating Curve= 0 ,0
Exp/Cntr=0.3,0.1

Type RM Length L Ch R = 1 ,15444   ,400,400,400
BEGIN DESCRIPTION:
TIDWELL CREEK 34.0
END DESCRIPTION:
XS GIS Cut Line= 3
      2339324.96     13711674.99        2339125.       13711625.
      2338524.98       13711775.
#Sta/Elev= 30
  4794.3  523.63  4817.5  522.55  4858.7  519.77    4936  513.85  4941.1  513.97
  4977.2  510.52  4982.4  510.39  4997.8  507.75    5003  507.75  5016.1  506.78
  5016.5  506.28  5020.5  506.28  5020.8  506.78    5052  508.43  5147.3  509.91
  5183.4   511.5  5216.9  512.07  5224.6  512.92  5229.8  512.75    5271  514.13
    5320  516.21  5348.3  518.03  5353.5  517.93  5361.2  518.63    5472   524.3
  5526.1  526.57  5554.5  528.39  5559.6  528.33  5567.3   529.2  5618.9  531.14
#Mann= 3 ,-1 , 0
  4794.3     .12       0  5016.1     .05       0  5020.8     .12       0
Bank Sta=5016.1,5020.8
XS Rating Curve= 0 ,0
Exp/Cntr=0.3,0.1

Type RM Length L Ch R = 1 ,15044   ,516,516,516
BEGIN DESCRIPTION:
TIDWELL CREEK 33.0
END DESCRIPTION:
XS GIS Cut Line= 3
      2339375.03     13711325.01      2339186.29     13711240.33
      2338232.81     13711272.96
#Sta/Elev= 30
    4782  521.78  4819.5   520.3  4842.7  518.48  4858.8  518.38  4865.9  517.42
  4889.1  517.18  4940.9  513.73  4964.1  509.17  4969.5   509.1  4986.8  505.76
    4992  505.76  5000.2  504.23  5017.8  503.67  5018.1  503.17  5022.2  503.17
  5022.6  503.67  5050.2  505.88  5170.3   510.9  5221.7  511.49  5361.2  516.31
  5410.4  517.66  5480.4  517.95  5520.5  519.39  5564.7  521.09  5620.5  524.59
  5660.5  526.27  5830.6  531.27    5856  533.32    5861  533.07  5942.9  537.99
#Mann= 5 ,-1 , 0
    4782     .12       0  5017.8     .05       0  5022.6     .12       0
  5221.7     .05       0  5361.2     .12       0
Bank Sta=5017.8,5022.6
XS Rating Curve= 0 ,0
Exp/Cntr=0.3,0.1

Type RM Length L Ch R = 1 ,14528   ,466,466,466
BEGIN DESCRIPTION:
TIDWELL CREEK 32.0
END DESCRIPTION:
XS GIS Cut Line= 3
      2339724.99     13710974.99        2339325.       13710775.
        2338925.       13710425.
#Sta/Elev= 30
  4552.8  516.55  4619.9  514.66  4678.6  513.86  4700.9  514.17  4709.3  513.59
  4723.3  513.83  4807.1  511.52  4851.9  509.35  4946.9  503.64  4963.7     503
    4986  501.71  4994.8  500.78  4995.2  500.28  4999.3  500.28  4999.7  500.78
  5013.8  501.36  5021.4  502.38  5042.2  502.56  5141.9  505.63  5148.5  506.35
  5162.8  506.98  5205.5  507.62  5226.4  508.41  5254.8  511.19  5290.9  513.92
  5297.5  514.84  5311.8  515.64    5383  522.57  5528.2  534.79  5531.5  534.79
#Mann= 3 ,-1 , 0
  4552.8     .12       0  4994.8     .05       0  4999.7     .12       0
Bank Sta=4994.8,4999.7
XS Rating Curve= 0 ,0
Exp/Cntr=0.3,0.1

Type RM Length L Ch R = 1 ,14062   ,469,469,469
BEGIN DESCRIPTION:
TIDWELL CREEK 31.0
END DESCRIPTION:
XS GIS Cut Line= 3
      2339774.98     13710724.97        2339525.       13710375.
      2339124.99       13710275.
#Sta/Elev= 30
    4575  514.27  4588.5  513.45  4597.1  513.71  4632.7  512.64    4661  512.14
  4683.1  512.19  4689.3  511.54  4729.1  510.22  4896.9   503.9  4941.2  501.65
  4947.3  500.92  4976.8  498.92    4983  498.07  4989.1     498  4989.5   497.5
  4993.7   497.5    4994     498  5007.7  498.33    5036  500.03  5087.5   502.1
  5193.2  507.35  5229.3  509.78  5262.8  511.59  5311.7  515.21  5316.9  515.18
  5376.2  519.87  5394.2  521.71  5399.4  521.76  5414.8  523.48  5417.4  523.48
#Mann= 4 ,-1 , 0
    4575     .07       0  4729.1     .12       0  4989.1     .05       0
    4994     .12       0
Bank Sta=4989.1,4994
XS Rating Curve= 0 ,0
Exp/Cntr=0.3,0.1

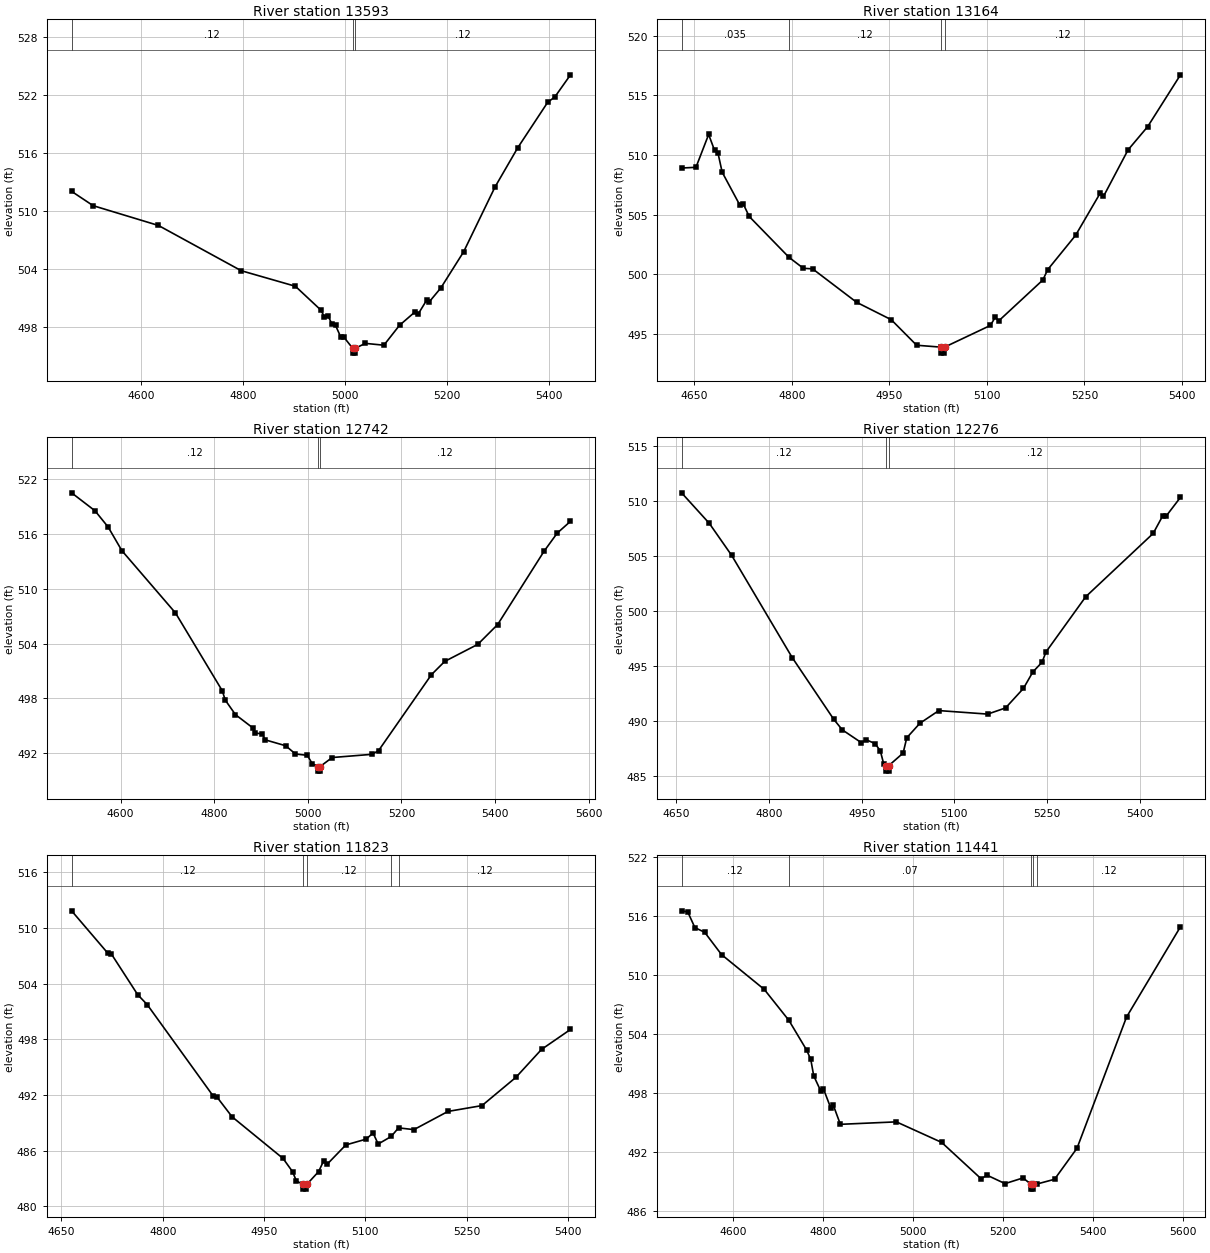
Type RM Length L Ch R = 1 ,13593   ,429,429,429
BEGIN DESCRIPTION:
TIDWELL CREEK 30.0
END DESCRIPTION:
XS GIS Cut Line= 3
      2340074.99     13710374.99        2339725.       13709975.
      2339325.01     13709775.01
#Sta/Elev= 30
  4464.3  512.01  4506.5  510.53  4634.7  508.48    4797   503.8  4903.3  502.19
  4953.6  499.71  4960.2  499.01  4967.8   499.1  4974.4  498.33    4982  498.15
  4992.5  496.91  4998.6  496.91  5015.7  495.77  5016.1  495.27  5020.3  495.27
  5020.7  495.77  5040.5  496.28  5076.9  496.09  5107.6  498.15  5138.3  499.55
  5143.9  499.29  5160.7  500.74  5166.3   500.6  5188.7  502.02  5233.4  505.76
  5294.9  512.46  5339.6  516.53  5398.3  521.23  5412.3  521.78    5443  524.07
#Mann= 3 ,-1 , 0
  4464.3     .12       0  5015.7     .05       0  5020.7     .12       0
Bank Sta=5015.7,5020.7
XS Rating Curve= 0 ,0
Exp/Cntr=0.3,0.1

Type RM Length L Ch R = 1 ,13164   ,422,422,422
BEGIN DESCRIPTION:
TIDWELL CREEK 29.0
END DESCRIPTION:
XS GIS Cut Line= 3
      2340174.98     13709674.99        2339825.       13709575.
      2339424.99       13709625.
#Sta/Elev= 30
  4630.6   508.9  4652.7  508.96  4672.2  511.71  4681.3  510.38  4686.5  510.17
    4693  508.55  4720.3  505.78  4725.5  505.88  4734.6  504.84  4795.9  501.41
  4817.8   500.5  4832.1  500.45  4899.7  497.65    4953  496.19    4992  494.05
  5029.9  493.89  5030.2  493.39  5034.5  493.39  5034.9  493.89  5105.4  495.71
    5113  496.41    5118  496.08  5186.1  499.52  5193.6  500.39  5236.4  503.26
  5274.2  506.79  5279.3  506.52  5317.1  510.42  5347.3  512.37  5397.7  516.71
#Mann= 4 ,-1 , 0
  4630.6    .035       0  4795.9     .12       0  5029.9     .05       0
  5034.9     .12       0
Bank Sta=5029.9,5034.9
XS Rating Curve= 0 ,0
Exp/Cntr=0.3,0.1

Type RM Length L Ch R = 1 ,12742   ,466,466,466
BEGIN DESCRIPTION:
TIDWELL CREEK 28.0
END DESCRIPTION:
XS GIS Cut Line= 3
        2340425.       13709525.        2340025.       13709225.
      2339624.99     13708824.99
#Sta/Elev= 30
  4495.4  520.52  4545.4  518.55  4573.5  516.77  4602.7  514.19  4717.3  507.36
  4817.3  498.83  4823.5  497.82  4845.4  496.22  4881.9  494.79  4888.1   494.2
  4902.7  494.11  4908.9  493.46  4952.7  492.81  4973.5  491.91  4998.9  491.76
  5009.5  490.84  5021.1  490.53  5021.5  490.03  5025.8  490.03  5026.2  490.53
    5052  491.52  5136.8  491.87    5151  492.27  5264.1   500.6  5292.4  502.05
  5363.1  503.92  5405.5  506.09  5504.5  514.11  5532.8  516.11  5561.1   517.4
#Mann= 3 ,-1 , 0
  4495.4     .12       0  5021.1     .05       0  5026.2     .12       0
Bank Sta=5021.1,5026.2
XS Rating Curve= 0 ,0
Exp/Cntr=0.3,0.1

Type RM Length L Ch R = 1 ,12276   ,453,453,453
BEGIN DESCRIPTION:
TIDWELL CREEK 27.0
END DESCRIPTION:
XS GIS Cut Line= 3
      2340575.03     13709025.02        2340275.       13708875.
      2339875.04     13708625.02
#Sta/Elev= 30
  4658.7  510.72  4703.5  507.95  4739.8  505.03  4837.6  495.76  4904.7  490.16
  4918.7  489.19  4949.4  488.03  4957.8  488.28  4971.8  487.94  4980.2  487.28
  4985.8  486.07  4988.7  485.94  4989.1  485.44  4993.5  485.44  4993.9  485.94
  5017.1  487.08    5023  488.47  5044.3  489.79  5074.9  490.94  5153.9  490.62
  5182.8  491.18  5211.7  492.95    5227  494.45  5241.8  495.33  5248.3  496.27
  5312.5  501.28  5421.6  507.03    5437  508.62  5442.8  508.62  5465.8  510.31
#Mann= 3 ,-1 , 0
  4658.7     .12       0  4988.7     .05       0  4993.9     .12       0
Bank Sta=4988.7,4993.9
XS Rating Curve= 0 ,0
Exp/Cntr=0.3,0.1

Type RM Length L Ch R = 1 ,11823   ,382,382,382
BEGIN DESCRIPTION:
TIDWELL CREEK 26.0
END DESCRIPTION:
XS GIS Cut Line= 3
      2340775.04     13708675.02        2340475.       13708525.
      2340074.97       13708475.
#Sta/Elev= 30
    4665  511.83  4718.2   507.3  4723.7   507.2  4762.9  502.79  4776.9  501.73
  4874.7  491.87  4880.3  491.76  4902.6  489.64  4978.1  485.15  4992.1  483.73
  4997.7  482.74  5007.9  482.35  5008.3  481.85  5012.7  481.85  5013.1  482.35
  5030.7  483.74  5038.3  484.92  5043.3  484.53    5071  486.61  5101.2  487.24
  5111.3   487.9  5118.9  486.71  5138.1  487.52    5149  488.45  5171.8  488.26
  5222.2  490.22  5272.6  490.85  5322.9   493.9  5360.7   496.9  5403.6  499.05
#Mann= 5 ,-1 , 0
    4665     .12       0  5007.9     .05       0  5013.1     .12       0
  5138.1     .07       0    5149     .12       0
Bank Sta=5007.9,5013.1
XS Rating Curve= 0 ,0
Exp/Cntr=0.3,0.1

Type RM Length L Ch R = 1 ,11441   ,443,443,443
BEGIN DESCRIPTION:
TIDWELL CREEK 25.0
END DESCRIPTION:
XS GIS Cut Line= 4
      2340975.01     13708375.01      2340590.35     13708157.47
        2340325.       13708125.      2339925.04       13708125.
#Sta/Elev= 30
    4485  516.49  4498.7  516.38  4514.6  514.78  4536.3  514.31  4573.8  512.04
  4668.8   508.5  4723.6  505.35  4762.9  502.34  4772.2  501.38  4778.8  499.71
  4794.7  498.14  4800.4  498.39  4816.3  496.48  4822.1  496.75    4838  494.78
  4962.5  495.03  5063.3  492.94    5151  489.24    5164  489.61  5204.2  488.75
  5244.2  489.33  5261.6  488.69    5262  488.19  5266.5  488.19  5266.9  488.69
  5274.2   488.7  5314.2  489.19  5364.2  492.35  5474.2  505.68  5594.2  514.87
#Mann= 5 ,-1 , 0
    4485     .12       0  4723.6     .07       0  5261.6     .05       0
  5266.9     .07       0  5274.2     .12       0
Bank Sta=5261.6,5266.9
XS Rating Curve= 0 ,0
Exp/Cntr=0.3,0.1

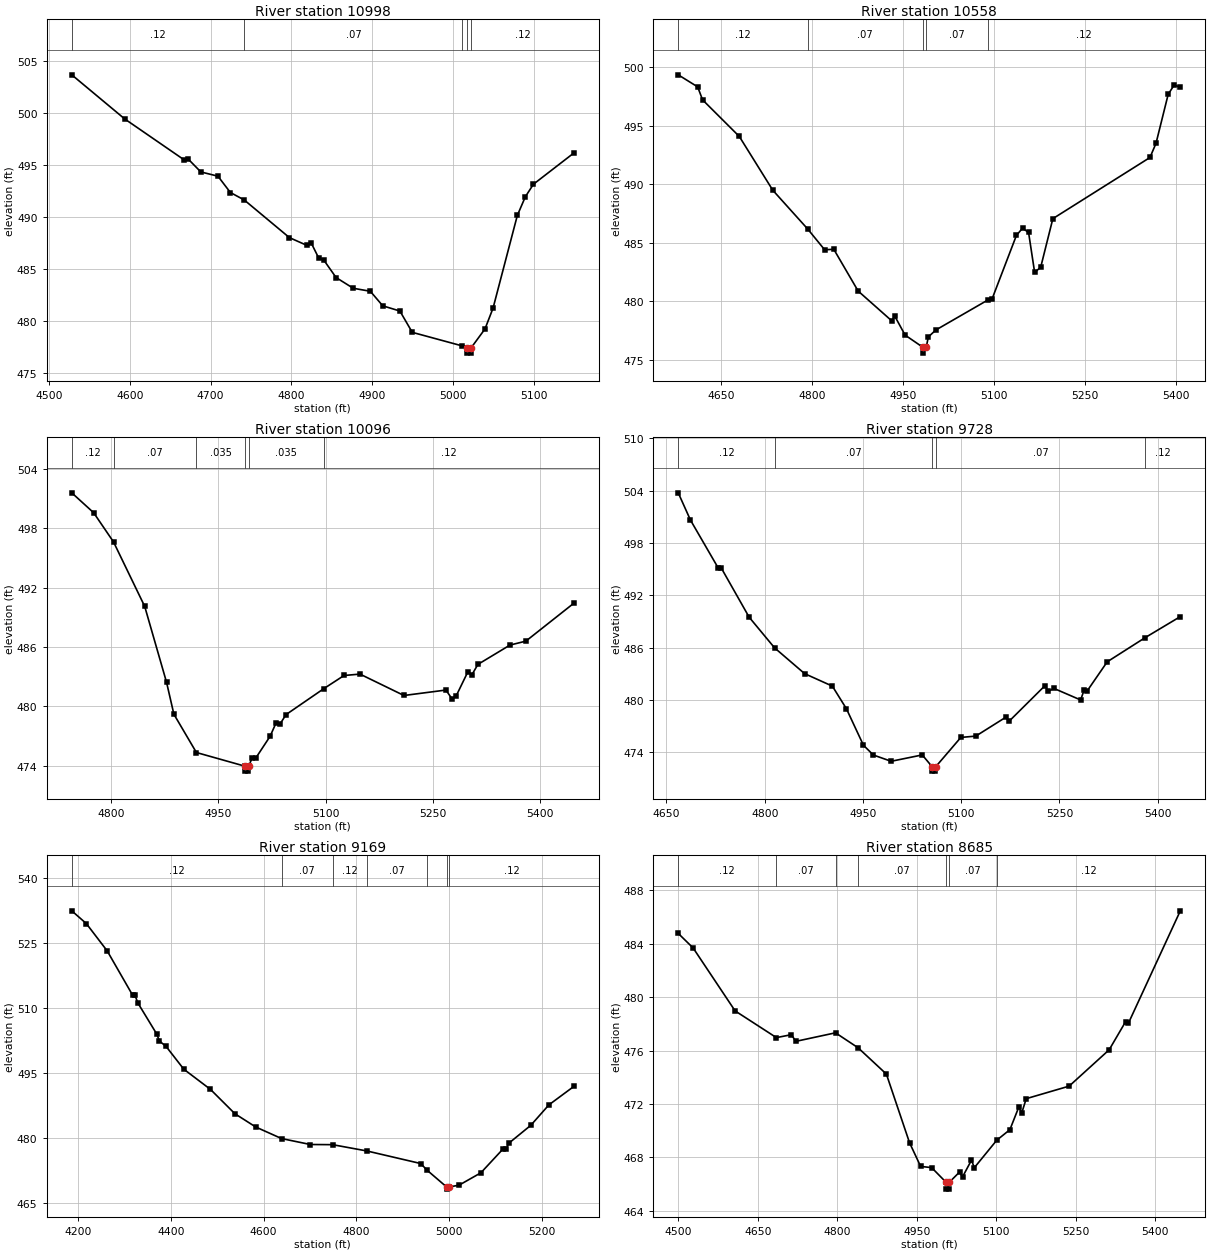
Type RM Length L Ch R = 1 ,10998   ,440,440,440
BEGIN DESCRIPTION:
TIDWELL CREEK 24.0
END DESCRIPTION:
XS GIS Cut Line= 3
      2340825.02     13707975.01        2340425.       13707725.
      2340275.03       13707725.
#Sta/Elev= 30
  4528.2  503.69  4593.7  499.45  4666.8  495.54  4672.7  495.56    4688  494.35
  4709.2  493.94  4724.6  492.37  4741.8  491.65  4797.7  488.03  4818.9   487.3
  4824.8   487.5  4834.2  486.03  4840.1  485.89  4855.5  484.19  4876.7  483.16
  4897.9  482.87  4913.3  481.47  4934.5  480.97  4949.8  478.92  5011.9  477.61
  5017.3  477.42  5017.7  476.92  5022.2  476.92  5022.6  477.42  5039.9  479.25
  5049.9  481.26  5079.9  490.16  5089.9  491.97  5099.9  493.17  5149.9  496.17
#Mann= 5 ,-1 , 0
  4528.2     .12       0  4741.8     .07       0  5011.9     .12       0
  5017.3     .05       0  5022.6     .12       0
Bank Sta=5017.3,5022.6
XS Rating Curve= 0 ,0
Exp/Cntr=0.3,0.1

Type RM Length L Ch R = 1 ,10558   ,462,462,462
BEGIN DESCRIPTION:
TIDWELL CREEK 23.0
END DESCRIPTION:
XS GIS Cut Line= 3
      2340925.01       13707225.        2340525.       13707375.
      2340125.01       13707375.
#Sta/Elev= 30
  4579.5  499.37  4611.5  498.34  4619.6  497.23  4680.1   494.1  4735.3   489.5
  4792.7  486.19  4820.7  484.41  4835.8  484.45  4875.9  480.88  4931.1  478.34
  4936.4  478.72  4953.3  477.11  4982.6  476.07  4983.1  475.57    4988  476.07
  4991.6  476.96    5004  477.55  5089.5  480.11  5096.7  480.22  5136.7  485.64
  5146.7  486.25  5156.7  485.89  5166.7  482.47  5176.7  482.92  5196.7  487.07
  5356.7   492.3  5366.7  493.52  5386.7   497.7  5396.7  498.51  5406.7  498.29
#Mann= 5 ,-1 , 0
  4579.5     .12       0  4792.7     .07       0  4982.6     .05       0
    4988     .07       0  5089.5     .12       0
Bank Sta=4982.6,4988
XS Rating Curve= 0 ,0
Exp/Cntr=0.3,0.1

Type RM Length L Ch R = 1 ,10096   ,368,368,368
BEGIN DESCRIPTION:
TIDWELL CREEK 22.0
END DESCRIPTION:
XS GIS Cut Line= 3
      2340825.04     13706975.01        2340575.       13706925.
        2340175.       13707125.
#Sta/Elev= 30
  4745.1  501.57  4775.7  499.56  4803.5  496.61  4847.1   490.1  4877.7  482.42
  4887.9  479.21  4919.4  475.34  4987.2  473.96  4987.6  473.46  4992.1  473.46
  4992.6  473.96  4997.5  474.83  5002.9  474.83  5022.5  476.98  5030.8  478.33
  5036.4  478.22  5044.8  479.17  5097.8   481.8  5125.9  483.12  5148.2  483.26
  5209.7   481.1  5268.4  481.65  5276.8  480.77  5282.4  481.01  5299.2  483.51
  5304.8   483.2  5313.1  484.24  5357.9  486.19  5380.2  486.59  5447.3  490.42
#Mann= 6 ,-1 , 0
  4745.1     .12       0  4803.5     .07       0  4919.4    .035       0
  4987.2    .035       0  4992.6    .035       0  5097.8     .12       0
Bank Sta=4987.2,4992.6
XS Rating Curve= 0 ,0
Exp/Cntr=0.3,0.1

Type RM Length L Ch R = 1 ,9728    ,559,559,559
BEGIN DESCRIPTION:
TIDWELL CREEK 21.0
END DESCRIPTION:
XS GIS Cut Line= 3
      2340774.96     13706525.01      2340335.58     13706628.66
      2340025.02       13706575.
#Sta/Elev= 30
    4668  503.76  4686.6  500.64  4728.9  495.15    4734  495.09  4776.3  489.48
    4815  485.97    4861     483  4903.3  481.57  4924.8  478.97  4950.8  474.78
  4965.9  473.66  4993.1  472.94  5040.6  473.67  5055.7  472.31  5056.1  471.81
  5060.7  471.81  5061.1  472.31  5099.5  475.68  5122.3  475.83    5168  477.99
  5173.1  477.53  5227.8  481.61  5232.9  480.99  5241.8   481.3  5282.4  479.98
  5287.6  481.09  5292.7  481.05    5323  484.36  5380.6  487.12  5434.6  489.55
#Mann= 5 ,-1 , 0
    4668     .12       0    4815     .07       0  5055.7     .05       0
  5061.1     .07       0  5380.6     .12       0
Bank Sta=5055.7,5061.1
XS Rating Curve= 0 ,0
Exp/Cntr=0.3,0.1

Type RM Length L Ch R = 1 ,9169    ,484,484,484
BEGIN DESCRIPTION:
TIDWELL CREEK 20.0
END DESCRIPTION:
XS GIS Cut Line= 3
      2340975.03     13706325.01        2340175.       13706175.
      2339925.03     13706274.99
#Sta/Elev= 30
    4186   532.4  4217.4  529.46  4262.3  523.18  4317.4  512.93  4322.5   512.9
  4328.5  511.17  4369.2  504.01  4375.1  502.38  4389.5  501.13  4427.7  495.88
  4485.3  491.22  4537.9  485.62  4582.8  482.56  4638.6  479.89  4700.7  478.52
  4748.7  478.48  4822.7  477.03  4938.9  474.13  4952.6  472.59  4994.7  468.73
  4995.1  468.23  5000.2  468.73  5021.5  469.14  5068.6  471.99  5117.1  477.57
  5122.5  477.45  5129.2  478.84  5176.3  482.94  5215.4  487.66  5269.2  491.91
#Mann= 7 ,-1 , 0
    4186     .12       0  4638.6     .07       0  4748.7     .12       0
  4822.7     .07       0  4952.6     .12       0  4994.7     .05       0
  5000.2     .12       0
Bank Sta=4994.7,5000.2
XS Rating Curve= 0 ,0
Exp/Cntr=0.3,0.1

Type RM Length L Ch R = 1 ,8685    ,452,452,452
BEGIN DESCRIPTION:
TIDWELL CREEK 19.0
END DESCRIPTION:
XS GIS Cut Line= 3
      2340674.97     13706024.98        2340275.       13705725.
      2339874.98     13705925.01
#Sta/Elev= 30
    4500  484.77  4528.1  483.68  4607.3  478.97  4685.2  476.97  4713.5  477.19
  4721.8  476.69  4796.7  477.33  4839.3  476.21  4892.7  474.24  4936.4   469.1
  4957.3  467.33  4978.1  467.24  5005.6  466.13    5006  465.63  5010.7  465.63
  5011.1  466.13  5030.7  466.91  5036.3  466.54  5053.1  467.79  5058.7  467.24
  5100.9  469.29  5125.7  470.08  5142.5  471.77  5148.1  471.34  5156.5   472.4
  5237.5  473.34    5313  476.06  5343.8  478.15  5349.3  478.05  5447.2  486.46
#Mann= 7 ,-1 , 0
    4500     .12       0  4685.2     .07       0  4796.7     .12       0
  4839.3     .07       0  5005.6     .05       0  5011.1     .07       0
  5100.9     .12       0
Bank Sta=5005.6,5011.1
XS Rating Curve= 0 ,0
Exp/Cntr=0.3,0.1

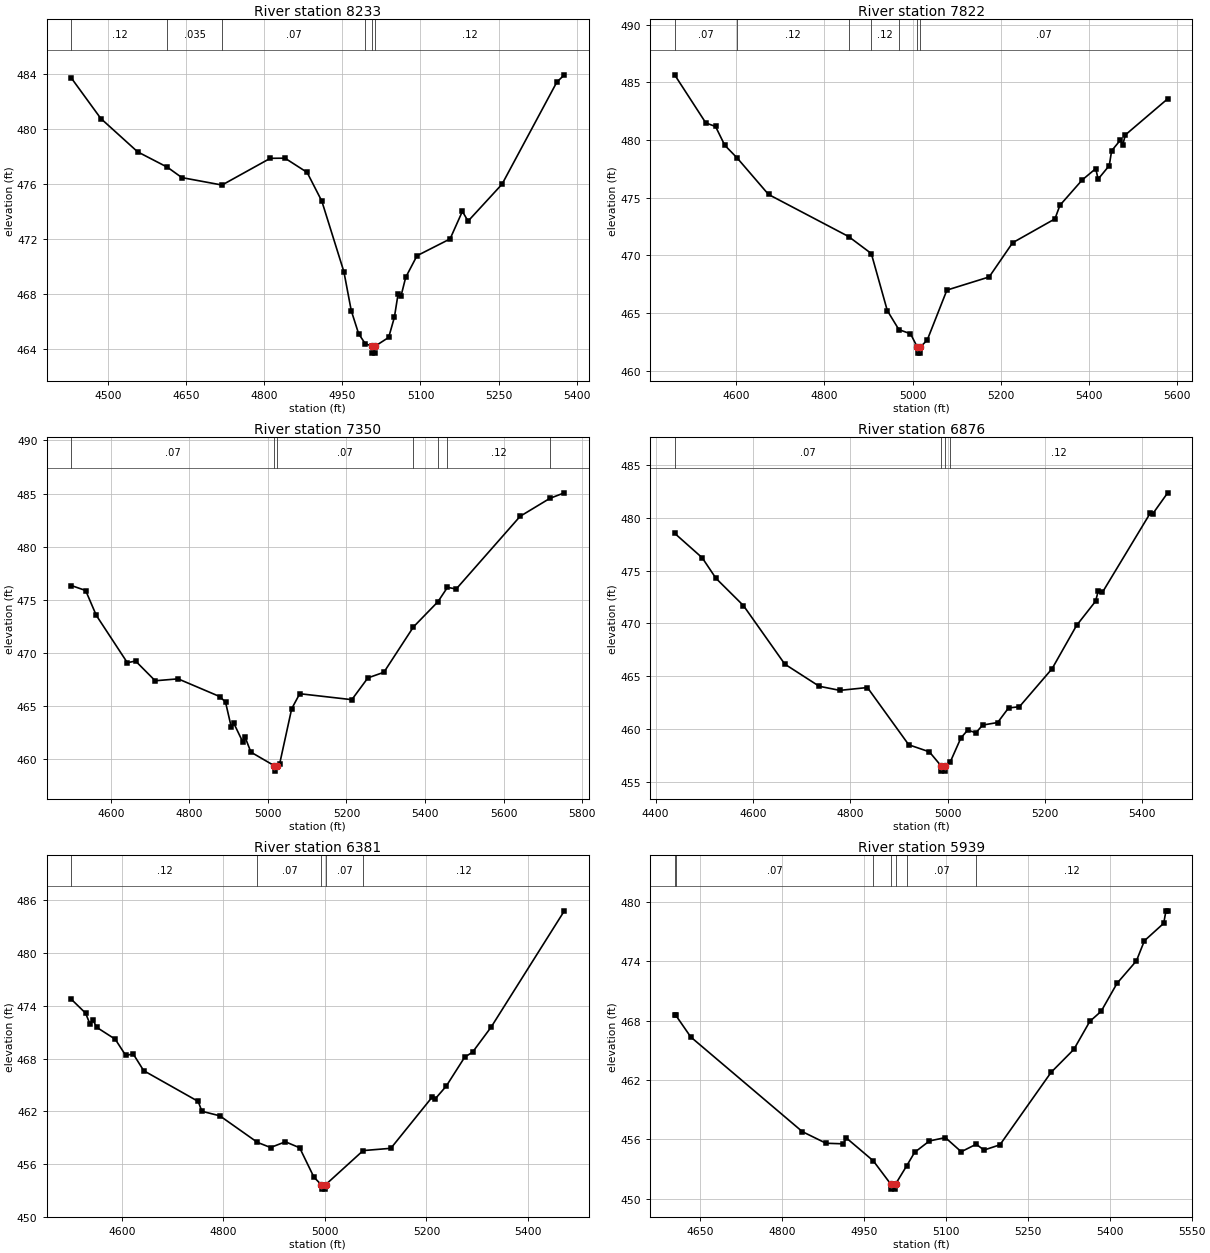
Type RM Length L Ch R = 1 ,8233    ,411,411,411
BEGIN DESCRIPTION:
TIDWELL CREEK 18.0
END DESCRIPTION:
XS GIS Cut Line= 3
      2340825.03     13705725.03        2340425.       13705325.
      2340075.01     13705175.01
#Sta/Elev= 30
  4429.7  483.68  4486.3  480.74    4557  478.32  4614.3   477.2  4641.9  476.45
    4719  475.91  4811.6  477.85  4839.9  477.86  4882.3  476.83  4910.6  474.74
    4953  469.61  4967.1  466.79  4981.3  465.11  4993.9   464.4  5007.1  464.21
  5007.6  463.71  5012.3  463.71  5012.7  464.21  5038.9  464.85  5049.8   466.3
  5057.1  468.03  5062.5  467.84  5071.6  469.21  5093.3  470.78  5156.8     472
  5180.4     474  5191.3  473.29  5256.5  475.97  5361.7  483.38  5376.2  483.91
#Mann= 6 ,-1 , 0
  4429.7     .12       0  4614.3    .035       0    4719     .07       0
  4993.9     .12       0  5007.1     .05       0  5012.7     .12       0
Bank Sta=5007.1,5012.7
XS Rating Curve= 0 ,0
Exp/Cntr=0.3,0.1

Type RM Length L Ch R = 1 ,7822    ,472,472,472
BEGIN DESCRIPTION:
TIDWELL CREEK 17.0
END DESCRIPTION:
XS GIS Cut Line= 3
      2341075.02     13705375.02        2340675.       13705025.
      2340124.97     13704824.99
#Sta/Elev= 30
  4461.2  485.66  4531.9  481.48  4553.8  481.18  4574.7  479.55  4602.9  478.44
  4673.8  475.28  4855.1  471.63  4906.7  470.15  4942.9   465.2  4969.1  463.55
  4995.4  463.19  5011.2  462.01  5011.6  461.51  5016.4  461.51  5016.9  462.01
  5033.3  462.64  5077.9  466.98  5173.6  468.12  5226.8  471.09  5322.6  473.16
  5333.9  474.34  5384.4  476.54    5415  477.52  5420.4  476.61  5445.6  477.78
    5451  479.07  5470.9     480  5476.2   479.6  5482.2  480.45    5578  483.58
#Mann= 7 ,-1 , 0
  4461.2     .07       0  4602.9     .12       0  4855.1     .07       0
  4906.7     .12       0  4969.1     .07       0  5011.2     .05       0
  5016.9     .07       0
Bank Sta=5011.2,5016.9
XS Rating Curve= 0 ,0
Exp/Cntr=0.3,0.1

Type RM Length L Ch R = 1 ,7350    ,474,474,474
BEGIN DESCRIPTION:
TIDWELL CREEK 16.0
END DESCRIPTION:
XS GIS Cut Line= 3
      2341175.01     13704925.01        2340775.       13704625.
      2340034.66     13704776.02
#Sta/Elev= 30
  4499.4  476.34  4535.9  475.87    4563  473.53  4642.1  469.07    4663  469.23
    4713  467.37  4771.3  467.55  4877.5  465.88  4892.1  465.36  4906.7  463.01
    4913  463.38  4935.9  461.62  4942.1  462.04  4956.7  460.65  5016.7  459.36
  5017.2  458.86  5022.4  459.36    5030  459.56  5060.6  464.74  5081.1  466.15
  5213.7  465.59  5254.6  467.64  5295.4  468.17  5370.6  472.44  5432.9  474.81
  5457.3  476.17  5479.5  476.01  5642.4  482.86  5718.1  484.55    5755  485.07
#Mann= 7 ,-1 , 0
  4499.4     .07       0  5016.7     .05       0  5022.4     .07       0
  5370.6    .035       0  5432.9     .07       0  5457.3     .12       0
  5718.1     .07       0
Bank Sta=5016.7,5022.4
XS Rating Curve= 0 ,0
Exp/Cntr=0.3,0.1

Type RM Length L Ch R = 1 ,6876    ,495,495,495
BEGIN DESCRIPTION:
TIDWELL CREEK 15.0
END DESCRIPTION:
XS GIS Cut Line= 3
      2341375.02     13704625.02        2340975.       13704225.
      2340775.01     13703825.02
#Sta/Elev= 30
  4439.1  478.55  4495.7  476.23    4524  474.28  4580.5  471.69  4665.4  466.14
  4736.1  464.04  4778.5  463.65  4835.1  463.92    4920  458.49  4962.4  457.82
  4986.4  456.49  4986.9  455.99  4994.4  455.99  4994.9  456.49  5005.6  456.89
  5027.2  459.14  5041.1  459.88  5057.9  459.63  5071.9  460.36  5102.6   460.6
    5125  461.98  5147.4   462.1  5214.4   465.7  5264.8  469.81  5303.9  472.11
  5309.5  473.12  5317.9  472.95  5415.7  480.43  5421.3   480.4    5452  482.39
#Mann= 4 ,-1 , 0
  4439.1     .07       0  4986.4     .05       0  4994.9     .07       0
  5005.6     .12       0
Bank Sta=4986.4,4994.9
XS Rating Curve= 0 ,0
Exp/Cntr=0.3,0.1

Type RM Length L Ch R = 1 ,6381    ,442,442,442
BEGIN DESCRIPTION:
TIDWELL CREEK 14.0
END DESCRIPTION:
XS GIS Cut Line= 3
      2341725.02     13704175.01        2341325.       13703875.
      2340925.02     13703625.01
#Sta/Elev= 30
  4500.2  474.74  4528.3  473.16  4536.7  471.96  4542.9  472.38  4550.2  471.55
  4586.7   470.2  4607.5  468.35  4622.1  468.53  4642.9  466.62  4750.2  463.13
  4757.5  462.01  4792.9  461.49  4867.1  458.47  4892.9  457.89  4922.1  458.54
  4950.2  457.86  4978.3  454.52  4992.8  453.66  4993.3  453.16  5000.8  453.16
  5001.3  453.66  5075.3  457.54  5129.9   457.8  5211.9  463.66  5217.8  463.45
    5239  464.86  5275.6  468.17  5290.9  468.72  5327.5  471.57  5471.9  484.79
#Mann= 5 ,-1 , 0
  4500.2     .12       0  4867.1     .07       0  4992.8     .05       0
  5001.3     .07       0  5075.3     .12       0
Bank Sta=4992.8,5001.3
XS Rating Curve= 0 ,0
Exp/Cntr=0.3,0.1

Type RM Length L Ch R = 1 ,5939    ,469,469,469
BEGIN DESCRIPTION:
TIDWELL CREEK 13.0
END DESCRIPTION:
XS GIS Cut Line= 3
      2341775.02     13703875.04        2341575.       13703525.
      2341174.97     13703224.98
#Sta/Elev= 30
  4602.9  468.51  4605.2  468.51  4632.5  466.33  4836.9  456.76  4880.1  455.59
  4911.8  455.53  4917.5  456.12  4966.8  453.81  4998.9  451.45  4999.4  450.95
    5007  450.95  5007.5  451.45  5027.7  453.28  5042.5  454.67  5069.6  455.82
  5098.8  456.16  5127.9  454.73  5155.3  455.49  5169.6   454.9  5198.8  455.43
  5292.5  462.76  5334.2  465.08  5363.4  467.91  5384.2  468.93  5413.4  471.77
  5448.8  474.03  5463.4  476.06  5498.8  477.83  5502.9  479.09  5506.1  479.09
#Mann= 7 ,-1 , 0
  4602.9     .12       0  4605.2     .07       0  4966.8    .035       0
  4998.9    .035       0  5007.5    .035       0  5027.7     .07       0
  5155.3     .12       0
Bank Sta=4998.9,5007.5
XS Rating Curve= 0 ,0
Exp/Cntr=0.3,0.1

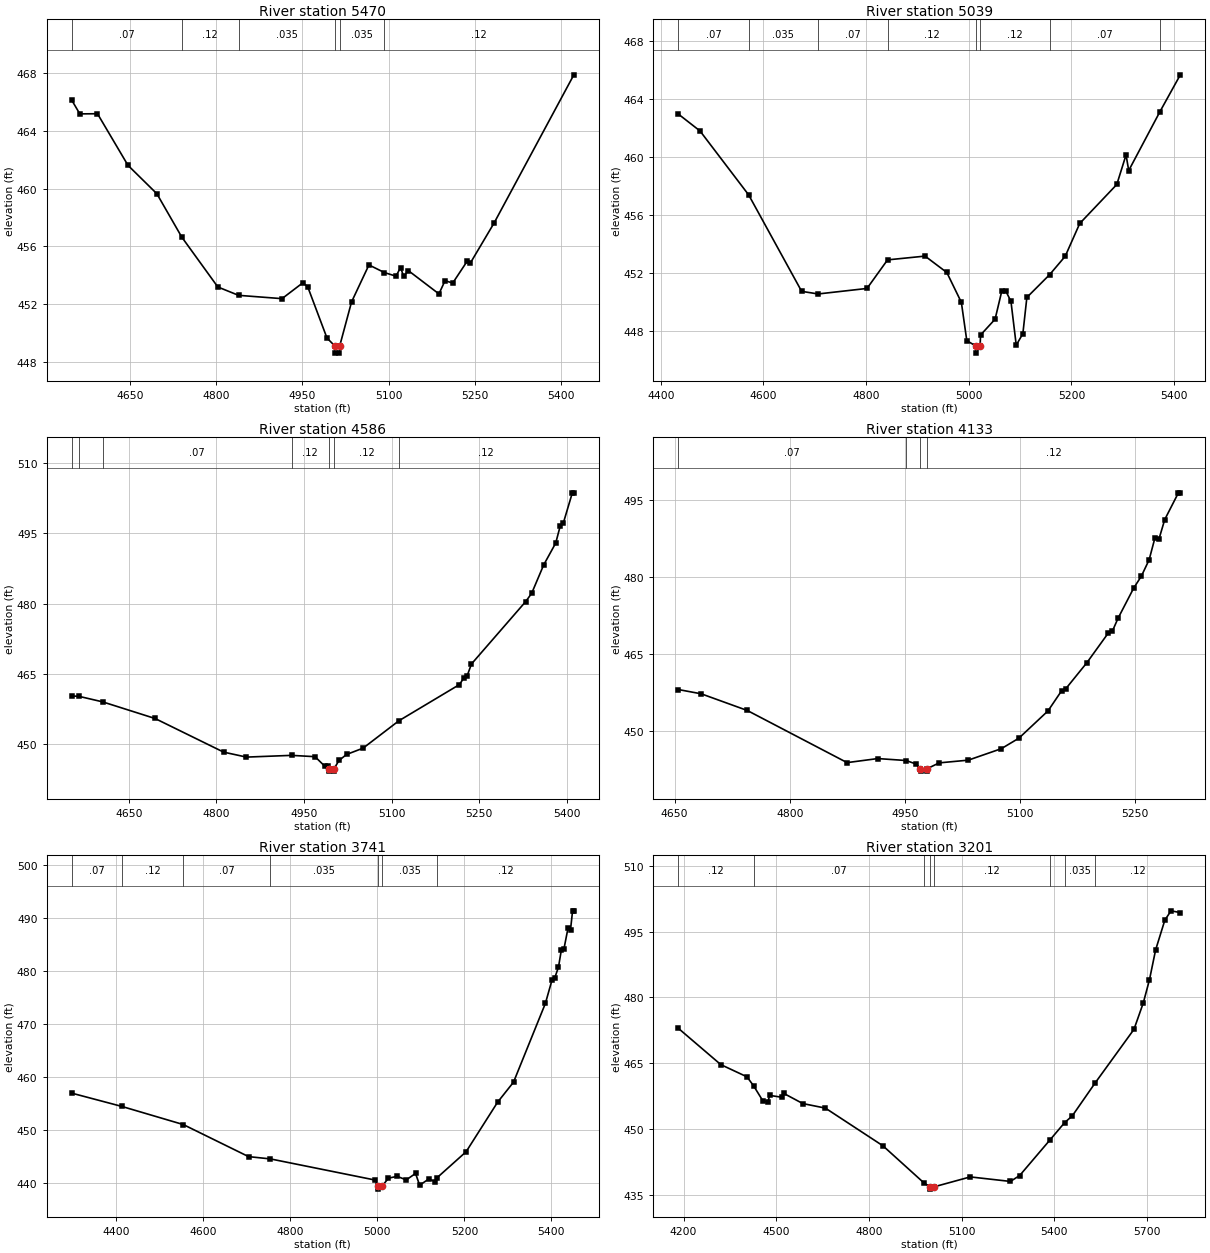
Type RM Length L Ch R = 1 ,5470    ,431,431,431
BEGIN DESCRIPTION:
TIDWELL CREEK 12.0
END DESCRIPTION:
XS GIS Cut Line= 3
      2342175.04     13703325.02        2341775.       13703125.
      2341374.96     13702974.98
#Sta/Elev= 30
  4548.2  466.14  4562.2  465.19    4593   465.2  4646.1  461.62  4696.4  459.65
  4739.8  456.64  4802.6  453.18  4838.7   452.6  4914.4  452.37  4950.7  453.47
  4959.1   453.2  4992.7  449.64  5006.3  449.09  5006.8  448.59  5014.4  448.59
  5014.9  449.09  5035.5  452.14  5065.8  454.71  5092.7  454.18  5112.9  453.93
  5120.9  454.53  5126.3  453.91  5134.3  454.32  5187.7   452.7  5198.4  453.62
  5211.7  453.45  5236.6  454.95    5242  454.81  5283.8  457.62  5422.7   467.9
#Mann= 6 ,-1 , 0
  4548.2     .07       0  4739.8     .12       0  4838.7    .035       0
  5006.3    .035       0  5014.9    .035       0  5092.7     .12       0
Bank Sta=5006.3,5014.9
XS Rating Curve= 0 ,0
Exp/Cntr=0.3,0.1

Type RM Length L Ch R = 1 ,5039    ,453,453,453
BEGIN DESCRIPTION:
TIDWELL CREEK 11.0
END DESCRIPTION:
XS GIS Cut Line= 3
      2342274.99     13703124.99        2341875.       13702725.
      2341774.99     13702324.98
#Sta/Elev= 30
  4434.1  462.96  4476.5  461.79  4571.3  457.38  4674.5  450.73  4706.6  450.55
  4801.8  450.93  4841.8   452.9  4914.9  453.16  4957.3  452.03  4985.6  449.97
  4996.2  447.33  5013.5  446.97    5014  446.47  5022.1  446.97    5023  447.72
  5051.3  448.81  5064.2  450.73  5071.9  450.77  5082.2  450.04  5092.5  447.02
  5105.4  447.81  5113.2  450.31  5157.5  451.88  5187.9  453.15  5216.2  455.41
  5288.4   458.1  5306.4  460.14  5311.6  459.06  5372.1   463.1  5412.1  465.66
#Mann= 8 ,-1 , 0
  4434.1     .07       0  4571.3    .035       0  4706.6     .07       0
  4841.8     .12       0  5013.5     .05       0  5022.1     .12       0
  5157.5     .07       0  5372.1     .12       0
Bank Sta=5013.5,5022.1
XS Rating Curve= 0 ,0
Exp/Cntr=0.3,0.1

Type RM Length L Ch R = 1 ,4586    ,453,453,453
BEGIN DESCRIPTION:
TIDWELL CREEK 10.0
END DESCRIPTION:
XS GIS Cut Line= 3
      2342425.01     13702925.03        2342225.       13702525.
      2342124.99     13702124.95
#Sta/Elev= 30
  4552.4  460.32  4564.2  460.27  4605.1  459.08    4695  455.53  4812.4  448.36
  4851.5   447.3  4928.6  447.67  4968.9  447.39  4985.7  445.34  4991.3  445.37
  4992.2  444.81  4992.7  444.31  5000.9  444.31  5001.4  444.81  5009.9  446.58
  5022.8  447.86  5051.2  449.21  5112.4  455.04  5216.1  462.76  5223.8   464.2
    5229  464.52  5236.7  467.15  5329.5  480.45  5339.8  482.22  5360.4  488.28
    5381  492.94  5388.8  496.64  5393.9  497.16  5409.4  503.64    5412  503.64
#Mann= 7 ,-1 , 0
  4552.4    .035       0  4564.2     .12       0  4605.1     .07       0
  4928.6     .12       0  4992.2     .05       0  5001.4     .12       0
  5112.4     .12       0
Bank Sta=4992.2,5001.4
XS Rating Curve= 0 ,0
Exp/Cntr=0.3,0.1

Type RM Length L Ch R = 1 ,4133    ,392,392,392
BEGIN DESCRIPTION:
TIDWELL CREEK 9.0
END DESCRIPTION:
XS GIS Cut Line= 3
        2342625.     13702725.05        2342625.       13702375.
        2342575.     13702074.98
#Sta/Elev= 30
  4654.7  458.11  4684.7  457.27  4744.7  454.02  4874.7  443.85  4914.7  444.64
  4951.6  444.26  4964.7  443.57  4970.1  442.69  4970.6  442.19  4978.9  442.19
  4979.4  442.69  4994.7   443.8  5032.6  444.33  5075.7  446.57  5098.5  448.61
  5136.5  453.94  5154.3  457.88  5159.4  458.21  5187.2  463.35  5215.1  469.14
  5220.2  469.44  5227.8  472.02  5248.1  477.88  5258.2  480.24  5268.3  483.43
  5275.9  487.73    5281  487.41  5288.6  491.26  5306.4  496.48  5308.9  496.48
#Mann= 4 ,-1 , 0
  4654.7     .07       0  4951.6     .12       0  4970.1     .05       0
  4979.4     .12       0
Bank Sta=4970.1,4979.4
XS Rating Curve= 0 ,0
Exp/Cntr=0.3,0.1

Type RM Length L Ch R = 1 ,3741    ,540,540,540
BEGIN DESCRIPTION:
TIDWELL CREEK 8.0
END DESCRIPTION:
XS GIS Cut Line= 4
      2342699.43     13702897.99      2342960.47      13702586.2
      2342960.47     13702234.52      2342625.02     13702025.01
#Sta/Elev= 30
  4297.7  456.95  4412.2  454.46  4553.9  451.03    4704  444.98  4754.1  444.55
  4995.5  440.55  5000.9  439.35  5001.4  438.85  5010.2  439.35  5025.5  440.92
  5045.5  441.26  5066.4  440.59  5087.7  441.81  5097.1  439.59  5118.3  440.77
  5133.2  440.23  5137.3  441.01  5203.9   445.9  5276.4  455.26  5312.9  459.03
  5386.1  473.88  5401.4  478.32  5407.3  478.62  5416.2  480.73  5422.6  483.87
  5428.5  484.05    5438  488.04  5443.9  487.81  5448.6  491.34  5451.5  491.34
#Mann= 7 ,-1 , 0
  4297.7     .07       0  4412.2     .12       0  4553.9     .07       0
  4754.1    .035       0  5000.9    .035       0  5010.2    .035       0
  5137.3     .12       0
Bank Sta=5000.9,5010.2
XS Rating Curve= 0 ,0
Exp/Cntr=0.3,0.1

Type RM Length L Ch R = 1 ,3201    ,413,413,413
BEGIN DESCRIPTION:
TIDWELL CREEK 7.0
END DESCRIPTION:
XS GIS Cut Line= 3
      2344058.98     13702317.67      2343236.01      13701919.1
      2342525.04       13701925.
#Sta/Elev= 30
  4182.6  473.01  4320.4  464.73  4405.2  461.95  4427.1  459.85  4455.9  456.56
  4472.9   456.2  4478.5  457.73  4518.1   457.3  4523.7   458.2  4585.8  455.87
  4659.1  454.83  4845.4  446.25  4978.3   437.8  4997.2   436.9  4997.7   436.4
  5009.6   436.9    5128  439.18    5258  438.15    5288   439.5    5387  447.67
  5433.7  451.55    5458  453.04  5532.1  460.54    5658  472.76    5688  478.74
    5708  483.99    5728  490.81    5758  497.62    5778  499.72    5808  499.32
#Mann= 8 ,-1 , 0
  4182.6     .12       0  4427.1     .07       0  4978.3     .12       0
  4997.2     .05       0  5009.6     .12       0    5387     .07       0
  5433.7    .035       0  5532.1     .12       0
Bank Sta=4997.2,5009.6
XS Rating Curve= 0 ,0
Exp/Cntr=0.3,0.1