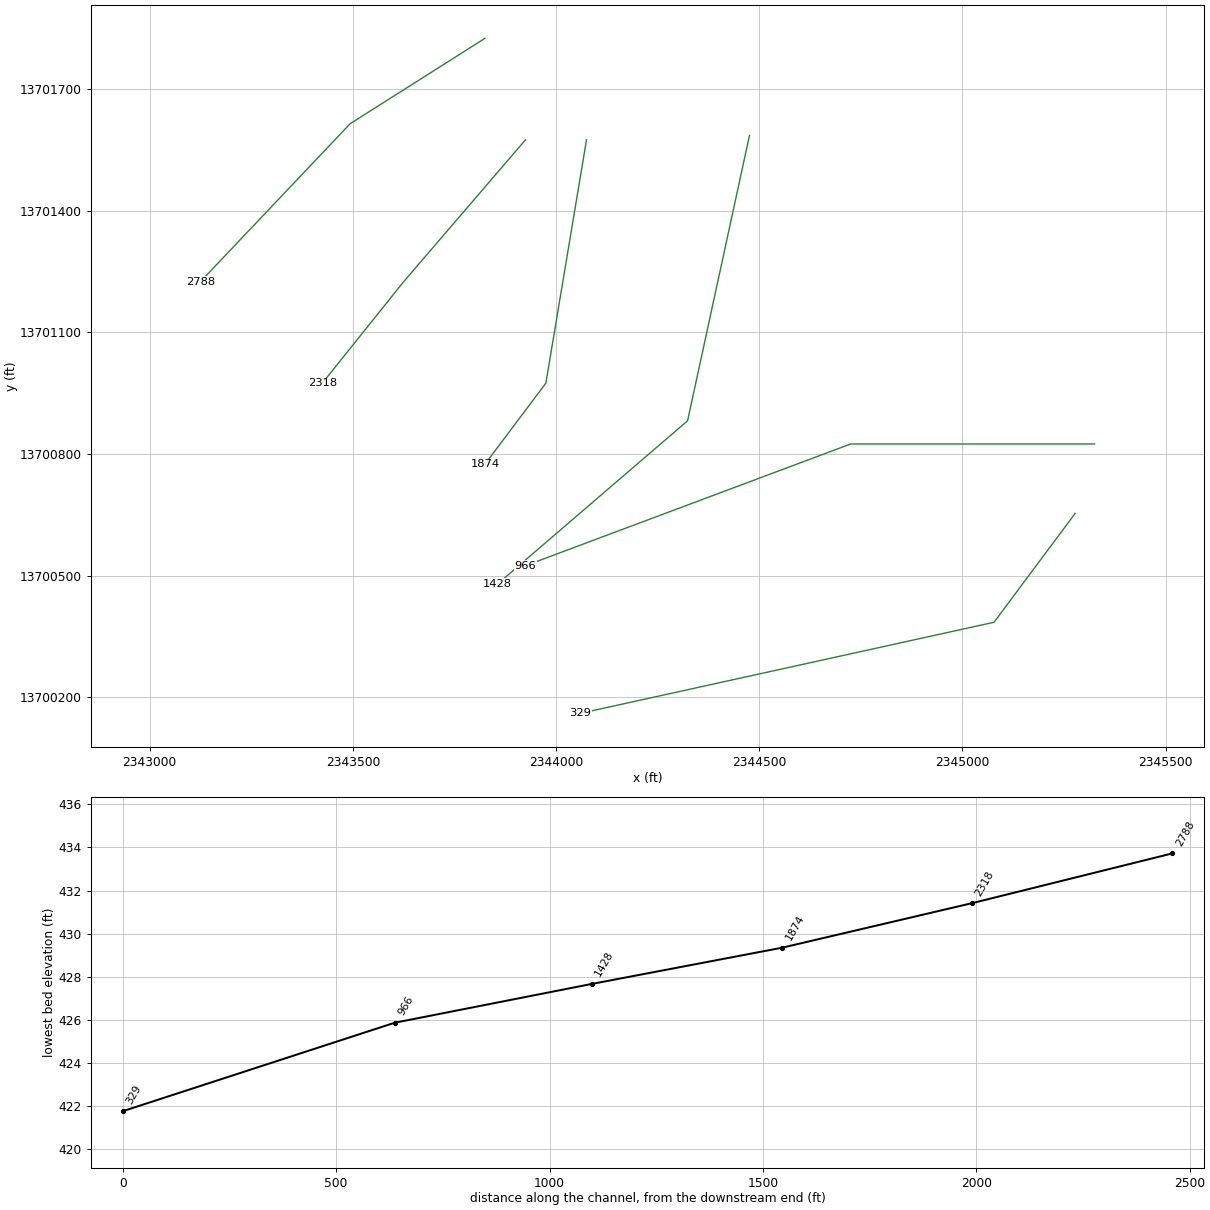
HEC-RAS study TIDWELL CREEK.prj: TIDWELL CREEK Base Level Engineering

--- TIDWELL CREEK.g01 (geometry) --- (continued)

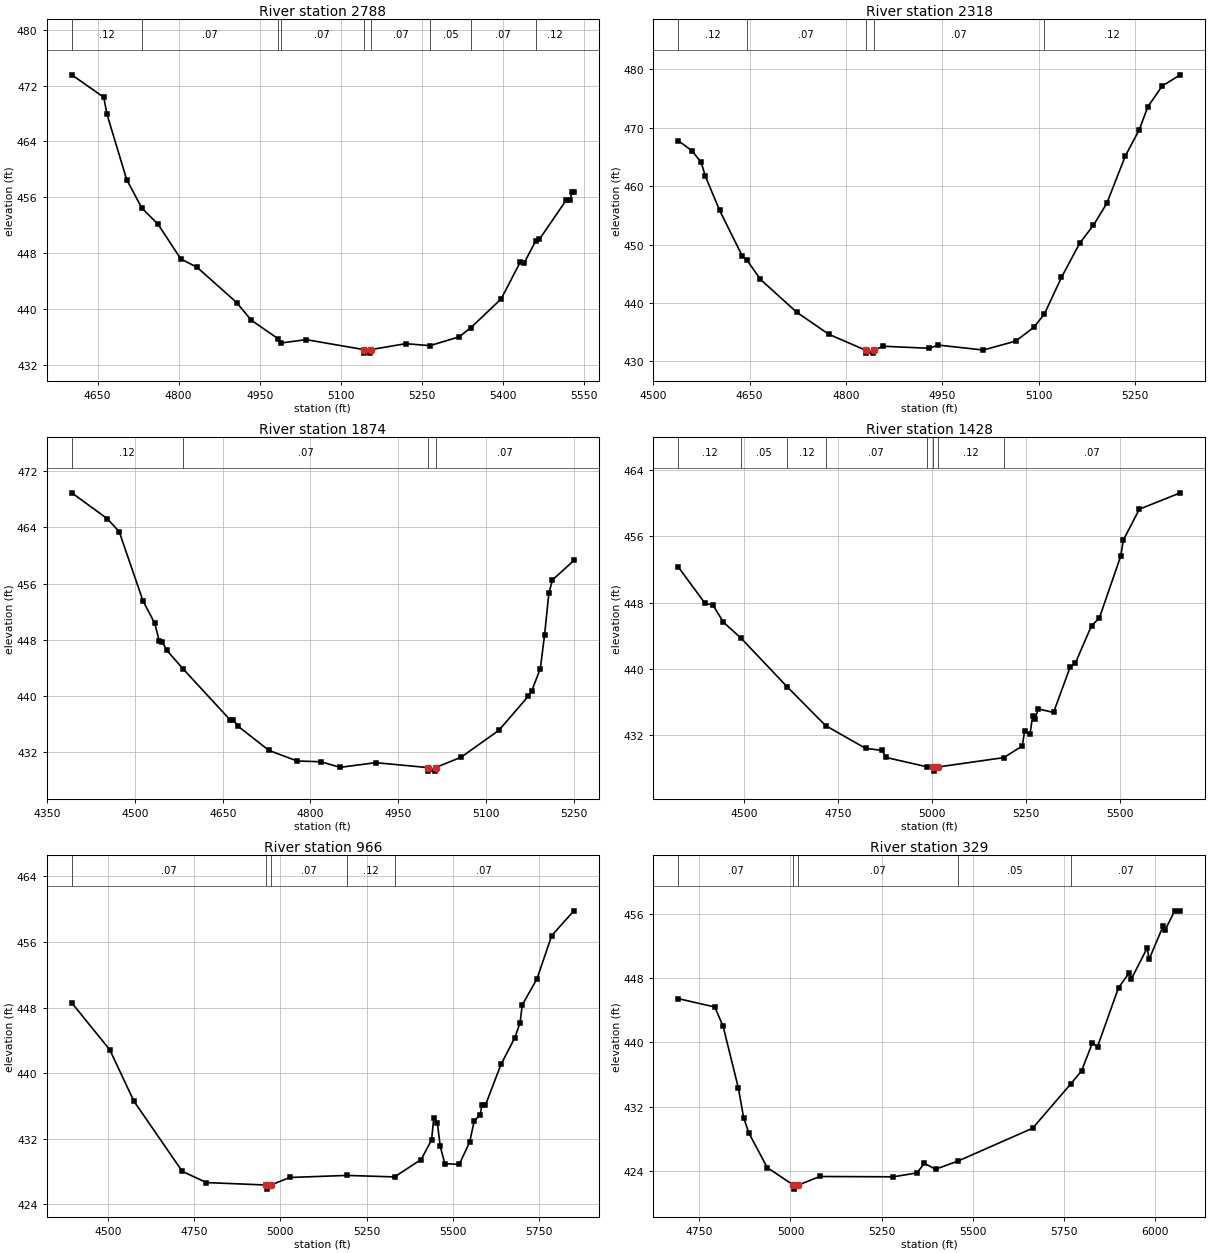
Type RM Length L Ch R = 1 ,2788    ,470,470,470
BEGIN DESCRIPTION:
TIDWELL CREEK 6.0
END DESCRIPTION:
XS GIS Cut Line= 3
      2343825.01     13701825.01      2343493.42     13701614.56
      2343125.01     13701225.01
#Sta/Elev= 30
  4602.2  473.53  4661.4  470.32  4667.4  467.87  4703.9  458.52    4732  454.45
  4761.5  452.19  4803.8  447.21  4834.3  445.98  4907.2  440.96  4934.3  438.43
  4984.4  435.75  4988.6  435.16  5035.8  435.65  5142.8  434.22  5143.3  433.72
  5154.7  433.72  5155.2  434.22  5219.8  435.07    5265  434.79  5318.9  436.05
  5340.7  437.37  5396.6  441.47  5432.2  446.78  5439.1  446.61  5460.5  449.76
  5467.4  450.01  5517.2  455.62    5524  455.56  5527.7  456.82  5531.1  456.82
#Mann= 9 ,-1 , 0
  4602.2     .12       0    4732     .07       0  4984.4     .12       0
  4988.6     .07       0  5142.8     .05       0  5155.2     .07       0
    5265     .05       0  5340.7     .07       0  5460.5     .12       0
Bank Sta=5142.8,5155.2
XS Rating Curve= 0 ,0
Exp/Cntr=0.3,0.1

Type RM Length L Ch R = 1 ,2318    ,444,444,444
BEGIN DESCRIPTION:
TIDWELL CREEK 5.0
END DESCRIPTION:
XS GIS Cut Line= 3
      2343924.99     13701574.99        2343625.       13701225.
      2343425.01     13700975.02
#Sta/Elev= 30
    4539  467.79  4560.4  466.06  4574.7  464.08  4581.2   461.7  4603.2   455.9
  4638.3  448.11  4645.6  447.39  4666.9  444.03  4723.4  438.41  4773.3  434.63
  4830.7  431.91  4831.2  431.41  4842.7  431.41  4843.2  431.91  4857.8  432.59
  4929.2  432.24  4943.4  432.79  5013.6  431.94    5064  433.47    5092  435.81
  5108.5  438.08  5135.2  444.38    5164  450.31  5184.9   453.3  5205.7  457.05
  5234.5  465.16  5256.1  469.64  5269.7  473.63  5292.1  477.18  5320.1  479.07
#Mann= 5 ,-1 , 0
    4539     .12       0  4645.6     .07       0  4830.7     .05       0
  4843.2     .07       0  5108.5     .12       0
Bank Sta=4830.7,4843.2
XS Rating Curve= 0 ,0
Exp/Cntr=0.3,0.1

Type RM Length L Ch R = 1 ,1874    ,446,446,446
BEGIN DESCRIPTION:
TIDWELL CREEK 4.0
END DESCRIPTION:
XS GIS Cut Line= 3
        2344075.       13701575.        2343975.       13700975.
      2343824.98     13700774.98
#Sta/Elev= 30
    4392  468.88  4452.8   465.2  4473.1  463.36  4513.7  453.54  4533.9  450.34
  4541.5  447.83  4546.6  447.73  4554.2  446.53  4581.9  443.91  4663.2  436.58
  4668.3  436.61  4675.9  435.75  4729.1  432.29  4777.2  430.79  4817.8  430.68
  4850.7  429.89  4911.6  430.55  5001.3  429.85  5001.8  429.35  5013.3  429.35
  5013.8  429.85  5057.6  431.33  5122.1  435.14  5172.1  439.96  5178.4  440.76
    5193  443.92  5200.3  448.73  5207.6  454.62  5213.8  456.51  5250.3  459.27
#Mann= 4 ,-1 , 0
    4392     .12       0  4581.9     .07       0  5001.3     .05       0
  5013.8     .07       0
Bank Sta=5001.3,5013.8
XS Rating Curve= 0 ,0
Exp/Cntr=0.3,0.1

Type RM Length L Ch R = 1 ,1428    ,462,462,462
BEGIN DESCRIPTION:
TIDWELL CREEK 3.0
END DESCRIPTION:
XS GIS Cut Line= 3
      2344475.93     13701585.54      2344323.66      13700882.2
      2343856.08     13700479.86
#Sta/Elev= 30
  4324.1  452.32  4395.3  447.93  4416.7   447.7  4444.5  445.64  4491.2  443.72
  4614.2  437.84  4716.2  433.17  4822.8  430.42  4866.9  430.17  4877.2  429.32
  4986.4  428.19  5003.2  428.17  5003.7  427.67  5015.7  428.17  5190.7   429.3
  5239.8   430.7  5246.4  432.53  5260.7  432.17  5267.3  434.28    5275  433.99
  5281.6  435.19  5323.1  434.75  5367.1  440.19  5381.4  440.73  5424.2  445.22
    5445  446.14  5502.1  453.64  5508.7  455.54  5551.5  459.28  5660.6  461.26
#Mann= 8 ,-1 , 0
  4324.1     .12       0  4491.2     .05       0  4614.2     .12       0
  4716.2     .07       0  4986.4     .12       0  5003.2     .05       0
  5015.7     .12       0  5190.7     .07       0
Bank Sta=5003.2,5015.7
XS Rating Curve= 0 ,0
Exp/Cntr=0.3,0.1

Type RM Length L Ch R = 1 ,966     ,637,637,637
BEGIN DESCRIPTION:
TIDWELL CREEK 2.0
END DESCRIPTION:
XS GIS Cut Line= 3
      2345324.99       13700825.        2344725.       13700825.
      2343924.99       13700525.
#Sta/Elev= 30
  4395.9  448.57  4505.9  442.86  4575.9  436.59  4715.9  428.04  4785.9  426.67
  4959.6  426.37  4960.1  425.87  4972.2  426.37  5027.9  427.29  5192.6  427.54
  5330.8  427.36    5408  429.48  5438.2  431.87  5444.5  434.55  5455.1  433.91
  5463.1  431.11  5476.5  428.98  5518.3  428.88  5548.6  431.62  5561.9  434.22
  5578.8  434.91  5584.2  436.15    5594  436.08  5639.4  441.09  5679.4  444.32
  5694.5  446.16  5700.8  448.31  5743.5   451.5  5786.2  456.77  5850.3  459.79
#Mann= 5 ,-1 , 0
  4395.9     .07       0  4959.6     .05       0  4972.2     .07       0
  5192.6     .12       0  5330.8     .07       0
Bank Sta=4959.6,4972.2
XS Rating Curve= 0 ,0
Exp/Cntr=0.3,0.1

Type RM Length L Ch R = 1 ,329     ,0,0,0
BEGIN DESCRIPTION:
TIDWELL CREEK 1.0
END DESCRIPTION:
XS GIS Cut Line= 3
       2345277.2     13700653.82      2345077.77      13700385.5
      2344059.48     13700160.83
#Sta/Elev= 30
  4692.1  445.44  4792.3   444.4  4815.2     442  4856.9  434.36  4871.6  430.61
  4886.2  428.71  4936.2  424.45  5008.2  422.27  5008.7  421.77    5021  422.27
  5080.5  423.34  5282.1   423.3  5346.7  423.78  5367.2  424.97  5397.9  424.24
  5459.4  425.26  5664.2  429.34  5768.9  434.85  5798.5  436.48    5828  439.93
  5842.2  439.48  5899.7   446.8  5929.5  448.66  5934.7  447.86  5978.4  451.74
  5983.5  450.31    6022  454.44  6027.2  453.94  6053.3   456.3  6069.2  456.35
#Mann= 5 ,-1 , 0
  4692.1     .07       0  5008.2     .05       0    5021     .07       0
  5459.4     .05       0  5768.9     .07       0
Bank Sta=5008.2,5021
XS Rating Curve= 0 ,0
Exp/Cntr=0.3,0.1

Chan Stop Cuts=-1
Use User Specified Reach Order=0
Composite Channel Slope=5