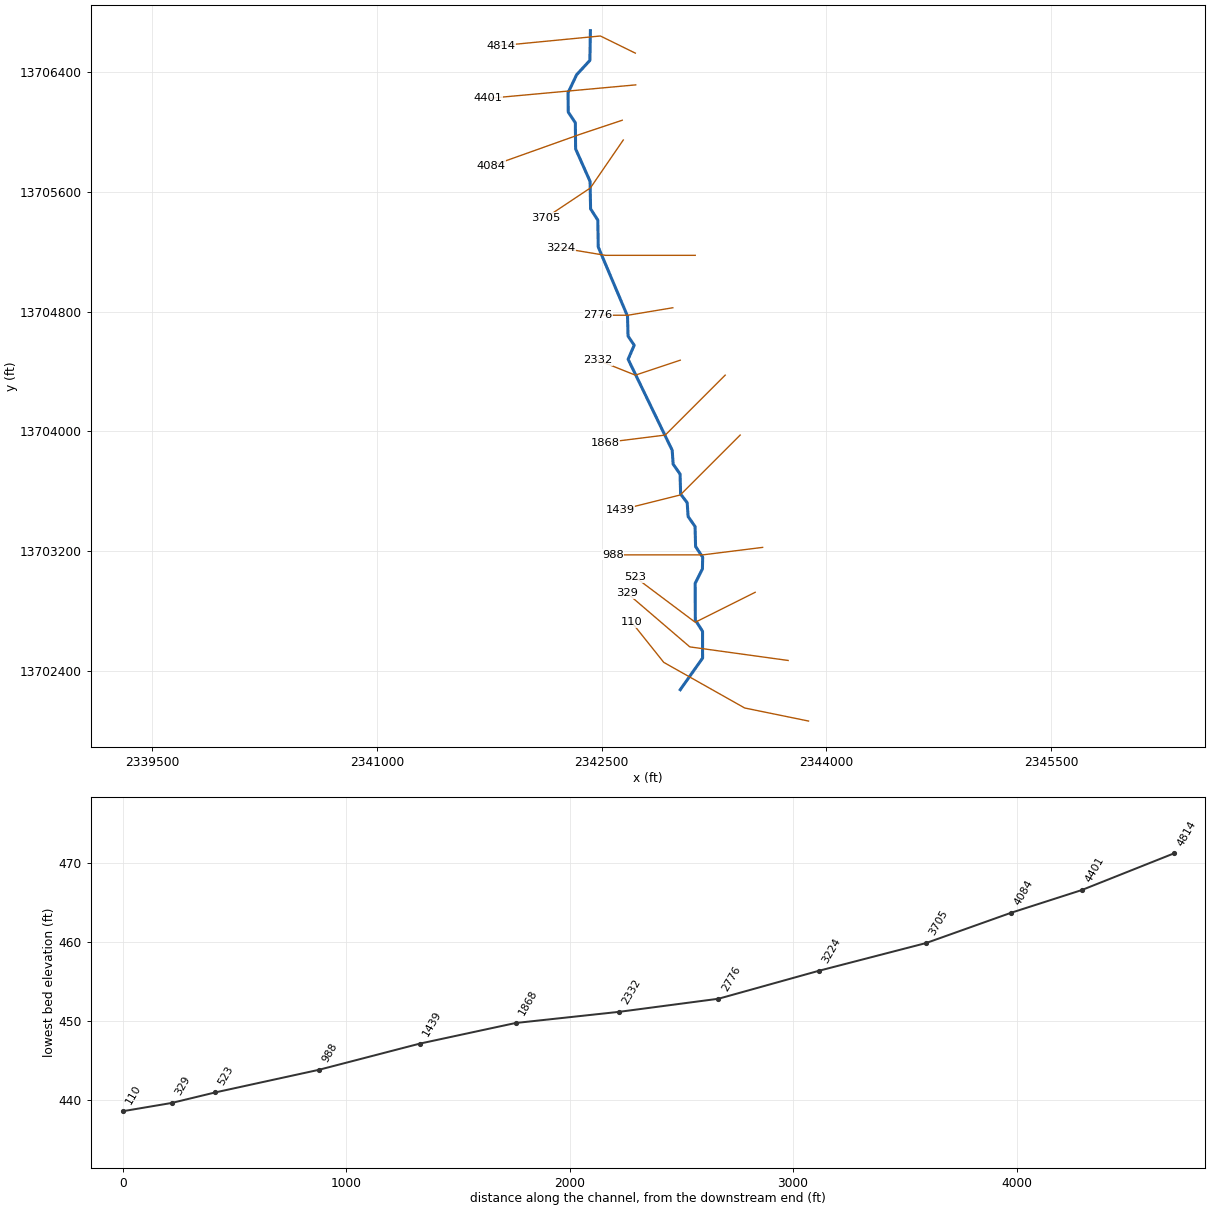
--- TIDWELL TRIBUTARY 1.prj (project) ---

Proj Title=TIDWELL TRIBUTARY 1 Base Level Engineering
Current Plan=p01
Default Exp/Contr=0.3,0.1
English Units
Geom File=g01
Flow File=f01
Plan File=p01
BEGIN DESCRIPTION:
TIDWELL TRIBUTARY 1
END DESCRIPTION:

--- TIDWELL TRIBUTARY 1.p01 (plan) ---

Plan Title=Multiple Run
Short Identifier=Multiple
Geom File=g01
Flow File=f01
Subcritical Flow
K Sum by GR= 0
Std Step Tol= 0.01
Critical Tol= 0.01
Num of Std Step Trials= 20
Max Error Tol= 0.3
Flow Tol Ratio= 0.001
Split Flow NTrial= 30
Split Flow Tol= 0.02
Split Flow Ratio= 0.02
Log Output Level= 0
Friction Slope Method= 1
Unsteady Friction Slope Method= 2
Unsteady Bridges Friction Slope Method= 1
Parabolic Critical Depth
Global Vel Dist=  1 , 1 , 1
Global Log Level= 0
CheckData=True
Encroach Param= -1, 0, 0, 0
BEGIN DESCRIPTION:
Multiple Run
END DESCRIPTION:

--- TIDWELL TRIBUTARY 1.f01 (steady flow) ---

Flow Title=Multiple
Number of Profiles=7
Profile Names=10-year,25-year,50-year,1pct_min,100-year,1pct_plu,500-year
River Rch & RM= TIDWELL TRIBUTAR,Reach-1,4814
     580     937    1261     822    1641    3274    2752
River Rch & RM= TIDWELL TRIBUTAR,Reach-1,2332
     854    1416    1937    1282    2559    5105    4428
Boundary for River Rch & Prof#=TIDWELL TRIBUTAR,Reach-1,1
Up Type=0
Dn Type=3
Dn Slope=0.005
Boundary for River Rch & Prof#=TIDWELL TRIBUTAR,Reach-1,2
Up Type=0
Dn Type=3
Dn Slope=0.005
Boundary for River Rch & Prof#=TIDWELL TRIBUTAR,Reach-1,3
Up Type=0
Dn Type=3
Dn Slope=0.005
Boundary for River Rch & Prof#=TIDWELL TRIBUTAR,Reach-1,4
Up Type=0
Dn Type=3
Dn Slope=0.005
Boundary for River Rch & Prof#=TIDWELL TRIBUTAR,Reach-1,5
Up Type=0
Dn Type=3
Dn Slope=0.005
Boundary for River Rch & Prof#=TIDWELL TRIBUTAR,Reach-1,6
Up Type=0
Dn Type=3
Dn Slope=0.005
Boundary for River Rch & Prof#=TIDWELL TRIBUTAR,Reach-1,7
Up Type=0
Dn Type=3
Dn Slope=0.005

--- TIDWELL TRIBUTARY 1.g01 (geometry) ---

Geom Title=Existing Conditions

River Reach=TIDWELL TRIBUTAR,Reach-1
Reach XY= 30
      2342425.00     13706675.00      2342421.46     13706476.47
      2342333.16     13706381.05      2342275.49     13706259.78
      2342277.25     13706130.94      2342324.48     13706059.78
      2342326.22     13705885.50      2342422.74     13705669.06
      2342426.22     13705485.51      2342474.48     13705409.78
      2342477.26     13705230.94      2342672.73     13704769.06
      2342676.39     13704635.44      2342717.41     13704574.99
      2342676.84     13704481.12      2342971.17     13703873.42
      2342977.36     13703780.98      2343023.77     13703714.49
      2343027.27     13703580.94      2343071.14     13703523.40
      2343077.36     13703430.98      2343123.77     13703364.49
      2343127.27     13703230.94      2343174.62     13703159.73
      2343172.83     13703080.98      2343124.55     13702985.19
      2343125.52     13702740.22      2343173.78     13702664.49
      2343173.95     13702485.44      2343025.00     13702275.00

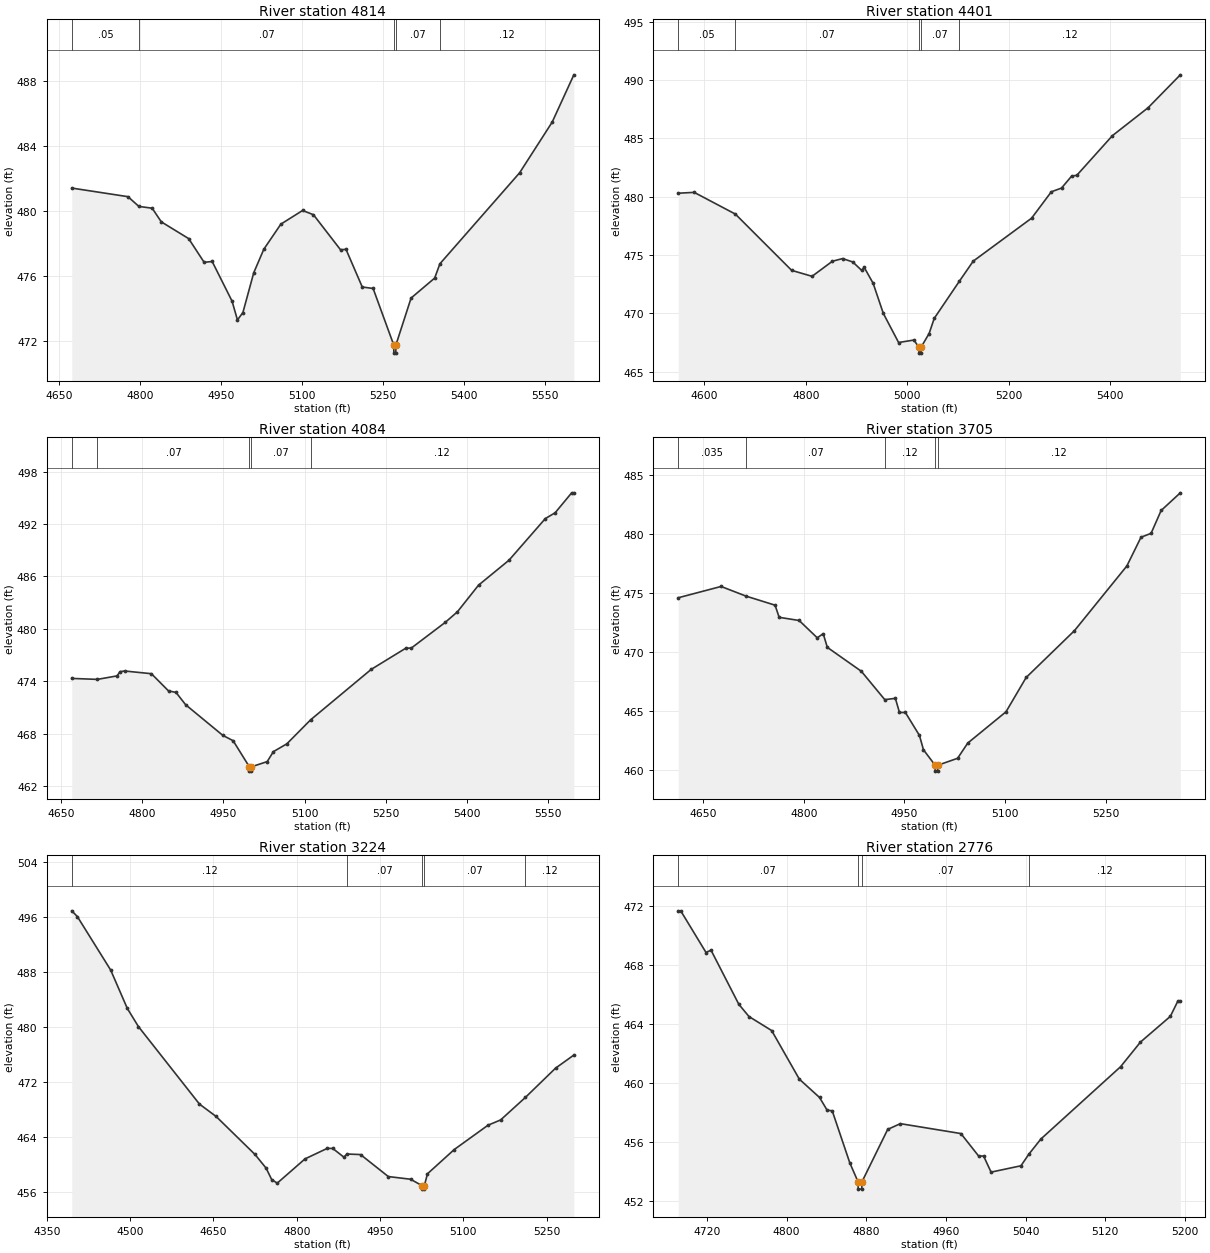
Type RM Length L Ch R = 1,4814,413,413,413
BEGIN DESCRIPTION:
TIDWELL TRIBUTARY 1 10.0
END DESCRIPTION:
XS GIS Cut Line= 3
      2342725.00     13706525.00      2342491.67     13706639.58
      2341825.04     13706575.00
#Sta/Elev= 30
  4673.1  481.42  4777.1  480.89  4797.4  480.29  4822.0  480.18  4838.9  479.34
  4889.5  478.31  4918.2  476.85  4933.1  476.90  4969.9  474.46  4979.9  473.30
  4990.0  473.76  5010.1  476.21  5028.8  477.66  5060.3  479.20  5100.5  480.04
  5120.6  479.78  5170.8  477.62  5180.9  477.65  5211.0  475.33  5231.1  475.24
  5269.3  471.76  5269.5  471.26  5273.0  471.26  5273.3  471.76  5301.4  474.65
  5345.1  475.88  5354.8  476.76  5502.4  482.36  5562.7  485.48  5602.8  488.39
#Mann=5,-1,0
  4673.1    0.05       0  4797.4    0.07       0  5269.3    0.05       0
  5273.3    0.07       0  5354.8    0.12       0
Bank Sta=5269.3,5273.3
Exp/Cntr=0.3,0.1

Type RM Length L Ch R = 1,4401,317,317,317
BEGIN DESCRIPTION:
XS7847
END DESCRIPTION:
XS GIS Cut Line= 2
      2342727.78     13706313.19      2341741.70     13706222.92
#Sta/Elev= 30
  4548.6  480.30  4580.1  480.37  4661.3  478.51  4772.3  473.69  4812.5  473.18
  4852.6  474.47  4872.7  474.70  4892.8  474.41  4910.3  473.69  4915.3  473.95
  4933.0  472.58  4953.1  470.00  4983.2  467.51  5013.3  467.72  5023.4  467.10
  5023.6  466.60  5027.1  466.60  5027.4  467.10  5043.4  468.28  5053.5  469.58
  5102.9  472.75  5130.4  474.48  5245.5  478.16  5284.4  480.42  5304.5  480.74
  5324.6  481.77  5334.6  481.83  5404.9  485.23  5475.2  487.62  5538.8  490.44
#Mann=5,-1,0
  4548.6    0.05       0  4661.3    0.07       0  5023.4    0.05       0
  5027.4    0.07       0  5102.9    0.12       0
Bank Sta=5023.4,5027.4
Exp/Cntr=0.3,0.1

Type RM Length L Ch R = 1,4084,379,379,379
BEGIN DESCRIPTION:
TIDWELL TRIBUTARY 1 9.0
END DESCRIPTION:
XS GIS Cut Line= 3
      2342637.54     13706077.10      2342366.67     13705986.81
      2341762.50     13705771.53
#Sta/Elev= 30
  4670.2  474.32  4717.5  474.21  4753.9  474.61  4759.2  475.09  4767.7  475.17
  4817.2  474.86  4848.8  472.89  4862.6  472.72  4880.4  471.31  4948.9  467.81
  4968.1  467.19  4998.0  464.21  4998.2  463.71  5001.7  463.71  5002.0  464.21
  5031.0  464.80  5042.4  465.94  5067.2  466.83  5111.1  469.58  5222.9  475.35
  5286.6  477.77  5297.2  477.80  5359.4  480.72  5382.1  481.94  5421.1  484.99
  5477.4  487.85  5544.4  492.61  5562.6  493.28  5593.1  495.56  5597.1  495.56
#Mann=5,-1,0
  4670.2    0.05       0  4717.5    0.07       0  4998.0    0.05       0
  5002.0    0.07       0  5111.1    0.12       0
Bank Sta=4998,5002
Exp/Cntr=0.3,0.1

Type RM Length L Ch R = 1,3705,481,481,481
BEGIN DESCRIPTION:
TIDWELL TRIBUTARY 1 8.0
END DESCRIPTION:
XS GIS Cut Line= 3
      2342644.43     13705945.12      2342425.00     13705625.00
      2342124.96     13705424.98
#Sta/Elev= 30
  4612.6  474.60  4676.5  475.56  4713.7  474.74  4757.0  473.97  4763.1  472.94
  4792.9  472.67  4819.9  471.20  4828.8  471.55  4834.9  470.39  4885.6  468.36
  4920.6  465.95  4936.4  466.06  4942.5  464.86  4951.3  464.86  4972.3  462.91
  4978.3  461.69  4995.7  460.38  4995.9  459.88  4999.4  459.88  4999.7  460.38
  5029.2  460.97  5044.3  462.26  5101.4  464.92  5131.4  467.83  5203.5  471.81
  5281.6  477.30  5302.7  479.74  5317.7  480.07  5332.7  482.01  5361.3  483.51
#Mann=5,-1,0
  4612.6   0.035       0  4713.7    0.07       0  4920.6    0.12       0
  4995.7    0.05       0  4999.7    0.12       0
Bank Sta=4995.7,4999.7
Exp/Cntr=0.3,0.1

Type RM Length L Ch R = 1,3224,448,448,448
BEGIN DESCRIPTION:
TIDWELL TRIBUTARY 1 7.0
END DESCRIPTION:
XS GIS Cut Line= 3
      2343124.95     13705175.00      2342525.00     13705175.00
      2342224.99     13705225.00
#Sta/Elev= 30
  4394.9  496.85  4404.9  496.02  4464.9  488.24  4494.9  482.65  4514.9  480.01
  4624.9  468.72  4654.9  466.92  4724.9  461.39  4744.9  459.40  4754.9  457.74
  4764.9  457.22  4814.9  460.75  4854.9  462.28  4864.9  462.27  4884.9  461.00
  4890.5  461.46  4914.9  461.38  4964.9  458.18  5005.0  457.79  5025.8  456.85
  5026.0  456.35  5029.5  456.35  5029.8  456.85  5035.4  458.58  5083.6  462.11
  5144.4  465.65  5167.2  466.42  5211.8  469.70  5266.0  473.95  5299.0  475.86
#Mann=5,-1,0
  4394.9    0.12       0  4890.5    0.07       0  5025.8    0.05       0
  5029.8    0.07       0  5211.8    0.12       0
Bank Sta=5025.8,5029.8
Exp/Cntr=0.3,0.1

Type RM Length L Ch R = 1,2776,444,444,444
BEGIN DESCRIPTION:
TIDWELL TRIBUTARY 1 6.0
END DESCRIPTION:
XS GIS Cut Line= 3
      2342974.99     13704825.00      2342675.00     13704775.00
      2342475.03     13704775.00
#Sta/Elev= 30
  4691.3  471.64  4693.8  471.64  4719.2  468.82  4724.2  468.98  4752.1  465.32
  4762.3  464.49  4785.1  463.54  4812.9  460.25  4833.2  459.01  4840.8  458.15
  4845.9  458.11  4863.6  454.58  4871.8  453.31  4872.0  452.81  4875.5  452.81
  4875.8  453.31  4901.6  456.85  4914.3  457.24  4975.1  456.57  4992.9  455.05
  4997.9  455.05  5005.4  453.96  5035.4  454.39  5043.4  455.18  5055.4  456.20
  5135.4  461.09  5155.4  462.76  5185.4  464.50  5192.9  465.53  5195.4  465.53
#Mann=4,-1,0
  4691.3    0.07       0  4871.8    0.05       0  4875.8    0.07       0
  5043.4    0.12       0
Bank Sta=4871.8,4875.8
Exp/Cntr=0.3,0.1

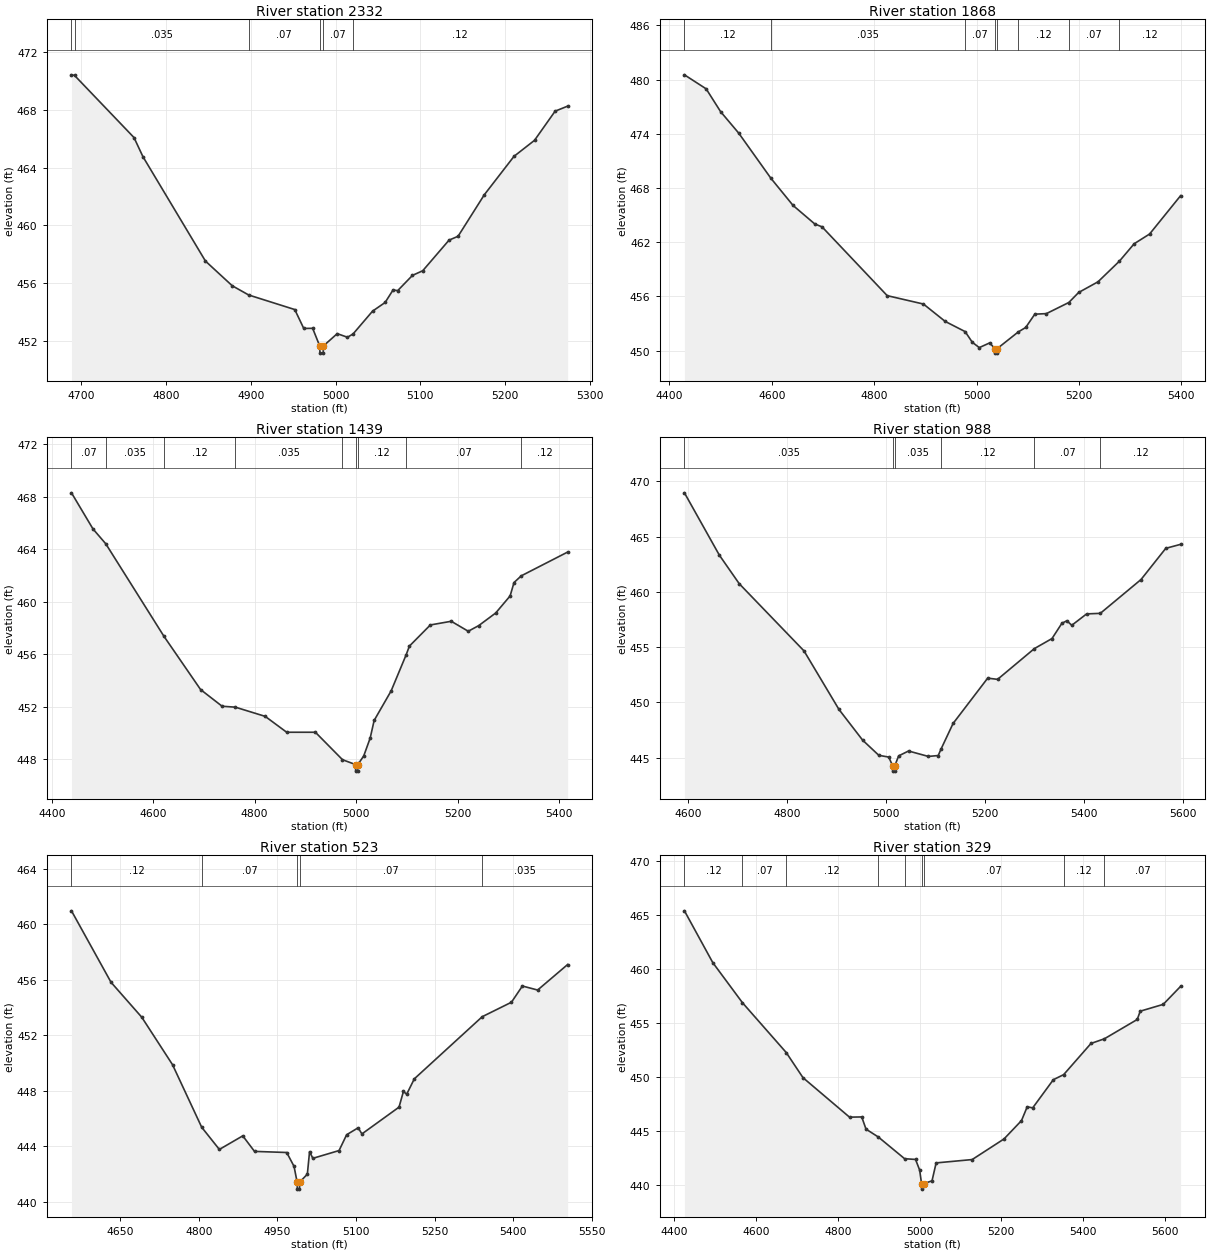
Type RM Length L Ch R = 1,2332,464,464,464
BEGIN DESCRIPTION:
TIDWELL TRIBUTARY 1 5.0
END DESCRIPTION:
XS GIS Cut Line= 3
      2343025.00     13704475.00      2342725.00     13704375.00
      2342474.99     13704475.00
#Sta/Elev= 30
  4688.3  470.44  4691.9  470.40  4762.1  466.09  4772.6  464.77  4846.4  457.53
  4878.0  455.82  4897.4  455.18  4951.8  454.17  4962.4  452.86  4972.9  452.87
  4981.2  451.65  4981.5  451.15  4985.3  451.15  4985.6  451.65  5001.9  452.50
  5014.0  452.25  5020.6  452.48  5043.6  454.06  5058.4  454.66  5067.8  455.53
  5073.2  455.48  5090.7  456.54  5102.8  456.86  5133.8  458.98  5144.5  459.25
  5175.5  462.13  5210.5  464.79  5234.7  465.90  5259.0  467.92  5273.8  468.27
#Mann=6,-1,0
  4688.3    0.12       0  4691.9   0.035       0  4897.4    0.07       0
  4981.2    0.05       0  4985.6    0.07       0  5020.6    0.12       0
Bank Sta=4981.2,4985.6
Exp/Cntr=0.3,0.1

Type RM Length L Ch R = 1,1868,429,429,429
BEGIN DESCRIPTION:
TIDWELL TRIBUTARY 1 4.0
END DESCRIPTION:
XS GIS Cut Line= 3
      2343324.97     13704374.97      2342925.00     13703975.00
      2342524.96     13703925.00
#Sta/Elev= 30
  4429.6  480.52  4472.0  478.97  4500.3  476.44  4535.6  474.07  4598.5  469.07
  4641.7  466.07  4684.1  464.02  4698.3  463.70  4825.5  456.09  4896.3  455.16
  4938.7  453.24  4977.7  452.11  4991.7  450.93  5005.3  450.34  5025.5  450.86
  5035.9  450.23  5036.2  449.73  5040.0  449.73  5040.3  450.23  5081.3  452.07
  5096.0  452.57  5113.7  454.04  5136.3  454.10  5180.1  455.33  5199.3  456.44
  5237.1  457.62  5279.0  459.91  5307.7  461.83  5337.9  462.91  5398.4  467.15
#Mann=8,-1,0
  4429.6    0.12       0  4598.5   0.035       0  4977.7    0.07       0
  5035.9    0.05       0  5040.3    0.07       0  5081.3    0.12       0
  5180.1    0.07       0  5279.0    0.12       0
Bank Sta=5035.9,5040.3
Exp/Cntr=0.3,0.1

Type RM Length L Ch R = 1,1439,451,451,451
BEGIN DESCRIPTION:
TIDWELL TRIBUTARY 1 3.0
END DESCRIPTION:
XS GIS Cut Line= 3
      2343424.97     13703974.97      2343025.00     13703575.00
      2342624.96     13703474.99
#Sta/Elev= 30
  4438.9  468.30  4481.3  465.55  4506.5  464.42  4621.1  457.38  4693.4  453.32
  4735.8  452.05  4761.9  451.98  4820.7  451.28  4863.1  450.07  4919.7  450.07
  4973.1  447.98  4998.8  447.61  4999.1  447.11  5002.9  447.11  5003.3  447.61
  5014.9  448.26  5027.7  449.63  5035.5  450.97  5069.0  453.22  5098.6  455.97
  5105.0  456.63  5146.3  458.24  5187.5  458.52  5221.0  457.76  5241.6  458.19
  5275.1  459.15  5303.5  460.45  5311.2  461.47  5325.5  461.98  5416.9  463.79
#Mann=9,-1,0
  4438.9    0.07       0  4506.5   0.035       0  4621.1    0.12       0
  4761.9   0.035       0  4973.1    0.12       0  4998.8    0.05       0
  5003.3    0.12       0  5098.6    0.07       0  5325.5    0.12       0
Bank Sta=4998.8,5003.3
Exp/Cntr=0.3,0.1

Type RM Length L Ch R = 1,988,465,465,465
BEGIN DESCRIPTION:
TIDWELL TRIBUTARY 1 2.0
END DESCRIPTION:
XS GIS Cut Line= 3
      2343574.97     13703225.00      2343175.00     13703175.00
      2342574.99     13703175.00
#Sta/Elev= 30
  4592.4  468.96  4662.9  463.33  4703.2  460.74  4834.2  454.66  4904.8  449.37
  4952.7  446.59  4985.4  445.22  5005.5  445.06  5013.1  444.29  5013.5  443.79
  5017.5  443.79  5017.8  444.29  5025.5  445.17  5045.5  445.61  5085.5  445.12
  5105.5  445.20  5110.9  445.76  5135.5  448.10  5205.5  452.20  5225.5  452.09
  5299.8  454.87  5335.5  455.78  5355.5  457.16  5365.5  457.39  5375.5  456.98
  5405.5  458.01  5433.2  458.06  5515.5  461.12  5565.5  463.94  5595.5  464.30
#Mann=6,-1,0
  4592.4   0.035       0  5013.1   0.035       0  5017.8   0.035       0
  5110.9    0.12       0  5299.8    0.07       0  5433.2    0.12       0
Bank Sta=5013.1,5017.8
Exp/Cntr=0.3,0.1

Type RM Length L Ch R = 1,523,194,194,194
BEGIN DESCRIPTION:
TIDWELL TRIBUTARY 1 1.0
END DESCRIPTION:
XS GIS Cut Line= 3
      2343525.01     13702925.00      2343125.00     13702725.00
      2342725.02     13703024.99
#Sta/Elev= 30
  4556.9  460.97  4632.4  455.82  4691.1  453.30  4749.8  449.88  4805.5  445.37
  4839.2  443.77  4883.9  444.75  4906.3  443.63  4967.8  443.55  4981.8  442.55
  4987.7  441.41  4988.1  440.91  4992.2  440.91  4992.5  441.41  5007.2  441.99
  5011.4  443.61  5017.7  443.13  5067.7  443.69  5082.2  444.83  5104.1  445.33
  5111.4  444.89  5182.2  446.82  5190.6  447.95  5196.8  447.75  5211.4  448.86
  5341.1  453.34  5396.8  454.38  5417.7  455.55  5446.8  455.26  5504.1  457.10
#Mann=5,-1,0
  4556.9    0.12       0  4805.5    0.07       0  4987.7    0.05       0
  4992.5    0.07       0  5341.1   0.035       0
Bank Sta=4987.7,4992.5
Exp/Cntr=0.3,0.1

Type RM Length L Ch R = 1,329,219,219,219
BEGIN DESCRIPTION:
H21496
END DESCRIPTION:
XS GIS Cut Line= 3
      2343745.24     13702470.01      2343088.84     13702560.67
      2342669.99     13702919.69
#Sta/Elev= 30
  4424.6  465.37  4494.0  460.57  4566.7  456.85  4673.7  452.24  4714.7  449.91
  4828.6  446.25  4858.5  446.27  4869.0  445.14  4899.1  444.41  4963.4  442.40
  4990.2  442.33  5000.3  441.34  5004.9  440.08  5005.2  439.58  5009.7  440.08
  5030.5  440.35  5040.6  442.01  5128.8  442.32  5206.7  444.23  5249.5  445.93
  5263.5  447.21  5276.9  447.11  5327.4  449.72  5352.7  450.19  5419.6  453.08
  5452.3  453.51  5532.7  455.30  5540.1  456.07  5596.3  456.70  5638.9  458.37
#Mann=9,-1,0
  4424.6    0.12       0  4566.7    0.07       0  4673.7    0.12       0
  4899.1   0.035       0  4963.4    0.07       0  5004.9    0.05       0
  5009.7    0.07       0  5352.7    0.12       0  5452.3    0.07       0
Bank Sta=5004.9,5009.7
Exp/Cntr=0.3,0.1

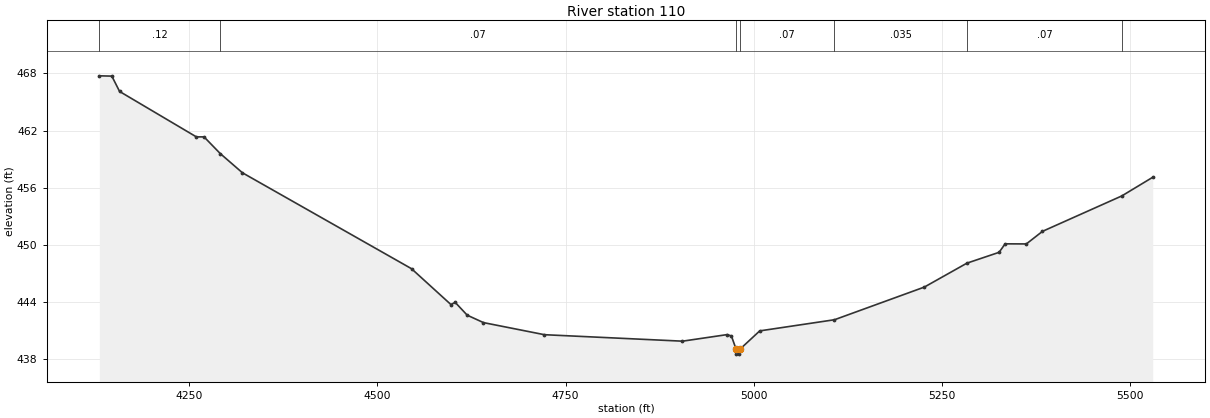
Type RM Length L Ch R = 1,110,0,0,0
BEGIN DESCRIPTION:
XS7846
END DESCRIPTION:
XS GIS Cut Line= 4
      2343881.28     13702065.62      2343455.14     13702152.66
      2342914.75     13702457.31      2342700.01     13702726.19
#Sta/Elev= 30
  4130.6  467.75  4147.2  467.72  4157.5  466.11  4259.5  461.34  4269.7  461.34
  4291.2  459.59  4320.7  457.57  4545.3  447.50  4597.6  443.74  4603.4  443.96
  4619.3  442.62  4640.9  441.84  4721.9  440.57  4905.3  439.89  4964.6  440.58
  4970.3  440.43  4976.6  439.03  4976.9  438.53  4981.0  438.53  4981.4  439.03
  5007.9  440.97  5107.2  442.14  5226.6  445.57  5283.1  448.08  5325.9  449.22
  5333.9  450.11  5362.1  450.10  5383.5  451.42  5488.9  455.14  5530.0  457.10
#Mann=7,-1,0
  4130.6    0.12       0  4291.2    0.07       0  4976.6    0.05       0
  4981.4    0.07       0  5107.2   0.035       0  5283.1    0.07       0
  5488.9    0.12       0
Bank Sta=4976.6,4981.4
Exp/Cntr=0.3,0.1

Chan Stop Cuts=-1