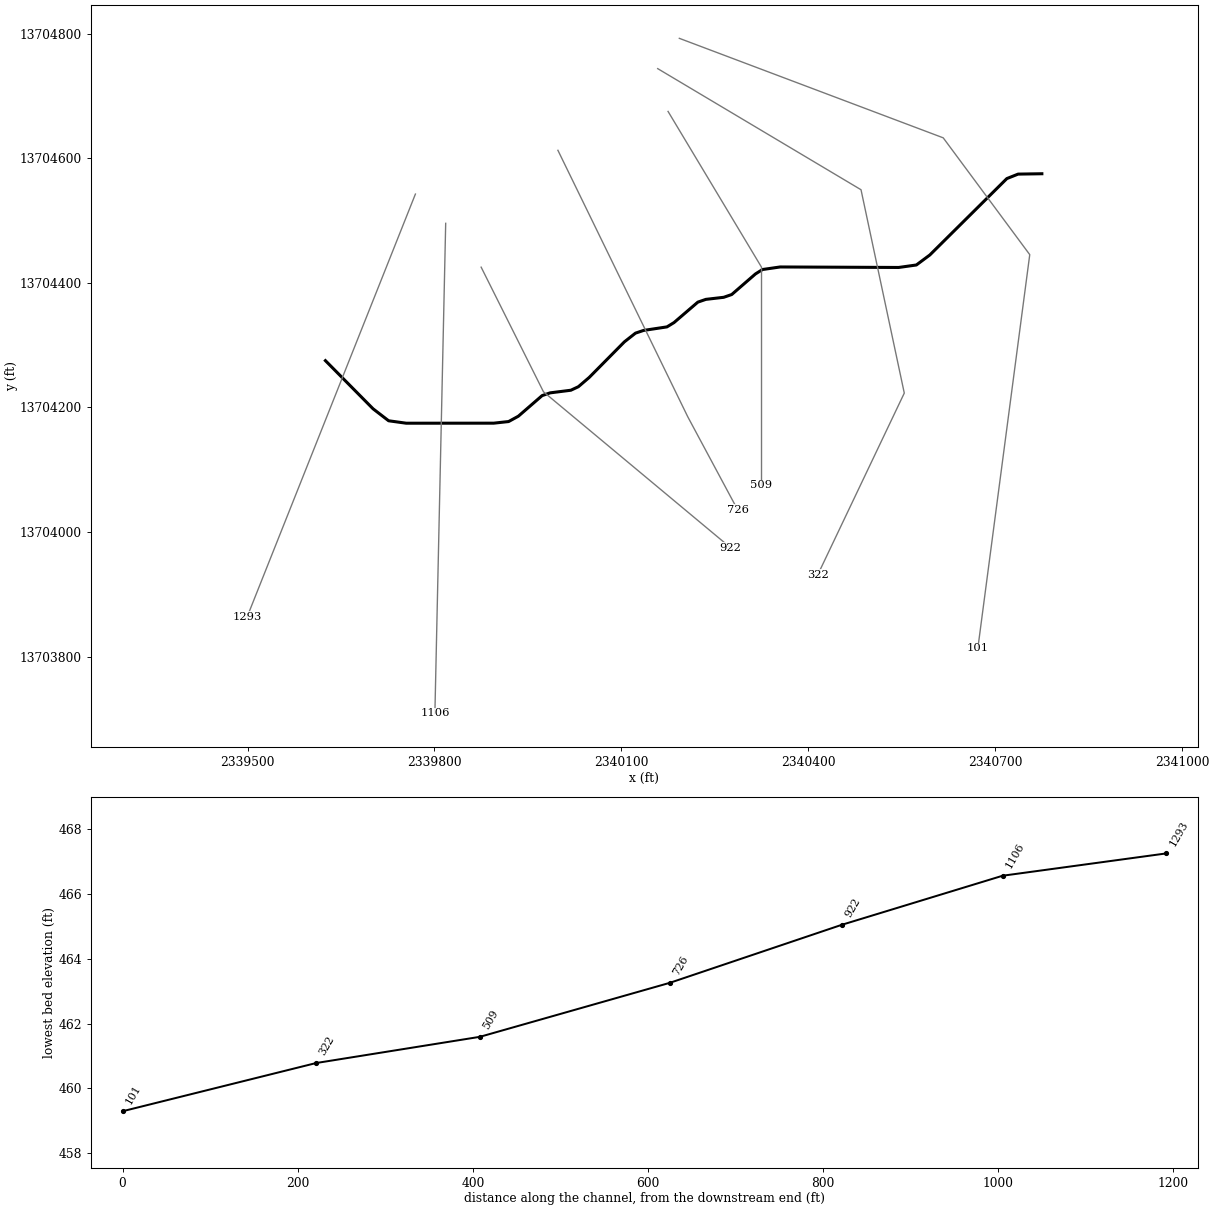
--- TIDWELL TRIBUTARY 2.prj (project) ---

Proj Title=TIDWELL TRIBUTARY 2 Base Level Engineering
Current Plan=p01
Default Exp/Contr=0.3,0.1
English Units
Geom File=g01
Flow File=f01
Plan File=p01
BEGIN DESCRIPTION:
TIDWELL TRIBUTARY 2
END DESCRIPTION:

--- TIDWELL TRIBUTARY 2.p01 (plan) ---

Plan Title=Multiple Run
Short Identifier=Multiple
Geom File=g01
Flow File=f01
Subcritical Flow
K Sum by GR= 0
Std Step Tol= 0.01
Critical Tol= 0.01
Num of Std Step Trials= 20
Max Error Tol= 0.3
Flow Tol Ratio= 0.001
Split Flow NTrial= 30
Split Flow Tol= 0.02
Split Flow Ratio= 0.02
Log Output Level= 0
Friction Slope Method= 1
Unsteady Friction Slope Method= 2
Unsteady Bridges Friction Slope Method= 1
Parabolic Critical Depth
Global Vel Dist=  1 , 1 , 1
Global Log Level= 0
CheckData=True
Encroach Param= -1, 0, 0, 0
BEGIN DESCRIPTION:
Multiple Run
END DESCRIPTION:

--- TIDWELL TRIBUTARY 2.f01 (steady flow) ---

Flow Title=Multiple
Number of Profiles=7
Profile Names=10-year,25-year,50-year,1pct_min,100-year,1pct_plu,500-year
River Rch & RM= TIDWELL TRIBUTAR,Reach-1,1293
     730    1202    1638    1081    2156    4302    3705
Boundary for River Rch & Prof#=TIDWELL TRIBUTAR,Reach-1,1
Up Type=0
Dn Type=3
Dn Slope=0.005
Boundary for River Rch & Prof#=TIDWELL TRIBUTAR,Reach-1,2
Up Type=0
Dn Type=3
Dn Slope=0.005
Boundary for River Rch & Prof#=TIDWELL TRIBUTAR,Reach-1,3
Up Type=0
Dn Type=3
Dn Slope=0.005
Boundary for River Rch & Prof#=TIDWELL TRIBUTAR,Reach-1,4
Up Type=0
Dn Type=3
Dn Slope=0.005
Boundary for River Rch & Prof#=TIDWELL TRIBUTAR,Reach-1,5
Up Type=0
Dn Type=3
Dn Slope=0.005
Boundary for River Rch & Prof#=TIDWELL TRIBUTAR,Reach-1,6
Up Type=0
Dn Type=3
Dn Slope=0.005
Boundary for River Rch & Prof#=TIDWELL TRIBUTAR,Reach-1,7
Up Type=0
Dn Type=3
Dn Slope=0.005

--- TIDWELL TRIBUTARY 2.g01 (geometry) ---

Geom Title=Existing Conditions

River Reach=TIDWELL TRIBUTAR,Reach-1
Reach XY= 30
      2339625.00     13704275.00      2339701.42     13704197.75
      2339726.44     13704178.48      2339754.82     13704174.56
      2339895.15     13704174.63      2339919.07     13704177.24
      2339934.67     13704185.79      2339972.83     13704218.86
      2339985.71     13704223.28      2340018.96     13704227.50
      2340031.05     13704233.16      2340048.45     13704248.06
      2340104.93     13704305.18      2340122.71     13704319.15
      2340135.63     13704323.49      2340173.26     13704329.19
      2340184.54     13704336.10      2340222.80     13704368.92
      2340235.68     13704373.35      2340264.31     13704376.67
      2340277.18     13704381.12      2340315.33     13704414.20
      2340326.55     13704421.25      2340354.85     13704425.36
      2340545.18     13704424.57      2340573.54     13704428.54
      2340595.16     13704444.60      2340718.79     13704567.24
      2340736.84     13704574.41      2340775.00     13704575.00

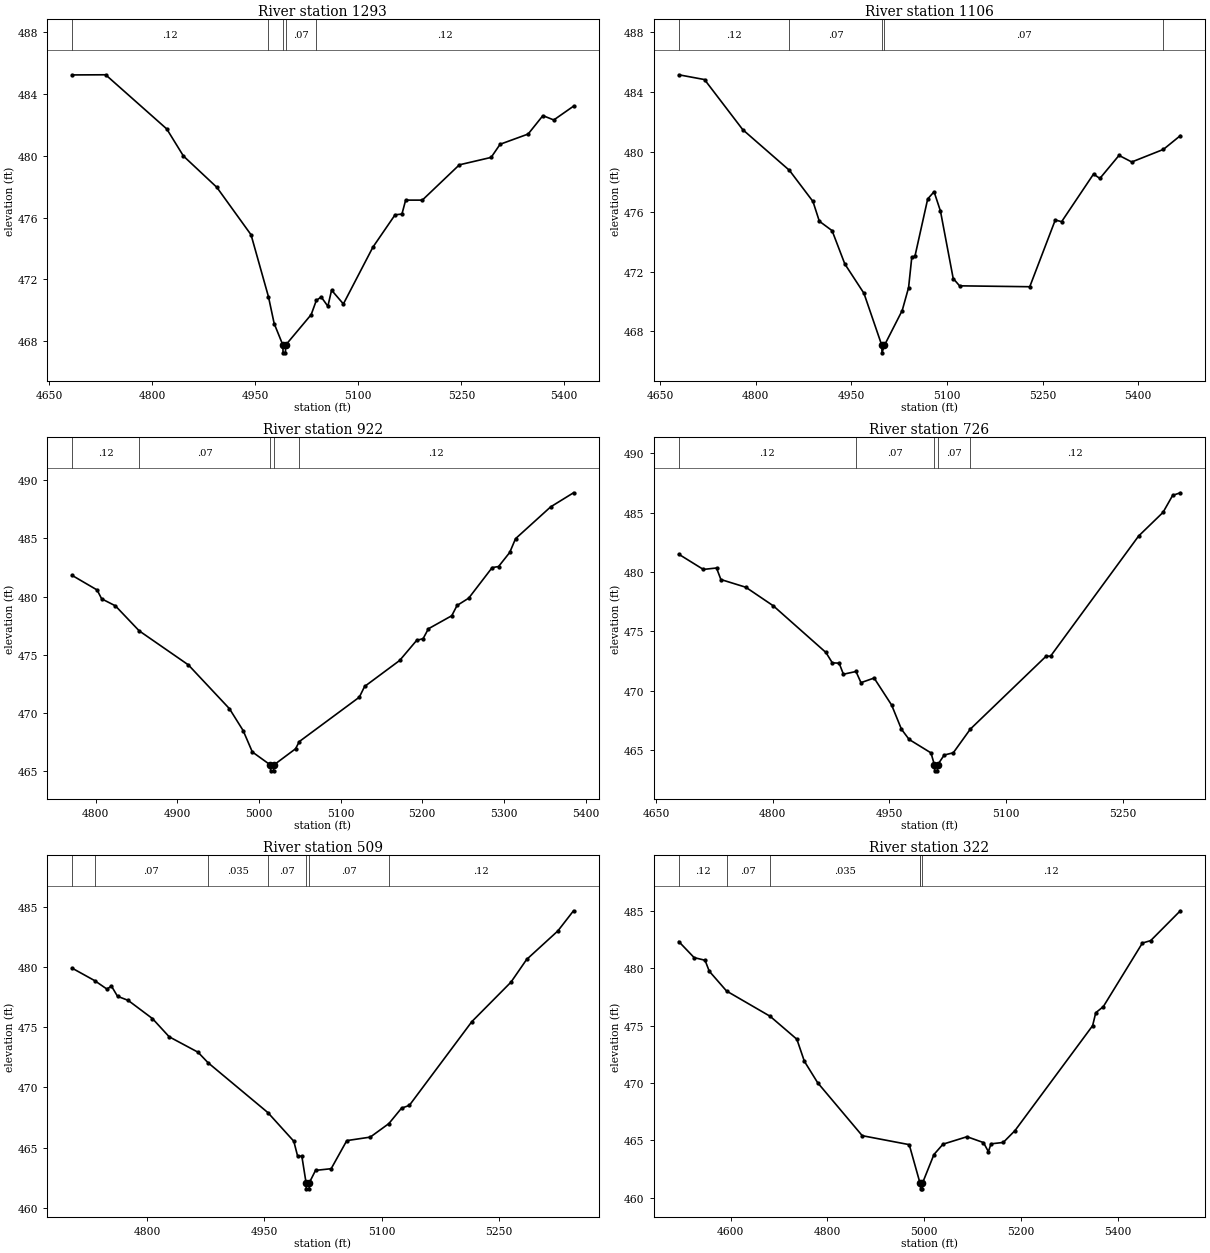
Type RM Length L Ch R = 1,1293,187,187,187
BEGIN DESCRIPTION:
XS7850
END DESCRIPTION:
XS GIS Cut Line= 2
      2339769.45     13704542.37      2339499.30     13703863.55
#Sta/Elev= 30
  4682.8  485.22  4731.9  485.23  4820.9  481.73  4845.2  479.98  4893.8  477.96
  4943.7  474.89  4969.1  470.88  4977.4  469.15  4990.1  467.76  4990.3  467.26
  4993.8  467.26  4994.1  467.76  5031.3  469.73  5038.8  470.65  5045.9  470.87
  5055.6  470.27  5061.0  471.31  5078.2  470.42  5121.2  474.09  5153.5  476.18
  5163.5  476.23  5168.9  477.13  5193.2  477.13  5247.1  479.41  5293.4  479.89
  5306.5  480.74  5347.3  481.40  5368.8  482.59  5384.7  482.31  5413.4  483.20
#Mann=5,-1,0
  4682.8    0.12       0  4969.1    0.07       0  4990.1    0.05       0
  4994.1    0.07       0  5038.8    0.12       0
Bank Sta=4990.1,4994.1
Exp/Cntr=0.3,0.1

Type RM Length L Ch R = 1,1106,184,184,184
BEGIN DESCRIPTION:
H21498
END DESCRIPTION:
XS GIS Cut Line= 2
      2339818.06     13704495.42      2339800.72     13703708.81
#Sta/Elev= 30
  4679.3  485.16  4719.7  484.84  4779.7  481.49  4852.9  478.77  4889.8  476.69
  4899.8  475.37  4919.8  474.74  4939.8  472.51  4969.8  470.55  4997.8  467.07
  4998.1  466.57  5001.9  467.07  5029.8  469.40  5039.8  470.93  5044.8  472.95
  5049.8  473.03  5069.8  476.86  5079.8  477.34  5089.8  476.05  5109.8  471.54
  5119.8  471.05  5229.9  470.99  5269.9  475.45  5279.9  475.34  5329.9  478.52
  5339.9  478.23  5369.9  479.77  5389.9  479.33  5439.5  480.17  5466.1  481.09
#Mann=5,-1,0
  4679.3    0.12       0  4852.9    0.07       0  4997.8    0.05       0
  5001.9    0.07       0  5439.5    0.12       0
Bank Sta=4997.8,5001.9
Exp/Cntr=0.3,0.1

Type RM Length L Ch R = 1,922,196,196,196
BEGIN DESCRIPTION:
TIDWELL TRIBUTARY 2 2.0
END DESCRIPTION:
XS GIS Cut Line= 3
      2339874.98     13704425.04      2339975.00     13704225.00
      2340275.03     13703974.98
#Sta/Elev= 30
  4771.0  481.83  4801.8  480.57  4807.4  479.81  4824.2  479.21  4853.4  477.06
  4913.6  474.14  4963.9  470.38  4980.7  468.50  4991.9  466.67  5014.1  465.55
  5014.3  465.05  5017.9  465.05  5018.2  465.55  5044.8  466.94  5049.4  467.56
  5122.9  471.37  5129.4  472.29  5172.3  474.52  5193.2  476.25  5201.0  476.39
  5207.5  477.24  5236.1  478.36  5242.6  479.24  5256.9  479.87  5285.6  482.49
  5293.4  482.58  5307.1  483.79  5314.2  484.97  5357.2  487.70  5385.2  488.91
#Mann=5,-1,0
  4771.0    0.12       0  4853.4    0.07       0  5014.1    0.05       0
  5018.2    0.07       0  5049.4    0.12       0
Bank Sta=5014.1,5018.2
Exp/Cntr=0.3,0.1

Type RM Length L Ch R = 1,726,217,217,217
BEGIN DESCRIPTION:
H21497
END DESCRIPTION:
XS GIS Cut Line= 3
      2339998.19     13704612.61      2340206.51     13704185.11
      2340286.82     13704035.34
#Sta/Elev= 30
  4678.9  481.49  4710.5  480.21  4727.5  480.33  4733.1  479.36  4765.2  478.71
  4800.7  477.14  4868.3  473.22  4876.5  472.35  4885.3  472.32  4890.8  471.39
  4907.0  471.62  4913.4  470.68  4930.3  471.07  4952.9  468.79  4965.5  466.76
  4975.4  465.90  5003.5  464.77  5007.9  463.76  5008.2  463.26  5011.8  463.26
  5012.0  463.76  5020.5  464.59  5032.2  464.78  5054.1  466.77  5151.7  472.91
  5157.4  472.91  5270.7  483.02  5302.1  485.01  5314.5  486.44  5324.4  486.66
#Mann=5,-1,0
  4678.9    0.12       0  4907.0    0.07       0  5007.9    0.05       0
  5012.0    0.07       0  5054.1    0.12       0
Bank Sta=5007.9,5012
Exp/Cntr=0.3,0.1

Type RM Length L Ch R = 1,509,187,187,187
BEGIN DESCRIPTION:
TIDWELL TRIBUTARY 2 1.0
END DESCRIPTION:
XS GIS Cut Line= 3
      2340174.99     13704675.02      2340325.00     13704425.00
      2340325.00     13704074.97
#Sta/Elev= 30
  4703.9  479.90  4732.9  478.86  4748.6  478.16  4754.5  478.40  4762.2  477.56
  4775.8  477.22  4806.9  475.71  4828.3  474.20  4865.2  472.92  4878.0  472.05
  4954.6  467.91  4987.7  465.54  4992.6  464.30  4998.0  464.30  5003.4  462.09
  5003.7  461.59  5007.3  461.59  5007.5  462.09  5015.5  463.12  5035.5  463.26
  5055.5  465.59  5085.5  465.88  5109.3  467.00  5125.5  468.28  5135.5  468.51
  5215.5  475.46  5265.5  478.73  5285.5  480.61  5325.5  482.98  5345.5  484.65
#Mann=7,-1,0
  4703.9    0.12       0  4732.9    0.07       0  4878.0   0.035       0
  4954.6    0.07       0  5003.4    0.05       0  5007.5    0.07       0
  5109.3    0.12       0
Bank Sta=5003.4,5007.5
Exp/Cntr=0.3,0.1

Type RM Length L Ch R = 1,322,221,221,221
BEGIN DESCRIPTION:
XS7849
END DESCRIPTION:
XS GIS Cut Line= 4
      2340158.36     13704743.73      2340484.72     13704549.31
      2340554.17     13704222.92      2340415.29     13703931.28
#Sta/Elev= 30
  4492.7  482.32  4524.5  480.92  4547.0  480.69  4555.7  479.74  4591.5  478.01
  4681.5  475.81  4736.8  473.81  4752.3  471.89  4779.8  470.02  4871.9  465.41
  4969.0  464.63  4990.4  461.41  4992.2  461.28  4992.5  460.78  4996.1  460.78
  4996.4  461.28  5020.1  463.77  5038.8  464.67  5088.4  465.32  5122.4  464.81
  5132.6  464.02  5138.0  464.70  5163.3  464.82  5187.5  465.85  5348.0  474.99
  5354.5  476.12  5370.1  476.65  5450.9  482.19  5468.0  482.40  5529.3  485.00
#Mann=6,-1,0
  4492.7    0.12       0  4591.5    0.07       0  4681.5   0.035       0
  4990.4    0.12       0  4992.2    0.05       0  4996.4    0.12       0
Bank Sta=4992.2,4996.4
Exp/Cntr=0.3,0.1

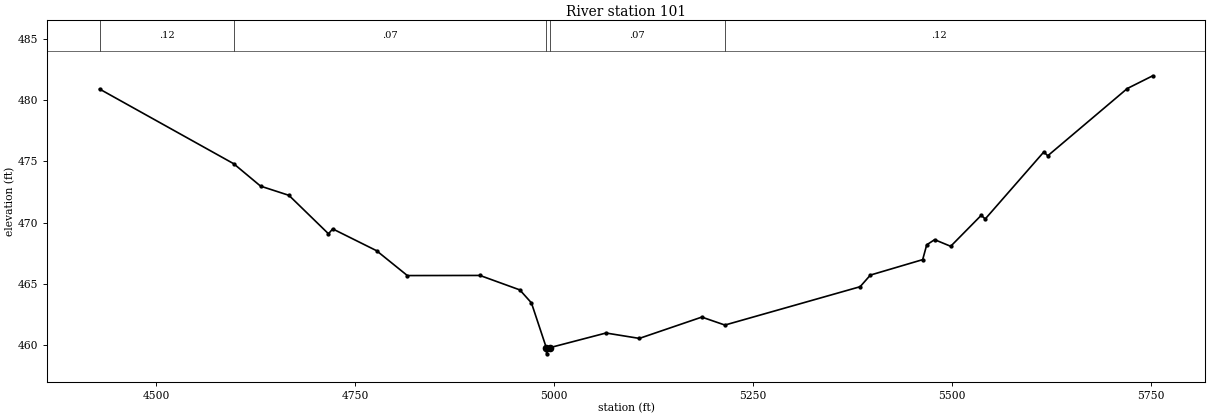
Type RM Length L Ch R = 1,101,0,0,0
BEGIN DESCRIPTION:
XS7848
END DESCRIPTION:
XS GIS Cut Line= 4
      2340193.09     13704792.35      2340616.67     13704632.64
      2340755.56     13704445.14      2340672.23     13703813.23
#Sta/Elev= 30
  4428.9  480.91  4597.5  474.81  4631.3  472.98  4666.9  472.23  4716.6  469.09
  4721.9  469.49  4777.0  467.71  4815.7  465.68  4906.9  465.69  4957.0  464.51
  4971.6  463.45  4990.3  459.79  4990.6  459.29  4994.5  459.79  5065.3  460.99
  5107.2  460.55  5185.7  462.29  5214.7  461.64  5384.6  464.77  5397.5  465.72
  5463.2  466.98  5468.3  468.19  5478.2  468.61  5498.4  468.07  5536.8  470.60
  5541.8  470.30  5615.4  475.77  5620.4  475.46  5720.3  480.95  5752.3  481.99
#Mann=5,-1,0
  4428.9    0.12       0  4597.5    0.07       0  4990.3    0.05       0
  4994.5    0.07       0  5214.7    0.12       0
Bank Sta=4990.3,4994.5
Exp/Cntr=0.3,0.1

Chan Stop Cuts=-1