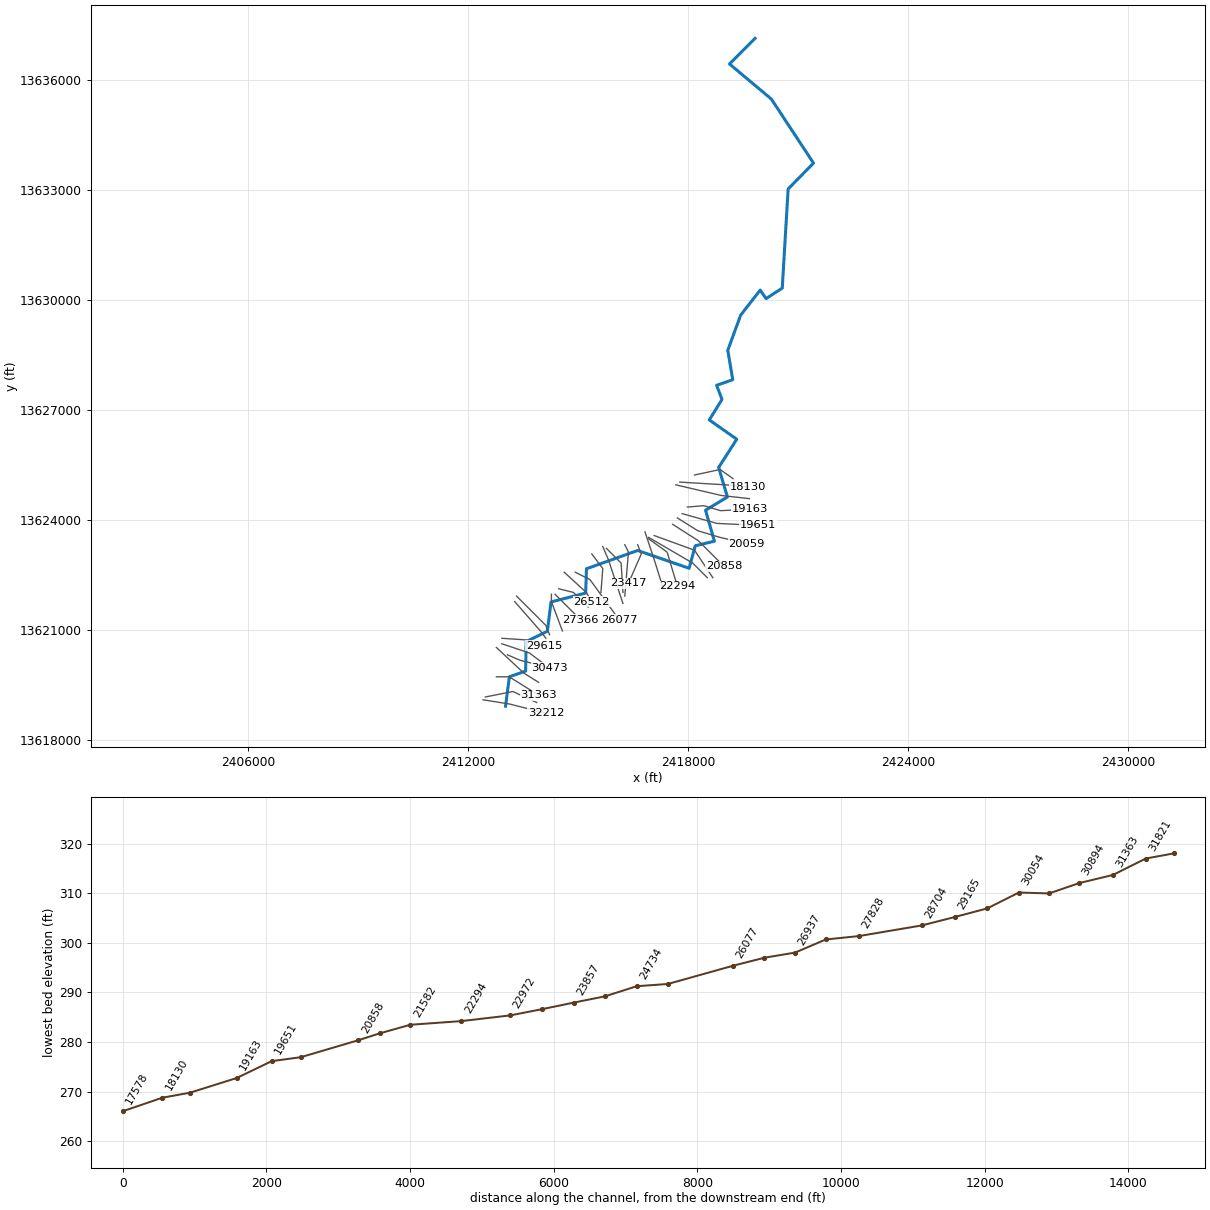
--- WEST COTTONWOOD CREEK.prj (project) ---

Proj Title=WEST COTTONWOOD CREEK Base Level Engineering
Current Plan=p01
Default Exp/Contr=0.3,0.1
English Units
Geom File=g01
Flow File=f01
Plan File=p01
Y Axis Title=Elevation
X Axis Title(PF)=Main Channel Distance
X Axis Title(XS)=Station
BEGIN DESCRIPTION:
WEST COTTONWOOD CREEK
END DESCRIPTION:
DSS Export Rating Curves= 0
DSS Export Rating Curve Sorted= 0
DSS Export Volume Flow Curves= 0
DXF OffsetX= 0
DXF OffsetY= 0
DXF ScaleX= 1
DXF ScaleY= 10

--- WEST COTTONWOOD CREEK.p01 (plan) ---

Plan Title=Multiple Run
Short Identifier=Multiple
Geom File=g01
Flow File=f01
Subcritical Flow
K Sum by GR= 0
Std Step Tol= 0.01
Critical Tol= 0.01
Num of Std Step Trials= 20
Max Error Tol= 0.3
Flow Tol Ratio= 0.001
Split Flow NTrial= 30
Split Flow Tol= 0.02
Split Flow Ratio= 0.02
Log Output Level= 0
Friction Slope Method= 1
Unsteady Friction Slope Method= 2
Unsteady Bridges Friction Slope Method= 1
Parabolic Critical Depth
Global Vel Dist=  1 , 1 , 1
Global Log Level= 0
CheckData=True
Encroach Param= -1, 0, 0, 0
BEGIN DESCRIPTION:
Multiple Run
END DESCRIPTION:

--- WEST COTTONWOOD CREEK.f01 (steady flow) ---

Flow Title=Multiple
Number of Profiles=7
Profile Names=10-year,25-year,50-year,1pct_min,100-year,1pct_plu,500-year
River Rch & RM= WEST COTTONWOOD ,Reach-1,32212
     667    1080    1454     948    1891    3773    3169
River Rch & RM= WEST COTTONWOOD ,Reach-1,31363
     875    1427    1928    1260    2513    5015    4233
River Rch & RM= WEST COTTONWOOD ,Reach-1,21582
    1137    1877    2557    1681    3355    6694    5731
River Rch & RM= WEST COTTONWOOD ,Reach-1,15334
    1278    2117    2890    1904    3799    7581    6513
River Rch & RM= WEST COTTONWOOD ,Reach-1,10620
    1489    2480    3400    2248    4485    8949    7743
River Rch & RM= WEST COTTONWOOD ,Reach-1,5085
    1583    2641    3625    2398    4785    9548    8273
Boundary for River Rch & Prof#=WEST COTTONWOOD ,Reach-1,1
Up Type=0
Dn Type=3
Dn Slope=0.005
Boundary for River Rch & Prof#=WEST COTTONWOOD ,Reach-1,2
Up Type=0
Dn Type=3
Dn Slope=0.005
Boundary for River Rch & Prof#=WEST COTTONWOOD ,Reach-1,3
Up Type=0
Dn Type=3
Dn Slope=0.005
Boundary for River Rch & Prof#=WEST COTTONWOOD ,Reach-1,4
Up Type=0
Dn Type=3
Dn Slope=0.005
Boundary for River Rch & Prof#=WEST COTTONWOOD ,Reach-1,5
Up Type=0
Dn Type=3
Dn Slope=0.005
Boundary for River Rch & Prof#=WEST COTTONWOOD ,Reach-1,6
Up Type=0
Dn Type=3
Dn Slope=0.005
Boundary for River Rch & Prof#=WEST COTTONWOOD ,Reach-1,7
Up Type=0
Dn Type=3
Dn Slope=0.005

--- WEST COTTONWOOD CREEK.g01 (geometry) ---

Geom Title=Existing Conditions
Program Version=4.10

River Reach=WEST COTTONWOOD ,Reach-1
Reach XY= 30
        2413025.       13618925.      2413130.34     13619727.74
      2413573.39     13619881.02      2413585.94     13620685.44
      2414164.04     13620964.95      2414265.19     13621764.58
      2415208.86     13622007.91      2415230.41     13622669.83
        2416625.     13623167.92      2418028.58     13622682.49
      2418194.61      13623295.2      2418717.42     13623421.66
      2418475.54     13624264.37      2419071.99     13624626.43
      2418832.59     13625428.35      2419325.51     13626200.04
      2418577.99      13626726.4      2418924.49      13627285.5
      2418776.96     13627669.13       2419217.2     13627821.58
      2419082.08       13628625.      2419432.68     13629581.52
      2419964.83     13630264.24      2420124.93     13630032.27
      2420566.02     13630318.34      2420726.62     13633018.96
      2421417.95     13633725.07      2420269.53     13635469.74
      2419128.34     13636426.72        2419825.       13637125.

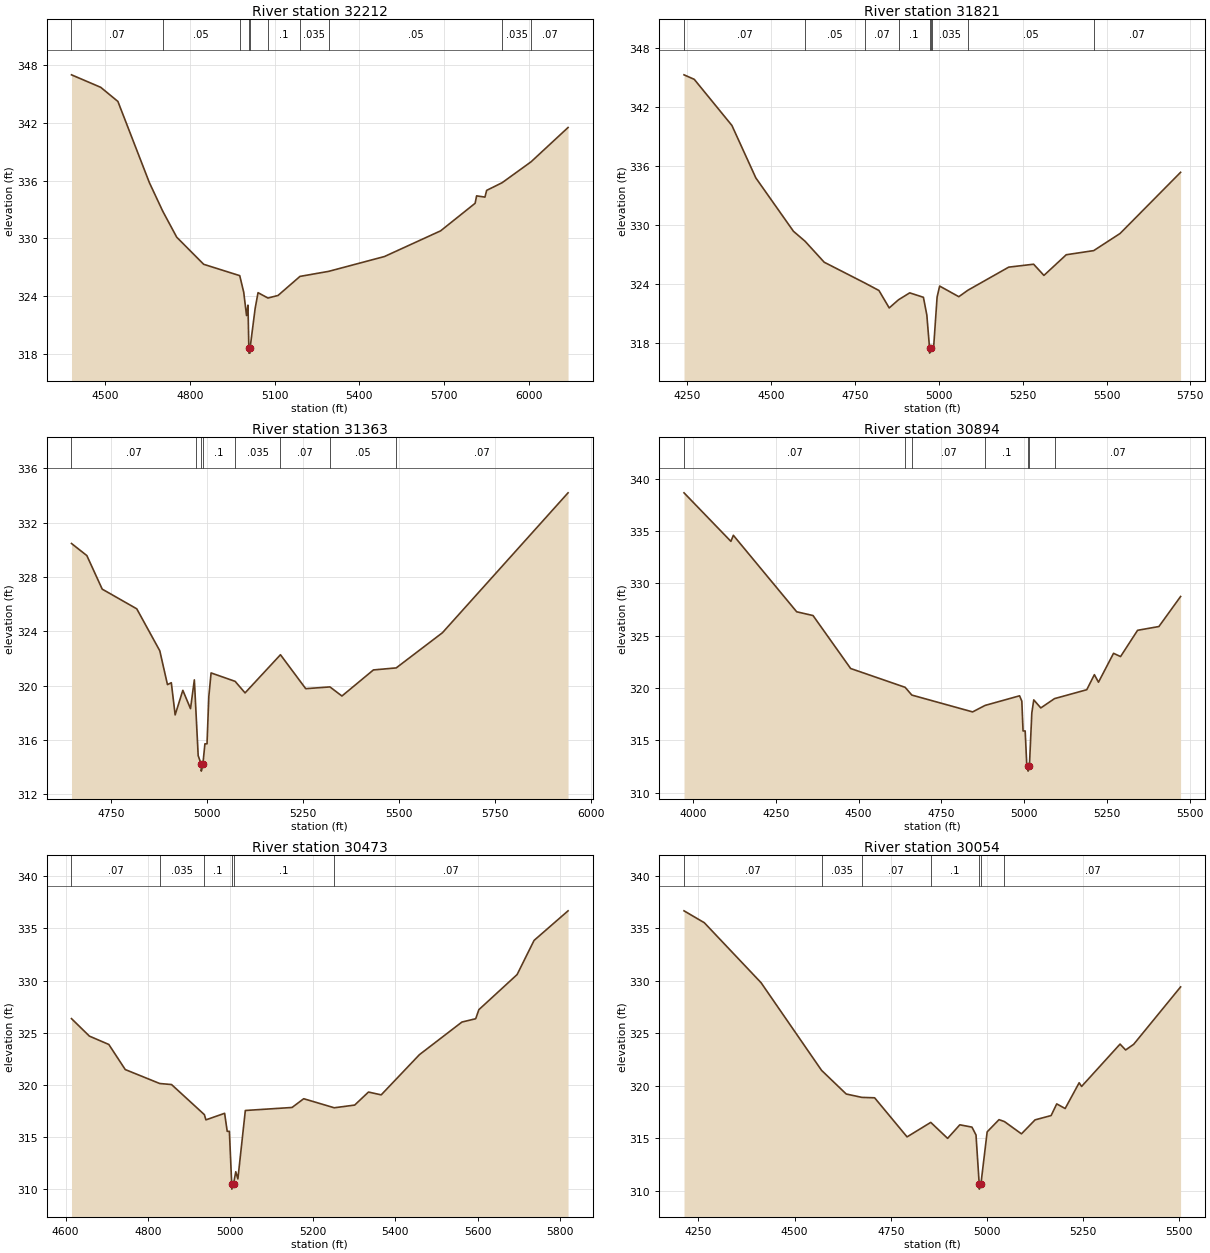
Type RM Length L Ch R = 1 ,32212   ,391,391,391
BEGIN DESCRIPTION:
H21628
END DESCRIPTION:
XS GIS Cut Line= 3
      2412412.73     13619099.35      2413141.83     13618981.96
      2414130.21     13618728.68
#Sta/Elev= 30
  4380.3     347  4483.9   345.7  4544.7  344.23  4656.1  335.79  4703.6  332.81
    4753  330.11  4848.5  327.29  4976.2  326.11  4990.3  324.39  5000.3  321.96
  5005.4  323.04  5008.5  318.55  5008.8  318.05  5012.4  318.05  5012.7  318.55
  5030.8   322.7    5041  324.34  5076.1  323.78  5111.9  324.05  5189.5  326.03
  5291.8  326.56  5488.9   328.1  5687.7  330.77    5810  333.64  5815.2  334.41
  5844.7  334.28  5850.8  334.98  5905.7  335.78    6008  337.95  6139.1  341.52
#Mann= 10 ,-1 , 0
  4380.3     .07       0  4703.6     .05       0  4976.2     .07       0
  5008.5     .05       0  5012.7     .07       0  5076.1      .1       0
  5189.5    .035       0  5291.8     .05       0  5905.7    .035       0
    6008     .07       0
Bank Sta=5008.5,5012.7
XS Rating Curve= 0 ,0
Exp/Cntr=0.3,0.1

Type RM Length L Ch R = 1 ,31821   ,458,458,458
BEGIN DESCRIPTION:
WEST COTTONWOOD CREEK 60.0
END DESCRIPTION:
XS GIS Cut Line= 3
      2412474.99       13619175.        2413225.       13619325.
      2413875.04     13619024.98
#Sta/Elev= 30
  4239.9  345.28  4270.5  344.82  4382.7  340.14  4454.1  334.81  4566.3  329.39
  4600.9  328.38    4658  326.25  4779.8  324.13  4821.2  323.38  4851.8  321.61
  4879.6  322.44    4913  323.14  4953.8  322.69    4964  320.89  4972.1  317.52
  4972.3  317.02  4976.3  317.52  4979.4  317.58  4984.4  317.68  4994.6  322.71
  5002.2  323.83  5059.4  322.75  5086.6  323.41  5208.1  325.75  5282.4  326.05
  5313.2  324.91  5379.7  327.01  5461.6  327.43  5540.3  329.17  5720.7  335.38
#Mann= 9 ,-1 , 0
  4239.9     .07       0  4600.9     .05       0  4779.8     .07       0
  4879.6      .1       0  4972.1    .035       0  4976.3      .1       0
  4979.4    .035       0  5086.6     .05       0  5461.6     .07       0
Bank Sta=4972.1,4976.3
XS Rating Curve= 0 ,0
Exp/Cntr=0.3,0.1

Type RM Length L Ch R = 1 ,31363   ,469,469,469
BEGIN DESCRIPTION:
WEST COTTONWOOD CREEK 59.0
END DESCRIPTION:
XS GIS Cut Line= 3
      2412774.95       13619725.        2413125.       13619725.
      2413924.96     13619225.03
#Sta/Elev= 30
  4646.2  330.46  4686.2  329.57  4726.2   327.1  4816.2  325.65  4876.2  322.56
  4896.2  320.07  4906.2  320.21  4916.2  317.84  4936.2  319.65  4956.2   318.3
  4966.2  320.42  4971.4  317.52  4976.2  314.84  4984.1   314.2  4984.3   313.7
  4988.4   314.2  4993.7  315.71  4999.2  315.71  5003.9  319.19  5009.8  320.93
  5072.4  320.31  5098.3  319.46  5190.5  322.27  5256.3  319.77  5319.4   319.9
  5350.6  319.23  5432.6  321.15    5492   321.3  5612.4  323.89  5939.6  334.19
#Mann= 8 ,-1 , 0
  4646.2     .07       0  4971.4      .1       0  4984.1     .05       0
  4988.4      .1       0  5072.4    .035       0  5190.5     .07       0
  5319.4     .05       0    5492     .07       0
Bank Sta=4984.1,4988.4
XS Rating Curve= 0 ,0
Exp/Cntr=0.3,0.1

Type RM Length L Ch R = 1 ,30894   ,421,421,421
BEGIN DESCRIPTION:
WEST COTTONWOOD CREEK 58.0
END DESCRIPTION:
XS GIS Cut Line= 3
        2412775.       13620525.        2413525.       13619825.
      2413924.99     13619575.01
#Sta/Elev= 30
  3973.6  338.66    4115  334.02  4122.4   334.6  4313.4  327.29  4362.7  326.93
  4476.1  321.87  4640.5  320.07  4660.6  319.33  4843.9  317.72  4881.5  318.34
  4985.6  319.26  4992.4  318.75  4996.1   315.9  5002.5   315.9  5007.2  312.73
  5010.9  312.56  5011.2  312.06  5015.3  312.56  5022.5  317.61  5028.4  318.87
  5049.6   318.1    5091  318.99  5188.2  319.84  5211.2  321.28  5223.6  320.56
    5269  323.32  5290.2  323.01  5341.5  325.52  5405.8  325.88  5471.2  328.75
#Mann= 7 ,-1 , 0
  3973.6     .07       0  4640.5    .035       0  4660.6     .07       0
  4881.5      .1       0  5010.9     .05       0  5015.3      .1       0
    5091     .07       0
Bank Sta=5010.9,5015.3
XS Rating Curve= 0 ,0
Exp/Cntr=0.3,0.1

Type RM Length L Ch R = 1 ,30473   ,419,419,419
BEGIN DESCRIPTION:
WEST COTTONWOOD CREEK 57.0
END DESCRIPTION:
XS GIS Cut Line= 3
      2413075.04     13620324.98        2413425.       13620175.
      2414225.03     13619974.99
#Sta/Elev= 30
  4614.3  326.34  4657.8  324.66  4704.9  323.86  4744.8  321.45  4828.5  320.11
  4857.2  320.01  4936.9  317.12  4940.6  316.62    4986  317.25  4992.3  315.52
  4997.6  315.52  5003.2  310.47  5003.5  309.97  5007.6  310.47  5013.1  311.64
  5018.2  310.95  5036.3  317.52  5149.7  317.81    5178  318.65  5252.2  317.78
  5301.7  318.04  5335.2  319.29  5366.1  319.02  5458.9  322.88    5562  326.01
  5595.5  326.33  5603.2   327.2    5696  330.57  5737.2  333.85  5819.7  336.69
#Mann= 6 ,-1 , 0
  4614.3     .07       0  4828.5    .035       0  4936.9      .1       0
  5003.2     .05       0  5007.6      .1       0  5252.2     .07       0
Bank Sta=5003.2,5007.6
XS Rating Curve= 0 ,0
Exp/Cntr=0.3,0.1

Type RM Length L Ch R = 1 ,30054   ,439,439,439
BEGIN DESCRIPTION:
WEST COTTONWOOD CREEK 56.0
END DESCRIPTION:
XS GIS Cut Line= 3
      2412925.01       13620625.        2413675.       13620375.
      2414075.03     13620074.97
#Sta/Elev= 30
  4212.8  336.64  4265.5  335.51  4413.1   329.8  4570.3  321.46  4634.4  319.21
    4675  318.89  4708.2  318.85  4792.5  315.13  4854.1  316.51  4897.9  314.99
  4929.6  316.28  4961.2  316.06  4971.7  315.31    4980  310.66  4980.3  310.16
  4984.5  310.66  5000.7  315.61  5031.5  316.77  5045.5  316.59  5089.8  315.42
  5125.2  316.75  5166.9  317.16  5181.5  318.27  5203.4  317.83  5239.8  320.28
  5246.1  319.93  5346.1  323.96  5360.6   323.4  5381.5  323.94  5503.4   329.4
#Mann= 7 ,-1 , 0
  4212.8     .07       0  4570.3    .035       0    4675     .07       0
  4854.1      .1       0    4980     .05       0  4984.5      .1       0
  5045.5     .07       0
Bank Sta=4980,4984.5
XS Rating Curve= 0 ,0
Exp/Cntr=0.3,0.1

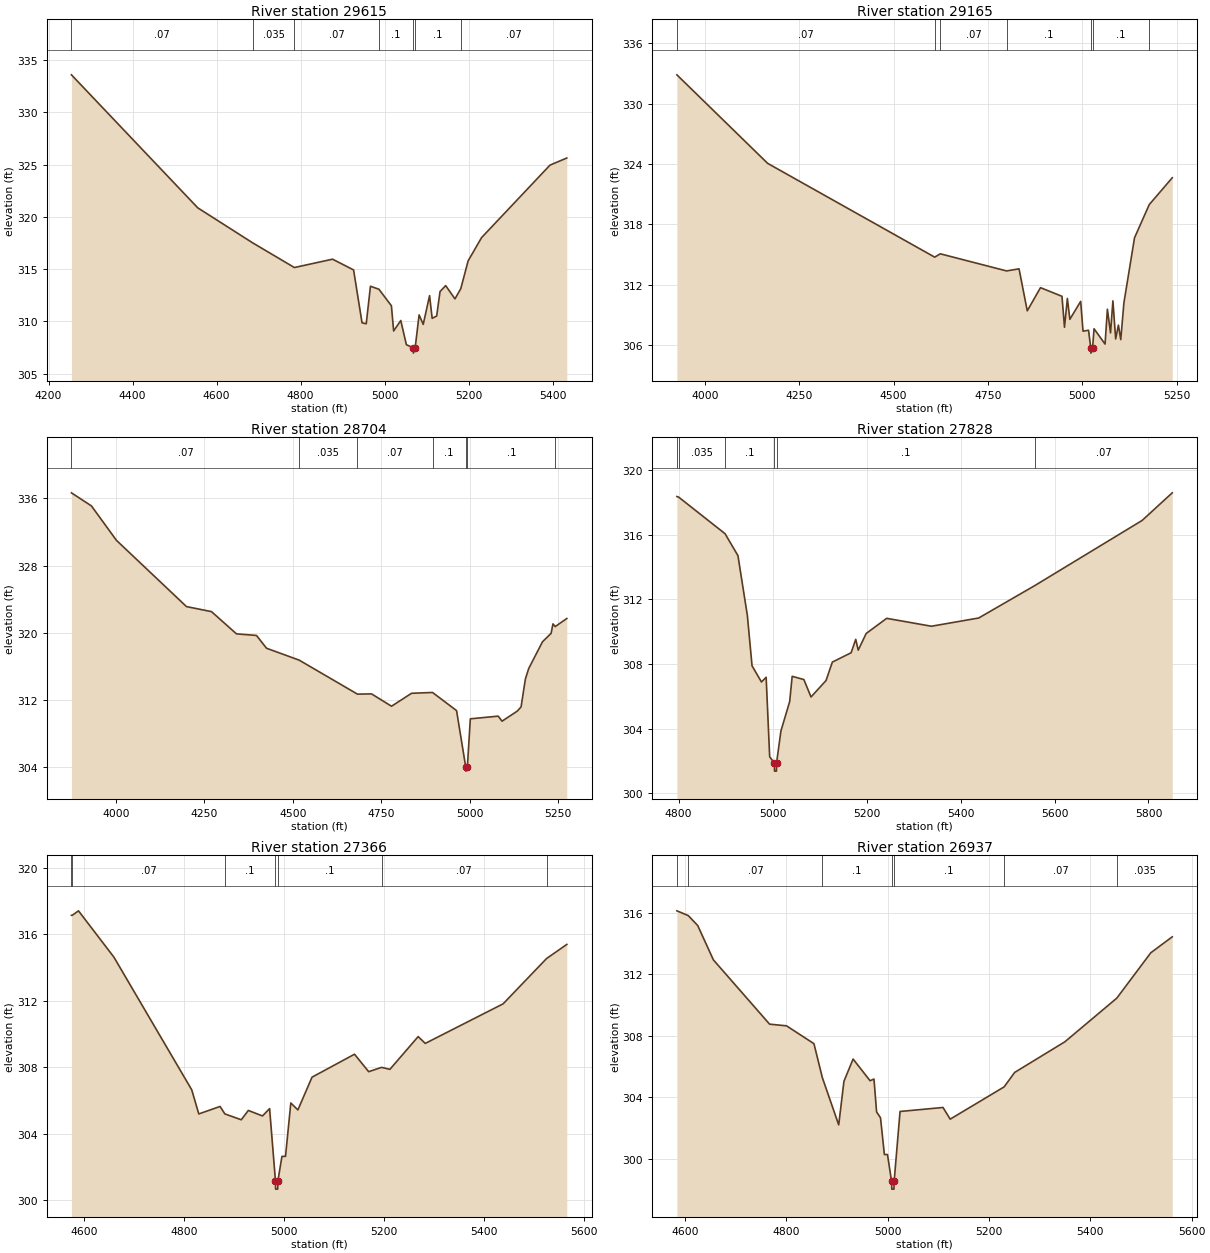
Type RM Length L Ch R = 1 ,29615   ,450,450,450
BEGIN DESCRIPTION:
WEST COTTONWOOD CREEK 55.0
END DESCRIPTION:
XS GIS Cut Line= 3
      2412924.95       13620775.        2413675.       13620725.
      2414074.99       13620575.
#Sta/Elev= 30
  4254.5  333.59  4555.2  320.86  4686.3   317.5  4785.1  315.15  4875.9  315.95
    4926  314.92  4946.1  309.86  4956.1  309.77  4966.1  313.36  4986.4  313.07
    5016  311.49  5021.3  309.08  5038.3  310.08  5051.6  307.77    5068  307.46
  5068.3  306.96  5072.5  307.46  5081.9  310.62  5091.7  309.71  5106.8  312.46
    5113  310.29  5123.7  310.51  5131.7  312.85  5145.1  313.42  5167.3  312.15
  5181.1  313.13  5198.5  315.78  5230.5  318.01  5393.4  324.95  5433.4  325.63
#Mann= 7 ,-1 , 0
  4254.5     .07       0  4686.3    .035       0  4785.1     .07       0
  4986.4      .1       0    5068     .05       0  5072.5      .1       0
  5181.1     .07       0
Bank Sta=5068,5072.5
XS Rating Curve= 0 ,0
Exp/Cntr=0.3,0.1

Type RM Length L Ch R = 1 ,29165   ,461,461,461
BEGIN DESCRIPTION:
WEST COTTONWOOD CREEK 54.0
END DESCRIPTION:
XS GIS Cut Line= 3
      2413275.02     13621774.98        2413975.       13620975.
      2414125.01     13620774.99
#Sta/Elev= 30
  3925.4  332.85    4166  324.06  4608.7  314.75  4623.6  315.08  4799.4  313.38
  4832.3  313.59  4854.1  309.42  4889.2  311.72  4946.1  310.86  4952.8  307.79
  4960.4  310.65    4967  308.58  4995.7  310.36  5001.9   307.4  5016.5  307.49
  5022.5  305.72  5022.8  305.22  5027.2  305.72  5031.1  307.64  5060.3  306.12
  5066.5  309.58  5074.8  307.23  5081.1  310.41  5088.4  306.63  5095.7     308
  5101.9  306.56  5110.3  310.22  5138.4  316.67  5177.5  319.97  5238.4  322.63
#Mann= 7 ,-1 , 0
  3925.4     .07       0  4608.7    .035       0  4623.6     .07       0
  4799.4      .1       0  5022.5     .05       0  5027.2      .1       0
  5177.5     .07       0
Bank Sta=5022.5,5027.2
XS Rating Curve= 0 ,0
Exp/Cntr=0.3,0.1

Type RM Length L Ch R = 1 ,28704   ,876,876,876
BEGIN DESCRIPTION:
WEST COTTONWOOD CREEK 53.0
END DESCRIPTION:
XS GIS Cut Line= 3
      2413324.96     13621925.04        2414125.       13621125.
      2414225.01     13620874.98
#Sta/Elev= 30
  3873.9  336.67  3930.5  335.11  4001.2  331.01  4199.2  323.12  4269.9  322.52
  4340.6  319.87  4397.2  319.68  4425.5  318.16  4517.9  316.74  4682.7  312.69
  4722.5  312.72    4779  311.25  4835.6  312.79  4894.9  312.89  4962.9  310.73
  4988.8  304.02  4989.2  303.52  4993.5  304.02  5001.8  309.75  5080.7  310.07
  5091.5  309.47  5134.6  310.67  5145.3  311.17  5157.5  314.49  5166.9  315.74
  5205.9  318.93  5230.2  319.93  5235.5  321.06  5241.9  320.74  5274.6   321.7
#Mann= 7 ,-1 , 0
  3873.9     .07       0  4517.9    .035       0  4682.7     .07       0
  4894.9      .1       0  4988.8     .05       0  4993.5      .1       0
  5241.9     .07       0
Bank Sta=4988.8,4993.5
XS Rating Curve= 0 ,0
Exp/Cntr=0.3,0.1

Type RM Length L Ch R = 1 ,27828   ,462,462,462
BEGIN DESCRIPTION:
WEST COTTONWOOD CREEK 52.0
END DESCRIPTION:
XS GIS Cut Line= 3
        2414275.     13621975.03        2414275.       13621775.
      2414574.99     13620975.03
#Sta/Elev= 30
  4796.2  318.37  4800.2  318.33  4898.7  316.07  4926.2  314.71  4946.2  311.01
  4956.2  307.89  4976.2  306.89  4986.2  307.18  4993.7  302.26  5003.6  301.87
    5004  301.37  5008.1  301.37  5008.4  301.87  5017.6  303.85  5036.3  305.68
  5041.6  307.24  5066.5  307.04  5081.7  305.96  5113.7  306.98  5127.1  308.12
  5167.1   308.7  5176.9  309.53  5182.2  308.86  5199.1  309.89  5242.8  310.83
    5338  310.34  5438.6  310.85  5557.6  312.85  5786.5  316.89  5850.6   318.6
#Mann= 6 ,-1 , 0
  4796.2     .07       0  4800.2    .035       0  4898.7      .1       0
  5003.6     .05       0  5008.4      .1       0  5557.6     .07       0
Bank Sta=5003.6,5008.4
XS Rating Curve= 0 ,0
Exp/Cntr=0.3,0.1

Type RM Length L Ch R = 1 ,27366   ,429,429,429
BEGIN DESCRIPTION:
WEST COTTONWOOD CREEK 51.0
END DESCRIPTION:
XS GIS Cut Line= 3
      2414375.01     13621974.99        2414675.       13621675.
      2415074.98     13621275.02
#Sta/Elev= 30
  4575.4  317.14  4576.9  317.14  4589.5  317.41  4660.2  314.63  4815.8  306.65
  4829.9   305.2  4872.4  305.65  4882.1   305.2  4914.8  304.85  4928.9  305.41
  4957.2  305.08  4971.4  305.52  4983.1  301.18  4983.4  300.68  4987.6  300.68
    4988  301.18  4996.1  302.65  5003.2  302.65  5013.8  305.86  5027.9  305.44
  5056.2  307.41  5141.1  308.79  5169.4  307.74  5195.2     308  5211.8  307.88
  5268.3  309.85  5282.5  309.44  5438.1  311.82  5524.8  314.54  5565.3  315.39
#Mann= 7 ,-1 , 0
  4575.4    .035       0  4576.9     .07       0  4882.1      .1       0
  4983.1     .05       0    4988      .1       0  5195.2     .07       0
  5524.8    .035       0
Bank Sta=4983.1,4988
XS Rating Curve= 0 ,0
Exp/Cntr=0.3,0.1

Type RM Length L Ch R = 1 ,26937   ,425,425,425
BEGIN DESCRIPTION:
WEST COTTONWOOD CREEK 50.0
END DESCRIPTION:
XS GIS Cut Line= 3
      2414475.01       13622125.        2414875.       13622025.
      2415275.01     13621624.99
#Sta/Elev= 30
  4583.7  316.13  4606.2  315.82  4624.9  315.17  4655.8  312.94  4766.7  308.76
  4800.2  308.65  4854.3  307.49  4870.9  305.28  4903.2  302.21  4913.5  305.04
  4931.6  306.49  4965.1  305.08  4972.8  305.19    4978  303.05  4985.7  302.67
  4993.4  300.28  4999.5  300.28  5007.6  298.53    5008  298.03  5012.3  298.03
  5012.6  298.53  5024.3  303.08  5109.1  303.34  5123.3  302.58  5229.8  304.68
  5250.6  305.62  5349.6  307.61  5452.2  310.45  5519.3   313.4  5561.7  314.44
#Mann= 7 ,-1 , 0
  4583.7    .035       0  4606.2     .07       0  4870.9      .1       0
  5007.6     .05       0  5012.6      .1       0  5229.8     .07       0
  5452.2    .035       0
Bank Sta=5007.6,5012.6
XS Rating Curve= 0 ,0
Exp/Cntr=0.3,0.1

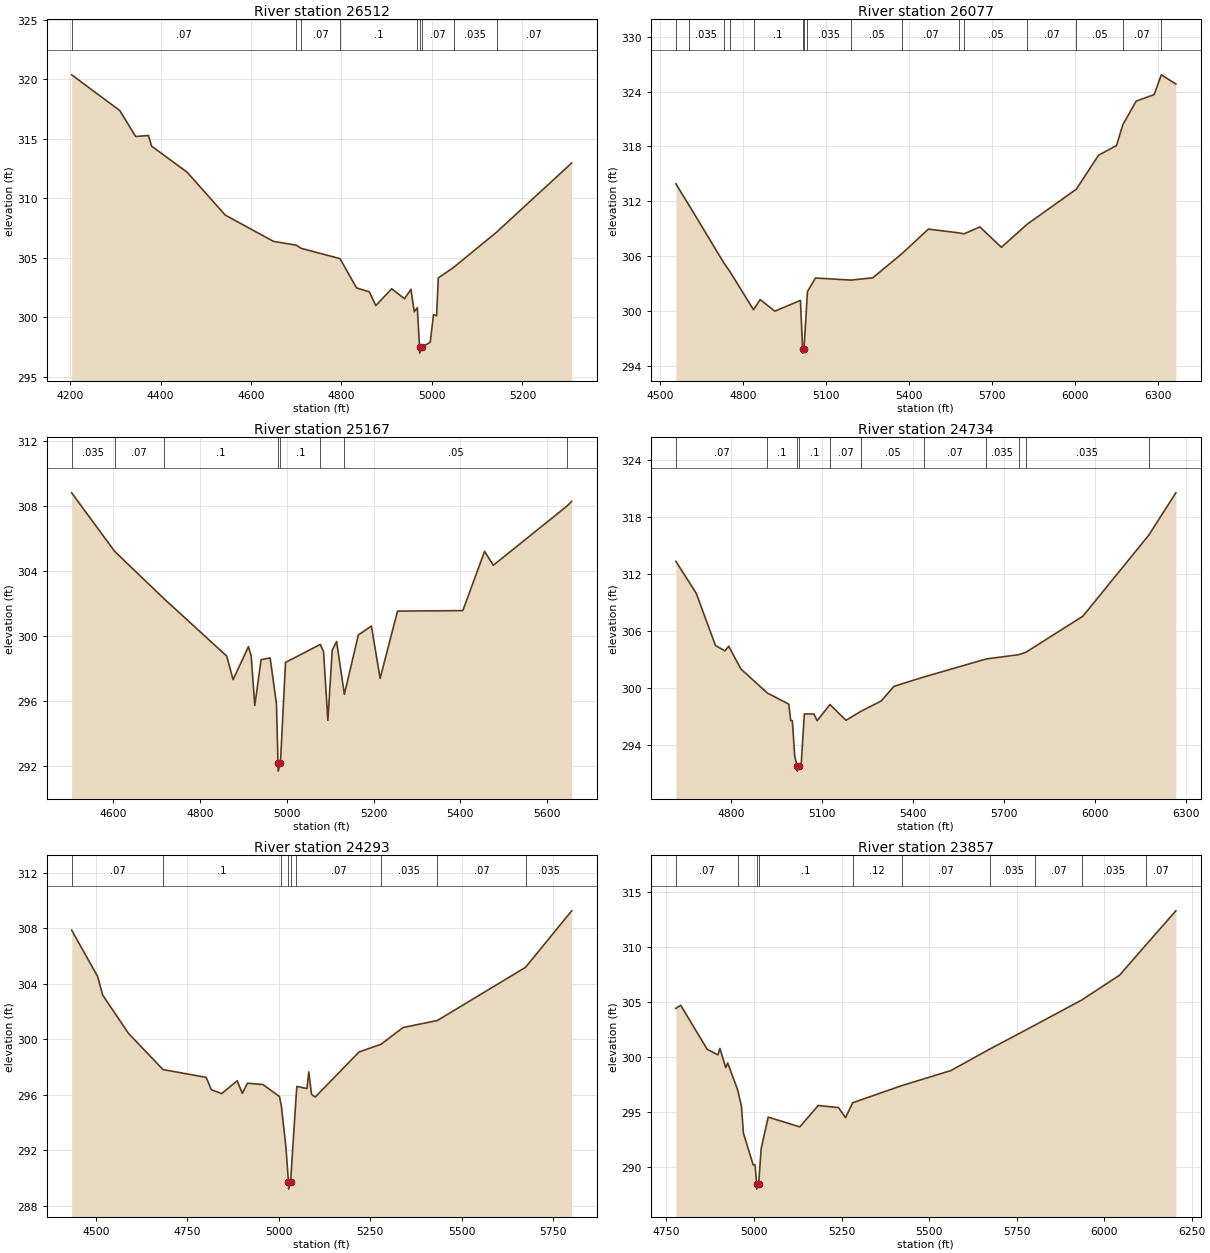
Type RM Length L Ch R = 1 ,26512   ,435,435,435
BEGIN DESCRIPTION:
WEST COTTONWOOD CREEK 49.0
END DESCRIPTION:
XS GIS Cut Line= 3
        2414625.       13622575.        2415225.       13622025.
        2415375.     13621774.99
#Sta/Elev= 30
  4203.4  320.38  4309.8  317.38  4344.9   315.2  4373.3  315.28  4380.1  314.39
  4458.4  312.21  4542.9   308.6  4649.5  306.39  4699.8  306.07  4711.2   305.8
  4796.7  304.94  4833.3  302.48  4861.6  302.15  4875.8  300.99    4911  302.41
  4939.3  301.57  4953.5  302.36  4960.9  300.48  4966.2  300.74  4967.7  300.81
  4972.6   297.5    4973     297  4977.6   297.5  4996.1  297.91  5003.5  300.24
  5010.3  300.14    5014  303.32  5047.8   304.2  5143.2  307.17  5308.9  312.97
#Mann= 9 ,-1 , 0
  4203.4     .07       0  4699.8    .035       0  4711.2     .07       0
  4796.7      .1       0  4966.2     .07       0  4972.6     .05       0
  4977.6     .07       0  5047.8    .035       0  5143.2     .07       0
Bank Sta=4972.6,4977.6
XS Rating Curve= 0 ,0
Exp/Cntr=0.3,0.1

Type RM Length L Ch R = 1 ,26077   ,910,910,910
BEGIN DESCRIPTION:
WEST COTTONWOOD CREEK 48.0
END DESCRIPTION:
XS GIS Cut Line= 3
      2414924.98     13622575.01        2415325.       13622375.
      2416125.01     13621274.99
#Sta/Elev= 30
  4556.1  313.92  4602.3  311.65  4728.4  305.32  4751.9   304.3  4836.8  300.14
  4860.8  301.25  4913.9  299.98  5006.4  301.16  5014.3  295.89  5014.7  295.39
  5019.4  295.89  5031.8  302.13  5060.9  303.61  5189.1  303.38    5268  303.63
  5374.1  306.29    5469  308.96  5581.1  308.54  5597.8  308.44  5655.2   309.2
  5732.9  306.97  5826.6  309.51  6003.5  313.32  6084.1  317.05    6149   318.1
  6171.8  320.38  6220.1  322.96    6285  323.68    6311  325.84  6363.5  324.84
#Mann= 16 ,-1 , 0
  4556.1     .07       0  4602.3    .035       0  4728.4      .1       0
  4751.9     .07       0  4836.8      .1       0  5014.3     .05       0
  5019.4      .1       0  5031.8    .035       0  5189.1     .05       0
  5374.1     .07       0  5581.1    .035       0  5597.8     .05       0
  5826.6     .07       0  6003.5     .05       0  6171.8     .07       0
    6311    .035       0
Bank Sta=5014.3,5019.4
XS Rating Curve= 0 ,0
Exp/Cntr=0.3,0.1

Type RM Length L Ch R = 1 ,25167   ,433,433,433
BEGIN DESCRIPTION:
WEST COTTONWOOD CREEK 47.0
END DESCRIPTION:
XS GIS Cut Line= 3
      2415374.98     13623075.03        2415675.       13622675.
        2415625.     13622024.96
#Sta/Elev= 30
  4504.4  308.83  4603.4  305.23  4716.1  302.34  4861.7  298.78  4876.3  297.33
  4911.7  299.36    4918   298.8  4926.3  295.74  4940.9  298.56  4961.7  298.67
  4976.3  295.83  4979.8   292.2  4980.2   291.7  4985.4   292.2  4997.1  298.39
  5077.3   299.5  5084.7  299.06  5094.7  294.83  5104.7  299.14  5114.8  299.68
  5132.7  296.43  5164.9  300.08    5195  300.63  5215.1  297.41  5255.2  301.55
  5405.6  301.58  5455.8  305.23  5475.8  304.37  5644.5  307.99  5656.4   308.3
#Mann= 8 ,-1 , 0
  4504.4    .035       0  4603.4     .07       0  4716.1      .1       0
  4979.8     .05       0  4985.4      .1       0  5077.3     .07       0
  5132.7     .05       0  5644.5     .07       0
Bank Sta=4979.8,4985.4
XS Rating Curve= 0 ,0
Exp/Cntr=0.3,0.1

Type RM Length L Ch R = 1 ,24734   ,441,441,441
BEGIN DESCRIPTION:
WEST COTTONWOOD CREEK 46.0
END DESCRIPTION:
XS GIS Cut Line= 3
        2415675.       13623275.        2415825.       13622925.
        2416225.       13621725.
#Sta/Elev= 30
  4619.3  313.33  4686.4  309.96  4749.9  304.46  4780.7  303.91  4793.4  304.39
  4833.3     302  4920.4  299.47    4991   298.3  4997.4  296.56  5002.7  296.56
  5010.6  292.86  5018.3  291.75  5018.8  291.25    5024  291.75  5031.7  291.93
  5042.3  297.27  5073.9  297.26  5084.4  296.55  5126.5  298.26  5179.3   296.6
  5229.4  297.56  5295.2  298.63  5337.4  300.17  5435.1  301.15  5640.8  303.05
  5747.3   303.5  5771.4  303.75  5959.3  307.56  6175.7  316.07    6265  320.53
#Mann= 11 ,-1 , 0
  4619.3     .07       0  4920.4      .1       0  5018.3     .05       0
    5024      .1       0  5126.5     .07       0  5229.4     .05       0
  5435.1     .07       0  5640.8    .035       0  5747.3     .07       0
  5771.4    .035       0  6175.7     .07       0
Bank Sta=5018.3,5024
XS Rating Curve= 0 ,0
Exp/Cntr=0.3,0.1

Type RM Length L Ch R = 1 ,24293   ,436,436,436
BEGIN DESCRIPTION:
WEST COTTONWOOD CREEK 45.0
END DESCRIPTION:
XS GIS Cut Line= 3
      2415774.98     13623225.02        2416175.       13622825.
        2416225.     13622024.98
#Sta/Elev= 30
  4433.5  307.86  4504.2  304.54  4518.4  303.18  4589.1  300.42  4683.3  297.82
  4801.2  297.26  4815.4  296.37  4843.7  296.09  4886.1  297.01  4900.2  296.11
  4914.4  296.84  4956.8  296.74  5001.7  295.88    5007  295.19  5019.3  292.25
  5026.4  289.71  5026.9  289.21  5032.1  289.71  5045.9  295.34  5049.3  296.61
  5076.9  296.45  5081.9  297.65  5089.4  296.04  5099.4  295.84  5219.6  299.09
  5279.5  299.64  5339.9  300.85  5433.3  301.35  5674.6  305.18  5800.8  309.25
#Mann= 9 ,-1 , 0
  4433.5     .07       0  4683.3      .1       0    5007     .12       0
  5026.4     .05       0  5032.1     .12       0  5045.9     .07       0
  5279.5    .035       0  5433.3     .07       0  5674.6    .035       0
Bank Sta=5026.4,5032.1
XS Rating Curve= 0 ,0
Exp/Cntr=0.3,0.1

Type RM Length L Ch R = 1 ,23857   ,440,440,440
BEGIN DESCRIPTION:
WEST COTTONWOOD CREEK 44.0
END DESCRIPTION:
XS GIS Cut Line= 3
        2416275.     13623324.99        2416375.       13623125.
        2416275.     13621924.96
#Sta/Elev= 30
  4776.9   304.4  4790.9  304.69  4866.3  300.68  4897.1  300.17  4902.7  300.76
  4919.4  299.01    4925  299.43  4953.2     297  4964.2  295.51  4969.8  293.05
  4997.7  290.15    5003  290.15  5007.6  288.44  5008.1  287.94  5013.4  288.44
  5020.6  291.64  5040.6   294.5  5130.9  293.61  5183.6  295.56  5241.3  295.37
  5261.4  294.45    5282  295.81  5422.1  297.37  5562.4  298.74  5673.4   300.7
    5803  302.89  5936.1  305.17  6044.1  307.43  6118.1  310.14  6204.7  313.29
#Mann= 10 ,-1 , 0
  4776.9     .07       0  4953.2      .1       0  5007.6     .05       0
  5013.4      .1       0    5282     .12       0  5422.1     .07       0
  5673.4    .035       0    5803     .07       0  5936.1    .035       0
  6118.1     .07       0
Bank Sta=5007.6,5013.4
XS Rating Curve= 0 ,0
Exp/Cntr=0.3,0.1

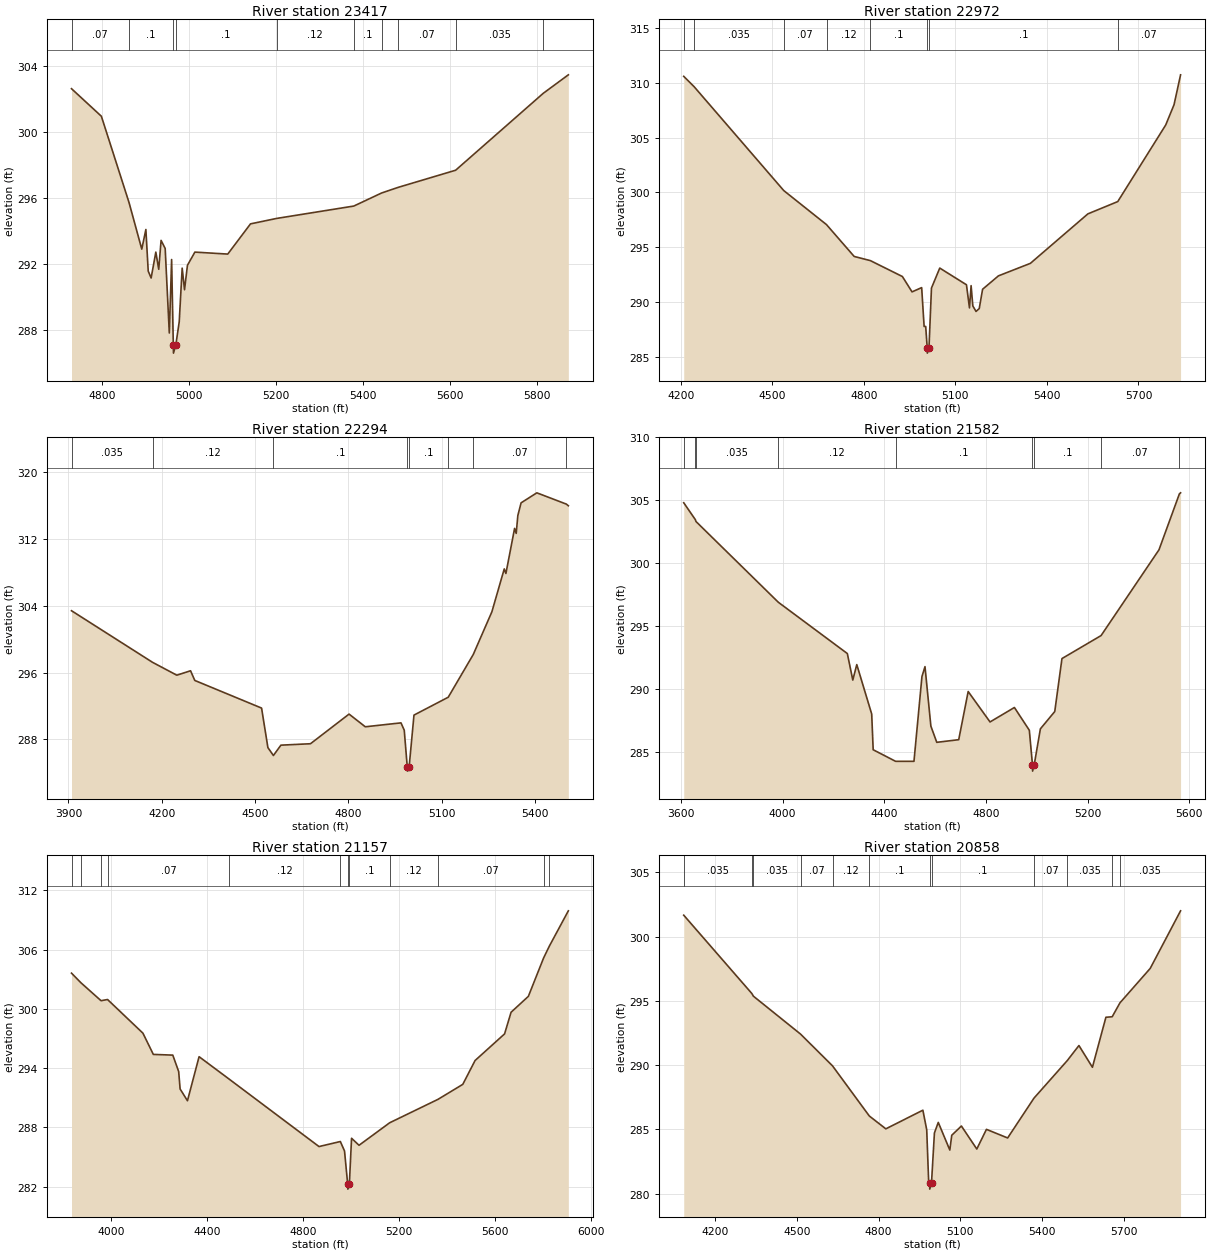
Type RM Length L Ch R = 1 ,23417   ,445,445,445
BEGIN DESCRIPTION:
WEST COTTONWOOD CREEK 43.0
END DESCRIPTION:
XS GIS Cut Line= 3
      2416624.99     13623325.03        2416725.       13623075.
        2416375.       13622275.
#Sta/Elev= 30
  4730.5  302.64  4799.2  300.97  4862.7  295.75  4892.1  292.92  4901.5  294.11
  4906.9  291.59  4913.6  291.17  4924.4  292.74  4931.1   291.7  4936.5  293.45
  4945.9  292.96  4955.4  287.84  4960.7  292.29  4964.6  287.12    4965  286.62
  4970.4  287.12  4978.2  288.52    4985  291.77  4990.4  290.46  4997.1  291.94
  5014.2  292.74  5089.8  292.62  5142.1  294.45  5202.1  294.78  5379.7  295.53
  5443.5  296.32  5481.4  296.66  5613.8   297.7  5815.3  302.36    5873  303.48
#Mann= 10 ,-1 , 0
  4730.5     .07       0  4862.7      .1       0  4964.6     .05       0
  4970.4      .1       0  5202.1     .12       0  5379.7      .1       0
  5443.5     .12       0  5481.4     .07       0  5613.8    .035       0
  5815.3     .07       0
Bank Sta=4964.6,4970.4
XS Rating Curve= 0 ,0
Exp/Cntr=0.3,0.1

Type RM Length L Ch R = 1 ,22972   ,678,678,678
BEGIN DESCRIPTION:
WEST COTTONWOOD CREEK 42.0
END DESCRIPTION:
XS GIS Cut Line= 3
      2416824.99     13623675.02        2417075.       13622925.
      2417324.99     13622125.04
#Sta/Elev= 30
  4209.4  310.58  4243.4  309.64  4537.4  300.17  4677.4  297.07  4768.1  294.17
  4821.2  293.79  4926.2  292.34  4957.8  290.94  4989.4  291.33  4997.4  287.79
  5002.6  287.79  5007.5  285.86    5008  285.36  5013.4  285.86  5021.5  291.29
  5048.7  293.11  5136.2  291.59  5146.1  289.48  5151.4  291.51  5157.1  289.66
  5167.6  289.16  5178.1  289.42  5189.1  291.18    5241   292.4  5345.7  293.54
  5534.3  298.05  5632.2  299.17  5789.4  306.15  5816.7     308  5838.1  310.72
#Mann= 8 ,-1 , 0
  4209.4     .07       0  4243.4    .035       0  4537.4     .07       0
  4677.4     .12       0  4821.2      .1       0  5007.5     .05       0
  5013.4      .1       0  5632.2     .07       0
Bank Sta=5007.5,5013.4
XS Rating Curve= 0 ,0
Exp/Cntr=0.3,0.1

Type RM Length L Ch R = 1 ,22294   ,712,712,712
BEGIN DESCRIPTION:
H21627
END DESCRIPTION:
XS GIS Cut Line= 3
      2416923.34     13623486.39        2417430.     13623121.84
      2417707.87     13622189.44
#Sta/Elev= 30
  3910.1  303.42  4170.6  297.24  4248.6   295.7  4292.8  296.23  4306.4  295.07
  4521.1  291.76  4541.4  287.03  4559.1  286.08  4583.2  287.32  4678.3  287.49
  4802.3  291.04  4854.5  289.52  4969.2  289.99  4979.7  289.11  4989.4  284.71
  4989.9  284.21  4995.4  284.71    5011  290.92  5121.1  293.06  5201.6  298.18
  5261.4  303.29  5301.2  308.43  5306.5  307.88  5334.4  313.28  5339.6  312.68
  5344.9  314.83  5355.3  316.34  5405.9  317.54  5500.7  316.19  5507.2  315.99
#Mann= 8 ,-1 , 0
  3910.1    .035       0  4170.6     .12       0  4559.1      .1       0
  4989.4     .05       0  4995.4      .1       0  5121.1     .12       0
  5201.6     .07       0  5500.7    .035       0
Bank Sta=4989.4,4995.4
XS Rating Curve= 0 ,0
Exp/Cntr=0.3,0.1

Type RM Length L Ch R = 1 ,21582   ,425,425,425
BEGIN DESCRIPTION:
WEST COTTONWOOD CREEK 41.0
END DESCRIPTION:
XS GIS Cut Line= 3
      2416925.04     13623524.98        2418125.       13622825.
      2418525.01     13622424.99
#Sta/Elev= 30
  3610.8  304.81  3656.7  303.46    3659  303.32  3982.9   296.9  4254.5  292.82
    4276  290.71  4291.7  291.94  4350.4  288.01  4356.2  285.17  4444.4  284.25
  4516.7  284.25  4548.1  290.99  4560.1  291.78  4583.2  287.05  4606.4  285.76
  4692.8  285.97    4730   289.8    4816  287.38  4911.9  288.53  4970.6  286.72
    4983  283.97  4983.5  283.47  4989.8  283.97  5014.1  286.83  5070.7  288.21
    5099  292.42    5253  294.25  5480.8  301.07  5561.1  305.52  5565.7   305.6
#Mann= 9 ,-1 , 0
  3610.8    .035       0  3656.7     .07       0    3659    .035       0
  3982.9     .12       0  4444.4      .1       0    4983     .05       0
  4989.8      .1       0    5253     .07       0  5561.1    .035       0
Bank Sta=4983,4989.8
XS Rating Curve= 0 ,0
Exp/Cntr=0.3,0.1

Type RM Length L Ch R = 1 ,21157   ,299,299,299
BEGIN DESCRIPTION:
WEST COTTONWOOD CREEK 40.0
END DESCRIPTION:
XS GIS Cut Line= 3
      2417075.01       13623575.        2418175.       13623175.
      2418674.97     13622425.04
#Sta/Elev= 30
  3833.9  303.61    3873  302.64  3957.1  300.82  3984.2  300.94  4131.8  297.53
  4175.1  295.38  4256.2  295.31  4280.8  293.65  4286.8  291.88  4317.4  290.69
  4365.9  295.15  4491.3  292.88    4866  286.05    4955  286.56  4972.4   285.6
  4985.6  282.24  4986.1  281.74  4992.5  282.24  5001.7  286.89  5032.9  286.18
  5160.7  288.46  5362.1  290.83  5465.6  292.35  5516.7  294.76  5639.8  297.46
  5666.9  299.65    5739  301.26  5802.6  305.15  5826.8  306.36  5905.7  309.92
#Mann= 12 ,-1 , 0
  3833.9    .035       0    3873     .07       0  3957.1    .035       0
  3984.2     .07       0  4491.3     .12       0    4955      .1       0
  4985.6     .05       0  4992.5      .1       0  5160.7     .12       0
  5362.1     .07       0  5802.6    .035       0  5826.8     .07       0
Bank Sta=4985.6,4992.5
XS Rating Curve= 0 ,0
Exp/Cntr=0.3,0.1

Type RM Length L Ch R = 1 ,20858   ,799,799,799
BEGIN DESCRIPTION:
H21626
END DESCRIPTION:
XS GIS Cut Line= 3
      2417578.27     13623881.86      2418282.69     13623430.78
      2418980.49     13622732.99
#Sta/Elev= 30
  4085.1  301.66  4334.9  295.57  4340.8  295.36  4513.8  292.41  4631.1  289.94
  4766.1  286.04  4826.8  285.04  4962.7  286.49  4976.8  284.97  4983.9  280.95
  4987.5  280.85    4988  280.35  4994.4  280.85  5005.1  284.72  5019.2  285.54
  5061.6  283.39  5068.7  284.54  5104.1  285.26  5160.6  283.47    5196     285
  5273.8  284.33  5370.5  287.43  5492.6  290.35  5535.4  291.52  5584.9  289.83
  5634.4  293.72  5657.5  293.76  5685.9  294.84    5797  297.52  5908.4     302
#Mann= 12 ,-1 , 0
  4085.1    .035       0  4334.9     .07       0  4340.8    .035       0
  4513.8     .07       0  4631.1     .12       0  4766.1      .1       0
  4987.5     .05       0  4994.4      .1       0  5370.5     .07       0
  5492.6    .035       0  5657.5     .07       0  5685.9    .035       0
Bank Sta=4987.5,4994.4
XS Rating Curve= 0 ,0
Exp/Cntr=0.3,0.1

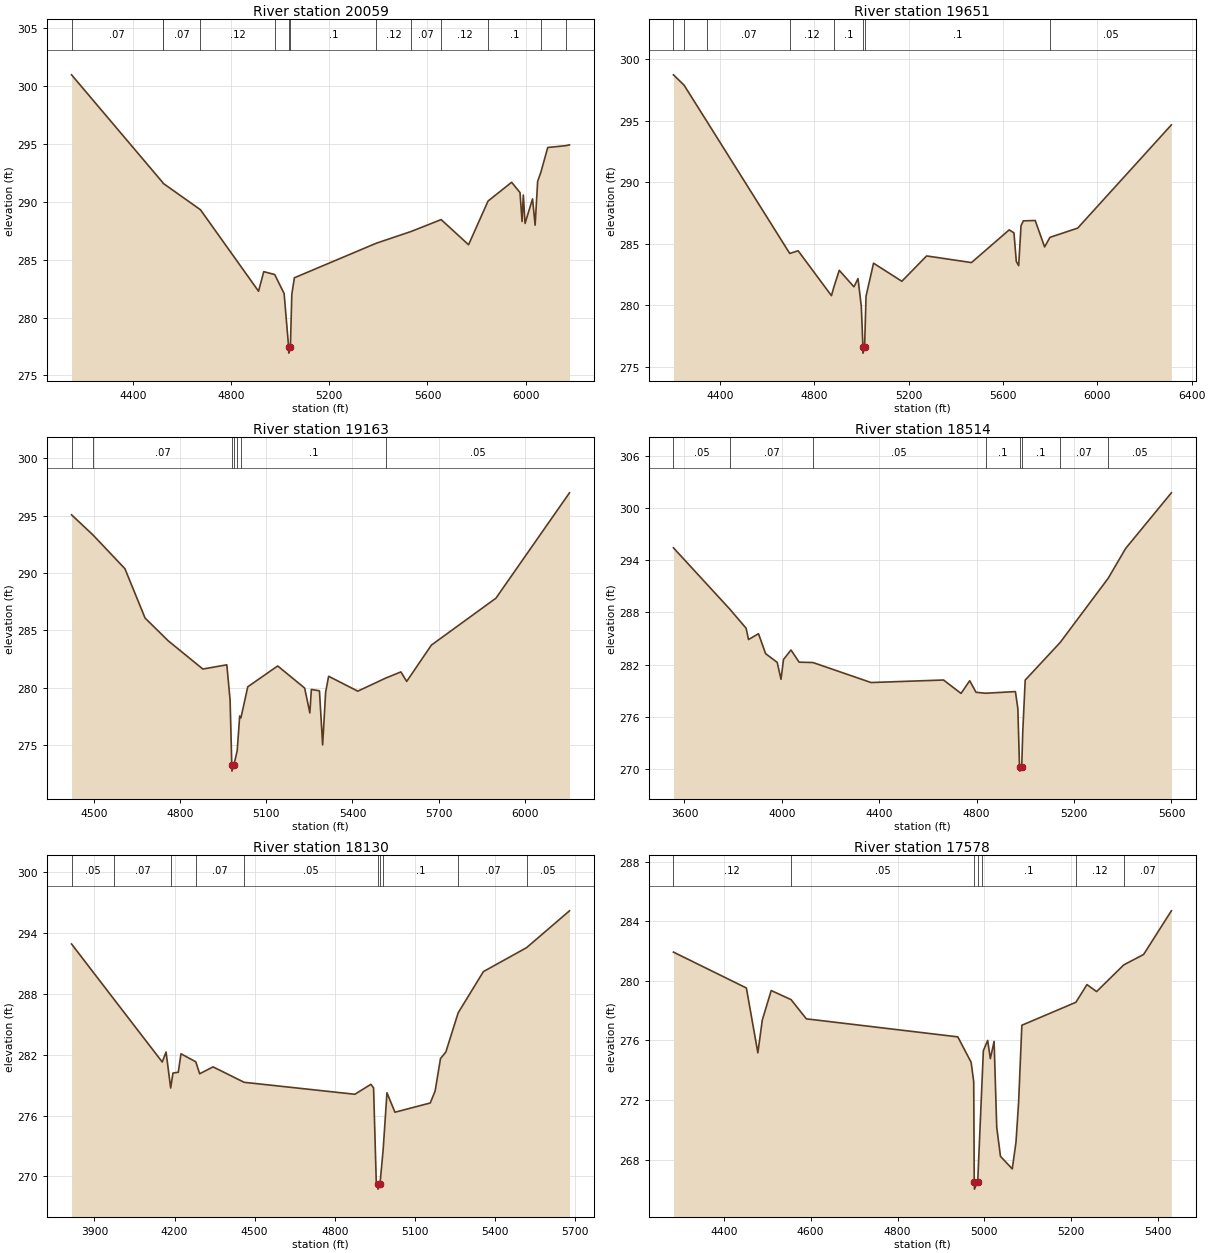
Type RM Length L Ch R = 1 ,20059   ,408,408,408
BEGIN DESCRIPTION:
H21625
END DESCRIPTION:
XS GIS Cut Line= 4
      2417708.09     13624054.83      2418270.34     13623702.66
      2418875.87     13623523.47      2419591.32     13623356.94
#Sta/Elev= 30
  4149.4  300.94    4521  291.65  4522.7  291.58  4674.8   289.3  4911.6  282.27
  4932.8  283.96  4977.5  283.71  5015.8  282.07  5034.3  277.43  5034.8  276.93
  5041.3  277.43  5047.1  281.99  5057.6  283.43  5391.2  286.41  5532.8  287.42
  5655.9  288.45  5767.6  286.28    5847  290.05  5943.1  291.67  5977.3  290.78
  5985.7  288.29  5990.8  290.57  5997.9  288.12  6028.3  290.24  6038.9  287.97
  6049.2  291.75  6062.7  292.56  6090.3  294.67  6164.4  294.83  6178.9   294.9
#Mann= 13 ,-1 , 0
  4149.4     .07       0    4521    .035       0  4522.7     .07       0
  4674.8     .12       0  4977.5      .1       0  5034.3     .05       0
  5041.3      .1       0  5391.2     .12       0  5532.8     .07       0
  5655.9     .12       0    5847      .1       0  6062.7     .12       0
  6164.4      .1       0
Bank Sta=5034.3,5041.3
XS Rating Curve= 0 ,0
Exp/Cntr=0.3,0.1

Type RM Length L Ch R = 1 ,19651   ,488,488,488
BEGIN DESCRIPTION:
H21624
END DESCRIPTION:
XS GIS Cut Line= 3
      2417837.82     13624172.25      2418783.19     13623906.56
      2419911.93     13623851.05
#Sta/Elev= 30
  4201.8  298.74  4246.9   297.9  4344.8  294.92  4695.1  284.22  4730.7  284.44
  4872.1  280.79  4881.9  281.47  4905.2  282.85  4967.5  281.51  4984.7  282.18
  4998.7  279.92  5005.6  276.62  5006.1  276.12  5012.6  276.62  5018.8  280.75
  5050.6  283.43  5170.6  281.96  5275.7  284.02    5466  283.48  5626.1  286.14
  5646.2  285.89  5656.2  283.57  5666.2  283.23  5676.2  286.48  5686.2  286.87
  5736.3   286.9  5776.3  284.75  5798.8  285.53  5916.5  286.28  6313.9  294.67
#Mann= 8 ,-1 , 0
  4201.8     .07       0  4246.9    .035       0  4344.8     .07       0
  4695.1     .12       0  4881.9      .1       0  5005.6     .05       0
  5012.6      .1       0  5798.8     .05       0
Bank Sta=5005.6,5012.6
XS Rating Curve= 0 ,0
Exp/Cntr=0.3,0.1

Type RM Length L Ch R = 1 ,19163   ,649,649,649
BEGIN DESCRIPTION:
H21623
END DESCRIPTION:
XS GIS Cut Line= 4
      2417979.97     13624351.45      2418424.81     13624388.52
      2418888.23     13624252.58      2419690.74     13624295.79
#Sta/Elev= 30
  4422.3  295.08  4496.6  293.33    4608  290.38  4678.2  286.07  4758.5  284.09
  4879.3  281.62  4962.7  281.99  4974.1  278.91    4980  273.21  4980.5  272.71
    4987  273.21  4998.8   274.5  5007.5  277.52  5011.8  277.36  5035.6  280.07
  5139.8  281.89  5233.6  279.96  5251.7  277.79  5256.9  279.84  5285.1  279.72
  5296.2     275  5306.6  279.59    5317  280.99  5418.5  279.69  5515.7  280.83
  5568.7  281.37  5588.7  280.54  5674.7  283.71  5899.2   287.8  6155.3     297
#Mann= 7 ,-1 , 0
  4422.3    .035       0  4496.6     .07       0    4980     .05       0
    4987     .07       0  4998.8     .12       0  5011.8      .1       0
  5515.7     .05       0
Bank Sta=4980,4987
XS Rating Curve= 0 ,0
Exp/Cntr=0.3,0.1

Type RM Length L Ch R = 1 ,18514   ,384,384,384
BEGIN DESCRIPTION:
H21622
END DESCRIPTION:
XS GIS Cut Line= 3
      2417664.85     13624956.97      2418906.77     13624666.57
      2419671.49     13624580.23
#Sta/Elev= 30
  3554.7  295.42  3785.7  288.39  3853.3  286.17    3863  284.88    3904  285.55
  3933.2  283.26  3980.8  282.26  3996.5  280.31  4006.7  282.59  4037.5  283.68
  4070.9  282.28  4127.6  282.24  4366.2  279.94    4664  280.23  4735.9  278.69
  4771.5  280.15  4797.5  278.82  4836.6  278.71  4959.2   278.9  4969.2  276.97
    4976  270.28  4977.1  270.26  4977.6  269.76  4985.1  270.26  4989.4   274.3
  4999.4  280.22  5142.9  284.54  5340.2  291.92    5412  295.35  5599.7  301.74
#Mann= 8 ,-1 , 0
  3554.7     .05       0  3785.7     .07       0  4127.6     .05       0
  4836.6      .1       0  4977.1     .05       0  4985.1      .1       0
  5142.9     .07       0  5340.2     .05       0
Bank Sta=4977.1,4985.1
XS Rating Curve= 0 ,0
Exp/Cntr=0.3,0.1

Type RM Length L Ch R = 1 ,18130   ,552,552,552
BEGIN DESCRIPTION:
H21621
END DESCRIPTION:
XS GIS Cut Line= 3
      2417776.02     13625031.13      2419116.85      13624950.8
      2419635.87     13624901.37
#Sta/Elev= 30
  3814.3  292.91  3973.6  287.45  4153.9  281.28  4168.2  282.26  4185.5  278.72
    4194  280.19    4214  280.27    4224  282.09  4279.5   281.3  4294.1  280.12
  4344.2   280.8  4460.4  279.28  4875.2   278.1  4935.3  279.08  4945.3  278.73
  4955.3  269.51  4961.3  269.25  4961.8  268.75  4969.3  269.25  4981.1  272.62
  4995.4  278.25  5025.4  276.33  5157.5  277.24  5175.8  278.42  5195.9  281.62
  5215.9  282.26  5262.1  286.13  5356.6  290.19  5518.3  292.55  5678.9  296.18
#Mann= 10 ,-1 , 0
  3814.3     .05       0  3973.6     .07       0  4185.5     .12       0
  4279.5     .07       0  4460.4     .05       0  4961.3     .05       0
  4969.3     .05       0  4981.1      .1       0  5262.1     .07       0
  5518.3     .05       0
Bank Sta=4961.3,4969.3
XS Rating Curve= 0 ,0
Exp/Cntr=0.3,0.1

Type RM Length L Ch R = 1 ,17578   ,435,435,435
BEGIN DESCRIPTION:
WEST COTTONWOOD CREEK 36.0
END DESCRIPTION:
XS GIS Cut Line= 3
      2418175.03     13625225.01        2418875.       13625375.
      2419225.02     13625124.99
#Sta/Elev= 30
  4284.3  281.93  4452.2  279.52  4478.6  275.17  4488.8  277.37  4509.3  279.35
    4555  278.74  4590.2  277.45  4938.8  276.24  4969.5  274.53  4975.4  273.23
  4976.6  266.52  4977.1  266.02  4984.6  266.52    4995  273.54  4997.6  275.31
  5007.5     276  5013.7  274.78  5022.3  275.94  5028.4  270.16    5037  268.22
  5064.1  267.38  5072.7  269.17  5078.8  271.88  5086.2  277.02  5210.5  278.56
  5236.1  279.75  5258.2  279.28  5320.7  281.07  5366.4  281.77  5430.3   284.7
#Mann= 7 ,-1 , 0
  4284.3     .12       0    4555     .05       0  4976.6     .05       0
  4984.6     .05       0    4995      .1       0  5210.5     .12       0
  5320.7     .07       0
Bank Sta=4976.6,4984.6
XS Rating Curve= 0 ,0
Exp/Cntr=0.3,0.1