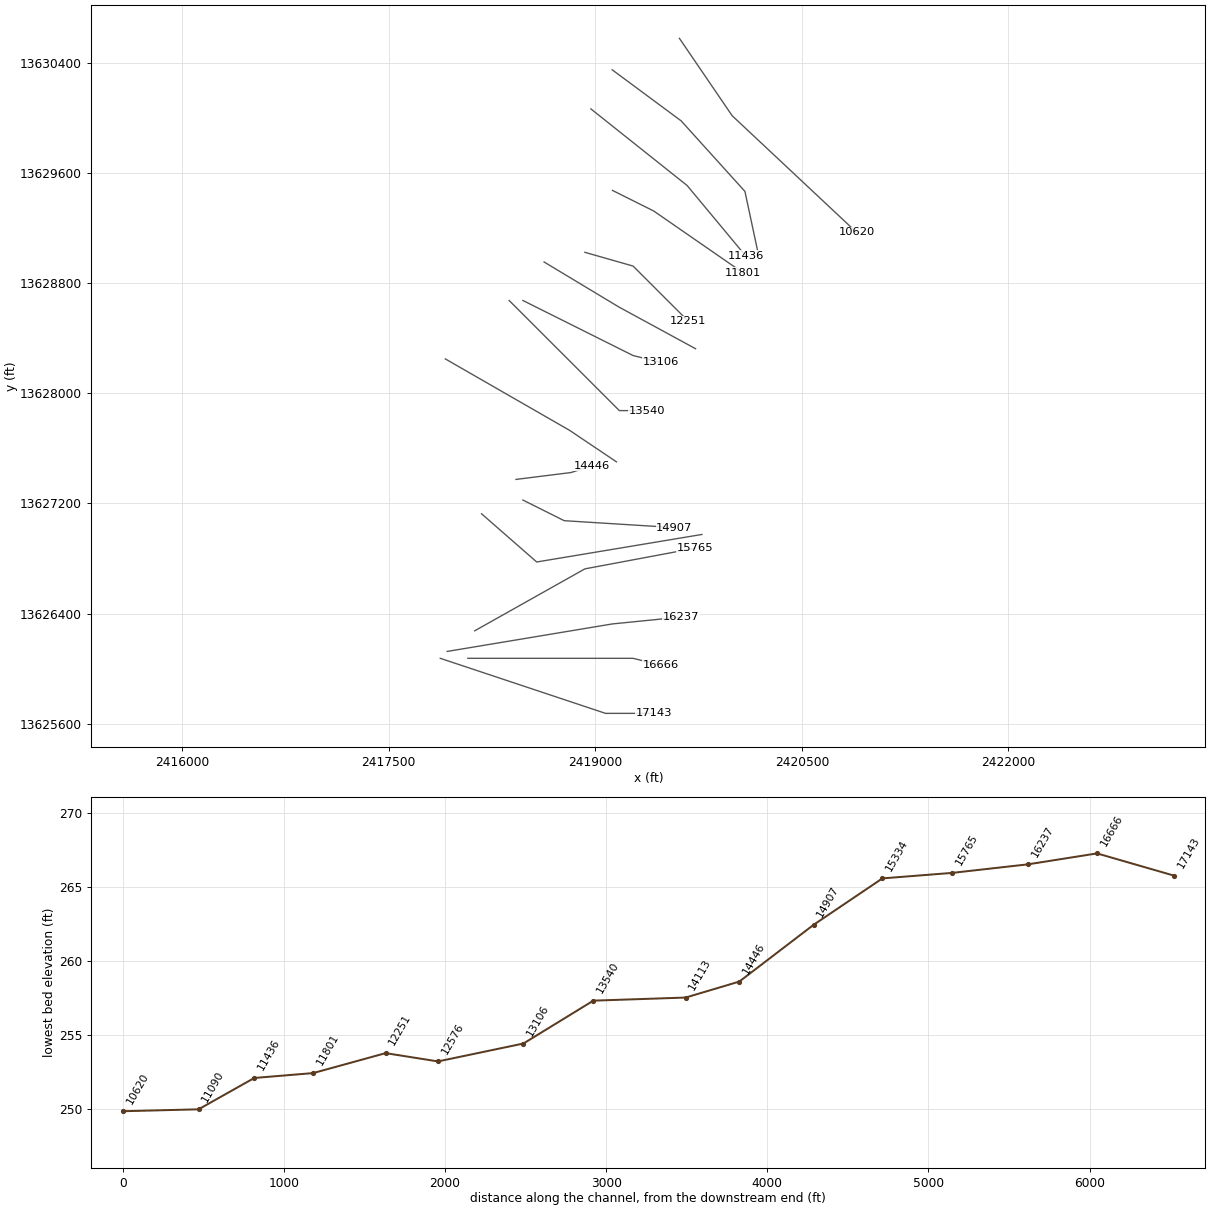
HEC-RAS study WEST COTTONWOOD CREEK.prj: WEST COTTONWOOD CREEK Base Level Engineering

--- WEST COTTONWOOD CREEK.g01 (geometry) --- (continued)

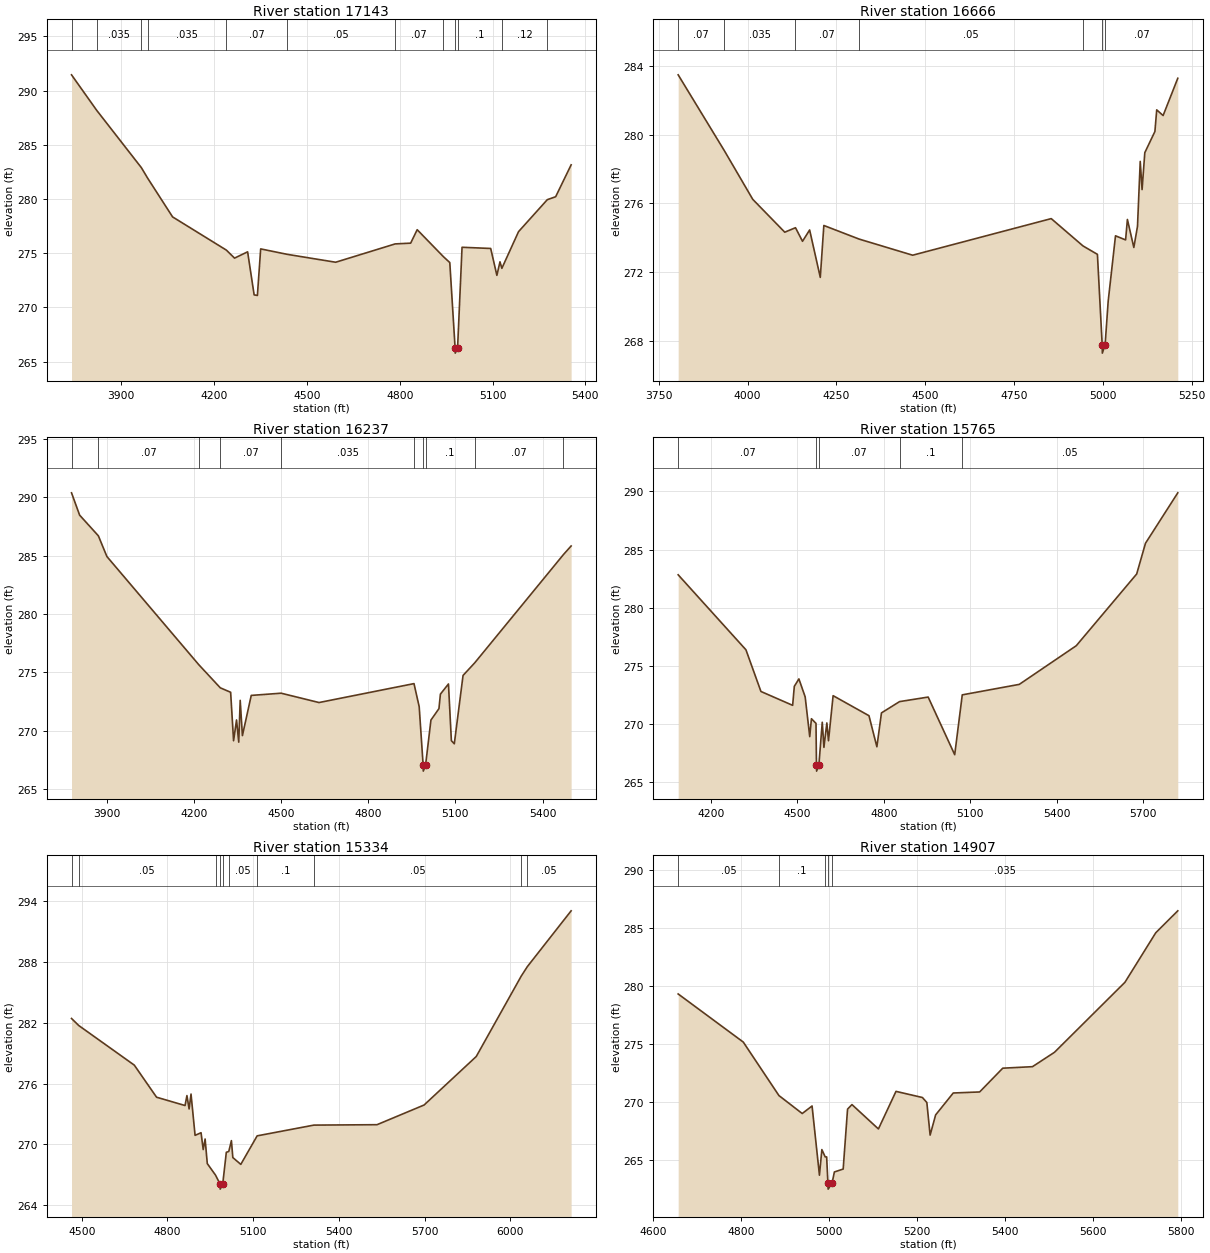
Type RM Length L Ch R = 1 ,17143   ,477,477,477
BEGIN DESCRIPTION:
WEST COTTONWOOD CREEK 35.0
END DESCRIPTION:
XS GIS Cut Line= 3
      2417875.02     13626074.99        2419075.       13625675.
      2419425.01       13625675.
#Sta/Elev= 30
  3739.2  291.45  3820.5  288.18    3965  282.89  3985.1  281.93  4065.9  278.35
  4239.6  275.29  4266.2  274.55  4308.4  275.13  4329.5  271.16    4340  271.11
  4350.6   275.4  4436.1   274.9    4593  274.17  4785.3  275.86  4835.4  275.93
  4856.5  277.17  4941.4  274.68  4961.9  274.14    4979  266.29  4979.5  265.79
  4987.1  266.29  5001.5  275.55  5094.1  275.44  5114.1  272.96  5124.1  274.21
  5130.2  273.61  5184.1  276.99  5277.1  279.94  5304.1  280.21  5354.1  283.15
#Mann= 12 ,-1 , 0
  3739.2     .05       0  3820.5    .035       0    3965     .07       0
  3985.1    .035       0  4239.6     .07       0  4436.1     .05       0
  4785.3     .07       0  4941.4      .1       0    4979     .05       0
  4987.1      .1       0  5130.2     .12       0  5277.1     .07       0
Bank Sta=4979,4987.1
XS Rating Curve= 0 ,0
Exp/Cntr=0.3,0.1

Type RM Length L Ch R = 1 ,16666   ,429,429,429
BEGIN DESCRIPTION:
WEST COTTONWOOD CREEK 34.0
END DESCRIPTION:
XS GIS Cut Line= 3
      2418074.97       13626075.        2419275.       13626075.
      2419475.02       13626025.
#Sta/Elev= 30
  3804.7  283.49  3934.8  279.07  4014.7  276.24  4104.7  274.33  4134.9  274.59
  4154.7   273.8  4174.7  274.46  4204.7   271.7  4214.7  274.72  4313.8  273.93
  4464.7  272.99  4854.7  275.12  4944.1  273.53  4984.7  273.04  4998.1  267.79
  4998.6  267.29  5006.4  267.79    5015  270.31  5035.6  274.12    5064  273.88
  5069.1  275.07  5087.2  273.44  5097.5  274.67  5105.2  278.45  5110.4  276.81
  5118.1  278.96  5146.5  280.19  5151.6  281.45  5169.6  281.12  5210.9  283.29
#Mann= 7 ,-1 , 0
  3804.7     .07       0  3934.8    .035       0  4134.9     .07       0
  4313.8     .05       0  4944.1     .07       0  4998.1     .05       0
  5006.4     .07       0
Bank Sta=4998.1,5006.4
XS Rating Curve= 0 ,0
Exp/Cntr=0.3,0.1

Type RM Length L Ch R = 1 ,16237   ,472,472,472
BEGIN DESCRIPTION:
WEST COTTONWOOD CREEK 33.0
END DESCRIPTION:
XS GIS Cut Line= 3
      2417924.97     13626124.99        2419125.       13626325.
      2419625.02       13626375.
#Sta/Elev= 30
  3779.1  290.37    3807  288.46  3871.5  286.69  3900.8  284.92    4217  275.66
    4291  273.68  4326.6   273.3  4336.7  269.15  4346.9  270.93  4354.5  269.03
  4359.5  272.61  4367.1  269.59  4397.5  273.03  4500.3  273.22  4630.7  272.42
  4957.5  274.04  4975.4  272.06    4989  267.05  4989.5  266.55  4997.3  267.05
  5015.8  270.92  5043.4   271.9  5048.4  273.14  5076.1  274.01  5086.1  269.16
  5096.2  268.89  5126.3  274.74  5166.2  275.81  5471.9  285.09  5498.2  285.82
#Mann= 10 ,-1 , 0
  3779.1     .05       0  3871.5     .07       0    4217    .035       0
    4291     .07       0  4500.3    .035       0  4957.5      .1       0
    4989     .05       0  4997.3      .1       0  5166.2     .07       0
  5471.9    .035       0
Bank Sta=4989,4997.3
XS Rating Curve= 0 ,0
Exp/Cntr=0.3,0.1

Type RM Length L Ch R = 1 ,15765   ,431,431,431
BEGIN DESCRIPTION:
WEST COTTONWOOD CREEK 32.0
END DESCRIPTION:
XS GIS Cut Line= 3
      2418124.96     13626274.98        2418925.       13626725.
      2419725.03     13626875.01
#Sta/Elev= 30
  4087.2  282.83  4322.1  276.39  4374.1  272.81    4484  271.62  4489.8  273.25
  4505.7  273.89  4527.4  272.35  4543.3  268.93  4549.1  270.47    4565  270.07
  4566.6  266.47  4567.1  265.97  4574.9  266.47  4586.7  270.17  4592.4  268.01
  4602.6  270.11  4608.3  268.58  4624.3  272.45  4748.6  270.73    4776  268.06
  4791.9  270.97  4854.6  271.94  4953.8  272.33  5045.8  267.38    5072  272.52
  5269.7  273.42  5467.2  276.74  5676.6   282.9  5707.2  285.54  5819.1  289.87
#Mann= 5 ,-1 , 0
  4087.2     .07       0  4566.6     .05       0  4574.9     .07       0
  4854.6      .1       0    5072     .05       0
Bank Sta=4566.6,4574.9
XS Rating Curve= 0 ,0
Exp/Cntr=0.3,0.1

Type RM Length L Ch R = 1 ,15334   ,427,427,427
BEGIN DESCRIPTION:
WEST COTTONWOOD CREEK 31.0
END DESCRIPTION:
XS GIS Cut Line= 3
      2418175.01     13627124.99        2418575.       13626775.
      2419774.95     13626974.99
#Sta/Elev= 30
  4464.4  282.42  4489.5  281.73  4684.1  277.82  4761.9  274.66  4861.6  273.84
  4868.2  274.82  4875.8   273.5  4882.5  274.97  4896.7   270.9  4917.6  271.16
  4925.2   269.5  4931.8  270.54  4939.4  268.12  4968.2  266.98  4984.1   266.1
  4984.6   265.6  4993.4   266.1    5006  269.23  5014.6  269.31  5023.8  270.38
  5028.8  268.71  5056.7  268.04  5113.8  270.85  5312.4  271.91  5533.2  271.95
  5697.9  273.89  5880.4  278.67  6037.7  286.59  6059.2  287.53  6212.4  293.03
#Mann= 10 ,-1 , 0
  4464.4    .035       0  4489.5     .05       0  4968.2     .07       0
  4984.1     .05       0  4993.4     .07       0  5014.6     .05       0
  5113.8      .1       0  5312.4     .05       0  6037.7    .035       0
  6059.2     .05       0
Bank Sta=4984.1,4993.4
XS Rating Curve= 0 ,0
Exp/Cntr=0.3,0.1

Type RM Length L Ch R = 1 ,14907   ,461,461,461
BEGIN DESCRIPTION:
WEST COTTONWOOD CREEK 30.0
END DESCRIPTION:
XS GIS Cut Line= 3
      2418474.99     13627225.01        2418775.       13627075.
      2419575.01       13627025.
#Sta/Elev= 30
  4656.7  279.29  4804.9  275.14    4886  270.53    4939  268.98  4961.4  269.63
  4978.2  263.66  4983.7  265.87  4991.3  265.24  4994.6  265.24  4997.5  262.96
    4998  262.46  5006.8  262.96  5012.2  263.94  5032.2  264.19  5042.2  269.36
  5052.2  269.75  5112.4  267.65  5152.4  270.89  5212.6  270.36  5222.6  269.93
  5230.1  267.12  5242.6  268.86  5282.7  270.75  5342.8  270.84  5395.4  272.89
    5463  273.02  5513.1  274.26  5673.5   280.3  5743.6  284.57  5793.7  286.46
#Mann= 5 ,-1 , 0
  4656.7     .05       0    4886      .1       0  4991.3    .035       0
  4997.5    .035       0  5006.8    .035       0
Bank Sta=4997.5,5006.8
XS Rating Curve= 0 ,0
Exp/Cntr=0.3,0.1

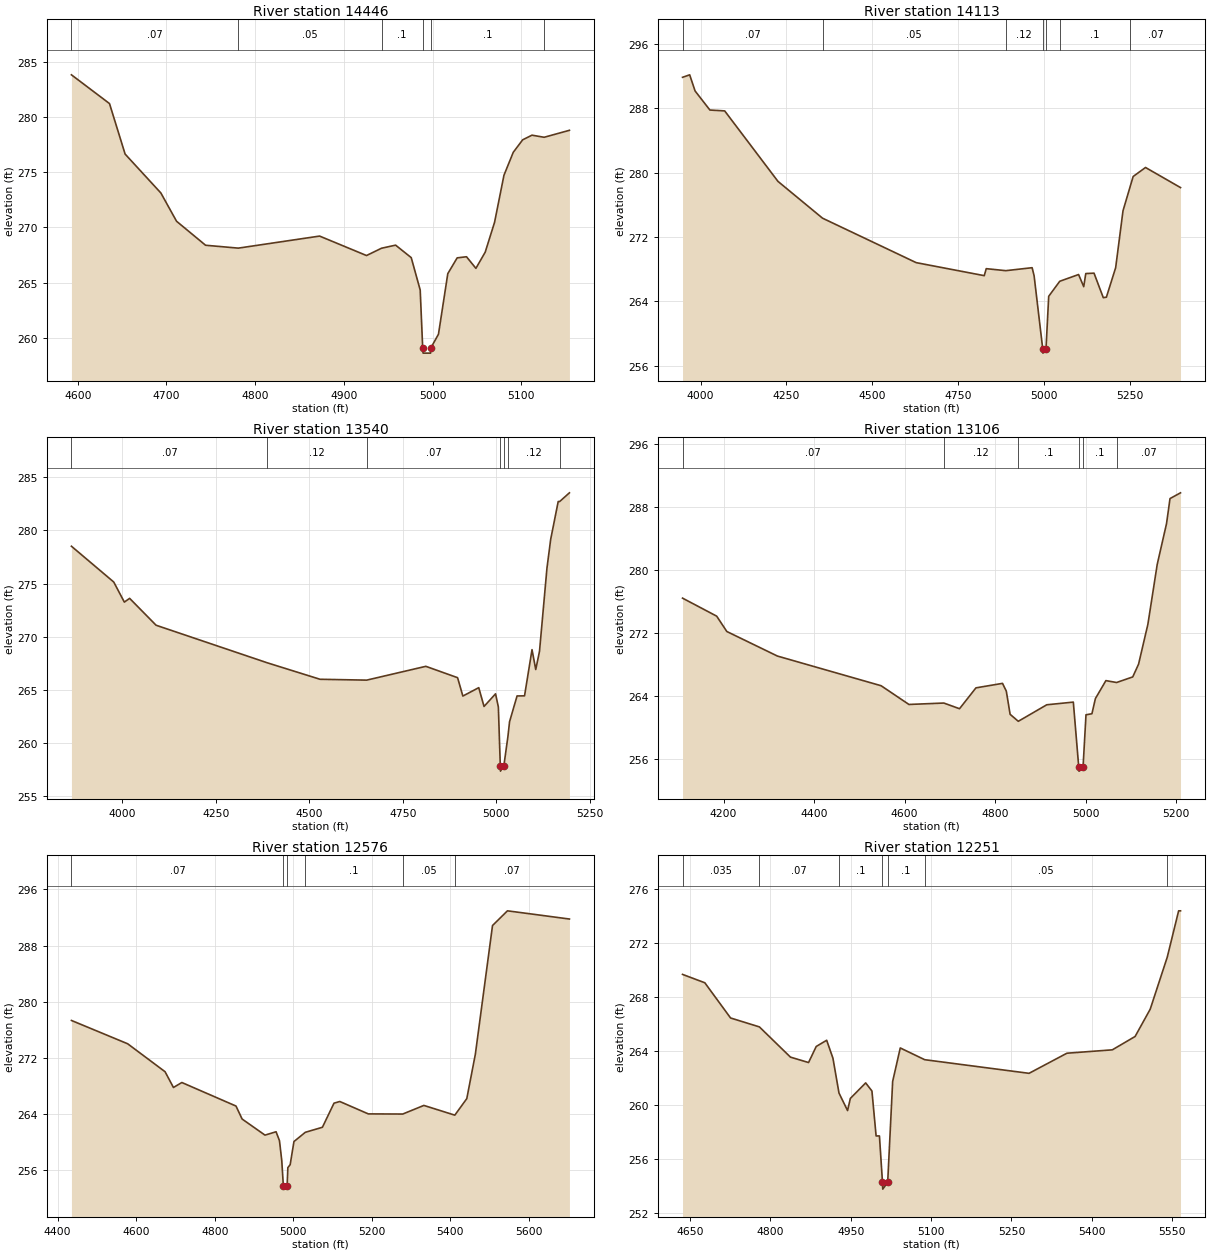
Type RM Length L Ch R = 1 ,14446   ,333,333,333
BEGIN DESCRIPTION:
WEST COTTONWOOD CREEK 29.0
END DESCRIPTION:
XS GIS Cut Line= 3
      2418424.96       13627375.        2418825.       13627425.
      2418975.03     13627475.01
#Sta/Elev= 30
  4592.9   283.8  4635.8   281.2  4653.4  276.63  4693.7  273.11  4711.4  270.55
  4744.1  268.38    4781  268.12  4872.6  269.21  4925.5  267.45  4942.4  268.11
  4958.3  268.39  4975.9  267.26    4986  264.33  4988.8  259.12  4989.3  258.62
  4997.7  258.62  4998.2  259.12  5006.6  260.33  5017.1  265.81  5027.7  267.24
  5038.2  267.34  5048.8  266.29  5059.3  267.76  5069.8  270.45  5080.4  274.71
  5090.9  276.79  5101.5  277.92    5112  278.34  5125.7  278.15  5154.2  278.78
#Mann= 6 ,-1 , 0
  4592.9     .07       0    4781     .05       0  4942.4      .1       0
  4988.8     .05       0  4998.2      .1       0  5125.7     .07       0
Bank Sta=4988.8,4998.2
XS Rating Curve= 0 ,0
Exp/Cntr=0.3,0.1

Type RM Length L Ch R = 1 ,14113   ,573,573,573
BEGIN DESCRIPTION:
WEST COTTONWOOD CREEK 28.0
END DESCRIPTION:
XS GIS Cut Line= 3
      2417911.95     13628250.35      2418814.08     13627731.32
      2419153.95     13627502.68
#Sta/Elev= 30
  3947.4  291.86  3968.2  292.17    3984  290.16  4027.1  287.79  4070.2  287.68
  4225.4  278.91  4355.2  274.33  4627.9   268.8  4826.2  267.18    4832  268.05
  4888.9   267.8  4965.6  268.17  4971.4  267.16  4996.6  258.04  4997.1  257.54
    5006  258.04  5013.9  264.61    5046  266.48  5100.9  267.32  5115.9  265.81
  5121.9  267.44  5145.9  267.49  5172.9  264.44  5181.9   264.5  5208.9  268.17
  5230.3  275.25  5251.2  278.27  5259.9  279.52  5295.9  280.64  5397.8  278.14
#Mann= 7 ,-1 , 0
  3947.4     .07       0  4355.2     .05       0  4888.9     .12       0
  4996.6     .05       0    5006     .12       0    5046      .1       0
  5251.2     .07       0
Bank Sta=4996.6,5006
XS Rating Curve= 0 ,0
Exp/Cntr=0.3,0.1

Type RM Length L Ch R = 1 ,13540   ,434,434,434
BEGIN DESCRIPTION:
WEST COTTONWOOD CREEK 27.0
END DESCRIPTION:
XS GIS Cut Line= 3
      2418374.99     13628675.01        2419175.       13627875.
      2419375.02       13627875.
#Sta/Elev= 30
  3863.9  278.51    3977  275.14  4005.3  273.25  4019.5   273.6  4090.2  271.07
  4387.6  267.53  4528.6  265.98  4653.3   265.9  4811.4   267.2  4896.3  266.13
  4910.4   264.4  4952.9  265.19    4967  263.42  4997.8  264.61  5005.3  263.37
  5010.5  257.83    5011  257.33    5020  257.83  5030.8  260.57  5035.3  261.99
  5055.3  264.41  5075.3  264.42  5095.3  268.77  5105.3   266.9  5115.3  268.61
  5135.3  276.47  5145.3  279.18  5165.3  282.72  5169.2  282.72  5195.3  283.54
#Mann= 7 ,-1 , 0
  3863.9     .07       0  4387.6     .12       0  4653.3     .07       0
  5010.5     .05       0    5020     .07       0  5030.8     .12       0
  5169.2     .07       0
Bank Sta=5010.5,5020
XS Rating Curve= 0 ,0
Exp/Cntr=0.3,0.1

Type RM Length L Ch R = 1 ,13106   ,530,530,530
BEGIN DESCRIPTION:
WEST COTTONWOOD CREEK 26.0
END DESCRIPTION:
XS GIS Cut Line= 3
      2418474.96     13628675.02        2419275.       13628275.
      2419474.97     13628225.01
#Sta/Elev= 30
  4109.3  276.41  4184.8  274.12  4207.2  272.17    4319  269.05  4548.2  265.28
  4609.7   262.9  4686.8  263.08  4721.5  262.36  4757.8  265.01  4816.5  265.58
  4824.9  264.59  4833.3  261.65  4851.4  260.76  4914.3  262.86    4973   263.2
    4985  254.93  4985.5  254.43  4994.5  254.93    5001  261.59  5014.1  261.72
  5021.8  263.65    5045  265.93  5068.6  265.69  5104.3   266.4  5117.2  268.02
  5137.8  273.09  5158.4  280.69    5179  285.88  5186.7  289.06  5209.9  289.79
#Mann= 6 ,-1 , 0
  4109.3     .07       0  4686.8     .12       0  4851.4      .1       0
    4985     .05       0  4994.5      .1       0  5068.6     .07       0
Bank Sta=4985,4994.5
XS Rating Curve= 0 ,0
Exp/Cntr=0.3,0.1

Type RM Length L Ch R = 1 ,12576   ,325,325,325
BEGIN DESCRIPTION:
WEST COTTONWOOD CREEK 25.0
END DESCRIPTION:
XS GIS Cut Line= 3
      2418628.73     13628954.74      2419172.46     13628627.26
      2419728.55      13628324.5
#Sta/Elev= 30
  4435.2   277.3  4578.4  273.97  4673.6  269.98  4694.9  267.73  4716.3  268.44
  4854.2  265.08  4869.7  263.23    4928  260.93  4956.2  261.41  4964.9  260.13
  4970.7   257.3  4974.7  253.72  4975.2  253.22  4984.4  253.72  4986.2  256.29
  4992.1  256.71  5001.7  260.01  5030.6  261.33  5074.2  262.05  5103.7  265.49
  5118.4  265.73    5191  263.96  5278.8  263.94  5332.5  265.17  5411.3  263.78
  5441.8  266.14  5463.6  272.48  5507.3  290.85  5545.3  292.95  5703.1  291.78
#Mann= 6 ,-1 , 0
  4435.2     .07       0  4974.7     .05       0  4984.4     .07       0
  5030.6      .1       0  5278.8     .05       0  5411.3     .07       0
Bank Sta=4974.7,4984.4
XS Rating Curve= 0 ,0
Exp/Cntr=0.3,0.1

Type RM Length L Ch R = 1 ,12251   ,450,450,450
BEGIN DESCRIPTION:
WEST COTTONWOOD CREEK 24.0
END DESCRIPTION:
XS GIS Cut Line= 3
      2418924.98     13629025.01        2419275.       13628925.
      2419674.99     13628525.01
#Sta/Elev= 30
    4636  269.69  4677.6  269.07  4725.7  266.46  4779.5   265.8  4837.5  263.56
  4871.3  263.16  4885.6  264.35  4905.1  264.81  4916.8  263.48  4928.1   260.9
  4944.1   259.6  4949.3   260.5  4977.9  261.65  4989.6  261.05  4997.4  257.72
  5003.6  257.72  5009.3  254.28  5009.8  253.78    5019  254.28  5028.3  261.76
  5042.5  264.24  5088.1  263.37  5282.9  262.36  5353.6  263.85  5438.4   264.1
  5480.9  265.09  5509.1  267.11  5540.9  270.96  5562.2   274.4  5565.7   274.4
#Mann= 7 ,-1 , 0
    4636    .035       0  4779.5     .07       0  4928.1      .1       0
  5009.3     .05       0    5019      .1       0  5088.1     .05       0
  5540.9     .07       0
Bank Sta=5009.3,5019
XS Rating Curve= 0 ,0
Exp/Cntr=0.3,0.1

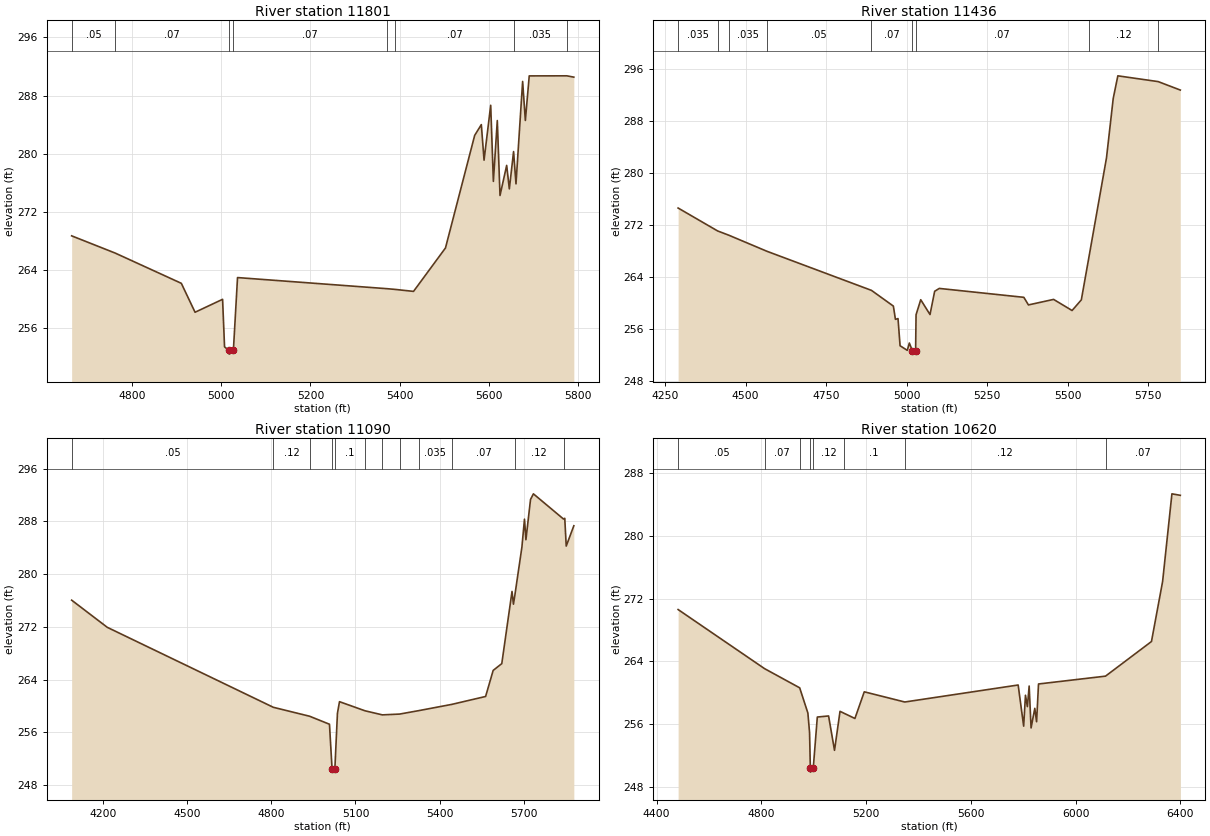
Type RM Length L Ch R = 1 ,11801   ,365,365,365
BEGIN DESCRIPTION:
WEST COTTONWOOD CREEK 23.0
END DESCRIPTION:
XS GIS Cut Line= 3
      2419125.03     13629474.98        2419425.       13629325.
      2420074.96     13628875.03
#Sta/Elev= 30
  4664.6   268.7  4762.2  266.33  4910.5  262.17  4941.3  258.19    5003  259.97
  5007.4  253.43  5017.3  252.93  5017.8  252.43  5027.2  252.93  5036.5  262.96
  5371.9  261.43  5390.1  261.33  5431.1  261.06  5502.7  267.03  5568.2  282.52
  5583.1     284  5589.2  279.11  5604.1  286.66  5610.1  276.19  5618.9  284.56
    5625  274.25  5639.9  278.39  5645.9  275.16  5655.4  280.29  5660.8  275.85
  5675.7  289.94  5681.8  284.57  5690.5   290.7  5774.7  290.71  5790.5  290.53
#Mann= 8 ,-1 , 0
  4664.6     .05       0  4762.2     .07       0  5017.3     .05       0
  5027.2     .07       0  5371.9     .05       0  5390.1     .07       0
  5655.4    .035       0  5774.7     .07       0
Bank Sta=5017.3,5027.2
XS Rating Curve= 0 ,0
Exp/Cntr=0.3,0.1

Type RM Length L Ch R = 1 ,11436   ,346,346,346
BEGIN DESCRIPTION:
H21620
END DESCRIPTION:
XS GIS Cut Line= 3
      2418968.59     13630066.92      2419666.77     13629510.85
       2420092.3     13628998.99
#Sta/Elev= 30
  4290.7  274.58  4413.4  271.05  4448.4  270.39    4566  267.93  4890.6  261.91
  4958.6  259.49    4965  257.45    4973  257.57  4979.4  253.39  5001.8  252.68
  5008.2  253.81  5017.7   252.6  5018.2   252.1  5027.6   252.6    5029  258.16
  5043.5  260.47  5072.3  258.19  5086.7  261.77  5101.1  262.21  5363.4  260.84
  5377.7  259.67  5455.8  260.52  5513.1  258.81  5541.8  260.45  5564.9  266.89
  5619.9   282.3  5640.7  291.42  5655.1  294.92  5780.3  294.03  5848.9  292.73
#Mann= 9 ,-1 , 0
  4290.7    .035       0  4413.4     .05       0  4448.4    .035       0
    4566     .05       0  4890.6     .07       0  5017.7     .05       0
  5027.6     .07       0  5564.9     .12       0  5780.3     .07       0
Bank Sta=5017.7,5027.6
XS Rating Curve= 0 ,0
Exp/Cntr=0.3,0.1

Type RM Length L Ch R = 1 ,11090   ,470,470,470
BEGIN DESCRIPTION:
H21619
END DESCRIPTION:
XS GIS Cut Line= 4
      2419123.06     13630351.16      2419623.52     13629980.45
      2420086.94     13629467.59      2420185.81     13629004.15
#Sta/Elev= 30
  4089.6  276.05  4216.5  271.93  4807.5  259.81  4936.9  258.45  5007.5  257.24
  5016.7  250.48  5017.2  249.98  5026.7  250.48  5035.9  258.91  5043.2  260.66
  5133.9  259.28  5195.7  258.66  5257.2  258.78  5325.1   259.3    5443  260.25
  5563.4  261.45  5590.3   265.4    5621  266.43  5657.4  277.37  5662.5  275.44
  5667.5  276.79  5692.6  284.09  5701.8  288.33  5706.9  285.21  5723.3  291.31
  5733.5  292.17  5840.7  288.35  5845.2  288.46  5850.4  284.25  5877.5  287.33
#Mann= 12 ,-1 , 0
  4089.6     .05       0  4807.5     .12       0  4936.9      .1       0
  5016.7     .05       0  5026.7      .1       0  5133.9     .07       0
  5195.7    .035       0  5257.2     .07       0  5325.1    .035       0
    5443     .07       0  5667.5     .12       0  5840.7     .07       0
Bank Sta=5016.7,5026.7
XS Rating Curve= 0 ,0
Exp/Cntr=0.3,0.1

Type RM Length L Ch R = 1 ,10620   ,646,646,646
BEGIN DESCRIPTION:
H21618
END DESCRIPTION:
XS GIS Cut Line= 3
      2419611.17      13630579.8      2419994.26     13630017.52
       2420896.4     13629170.99
#Sta/Elev= 30
  4482.3   270.6  4812.3  263.06  4946.5  260.61  4977.8  257.39  4984.2   254.9
  4987.2  250.35  4987.7  249.85  4998.3  250.35  5013.8  256.88  5056.8  257.02
  5079.5  252.63  5100.5  257.61  5114.1  257.39  5157.4   256.7  5193.1   260.1
  5347.8   258.8  5780.7  260.97  5801.7  255.72  5808.6  259.66  5815.9  258.21
  5822.7  260.84    5830  255.49  5844.2  257.99  5851.1  256.28  5858.4   261.1
  6114.2   262.1  6289.7  266.52  6332.2  274.17  6367.8  285.37  6399.8  285.18
#Mann= 8 ,-1 , 0
  4482.3     .05       0  4812.3     .07       0  4946.5     .12       0
  4987.2     .05       0  4998.3     .12       0  5114.1      .1       0
  5347.8     .12       0  6114.2     .07       0
Bank Sta=4987.2,4998.3
XS Rating Curve= 0 ,0
Exp/Cntr=0.3,0.1