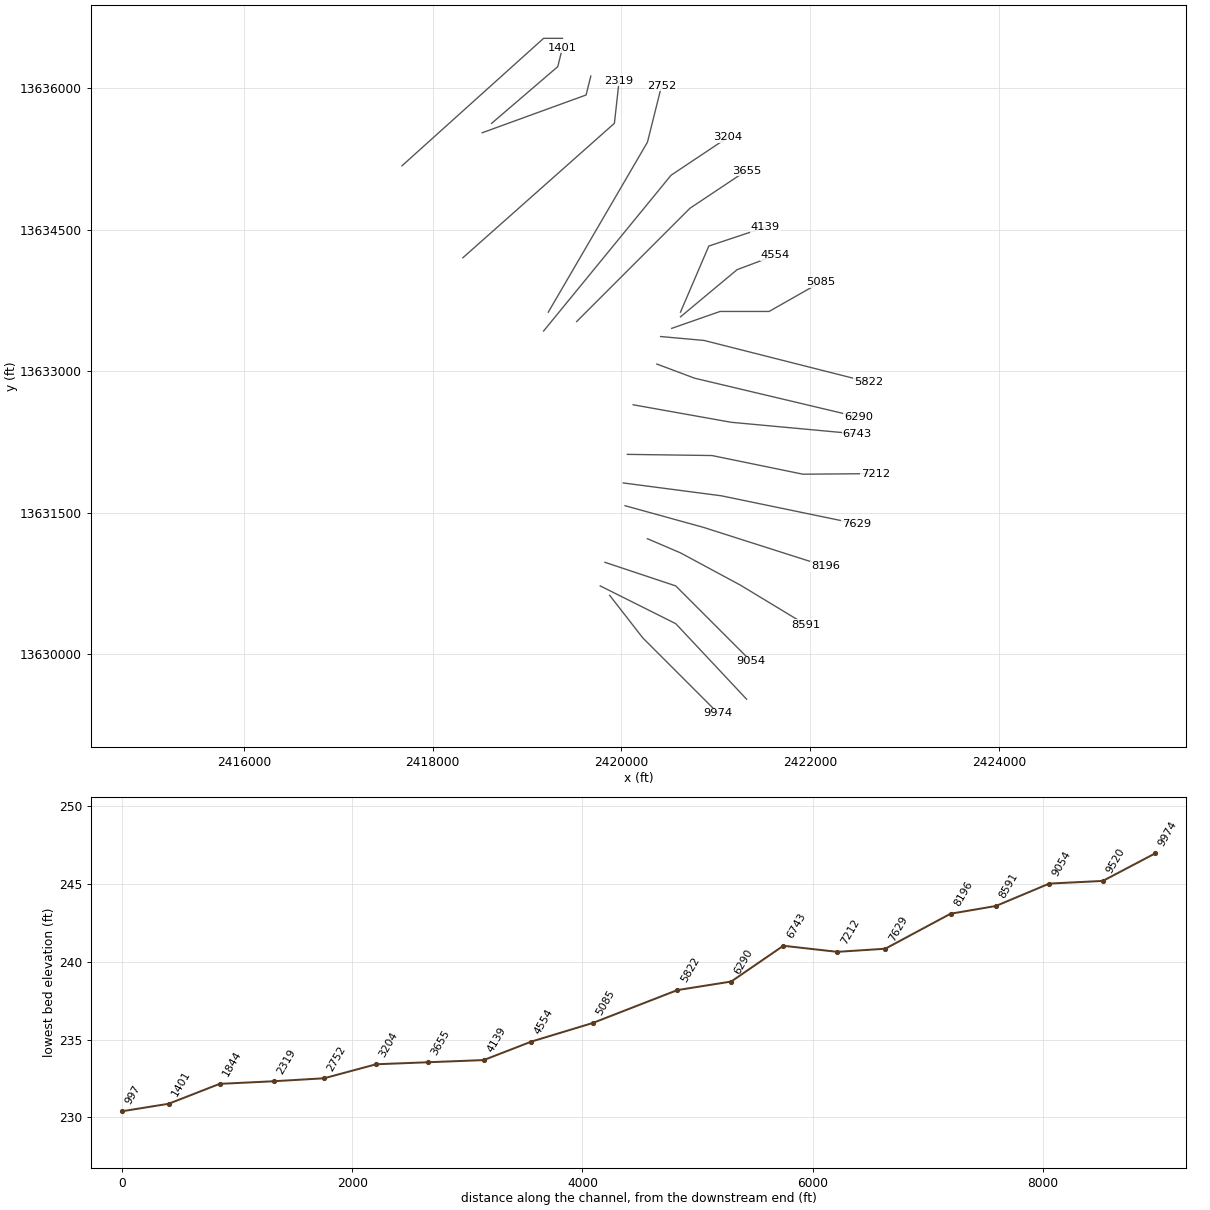
HEC-RAS study WEST COTTONWOOD CREEK.prj: WEST COTTONWOOD CREEK Base Level Engineering

--- WEST COTTONWOOD CREEK.g01 (geometry) --- (continued)

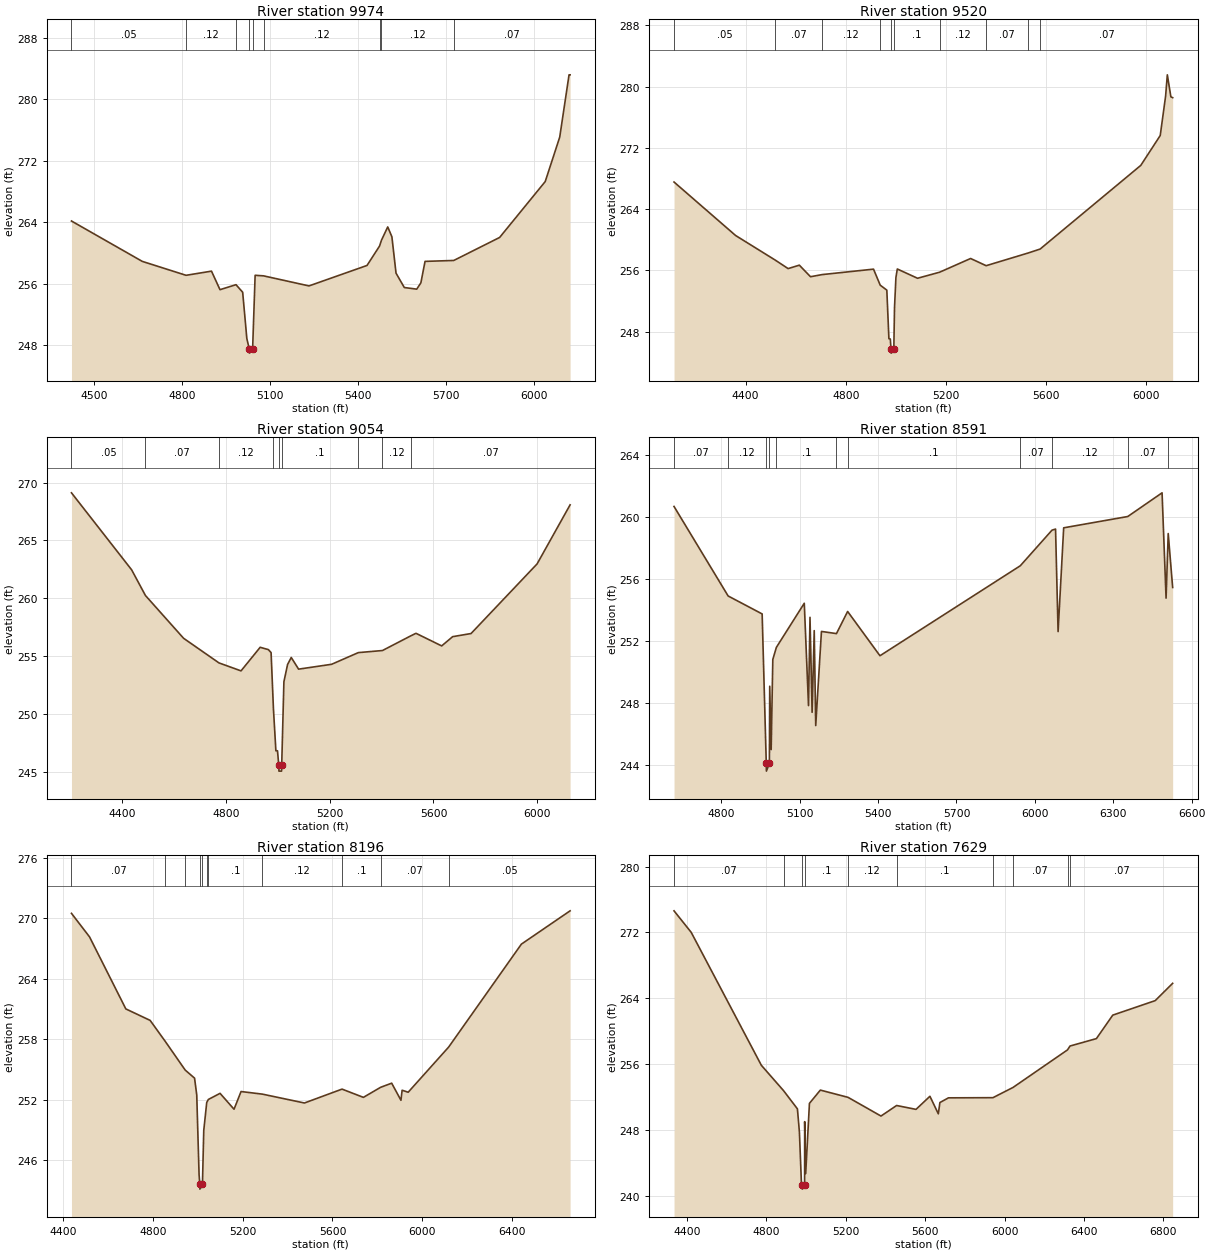
Type RM Length L Ch R = 1 ,9974    ,454,454,454
BEGIN DESCRIPTION:
WEST COTTONWOOD CREEK 20.0
END DESCRIPTION:
XS GIS Cut Line= 3
        2419875.       13630625.        2420225.       13630175.
      2421025.02     13629374.98
#Sta/Elev= 30
  4422.7  264.16  4664.3  258.91  4813.8   257.1  4900.5  257.64  4929.5  255.23
  4984.1  255.88  5006.9   254.9  5021.1  248.88  5029.7  247.48  5030.2  246.98
  5040.8  247.48  5049.4   257.1    5078  257.03  5233.2  255.72  5431.2  258.38
  5473.9   260.9  5480.6  261.67  5501.9  263.39  5516.1  262.11  5530.2  257.38
  5558.5  255.51  5600.9   255.3    5615  256.12  5629.2  258.91  5727.2  259.03
  5883.7  262.02  6039.3  269.29  6088.8  275.07  6120.6  283.17  6124.2  283.17
#Mann= 9 ,-1 , 0
  4422.7     .05       0  4813.8     .12       0  4984.1      .1       0
  5029.7     .05       0  5040.8      .1       0    5078     .12       0
  5473.9     .07       0  5480.6     .12       0  5727.2     .07       0
Bank Sta=5029.7,5040.8
XS Rating Curve= 0 ,0
Exp/Cntr=0.3,0.1

Type RM Length L Ch R = 1 ,9520    ,466,466,466
BEGIN DESCRIPTION:
WEST COTTONWOOD CREEK 19.0
END DESCRIPTION:
XS GIS Cut Line= 3
      2419775.04     13630724.98        2420575.       13630325.
      2421325.02     13629524.98
#Sta/Elev= 30
  4114.4  267.54  4360.3  260.56  4518.6  257.35    4570  256.24  4614.7  256.69
  4659.4  255.18    4706  255.46    4911  256.17  4937.7  254.08  4964.1  253.43
  4972.4   247.1    4978  247.05  4980.9  245.71  4981.4  245.21    4992  245.71
  4994.8  251.16  5000.4  255.08    5006  256.19  5086.7  254.98  5174.8  255.77
  5298.7  257.56  5360.7  256.62  5528.7  258.28  5576.1  258.79  5978.1  269.71
  6055.8  273.61  6077.3  278.76  6084.1  281.53  6098.3  278.66  6105.4  278.55
#Mann= 10 ,-1 , 0
  4114.4     .05       0  4518.6     .07       0    4706     .12       0
  4937.7      .1       0  4980.9     .05       0    4992      .1       0
  5174.8     .12       0  5360.7     .07       0  5528.7     .12       0
  5576.1     .07       0
Bank Sta=4980.9,4992
XS Rating Curve= 0 ,0
Exp/Cntr=0.3,0.1

Type RM Length L Ch R = 1 ,9054    ,463,463,463
BEGIN DESCRIPTION:
WEST COTTONWOOD CREEK 18.0
END DESCRIPTION:
XS GIS Cut Line= 3
      2419825.05     13630974.98        2420575.       13630725.
      2421375.01     13629924.99
#Sta/Elev= 30
  4204.8  269.11  4436.7  262.45  4489.9  260.23  4636.9  256.53  4773.3   254.4
  4858.3  253.71  4932.1  255.75  4963.7  255.55  4974.2  255.29  4983.3  250.41
  4992.7   246.8  4998.9   246.8  5003.9  245.54  5004.4  245.04  5014.6  245.04
  5015.1  245.54  5023.6  252.77  5037.7  254.26  5051.9  254.87  5080.2  253.86
  5207.5  254.28  5310.4  255.29  5403.5  255.47  5511.8  256.73  5532.7  256.96
  5631.7  255.87  5674.1  256.67  5744.9  256.94  5999.4  262.96  6126.7  268.07
#Mann= 9 ,-1 , 0
  4204.8     .05       0  4489.9     .07       0  4773.3     .12       0
  4983.3      .1       0  5003.9     .05       0  5015.1      .1       0
  5310.4     .07       0  5403.5     .12       0  5511.8     .07       0
Bank Sta=5003.9,5015.1
XS Rating Curve= 0 ,0
Exp/Cntr=0.3,0.1

Type RM Length L Ch R = 1 ,8591    ,395,395,395
BEGIN DESCRIPTION:
WEST COTTONWOOD CREEK 17.0
END DESCRIPTION:
XS GIS Cut Line= 4
      2420275.05     13631224.98        2420625.       13631075.
      2421260.84     13630732.66      2421949.62     13630315.77
#Sta/Elev= 30
  4619.3  260.69  4826.3  254.91  4956.5  253.75  4972.3   244.1  4972.8   243.6
  4984.2   244.1  4985.5  249.08    4991  244.99  4997.3  250.81  5010.9  251.59
  5117.7  254.44  5133.9  247.83  5139.6  253.53  5147.7   247.4  5155.8  252.67
  5161.5  246.54  5183.4  252.62  5240.9  252.48  5283.6  253.91  5407.3  251.05
  5944.3  256.86  6065.7  259.16  6079.2  259.23  6088.9  252.61  6110.3  259.31
  6355.5  260.04  6486.8  261.57  6502.1  254.77  6510.3  258.94  6527.3  255.46
#Mann= 11 ,-1 , 0
  4619.3     .07       0  4826.3     .12       0  4972.3     .05       0
  4984.2     .12       0  5010.9      .1       0  5240.9     .12       0
  5283.6      .1       0  5944.3     .07       0  6065.7     .12       0
  6355.5     .07       0  6510.3     .12       0
Bank Sta=4972.3,4984.2
XS Rating Curve= 0 ,0
Exp/Cntr=0.3,0.1

Type RM Length L Ch R = 1 ,8196    ,567,567,567
BEGIN DESCRIPTION:
H21617
END DESCRIPTION:
XS GIS Cut Line= 3
      2420037.47     13631574.62      2420865.49     13631345.99
      2422161.52     13630932.49
#Sta/Elev= 30
  4438.4  270.51  4518.8  268.17  4680.4  261.01  4788.6  259.87  4856.6  257.76
  4944.7  254.93  4986.3  254.13    4996  252.46  5006.4  244.53  5009.5   243.6
    5010   243.1  5021.4   243.6  5027.2  248.93  5040.4  251.71  5047.6  252.01
  5099.8  252.62    5162  251.04  5193.2   252.8  5288.5  252.54  5475.3  251.66
  5642.6  253.04  5737.8  252.22  5814.5  253.22  5863.7  253.63  5904.9  251.93
  5910.1  252.93  5937.1  252.73  6117.3  257.22    6441  267.45  6657.8  270.76
#Mann= 11 ,-1 , 0
  4438.4     .07       0  4856.6     .12       0  4944.7      .1       0
  5009.5     .05       0  5021.4      .1       0  5040.4     .12       0
  5047.6      .1       0  5288.5     .12       0  5642.6      .1       0
  5814.5     .07       0  6117.3     .05       0
Bank Sta=5009.5,5021.4
XS Rating Curve= 0 ,0
Exp/Cntr=0.3,0.1

Type RM Length L Ch R = 1 ,7629    ,417,417,417
BEGIN DESCRIPTION:
H21616
END DESCRIPTION:
XS GIS Cut Line= 3
        2420019.     13631815.58      2421057.03     13631679.65
      2422490.28     13631383.12
#Sta/Elev= 30
  4335.8  274.63  4422.5  272.01  4775.5  255.88  4887.7  252.79  4957.1  250.59
  4967.1  247.77  4977.2  241.58  4981.4  241.35  4981.9  240.85  4993.3  241.35
  4993.6  249.04  4998.7  242.73  5017.6  251.26  5072.5  252.87    5212  251.99
  5377.8  249.72  5456.5     251  5554.2  250.53  5624.2  252.12  5666.5  249.99
  5674.4  251.36  5717.6  251.93  5941.4  251.95  6042.5  253.19  6316.9  257.75
  6329.6  258.22  6462.4  259.12  6544.8  261.97  6758.5  263.73  6846.3  265.83
#Mann= 10 ,-1 , 0
  4335.8     .07       0  4887.7      .1       0  4981.4     .05       0
  4993.3      .1       0    5212     .12       0  5456.5      .1       0
  5941.4     .12       0  6042.5     .07       0  6316.9     .05       0
  6329.6     .07       0
Bank Sta=4981.4,4993.3
XS Rating Curve= 0 ,0
Exp/Cntr=0.3,0.1

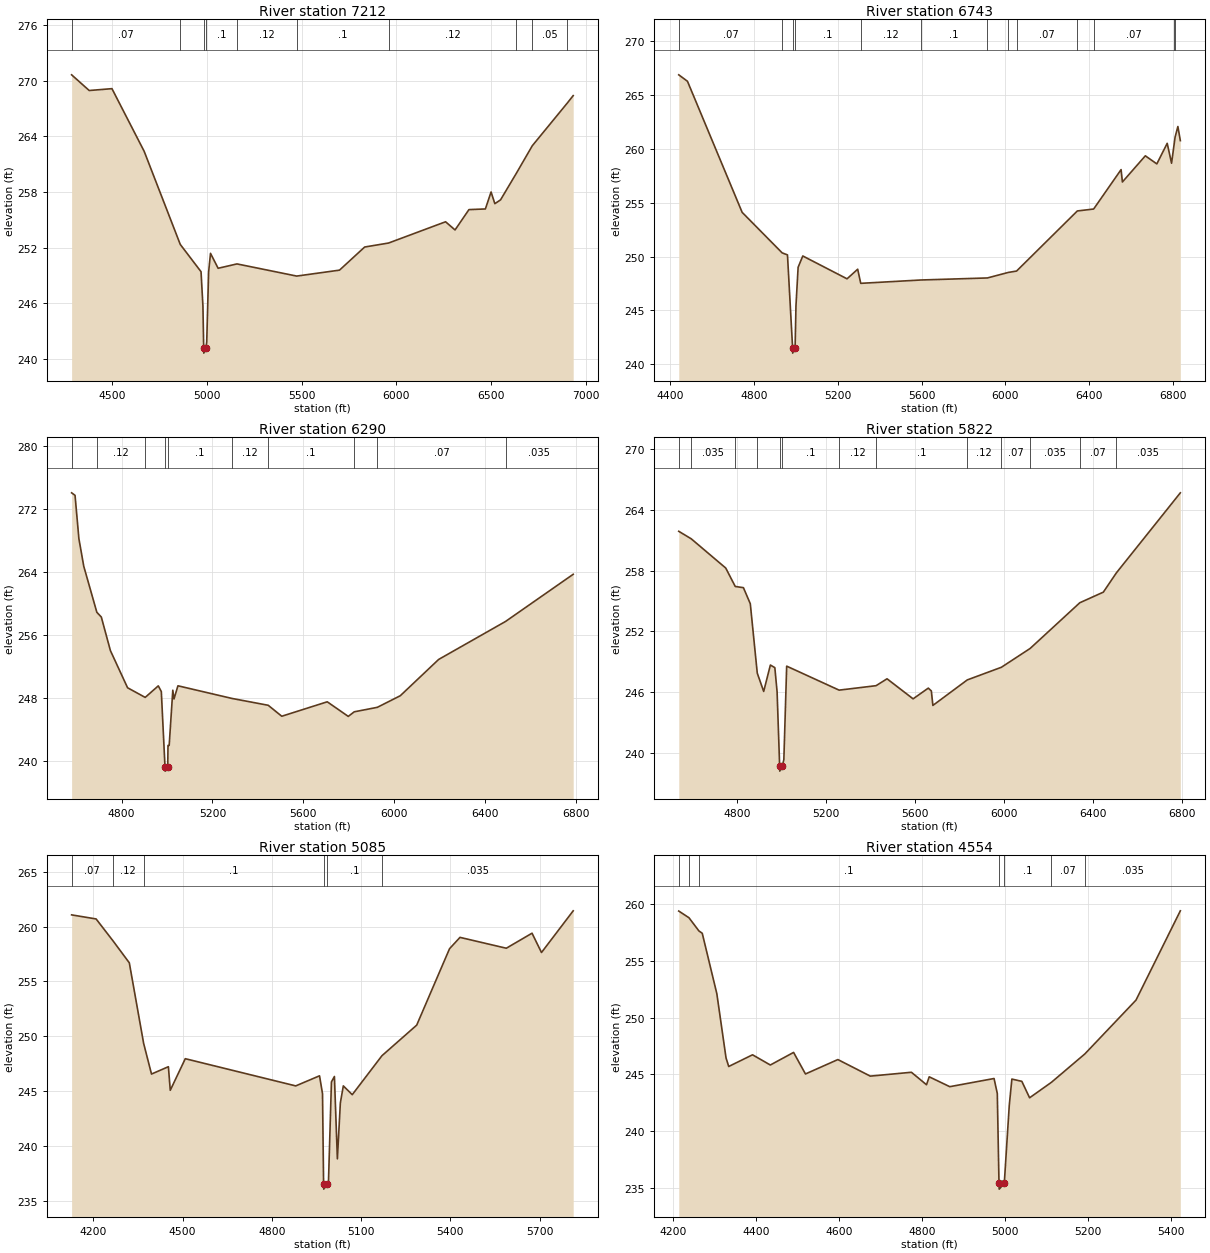
Type RM Length L Ch R = 1 ,7212    ,469,469,469
BEGIN DESCRIPTION:
H21615
END DESCRIPTION:
XS GIS Cut Line= 4
      2420062.22     13632118.35      2420958.17       13632106.
      2421922.08     13631908.27      2422688.24     13631914.45
#Sta/Elev= 30
  4287.1  270.63  4379.9  268.94  4499.9  269.14  4669.9  262.39  4860.3  252.36
  4969.9  249.42  4979.9  245.71  4983.9  241.15  4984.4  240.65  4995.9  241.15
  4999.9  241.87  5009.9  249.39  5019.9   251.4    5060  249.79  5159.7  250.26
  5474.7  248.95  5700.5  249.59  5833.2  252.08  5959.3  252.51    6260   254.8
    6310  253.92  6383.3  256.11    6470  256.18    6500  258.01    6520  256.75
    6550  257.16  6633.9  260.04  6717.5  262.99  6901.4  267.57  6933.3  268.39
#Mann= 10 ,-1 , 0
  4287.1     .07       0  4860.3      .1       0  4983.9     .05       0
  4995.9      .1       0  5159.7     .12       0  5474.7      .1       0
  5959.3     .12       0  6633.9     .07       0  6717.5     .05       0
  6901.4     .07       0
Bank Sta=4983.9,4995.9
XS Rating Curve= 0 ,0
Exp/Cntr=0.3,0.1

Type RM Length L Ch R = 1 ,6743    ,453,453,453
BEGIN DESCRIPTION:
H21614
END DESCRIPTION:
XS GIS Cut Line= 3
      2420124.02     13632643.56      2421162.07      13632458.2
      2422496.69     13632334.62
#Sta/Elev= 30
  4440.7  266.88  4482.3  266.28  4743.4  254.11  4934.3  250.35  4959.8  250.16
  4984.2  241.54  4984.7  241.04  4996.2  241.54  5000.4  245.46  5010.6  249.01
  5032.9  250.06  5244.2  247.94    5295  248.83  5309.6  247.52  5596.3  247.83
  5914.5  248.02  6013.6  248.53  6053.6  248.66  6343.7  254.24  6421.6  254.42
  6552.6  258.08  6558.9  256.93  6668.4  259.36  6723.3  258.61  6772.8  260.52
  6793.6  258.67  6807.3  260.64  6810.5   261.1  6823.8  262.08  6835.5  260.77
#Mann= 13 ,-1 , 0
  4440.7     .07       0  4934.3      .1       0  4984.2     .05       0
  4996.2      .1       0  5309.6     .12       0  5596.3      .1       0
  5914.5     .07       0  6013.6     .12       0  6053.6     .07       0
  6343.7    .035       0  6421.6     .07       0  6807.3    .035       0
  6810.5     .07       0
Bank Sta=4984.2,4996.2
XS Rating Curve= 0 ,0
Exp/Cntr=0.3,0.1

Type RM Length L Ch R = 1 ,6290    ,468,468,468
BEGIN DESCRIPTION:
WEST COTTONWOOD CREEK 12.0
END DESCRIPTION:
XS GIS Cut Line= 3
      2420375.03     13633074.99        2420775.       13632925.
      2422509.04     13632513.81
#Sta/Elev= 30
  4579.5  274.03  4594.6  273.71  4611.5  268.23  4632.9  264.73  4690.6  258.88
  4710.3  258.28  4750.4  254.02    4826  249.31  4903.6  248.09  4961.3  249.55
  4974.6  248.83  4990.9  239.24  4991.4  238.74  5002.9  239.24    5004     242
  5009.2     242  5025.2     249  5030.4  247.89  5047.8  249.56  5286.9  247.95
  5445.4  247.09  5505.1   245.7  5705.5  247.53    5798  245.68  5824.3  246.26
  5926.1  246.83  6027.2   248.3  6196.1   252.9  6490.9  257.72  6788.8   263.7
#Mann= 10 ,-1 , 0
  4579.5     .07       0  4690.6     .12       0  4903.6      .1       0
  4990.9     .05       0  5002.9      .1       0  5286.9     .12       0
  5445.4      .1       0  5824.3     .12       0  5926.1     .07       0
  6490.9    .035       0
Bank Sta=4990.9,5002.9
XS Rating Curve= 0 ,0
Exp/Cntr=0.3,0.1

Type RM Length L Ch R = 1 ,5822    ,737,737,737
BEGIN DESCRIPTION:
WEST COTTONWOOD CREEK 11.0
END DESCRIPTION:
XS GIS Cut Line= 3
      2420414.43      13633366.5        2420875.       13633325.
      2422614.15     13632884.53
#Sta/Elev= 30
  4537.6  261.88  4593.6  261.14    4749  258.25  4791.7  256.43  4828.6  256.31
  4859.5  254.72  4890.8  247.87  4919.7  246.06  4949.8  248.67  4969.9  248.41
    4980  246.02  4991.5  238.69    4992  238.19  5003.6  238.69  5010.4  239.33
  5023.1  248.56    5259  246.19  5425.3  246.63  5474.6  247.31  5591.9  245.33
  5660.2  246.39  5673.9  246.11  5680.9  244.68  5835.6   247.2  5989.2  248.45
  6118.6  250.31  6341.7  254.82  6447.7  255.87  6506.6  257.78  6794.1  265.68
#Mann= 13 ,-1 , 0
  4537.6     .07       0  4593.6    .035       0  4791.7     .07       0
  4890.8      .1       0  4991.5     .05       0  5003.6      .1       0
    5259     .12       0  5425.3      .1       0  5835.6     .12       0
  5989.2     .07       0  6118.6    .035       0  6341.7     .07       0
  6506.6    .035       0
Bank Sta=4991.5,5003.6
XS Rating Curve= 0 ,0
Exp/Cntr=0.3,0.1

Type RM Length L Ch R = 1 ,5085    ,531,531,531
BEGIN DESCRIPTION:
H21613
END DESCRIPTION:
XS GIS Cut Line= 4
      2420531.82       13633453.      2421044.67     13633632.19
       2421563.7     13633632.19      2422106.43     13633940.56
#Sta/Elev= 30
  4126.6  261.07  4208.9   260.7  4265.6  258.71  4320.6   256.7  4368.8  249.35
  4395.2  246.56    4452  247.23  4458.3  245.08  4508.8  247.96  4880.2  245.48
  4960.2   246.4  4970.2  244.77  4973.8  236.57  4974.3  236.07  4986.5  236.57
  4990.2  236.68  5000.2  245.84  5010.2  246.34  5020.2  238.83  5030.2  243.93
  5040.2  245.48  5070.2  244.68    5170  248.23  5286.9  251.02  5397.4  257.99
  5432.5  259.02  5588.2  258.03  5674.7   259.4  5706.5  257.64  5813.1  261.44
#Mann= 6 ,-1 , 0
  4126.6     .07       0  4265.6     .12       0  4368.8      .1       0
  4973.8     .05       0  4986.5      .1       0    5170    .035       0
Bank Sta=4973.8,4986.5
XS Rating Curve= 0 ,0
Exp/Cntr=0.3,0.1

Type RM Length L Ch R = 1 ,4554    ,415,415,415
BEGIN DESCRIPTION:
WEST COTTONWOOD CREEK 10.0
END DESCRIPTION:
XS GIS Cut Line= 3
      2420625.02     13633575.02        2421225.       13634075.
        2421625.       13634225.
#Sta/Elev= 30
  4214.4  259.39    4239   258.8  4262.9  257.64    4271  257.43  4306.1  252.11
  4328.3  246.44  4334.8  245.69  4392.1  246.72    4435  245.82    4491  246.93
  4519.6  245.03  4597.7   246.3  4675.8  244.84  4774.8  245.18  4811.2  244.08
  4817.7  244.78  4867.2  243.91  4973.9  244.63  4981.7  243.31  4985.8  235.38
  4986.3  234.88  4998.5  235.38  5010.5  242.24  5016.8  244.58  5040.8  244.38
  5059.5  242.93  5111.9  244.29  5192.7   246.8  5315.8  251.54  5422.6  259.41
#Mann= 7 ,-1 , 0
  4214.4     .07       0    4239     .12       0  4262.9      .1       0
  4985.8     .05       0  4998.5      .1       0  5111.9     .07       0
  5192.7    .035       0
Bank Sta=4985.8,4998.5
XS Rating Curve= 0 ,0
Exp/Cntr=0.3,0.1

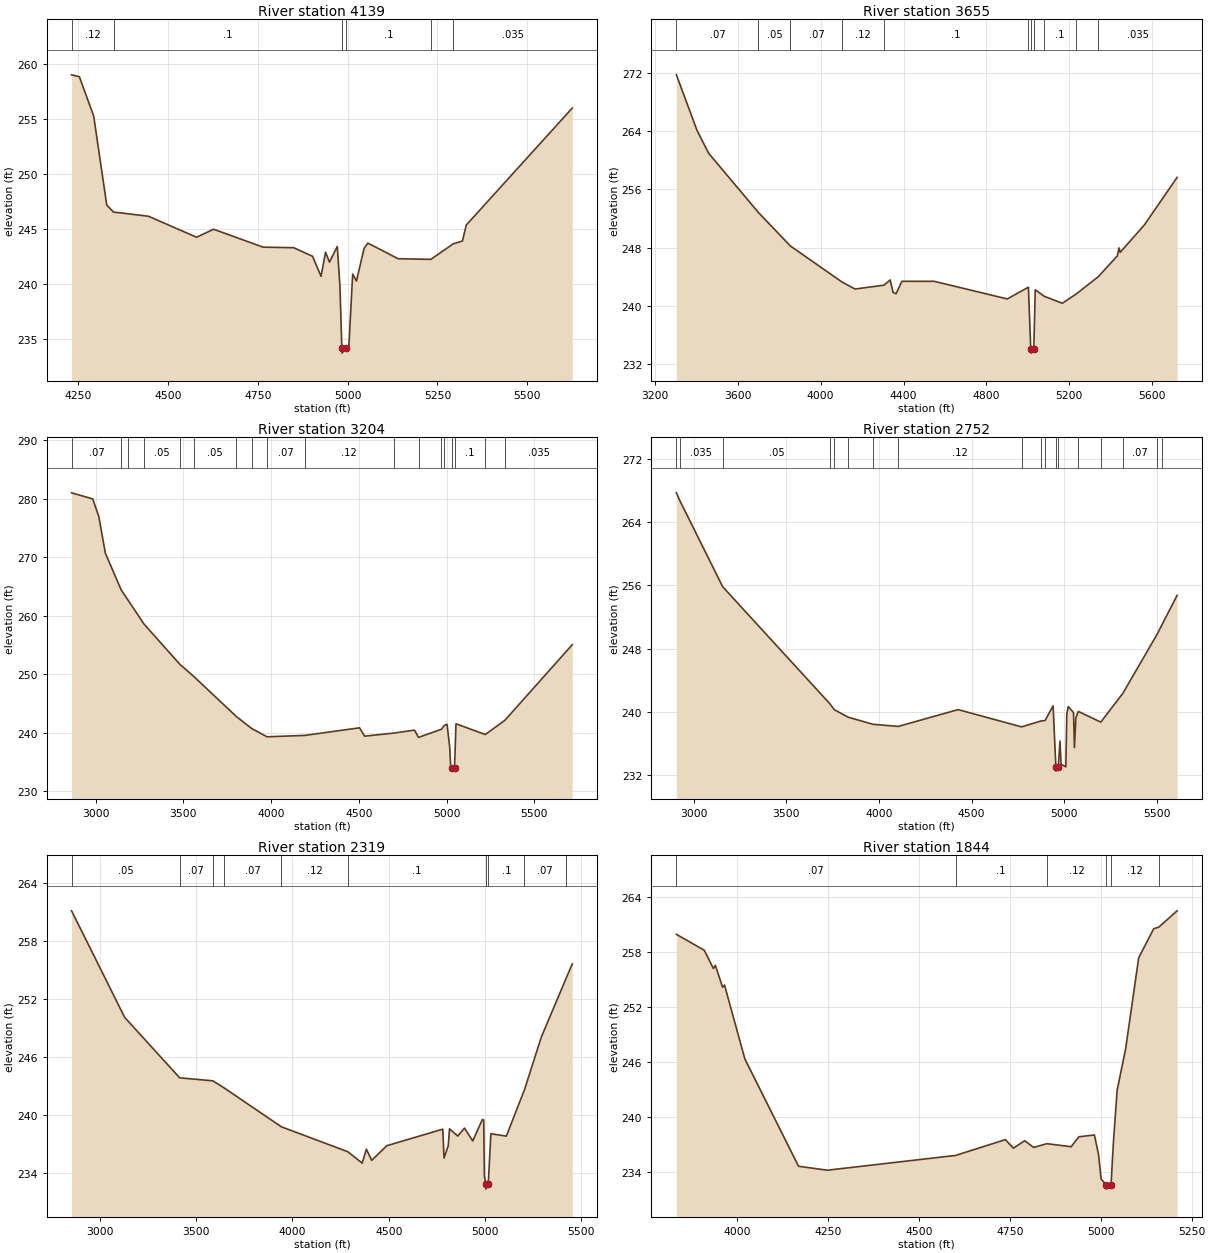
Type RM Length L Ch R = 1 ,4139    ,484,484,484
BEGIN DESCRIPTION:
WEST COTTONWOOD CREEK 9.0
END DESCRIPTION:
XS GIS Cut Line= 3
        2420625.     13633625.01        2420925.       13634325.
      2421524.98     13634524.99
#Sta/Elev= 30
  4231.3  258.98    4253  258.81  4292.9  255.23  4329.2  247.15  4348.1  246.51
  4445.3  246.13  4579.4  244.22  4626.6  244.95  4764.4  243.32  4849.6  243.27
  4902.2  242.49  4925.8  240.67  4938.5  242.86  4949.3  241.96  4971.1  243.38
  4978.4   239.8  4983.7  234.19  4984.2  233.69  4996.5  234.19  5003.4  234.38
  5013.9  240.87  5024.5  240.24  5045.6   243.2  5056.1  243.69  5140.4  242.27
  5231.6  242.21  5293.7  243.62  5319.6  243.88  5330.2  245.33  5625.3  255.96
#Mann= 6 ,-1 , 0
  4231.3     .12       0  4348.1      .1       0  4983.7     .05       0
  4996.5      .1       0  5231.6     .07       0  5293.7    .035       0
Bank Sta=4983.7,4996.5
XS Rating Curve= 0 ,0
Exp/Cntr=0.3,0.1

Type RM Length L Ch R = 1 ,3655    ,451,451,451
BEGIN DESCRIPTION:
WEST COTTONWOOD CREEK 8.0
END DESCRIPTION:
XS GIS Cut Line= 3
      2419524.98     13633524.98        2420725.       13634725.
        2421325.       13635125.
#Sta/Elev= 30
  3303.2  271.71  3402.2  264.13  3458.8  260.96  3698.7  252.85  3853.8  248.24
  4104.2  243.28  4165.9  242.34  4306.1  242.87  4335.6  243.59  4349.7  241.89
  4363.9  241.69  4392.2   243.4  4547.7   243.4  4901.3  240.98  5001.7  242.57
  5003.3  242.57  5013.8  234.67  5016.4  234.05  5016.9  233.55  5029.2  234.05
  5036.3  242.24  5079.2  241.35    5167  240.39  5233.8  241.65  5340.3  244.02
    5433  246.89  5440.5  247.98  5446.5  247.37  5563.7  251.14  5721.4  257.65
#Mann= 11 ,-1 , 0
  3303.2     .07       0  3698.7     .05       0  3853.8     .07       0
  4104.2     .12       0  4306.1      .1       0  5001.7     .12       0
  5016.4     .05       0  5029.2     .12       0  5079.2      .1       0
  5233.8     .07       0  5340.3    .035       0
Bank Sta=5016.4,5029.2
XS Rating Curve= 0 ,0
Exp/Cntr=0.3,0.1

Type RM Length L Ch R = 1 ,3204    ,452,452,452
BEGIN DESCRIPTION:
WEST COTTONWOOD CREEK 7.0
END DESCRIPTION:
XS GIS Cut Line= 3
      2419174.99     13633424.99        2420525.       13635075.
      2421124.98     13635474.99
#Sta/Elev= 30
  2862.8  281.02  2983.4  279.98  3018.6  276.89  3055.2  270.71  3145.5  264.42
  3184.8  262.66  3275.9  258.56  3479.3  251.71  3558.5  249.63  3802.4  242.74
  3888.1  240.73  3976.3  239.29  4191.4  239.53  4503.7  240.83  4532.4   239.4
  4699.5  239.93  4816.7  240.43  4840.1  239.19  4970.5  240.59  4986.1  241.22
  5002.2  241.43  5017.2   237.6  5023.3  234.04  5031.8  233.92  5032.3  233.42
  5044.7  233.92  5053.3  241.52  5220.1  239.68  5331.4   242.1  5715.8  255.05
#Mann= 18 ,-1 , 0
  2862.8     .07       0  3145.5    .035       0  3184.8     .07       0
  3275.9     .05       0  3479.3     .07       0  3558.5     .05       0
  3802.4     .07       0  3888.1     .12       0  3976.3     .07       0
  4191.4     .12       0  4699.5      .1       0  4840.1     .07       0
  4970.5     .12       0  4986.1      .1       0  5031.8     .05       0
  5044.7      .1       0  5220.1     .07       0  5331.4    .035       0
Bank Sta=5031.8,5044.7
XS Rating Curve= 0 ,0
Exp/Cntr=0.3,0.1

Type RM Length L Ch R = 1 ,2752    ,433,433,433
BEGIN DESCRIPTION:
WEST COTTONWOOD CREEK 6.0
END DESCRIPTION:
XS GIS Cut Line= 3
      2419224.98     13633624.96        2420275.       13635425.
      2420425.01     13636025.02
#Sta/Elev= 30
  2906.9  267.67  2924.7  266.72  3156.7  255.81  3736.7  240.99    3759  240.28
  3834.3  239.33  3968.7  238.43  4104.7  238.17  4427.3  240.29  4769.8  238.11
  4875.6  238.86  4896.6  238.91    4940  240.77    4955  233.02  4955.5  232.52
  4967.9  233.02  4977.2  236.32    4983  233.39  5008.8  233.06    5014  239.71
  5021.7  240.68  5050.1  239.92  5055.2  235.49    5063  239.28  5076.3  240.06
  5197.4  238.71  5316.9  242.36  5499.6  249.73  5529.1  251.07  5609.3  254.72
#Mann= 18 ,-1 , 0
  2906.9     .07       0  2924.7    .035       0  3156.7     .05       0
  3736.7     .07       0    3759     .05       0  3834.3     .07       0
  3968.7    .035       0  4104.7     .12       0  4769.8     .07       0
  4875.6     .12       0  4896.6    .035       0    4955    .035       0
  4967.9    .035       0  5076.3      .1       0  5197.4    .035       0
  5316.9     .07       0  5499.6     .05       0  5529.1     .07       0
Bank Sta=4955,4967.9
XS Rating Curve= 0 ,0
Exp/Cntr=0.3,0.1

Type RM Length L Ch R = 1 ,2319    ,475,475,475
BEGIN DESCRIPTION:
WEST COTTONWOOD CREEK 5.0
END DESCRIPTION:
XS GIS Cut Line= 3
      2418319.75     13634200.64        2419925.       13635625.
        2419975.     13636074.96
#Sta/Elev= 30
  2853.9  261.11  3129.6  250.09  3415.1  243.84    3587  243.53  3643.2  242.83
  3943.3  238.77  4287.4   236.2  4362.3  235.02    4384  236.46  4411.7  235.31
  4490.2  236.82  4780.4  238.53  4787.1  235.54  4808.9  236.82  4815.6  238.57
  4858.2  237.82  4893.3  238.64    4936  237.31  4986.2  239.54  4992.9  239.48
  4996.6  233.71  5003.5  232.83    5004  232.33  5016.5  232.83  5030.2  238.06
  5110.6  237.81  5204.4   242.6  5291.8  248.04  5420.1   254.1  5452.7  255.62
#Mann= 10 ,-1 , 0
  2853.9     .05       0  3415.1     .07       0    3587     .12       0
  3643.2     .07       0  3943.3     .12       0  4287.4      .1       0
  5003.5     .05       0  5016.5      .1       0  5204.4     .07       0
  5420.1     .05       0
Bank Sta=5003.5,5016.5
XS Rating Curve= 0 ,0
Exp/Cntr=0.3,0.1

Type RM Length L Ch R = 1 ,1844    ,443,443,443
BEGIN DESCRIPTION:
WEST COTTONWOOD CREEK 4.0
END DESCRIPTION:
XS GIS Cut Line= 3
      2418525.02     13635525.01        2419625.       13635925.
        2419675.     13636124.99
#Sta/Elev= 30
  3833.3  259.91  3909.8  258.18    3935  256.19  3940.4  256.53  3960.3  254.15
  3965.6  254.39  4021.5  246.34  4169.1  234.65  4248.3  234.22  4600.9  235.83
  4737.7  237.55  4759.7  236.62  4790.9  237.43  4815.5   236.7  4851.8  237.11
  4918.6  236.78  4939.9  237.86  4982.5  238.06  4993.8  235.95  5001.1  233.24
  5015.3  232.66  5015.8  232.16  5028.3  232.66  5034.7  237.19    5045  242.93
  5068.2  247.39  5104.3  257.35  5145.5  260.52  5159.4  260.69  5209.9  262.47
#Mann= 6 ,-1 , 0
  3833.3     .07       0  4600.9      .1       0  4851.8     .12       0
  5015.3     .05       0  5028.3     .12       0  5159.4     .07       0
Bank Sta=5015.3,5028.3
XS Rating Curve= 0 ,0
Exp/Cntr=0.3,0.1

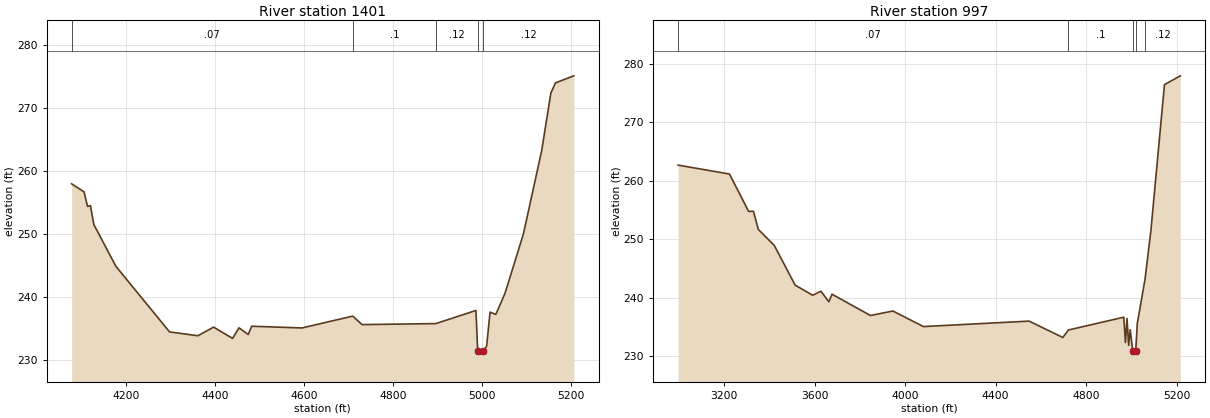
Type RM Length L Ch R = 1 ,1401    ,404,404,404
BEGIN DESCRIPTION:
WEST COTTONWOOD CREEK 3.0
END DESCRIPTION:
XS GIS Cut Line= 3
      2418625.03     13635625.03        2419325.       13636225.
      2419375.01     13636425.03
#Sta/Elev= 30
  4077.8  257.94  4105.7  256.66  4113.4  254.36    4120  254.47  4127.7  251.47
  4177.1  244.84  4297.8  234.41  4361.5   233.8  4396.6  235.17  4439.4  233.38
  4453.7  235.06  4474.5     234  4482.2  235.31  4595.3  235.04  4709.2  236.92
  4730.3  235.57  4895.9  235.73    4986  237.82  4989.9  231.38  4990.4  230.88
  5002.9  231.38    5010  232.15  5017.7  237.55  5030.6  237.19  5051.2  240.52
  5092.5  249.94  5133.7  263.22  5154.3  272.36  5164.6  273.98  5205.9   275.1
#Mann= 5 ,-1 , 0
  4077.8     .07       0  4709.2      .1       0  4895.9     .12       0
  4989.9     .05       0  5002.9     .12       0
Bank Sta=4989.9,5002.9
XS Rating Curve= 0 ,0
Exp/Cntr=0.3,0.1

Type RM Length L Ch R = 1 ,997     ,0,0,0
BEGIN DESCRIPTION:
WEST COTTONWOOD CREEK 2.0
END DESCRIPTION:
XS GIS Cut Line= 3
      2417674.97     13635174.97        2419175.       13636525.
      2419375.01       13636525.
#Sta/Elev= 30
  2997.6   262.7  3224.5  261.18  3308.9   254.8  3330.6   254.8  3351.6  251.73
  3422.6  248.96  3514.5  242.19  3592.2  240.46  3628.1  241.16  3663.2  239.35
  3677.4  240.64  3847.1     237  3946.5  237.77    4081  235.11  4548.2  236.04
  4696.9  233.24  4721.2  234.52    4966  236.71  4973.5  232.38  4980.2   236.5
  4987.7  231.91  4994.4  234.56  5005.8   230.9  5006.3   230.4  5018.8   230.9
  5025.7  235.62    5060  243.22  5085.7  251.45  5145.7  276.46  5215.7  277.96
#Mann= 5 ,-1 , 0
  2997.6     .07       0  4721.2      .1       0  5005.8     .05       0
  5018.8      .1       0    5060     .12       0
Bank Sta=5005.8,5018.8
XS Rating Curve= 0 ,0
Exp/Cntr=0.3,0.1

Chan Stop Cuts=-1
Use User Specified Reach Order=0
Composite Channel Slope=5