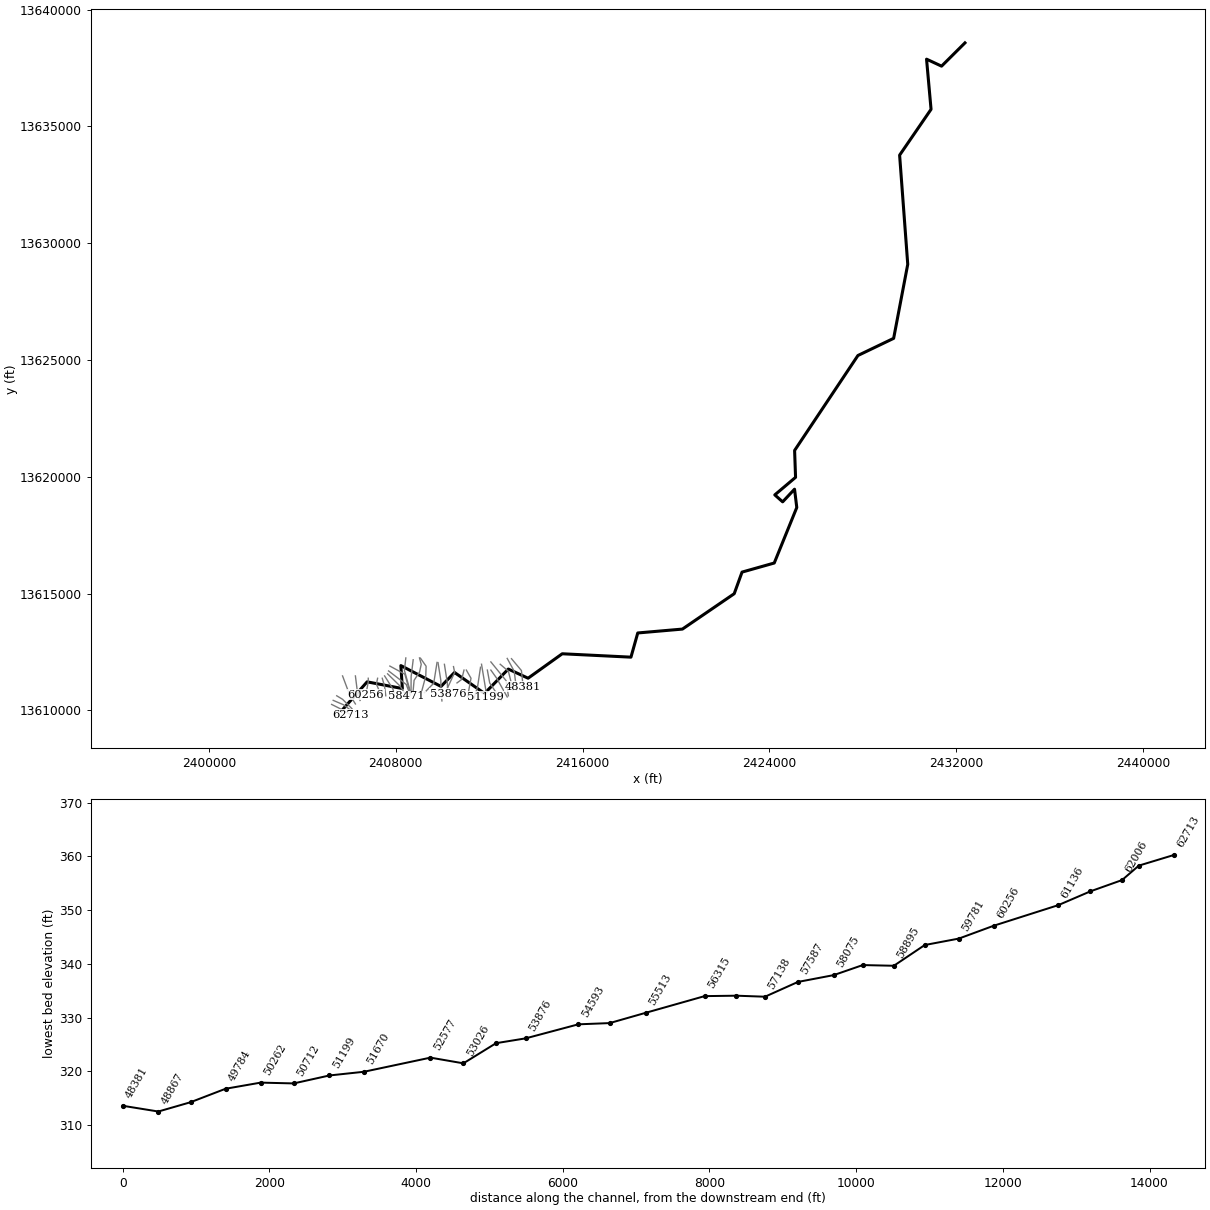
--- WEST ROCKY CREEK.prj (project) ---

Proj Title=WEST ROCKY CREEK Base Level Engineering
Current Plan=p01
Default Exp/Contr=0.3,0.1
English Units
Geom File=g01
Flow File=f01
Plan File=p01
Y Axis Title=Elevation
X Axis Title(PF)=Main Channel Distance
X Axis Title(XS)=Station
BEGIN DESCRIPTION:
WEST ROCKY CREEK
END DESCRIPTION:
DSS Export Rating Curves= 0
DSS Export Rating Curve Sorted= 0
DSS Export Volume Flow Curves= 0
DXF OffsetX= 0
DXF OffsetY= 0
DXF ScaleX= 1
DXF ScaleY= 10

--- WEST ROCKY CREEK.p01 (plan) ---

Plan Title=Multiple Run
Short Identifier=Multiple
Geom File=g01
Flow File=f01
Subcritical Flow
K Sum by GR= 0
Std Step Tol= 0.01
Critical Tol= 0.01
Num of Std Step Trials= 20
Max Error Tol= 0.3
Flow Tol Ratio= 0.001
Split Flow NTrial= 30
Split Flow Tol= 0.02
Split Flow Ratio= 0.02
Log Output Level= 0
Friction Slope Method= 1
Unsteady Friction Slope Method= 2
Unsteady Bridges Friction Slope Method= 1
Parabolic Critical Depth
Global Vel Dist=  1 , 1 , 1
Global Log Level= 0
CheckData=True
Encroach Param= -1, 0, 0, 0
BEGIN DESCRIPTION:
Multiple Run
END DESCRIPTION:

--- WEST ROCKY CREEK.f01 (steady flow) ---

Flow Title=Multiple
Number of Profiles=7
Profile Names=10-year,25-year,50-year,1pct_min,100-year,1pct_plu,500-year
River Rch & RM= WEST ROCKY CREEK,Reach-1,62713
     611     989    1331     868    1732    3455    2904
River Rch & RM= WEST ROCKY CREEK,Reach-1,61576
     910    1497    2037    1340    2674    5335    4568
River Rch & RM= WEST ROCKY CREEK,Reach-1,57138
    1058    1751    2390    1577    3147    6279    5408
River Rch & RM= WEST ROCKY CREEK,Reach-1,54593
    1336    2232    3067    2035    4060    8102    7058
River Rch & RM= WEST ROCKY CREEK,Reach-1,50712
    1494    2504    3447    2290    4568    9115    7960
River Rch & RM= WEST ROCKY CREEK,Reach-1,46635
    1613    2706    3728    2477    4942    9861    8617
River Rch & RM= WEST ROCKY CREEK,Reach-1,43095
    1774    2986    4122    2744    5475   10923    9580
River Rch & RM= WEST ROCKY CREEK,Reach-1,39100
    1919    3240    4481    2988    5961   11894   10465
River Rch & RM= WEST ROCKY CREEK,Reach-1,36452
    2078    3514    4867    3247    6479   12926   11392
River Rch & RM= WEST ROCKY CREEK,Reach-1,32459
    2102    3555    4923    3284    6553   13076   11523
River Rch & RM= WEST ROCKY CREEK,Reach-1,31564
    2315    3932    5463    3655    7293   14551   12896
River Rch & RM= WEST ROCKY CREEK,Reach-1,31091
    2359    3995    5538    3697    7376   14717   12983
River Rch & RM= WEST ROCKY CREEK,Reach-1,22904
    2547    4328    6014    4023    8026   16014   14184
River Rch & RM= WEST ROCKY CREEK,Reach-1,20155
    2647    4505    6266    4196    8371   16703   14825
River Rch & RM= WEST ROCKY CREEK,Reach-1,19569
    2879    4912    6844    4589    9156   18268   16258
River Rch & RM= WEST ROCKY CREEK,Reach-1,16225
    3212    5474    7622    5106   10188   20328   18052
River Rch & RM= WEST ROCKY CREEK,Reach-1,10562
    3313    5646    7861    5265   10505   20961   18605
River Rch & RM= WEST ROCKY CREEK,Reach-1,7835
    3269    5559    7728    5168   10311   20573   18202
River Rch & RM= WEST ROCKY CREEK,Reach-1,4885
    3456    5892    8206    5497   10968   21884   19431
Boundary for River Rch & Prof#=WEST ROCKY CREEK,Reach-1,1
Up Type=0
Dn Type=3
Dn Slope=0.005
Boundary for River Rch & Prof#=WEST ROCKY CREEK,Reach-1,2
Up Type=0
Dn Type=3
Dn Slope=0.005
Boundary for River Rch & Prof#=WEST ROCKY CREEK,Reach-1,3
Up Type=0
Dn Type=3
Dn Slope=0.005
Boundary for River Rch & Prof#=WEST ROCKY CREEK,Reach-1,4
Up Type=0
Dn Type=3
Dn Slope=0.005
Boundary for River Rch & Prof#=WEST ROCKY CREEK,Reach-1,5
Up Type=0
Dn Type=3
Dn Slope=0.005
Boundary for River Rch & Prof#=WEST ROCKY CREEK,Reach-1,6
Up Type=0
Dn Type=3
Dn Slope=0.005
Boundary for River Rch & Prof#=WEST ROCKY CREEK,Reach-1,7
Up Type=0
Dn Type=3
Dn Slope=0.005

--- WEST ROCKY CREEK.g01 (geometry) ---

Geom Title=Existing Conditions
Program Version=4.10

River Reach=WEST ROCKY CREEK,Reach-1
Reach XY= 30
        2405675.       13609975.      2406776.45     13611221.47
      2408285.24     13610935.34       2408221.3     13611917.33
      2409940.17     13611025.36      2410519.15     13611622.94
      2411804.83      13610724.7      2412822.15      13611769.2
      2413669.16     13611377.05      2415131.03     13612423.42
      2418073.75     13612278.45      2418364.62      13613314.2
       2420277.7     13613480.36      2422495.09     13614994.78
      2422830.09     13615919.55      2424208.79     13616308.33
       2425173.8      13618685.5      2425077.67     13619469.71
      2424568.98     13618926.61      2424232.53     13619225.01
      2425121.64     13619976.25      2425080.73     13621127.55
      2427791.64     13625191.68      2429321.55     13625926.25
      2429925.28     13629095.18      2429576.96     13633769.11
      2430923.13     13635730.69      2430730.36     13637877.78
      2431373.28     13637578.34        2432375.       13638575.

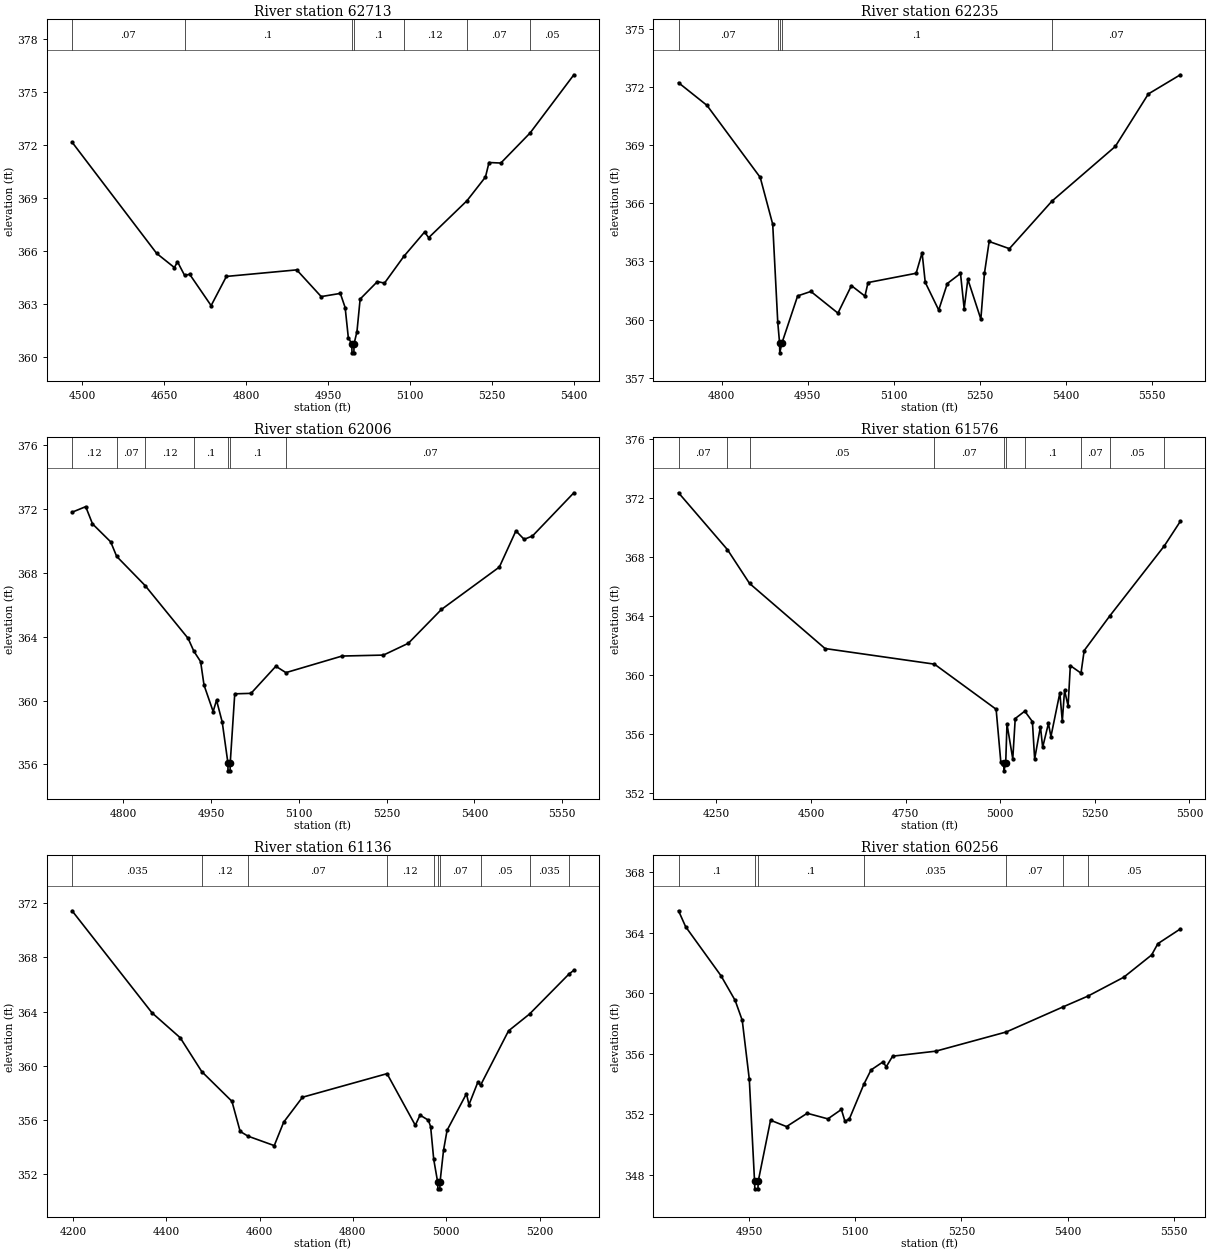
Type RM Length L Ch R = 1 ,62713   ,478,478,478
BEGIN DESCRIPTION:
H21776
END DESCRIPTION:
XS GIS Cut Line= 3
      2405256.59     13610255.61      2405689.16     13610039.33
      2406065.03     13609823.02
#Sta/Elev= 30
  4481.9  372.17  4636.6  365.88    4669  365.08  4674.6  365.41  4687.6  364.64
  4696.9   364.7  4736.1  362.93    4764  364.58  4892.6  364.95  4937.3  363.44
  4972.3  363.62  4981.1  362.82  4986.9  361.12  4993.3  360.76  4993.6  360.26
  4997.1  360.26  4997.3  360.76  5002.7  361.46  5008.5   363.3  5040.1  364.29
    5053   364.2  5088.3  365.71  5126.3  367.09  5133.8  366.77  5203.8  368.86
  5237.6   370.2  5244.1  371.02  5265.7  370.99  5319.2  372.69  5399.2  375.98
#Mann= 7 ,-1 , 0
  4481.9     .07       0  4687.6      .1       0  4993.3     .05       0
  4997.3      .1       0  5088.3     .12       0  5203.8     .07       0
  5319.2     .05       0
Bank Sta=4993.3,4997.3
XS Rating Curve= 0 ,0
Exp/Cntr=0.3,0.1

Type RM Length L Ch R = 1 ,62235   ,229,229,229
BEGIN DESCRIPTION:
H21777
END DESCRIPTION:
XS GIS Cut Line= 3
      2405323.99     13610429.34      2405770.71     13610237.89
      2406079.21     13610000.31
#Sta/Elev= 30
  4724.6  372.23  4774.2  371.06  4867.1  367.34  4888.9  364.92  4897.7  359.86
  4900.9  358.78  4901.2  358.28  4904.9  358.78  4932.4  361.22  4955.5  361.45
  5002.7  360.33  5026.2  361.75  5049.8  361.21  5055.2  361.91  5139.1  362.39
  5149.5  363.45    5155  361.92  5178.5  360.49  5193.5  361.86  5216.5  362.38
  5222.9  360.56  5229.3  362.08    5252  360.02  5258.3  362.39  5266.5  364.03
  5301.8  363.66  5376.2  366.12  5486.6  368.94  5544.2  371.65    5600  372.64
#Mann= 5 ,-1 , 0
  4724.6     .07       0  4897.7      .1       0  4900.9     .05       0
  4904.9      .1       0  5376.2     .07       0
Bank Sta=4900.9,4904.9
XS Rating Curve= 0 ,0
Exp/Cntr=0.3,0.1

Type RM Length L Ch R = 1 ,62006   ,430,430,430
BEGIN DESCRIPTION:
WEST ROCKY CREEK 96.0
END DESCRIPTION:
XS GIS Cut Line= 3
      2405475.03     13610624.98        2405725.       13610475.
        2406125.       13610075.
#Sta/Elev= 30
  4712.7  371.81    4736  372.16  4747.6  371.08  4778.7  369.95  4788.9  369.04
  4837.5  367.21  4910.9   363.9  4920.8  363.09  4932.3  362.44  4938.1  360.97
  4953.7  359.31  4959.5  360.02  4969.2  358.65  4978.9  356.09  4979.1  355.59
  4982.6  355.59  4982.9  356.09  4990.6  360.42  5018.4  360.45  5060.8  362.15
    5078  361.75  5173.9  362.79  5244.6  362.85  5287.1  363.59  5343.6  365.71
  5442.6  368.37  5470.9  370.64    5485  370.11  5499.2  370.32  5569.9  373.03
#Mann= 7 ,-1 , 0
  4712.7     .12       0  4788.9     .07       0  4837.5     .12       0
  4920.8      .1       0  4978.9     .05       0  4982.9      .1       0
    5078     .07       0
Bank Sta=4978.9,4982.9
XS Rating Curve= 0 ,0
Exp/Cntr=0.3,0.1

Type RM Length L Ch R = 1 ,61576   ,440,440,440
BEGIN DESCRIPTION:
WEST ROCKY CREEK 95.0
END DESCRIPTION:
XS GIS Cut Line= 3
        2405725.     13611475.01        2406025.       13610675.
      2406274.99     13610275.01
#Sta/Elev= 30
  4149.7  372.37    4279  368.51  4337.3  366.22  4536.9   361.8    4826  360.74
    4989  357.68  5001.4   354.1  5009.2     354  5009.6   353.5  5014.3     354
  5017.7  356.68    5033  354.31  5039.5  357.05  5064.7  357.55  5084.9  356.84
  5090.8   354.3  5106.1   356.5    5112   355.1  5127.3  356.72  5133.8  355.82
  5157.4  358.79  5163.9  356.87  5169.8  358.96  5179.2  357.91  5185.1  360.64
  5213.3  360.13  5221.7  361.66    5289     364  5433.6  368.77  5475.8  370.43
#Mann= 10 ,-1 , 0
  4149.7     .07       0    4279    .035       0  4337.3     .05       0
    4826     .07       0  5009.2     .05       0  5014.3     .07       0
  5064.7      .1       0  5213.3     .07       0    5289     .05       0
  5433.6     .07       0
Bank Sta=5009.2,5014.3
XS Rating Curve= 0 ,0
Exp/Cntr=0.3,0.1

Type RM Length L Ch R = 1 ,61136   ,880,880,880
BEGIN DESCRIPTION:
WEST ROCKY CREEK 94.0
END DESCRIPTION:
XS GIS Cut Line= 3
        2406275.     13611474.96        2406375.       13610675.
      2406474.98     13610425.04
#Sta/Elev= 30
  4198.2  371.44  4369.5  363.91    4430  362.07  4476.2  359.57  4540.8  357.38
  4558.4  355.16  4575.1  354.81  4631.5  354.11  4651.7  355.84    4692  357.68
  4873.2  359.42  4933.8  355.61  4943.9  356.36  4961.6  355.99  4966.6  355.52
  4973.3  353.09  4981.7  351.42  4982.1  350.92  4986.4  350.92  4986.8  351.42
  4994.3  353.77  5001.9  355.24  5043.4  357.94  5048.8  357.13  5067.7  358.78
  5073.7  358.57  5133.6  362.58  5178.6  363.82  5263.1  366.77  5273.6  367.05
#Mann= 10 ,-1 , 0
  4198.2    .035       0  4476.2     .12       0  4575.1     .07       0
  4873.2     .12       0  4973.3     .07       0  4981.7     .05       0
  4986.8     .07       0  5073.7     .05       0  5178.6    .035       0
  5263.1     .05       0
Bank Sta=4981.7,4986.8
XS Rating Curve= 0 ,0
Exp/Cntr=0.3,0.1

Type RM Length L Ch R = 1 ,60256   ,475,475,475
BEGIN DESCRIPTION:
WEST ROCKY CREEK 93.0
END DESCRIPTION:
XS GIS Cut Line= 3
        2406825.     13611375.03        2406825.       13611225.
      2406725.01     13610675.05
#Sta/Elev= 30
  4850.4  365.45  4860.4   364.4  4910.4  361.16  4930.4  359.53  4940.4  358.22
  4950.4  354.32  4957.8  347.59  4958.2  347.09  4962.6  347.09    4963  347.59
  4980.4  351.62    5003   351.2  5032.2  352.08  5061.4  351.71  5080.5  352.33
  5085.6  351.54  5091.9  351.72  5112.3     354  5122.4  354.94  5138.9  355.46
    5144  355.16  5152.9  355.85  5213.9  356.18  5313.6  357.45    5394  359.11
    5429  359.82  5479.4  361.06  5518.8  362.53  5527.7  363.28  5559.4  364.25
#Mann= 7 ,-1 , 0
  4850.4      .1       0  4957.8     .05       0    4963      .1       0
  5112.3    .035       0  5313.6     .07       0    5394    .035       0
    5429     .05       0
Bank Sta=4957.8,4963
XS Rating Curve= 0 ,0
Exp/Cntr=0.3,0.1

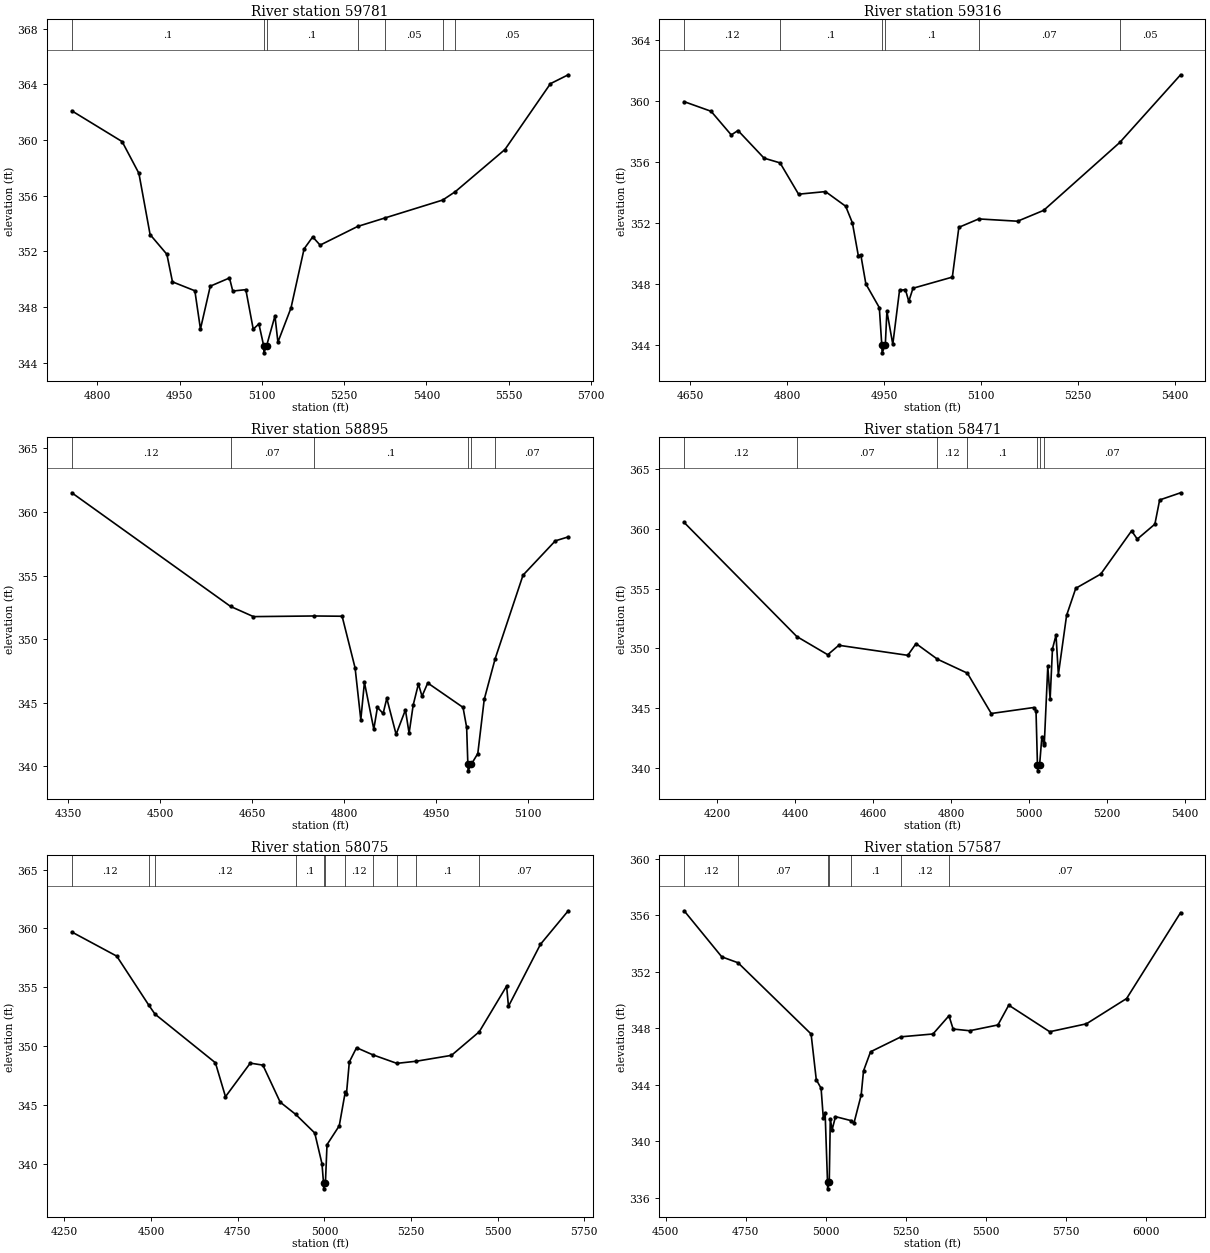
Type RM Length L Ch R = 1 ,59781   ,465,465,465
BEGIN DESCRIPTION:
WEST ROCKY CREEK 92.0
END DESCRIPTION:
XS GIS Cut Line= 3
      2407224.99     13611374.95        2407175.       13611125.
        2407425.       13610525.
#Sta/Elev= 30
  4753.5  362.09  4845.2  359.88  4875.8   357.6  4896.2   353.2  4926.8  351.78
    4937   349.8  4977.8  349.16    4988  346.41  5005.9  349.49  5040.9  350.08
  5046.9  349.14  5070.7  349.24  5084.2   346.4  5094.5  346.78  5103.3   345.2
  5103.7   344.7  5108.5   345.2  5123.8  347.35  5129.2  345.47    5153  347.92
  5176.9  352.17  5192.6  353.03  5206.1  352.44  5274.4  353.78  5324.1  354.39
  5429.6  355.68  5452.5  356.28    5543  359.31  5625.9  364.04  5658.4  364.68
#Mann= 7 ,-1 , 0
  4753.5      .1       0  5103.3     .05       0  5108.5      .1       0
  5274.4     .07       0  5324.1     .05       0  5429.6     .07       0
  5452.5     .05       0
Bank Sta=5103.3,5108.5
XS Rating Curve= 0 ,0
Exp/Cntr=0.3,0.1

Type RM Length L Ch R = 1 ,59316   ,421,421,421
BEGIN DESCRIPTION:
WEST ROCKY CREEK 91.0
END DESCRIPTION:
XS GIS Cut Line= 3
        2407425.       13611375.        2407525.       13611025.
        2407575.     13610625.02
#Sta/Elev= 30
  4641.1  359.95  4682.7  359.32  4713.9  357.77  4724.3  358.06  4764.6  356.25
  4789.3  355.94  4817.9  353.89  4859.5  354.06  4890.7   353.1  4901.1  352.01
  4910.2  349.87  4914.1  349.91  4921.9  348.01  4942.7  346.46  4946.5     344
    4947   343.5  4951.9     344  4954.4  346.22  4963.5  344.06  4973.9  347.59
    4983  347.64  4988.2  346.87  4994.7  347.73  5055.5  348.46  5065.6  351.72
  5096.3  352.27  5156.3  352.12  5196.6  352.83  5314.3  357.28  5408.2  361.71
#Mann= 6 ,-1 , 0
  4641.1     .12       0  4789.3      .1       0  4946.5     .05       0
  4951.9      .1       0  5096.3     .07       0  5314.3     .05       0
Bank Sta=4946.5,4951.9
XS Rating Curve= 0 ,0
Exp/Cntr=0.3,0.1

Type RM Length L Ch R = 1 ,58895   ,424,424,424
BEGIN DESCRIPTION:
WEST ROCKY CREEK 90.0
END DESCRIPTION:
XS GIS Cut Line= 3
      2407524.98     13611475.03        2407875.       13610925.
      2407925.01     13610774.97
#Sta/Elev= 30
  4355.7  361.51  4614.8  352.57  4652.1  351.77  4750.6  351.82  4796.8   351.8
    4818  347.73  4827.3  343.66  4833.2   346.6  4848.5  342.92  4854.4  344.63
  4863.7  344.15  4869.7  345.34  4884.9  342.51  4900.1  344.43  4906.1   342.6
  4912.8  344.82  4921.3  346.47  4927.2  345.51  4936.5  346.55  4994.1  344.63
    5000  343.06    5002  340.14  5002.4  339.64  5007.4  340.14  5018.2     341
  5028.7  345.26  5046.4  348.44    5092  355.03  5144.7  357.73  5165.8  358.04
#Mann= 6 ,-1 , 0
  4355.7     .12       0  4614.8     .07       0  4750.6      .1       0
    5002     .05       0  5007.4      .1       0  5046.4     .07       0
Bank Sta=5002,5007.4
XS Rating Curve= 0 ,0
Exp/Cntr=0.3,0.1

Type RM Length L Ch R = 1 ,58471   ,396,396,396
BEGIN DESCRIPTION:
H21775
END DESCRIPTION:
XS GIS Cut Line= 3
      2407653.46     13611564.03      2408181.81     13611046.32
      2408472.42     13610599.77
#Sta/Elev= 30
    4116  360.52  4404.8  350.99  4484.1  349.47  4512.4  350.26  4689.2  349.42
  4710.4   350.4  4765.1   349.1    4842  347.93  4903.2  344.56  5011.9  345.06
  5017.9   344.8  5021.6  340.27    5022  339.77  5027.1  340.27    5033  342.63
  5037.4   342.1    5039  341.91  5048.1   348.5  5054.1  345.77  5060.1  349.96
  5069.2  351.11  5075.2  347.81  5096.3  352.76  5119.8  355.02  5183.9  356.21
  5262.9  359.82  5277.5  359.13  5322.6  360.38  5334.8   362.4  5388.5     363
#Mann= 7 ,-1 , 0
    4116     .12       0  4404.8     .07       0  4765.1     .12       0
    4842      .1       0  5021.6     .05       0  5027.1      .1       0
  5037.4     .07       0
Bank Sta=5021.6,5027.1
XS Rating Curve= 0 ,0
Exp/Cntr=0.3,0.1

Type RM Length L Ch R = 1 ,58075   ,488,488,488
BEGIN DESCRIPTION:
H21774
END DESCRIPTION:
XS GIS Cut Line= 3
      2407696.07     13611688.07      2408451.28     13611110.14
      2408621.45     13610659.89
#Sta/Elev= 30
  4271.2   359.7  4400.9  357.65  4493.3  353.49  4511.2  352.73  4685.5   348.6
  4714.6  345.72  4786.1  348.57  4822.5   348.4  4872.4  345.26  4917.1  344.22
  4972.1  342.64    4993  340.03  4997.4   338.4  4997.9   337.9  5002.9   338.4
  5007.5  341.65  5042.8  343.25  5059.9  346.08  5063.7  345.99  5071.9  348.67
  5092.7  349.88  5139.2  349.28    5209  348.55    5265  348.73  5366.6  349.23
  5446.7  351.23  5525.7  355.11    5531  353.39  5623.2  358.65  5703.5   361.5
#Mann= 11 ,-1 , 0
  4271.2     .12       0  4493.3     .07       0  4511.2     .12       0
  4917.1      .1       0  4997.4     .05       0  5002.9      .1       0
  5059.9     .12       0  5139.2      .1       0    5209     .07       0
    5265      .1       0  5446.7     .07       0
Bank Sta=4997.4,5002.9
XS Rating Curve= 0 ,0
Exp/Cntr=0.3,0.1

Type RM Length L Ch R = 1 ,57587   ,449,449,449
BEGIN DESCRIPTION:
H21773
END DESCRIPTION:
XS GIS Cut Line= 3
      2407749.24     13611897.29        2408391.     13611549.81
      2408617.93     13610762.66
#Sta/Elev= 30
    4558  356.31  4675.4  353.05  4726.2  352.63  4954.1  347.59  4970.3  344.35
  4985.3  343.75  4992.2  341.64  4997.9     342  5005.3  337.13  5005.7  336.63
  5010.8  337.13    5014  341.59  5019.7  340.81  5030.2  341.74  5078.4  341.46
  5087.7  341.27  5110.4  343.27  5117.7  344.98  5139.6  346.33  5234.7  347.39
  5334.4  347.59  5384.3  348.88  5397.3  347.94  5448.9  347.82  5537.1  348.23
  5570.8  349.63  5698.7  347.75  5813.2  348.31  5938.6   350.1    6107  356.18
#Mann= 7 ,-1 , 0
    4558     .12       0  4726.2     .07       0  5005.3     .05       0
  5010.8     .07       0  5078.4      .1       0  5234.7     .12       0
  5384.3     .07       0
Bank Sta=5005.3,5010.8
XS Rating Curve= 0 ,0
Exp/Cntr=0.3,0.1

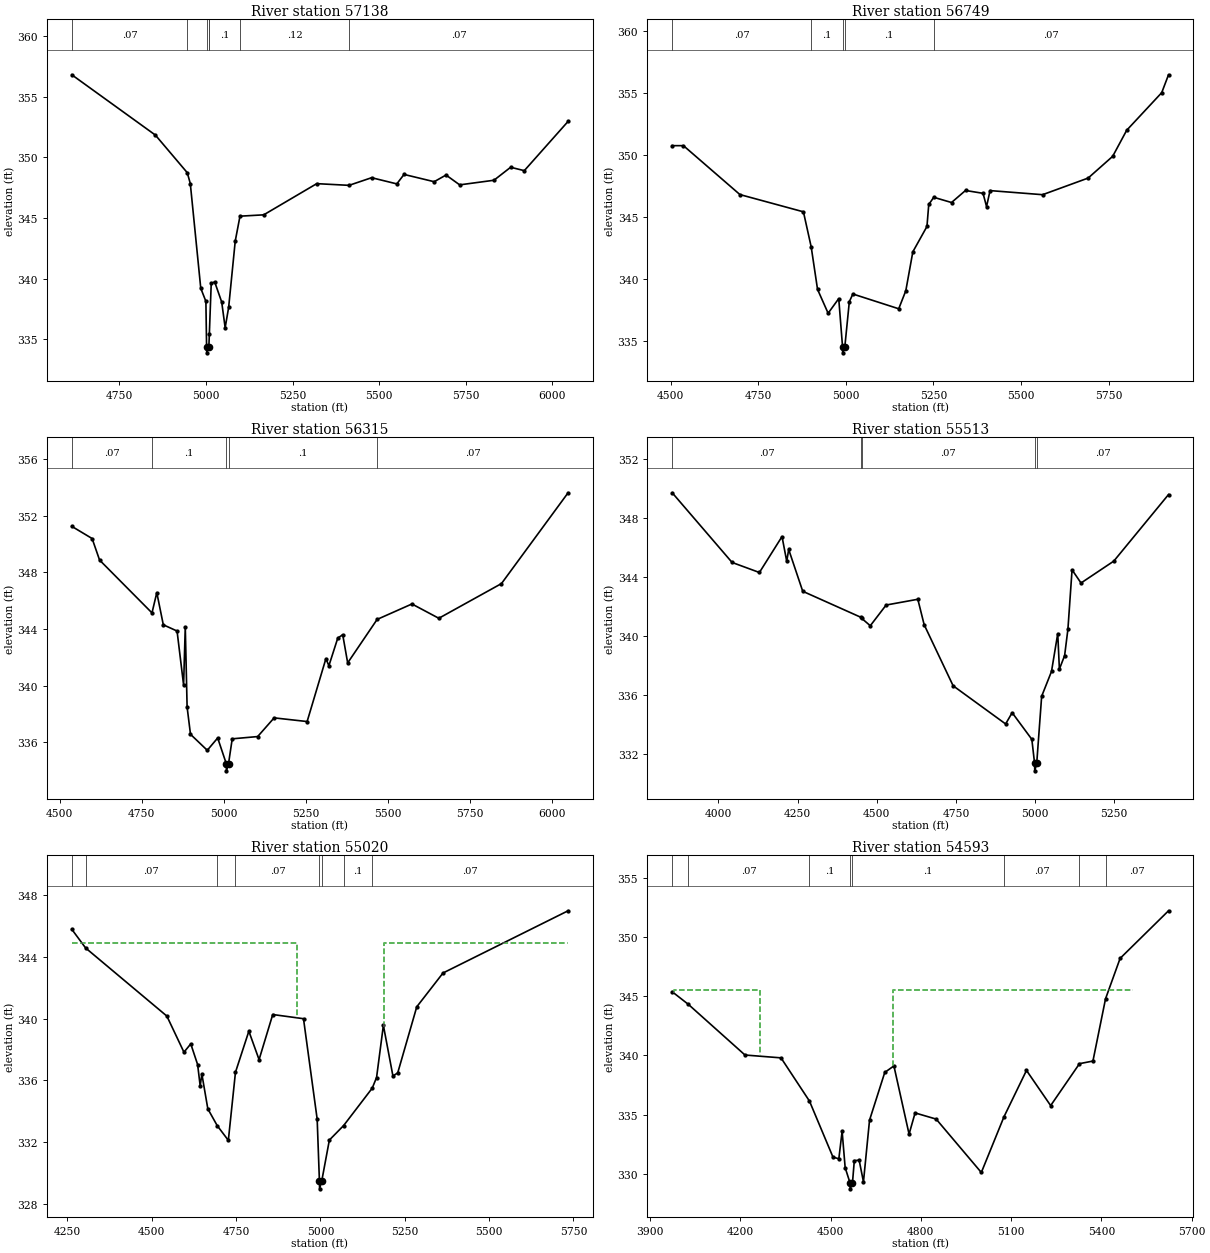
Type RM Length L Ch R = 1 ,57138   ,389,389,389
BEGIN DESCRIPTION:
H21772
END DESCRIPTION:
XS GIS Cut Line= 3
      2408433.56      13612244.8      2408373.28     13611712.91
      2408614.08     13610848.83
#Sta/Elev= 30
  4612.9  356.79  4854.2  351.82  4946.2  348.72  4954.9  347.83  4985.1   339.2
  4999.9  338.12  5001.9  334.38  5002.4  333.88  5008.5  334.38  5009.9  335.46
  5015.3  339.61  5025.3  339.72  5045.5  338.07  5055.5  335.95  5065.6  337.63
  5084.6  343.09  5098.3  345.14  5166.8  345.25  5319.8  347.82    5413  347.68
  5478.2  348.31  5550.9   347.8  5571.7  348.58  5658.7  347.98  5692.9  348.53
  5732.3  347.72  5831.2   348.1  5879.4  349.17  5918.8  348.89  6045.2  352.95
#Mann= 7 ,-1 , 0
  4612.9     .07       0  4946.2     .12       0  5001.9     .05       0
  5008.5     .12       0  5009.9      .1       0  5098.3     .12       0
    5413     .07       0
Bank Sta=5001.9,5008.5
XS Rating Curve= 0 ,0
Exp/Cntr=0.3,0.1

Type RM Length L Ch R = 1 ,56749   ,434,434,434
BEGIN DESCRIPTION:
H21771
END DESCRIPTION:
XS GIS Cut Line= 3
      2408749.12     13612166.78      2408660.48     13611439.89
      2408656.93     13610755.57
#Sta/Elev= 30
  4504.5  350.76  4536.5  350.76  4697.7  346.82    4879  345.43  4901.2   342.6
  4919.3  339.18  4949.5  337.26  4979.8  338.44  4990.6  334.57  4991.1  334.07
  4997.2  334.57    5010  338.19  5020.1  338.81    5151  337.62  5171.2  339.07
  5191.3  342.21  5231.6  344.25  5236.7  346.02    5251   346.6  5301.7  346.18
  5341.7  347.15  5391.7  346.92  5401.7  345.85  5411.7  347.14  5561.7  346.81
  5691.7  348.15  5761.7   349.9  5801.7     352  5901.7  355.03  5921.1  356.47
#Mann= 5 ,-1 , 0
  4504.5     .07       0  4901.2      .1       0  4990.6     .05       0
  4997.2      .1       0    5251     .07       0
Bank Sta=4990.6,4997.2
XS Rating Curve= 0 ,0
Exp/Cntr=0.3,0.1

Type RM Length L Ch R = 1 ,56315   ,802,802,802
BEGIN DESCRIPTION:
H21770
END DESCRIPTION:
XS GIS Cut Line= 5
       2409018.6     13612244.75      2409093.06     13611971.75
      2409022.14       13611642.      2408788.13     13611287.43
      2408745.58     13610822.97
#Sta/Elev= 30
  4536.6  351.25  4598.5  350.39  4621.2  348.87  4780.8  345.14  4795.5  346.57
  4815.3   344.3  4857.2  343.86  4877.1  340.05  4882.2  344.16  4887.8  338.49
  4898.1  336.57  4949.2  335.44  4980.9  336.31  5007.2  334.49  5007.7  333.99
  5013.9  334.49  5025.2  336.25  5102.7  336.41  5152.8  337.73  5253.3  337.47
  5310.5  341.91  5319.6  341.41  5346.6  343.36  5361.7   343.6  5376.8  341.61
  5466.5  344.68  5572.5  345.77  5654.4  344.76  5845.2  347.21  6048.1  353.62
#Mann= 5 ,-1 , 0
  4536.6     .07       0  4780.8      .1       0  5007.2     .05       0
  5013.9      .1       0  5466.5     .07       0
Bank Sta=5007.2,5013.9
XS Rating Curve= 0 ,0
Exp/Cntr=0.3,0.1

Type RM Length L Ch R = 1 ,55513   ,493,493,493
BEGIN DESCRIPTION:
H21769
END DESCRIPTION:
XS GIS Cut Line= 4
      2409061.13     13612234.17      2409302.26      13611890.2
      2409288.07     13611468.26      2409100.65     13610768.06
#Sta/Elev= 30
  3854.2  349.69  4043.2  344.98  4129.5   344.3  4200.9  346.73  4215.8  345.05
  4221.9  345.86  4266.3  343.03    4450  341.27  4452.5   341.2  4479.6   340.7
  4529.6   342.1  4629.7  342.49  4649.7  340.77  4741.2  336.64  4906.9  334.06
  4927.6  334.82  4989.7  333.02  4998.4  331.39  4998.9  330.89  5005.1  331.39
  5020.7  335.93  5051.8  337.61  5071.5  340.17  5076.7  337.77  5093.2  338.68
  5103.6  340.46  5116.7  344.48    5145  343.59  5248.5  345.07  5421.3  349.57
#Mann= 5 ,-1 , 0
  3854.2     .07       0    4450      .1       0  4452.5     .07       0
  4998.4     .05       0  5005.1     .07       0
Bank Sta=4998.4,5005.1
XS Rating Curve= 0 ,0
Exp/Cntr=0.3,0.1

Type RM Length L Ch R = 1 ,55020   ,427,427,427
BEGIN DESCRIPTION:
H21768
END DESCRIPTION:
XS GIS Cut Line= 3
      2409770.29     13612053.31      2409628.46     13611163.32
      2409228.91     13610756.69
#Sta/Elev= 30
  4262.8  345.78  4303.8  344.57  4544.6  340.16  4595.3  337.82  4615.5  338.36
  4635.8  337.02  4643.4  335.64  4648.4   336.4  4666.1  334.15    4694  333.06
  4726.9  332.11    4748  336.52  4787.7  339.18    4818  337.34  4858.5  340.26
  4949.7  339.99  4990.2  333.49  4996.9  329.47  4997.4  328.97  5003.7  329.47
  5026.4  332.13  5068.7  333.07  5153.4  335.49  5166.3  336.18  5186.5  339.56
  5214.8  336.28    5229  336.48  5285.5  340.76  5363.3  342.95  5734.1  346.98
#Mann= 8 ,-1 , 0
  4262.8     .05       0  4303.8     .07       0    4694      .1       0
    4748     .07       0  4996.9     .05       0  5003.7     .07       0
  5068.7      .1       0  5153.4     .07       0
#XS Ineff= 2 , 0
       0  4929.1   344.9  5187.6       0   344.9
Permanent Ineff=
       F       F
Bank Sta=4996.9,5003.7
XS Rating Curve= 0 ,0
Exp/Cntr=0.3,0.1

Type RM Length L Ch R = 1 ,54593   ,717,717,717
BEGIN DESCRIPTION:
H21767
END DESCRIPTION:
XS GIS Cut Line= 4
      2409812.84     13612042.67       2409933.4     13611280.33
      2409936.94     13610932.85      2409979.49     13610404.57
#Sta/Elev= 30
  3973.8  345.38  4027.3  344.32  4215.6  340.04  4335.3   339.8  4429.9  336.15
    4508  331.42  4527.5  331.28  4538.4   333.6  4548.5  330.53  4564.7  329.24
  4565.2  328.74  4572.8  329.24  4578.9  331.12    4595  331.16  4609.3  329.33
  4629.5  334.54  4680.1  338.57  4710.5  339.12  4760.9  333.36  4780.9  335.15
  4850.9  334.63    5001  330.12  5076.4  334.83  5151.1  338.74  5231.4  335.77
  5327.2  339.31  5371.9  339.53  5413.8  344.79  5462.2   348.2  5623.1  352.22
#Mann= 8 ,-1 , 0
  3973.8     .05       0  4027.3     .07       0  4429.9      .1       0
  4564.7     .05       0  4572.8      .1       0  5076.4     .07       0
  5327.2      .1       0  5413.8     .07       0
#XS Ineff= 2 ,-1
  3978.3  4266.9  345.49  4708.4    5506  345.49
Permanent Ineff=
       F       F
Bank Sta=4564.7,4572.8
XS Rating Curve= 0 ,0
Exp/Cntr=0.3,0.1

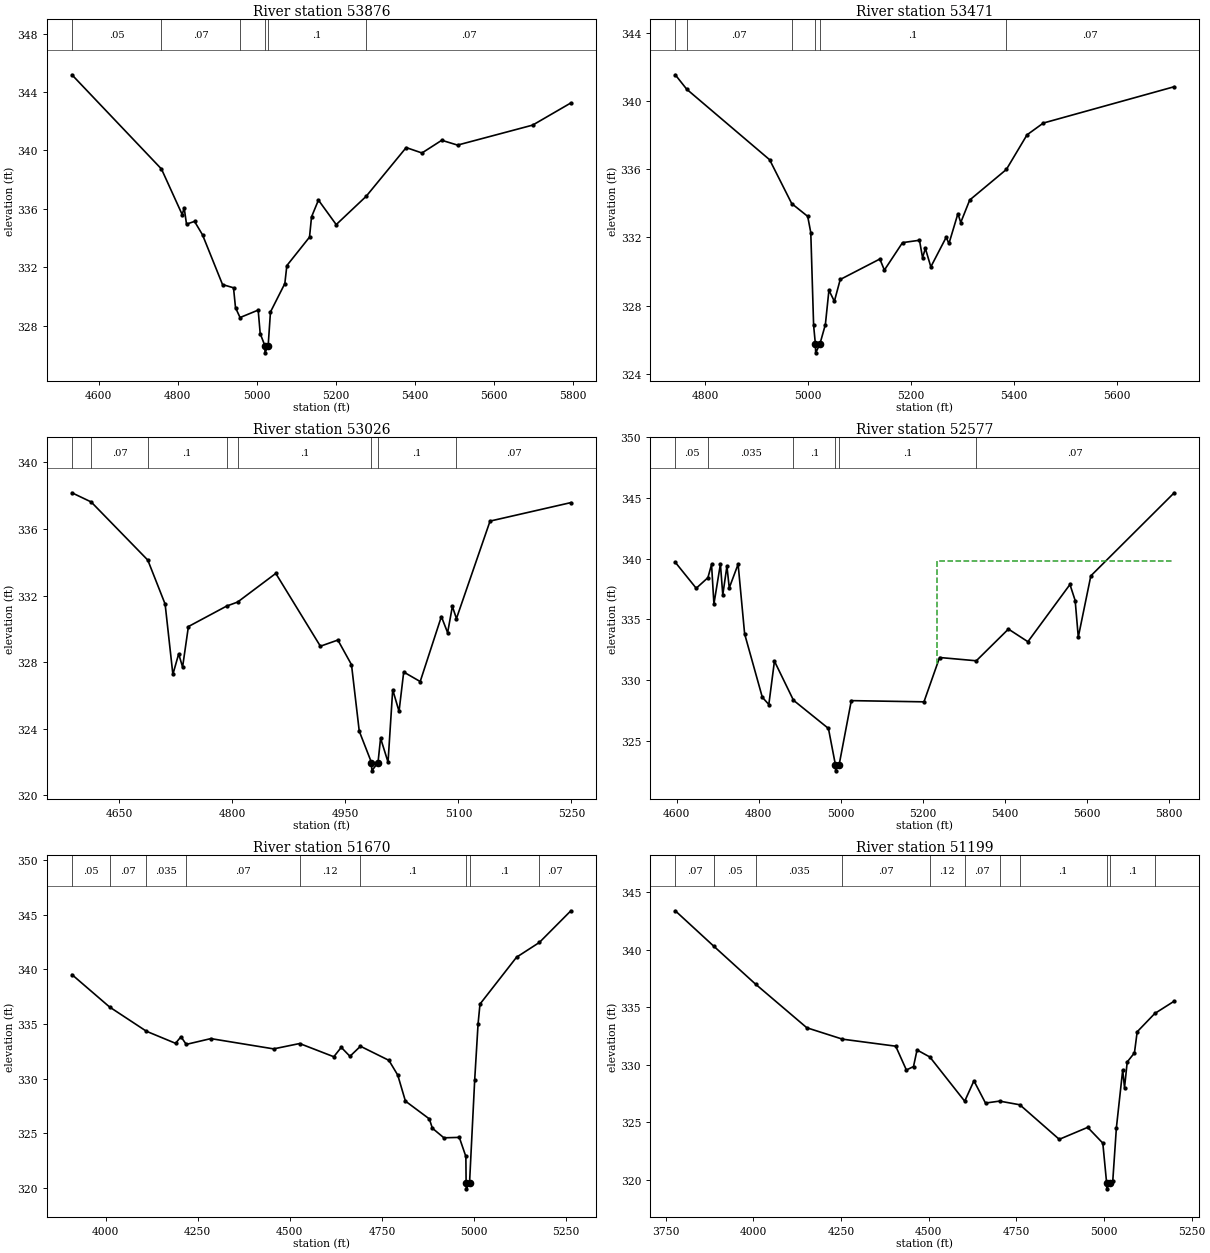
Type RM Length L Ch R = 1 ,53876   ,405,405,405
BEGIN DESCRIPTION:
H21766
END DESCRIPTION:
XS GIS Cut Line= 3
      2410085.87     13611971.71      2410209.96      13611184.6
      2410231.16     13610718.31
#Sta/Elev= 30
    4532  345.19  4758.8  338.73  4811.2  335.61  4816.3  336.06  4822.2  334.95
  4842.5  335.14  4862.7  334.22  4913.4  330.81  4941.2  330.59  4946.3  329.22
  4957.8  328.55  5003.7  329.06  5008.8  327.45  5020.5  326.63    5021  326.13
    5029  326.63  5034.8  328.93  5071.2  330.88  5076.3  332.11  5133.7  334.06
  5138.8  335.45  5156.3   336.6  5201.3  334.92  5277.2  336.86  5378.5   340.2
  5418.5  339.83  5468.6   340.7  5508.6  340.37  5698.8  341.74  5795.6  343.26
#Mann= 6 ,-1 , 0
    4532     .05       0  4758.8     .07       0  4957.8      .1       0
  5020.5     .05       0    5029      .1       0  5277.2     .07       0
Bank Sta=5020.5,5029
XS Rating Curve= 0 ,0
Exp/Cntr=0.3,0.1

Type RM Length L Ch R = 1 ,53471   ,445,445,445
BEGIN DESCRIPTION:
WEST ROCKY CREEK 84.0
END DESCRIPTION:
XS GIS Cut Line= 3
        2410475.     13611875.01        2410525.       13611625.
      2410224.98     13610974.96
#Sta/Elev= 30
  4741.2  341.53  4763.6  340.68  4924.8  336.55  4967.8  333.98  4998.9  333.23
  5004.9  332.28  5010.4  326.84  5013.9  325.73  5014.4  325.23  5022.5  325.73
  5033.3  326.89  5040.2   328.9  5050.8  328.25  5062.2  329.53  5139.3  330.73
  5148.1  330.08  5183.4  331.69  5216.4  331.83  5222.4  330.81  5227.9  331.35
  5238.5  330.27  5268.3     332  5273.8  331.64  5291.2  333.39  5296.7  332.87
  5314.2  334.19  5385.5  335.98  5425.7  338.01  5457.4   338.7  5712.1  340.83
#Mann= 6 ,-1 , 0
  4741.2     .05       0  4763.6     .07       0  4967.8      .1       0
  5013.9     .05       0  5022.5      .1       0  5385.5     .07       0
Bank Sta=5013.9,5022.5
XS Rating Curve= 0 ,0
Exp/Cntr=0.3,0.1

Type RM Length L Ch R = 1 ,53026   ,449,449,449
BEGIN DESCRIPTION:
WEST ROCKY CREEK 83.0
END DESCRIPTION:
XS GIS Cut Line= 3
      2410924.99     13611724.98        2410825.       13611325.
      2410624.99     13611174.99
#Sta/Elev= 30
  4586.9  338.17  4612.4  337.62  4687.6  334.13  4710.6  331.49  4720.9  327.27
  4728.6   328.5  4733.8  327.71  4741.5  330.14  4792.3  331.37  4806.8  331.61
  4857.5  333.33  4916.7  328.96  4939.9  329.33    4958  327.85  4968.3  323.86
  4984.5  321.98    4985  321.48  4993.2  321.98  4996.6  323.44  5006.5     322
  5012.7  326.35  5021.1  325.05  5027.3  327.41  5049.2  326.84  5077.3  330.74
  5085.6  329.77  5091.9  331.35  5097.3  330.62  5141.9  336.47  5249.2  337.58
#Mann= 8 ,-1 , 0
  4586.9     .05       0  4612.4     .07       0  4687.6      .1       0
  4792.3     .07       0  4806.8      .1       0  4984.5     .05       0
  4993.2      .1       0  5097.3     .07       0
Bank Sta=4984.5,4993.2
XS Rating Curve= 0 ,0
Exp/Cntr=0.3,0.1

Type RM Length L Ch R = 1 ,52577   ,907,907,907
BEGIN DESCRIPTION:
WEST ROCKY CREEK 82.0
END DESCRIPTION:
XS GIS Cut Line= 3
        2411025.       13611725.        2411225.       13611375.
      2411075.01     13610575.05
#Sta/Elev= 30
  4596.9  339.71    4648  337.57  4676.5  338.44  4685.4  339.53  4691.2  336.28
    4707  339.56  4712.8  337.03  4722.9  339.39  4728.6   337.6  4750.2  339.55
  4766.1  333.81  4809.2   328.6  4825.1     328  4838.8  331.57  4885.2  328.35
  4970.5  326.03  4987.5  323.04    4988  322.54  4996.6  323.04  5026.3  328.32
  5203.5  328.22  5241.6  331.87  5331.2   331.6  5409.5  334.21    5457  333.17
  5559.6  337.88  5572.3  336.56  5579.9  333.55  5610.5  338.59  5813.9  345.43
#Mann= 6 ,-1 , 0
  4596.9     .05       0  4676.5    .035       0  4885.2      .1       0
  4987.5     .05       0  4996.6      .1       0  5331.2     .07       0
#XS Ineff= 2 , 0
       0                  5236.4       0   339.8
Permanent Ineff=
       F       F
Bank Sta=4987.5,4996.6
XS Rating Curve= 0 ,0
Exp/Cntr=0.3,0.1

Type RM Length L Ch R = 1 ,51670   ,471,471,471
BEGIN DESCRIPTION:
H21765
END DESCRIPTION:
XS GIS Cut Line= 3
       2411631.8     13611847.64       2411507.7      13611021.5
      2411358.77     13610525.06
#Sta/Elev= 30
  3908.8  339.52  4011.1  336.55  4111.1  334.33  4189.9  333.23  4204.7  333.83
  4218.9  333.13  4285.6  333.66    4456  332.72  4526.7  333.21  4619.3     332
  4639.5  332.86  4663.1  332.04  4691.6  332.96  4768.8  331.67  4792.8  330.32
  4813.6  327.94  4878.5  326.31  4886.7  325.46    4918  324.58  4959.8  324.62
  4977.6  322.87  4978.3  320.41  4978.8  319.91  4987.5  320.41  5001.6  329.91
  5010.7     335  5015.9  336.82  5115.1  341.11    5177  342.46  5262.5  345.36
#Mann= 9 ,-1 , 0
  3908.8     .05       0  4011.1     .07       0  4111.1    .035       0
  4218.9     .07       0  4526.7     .12       0  4691.6      .1       0
  4978.3     .05       0  4987.5      .1       0    5177     .07       0
Bank Sta=4978.3,4987.5
XS Rating Curve= 0 ,0
Exp/Cntr=0.3,0.1

Type RM Length L Ch R = 1 ,51199   ,487,487,487
BEGIN DESCRIPTION:
WEST ROCKY CREEK 81.0
END DESCRIPTION:
XS GIS Cut Line= 3
        2411675.     13611975.02        2411875.       13610775.
      2411825.01     13610575.03
#Sta/Elev= 30
  3777.4  343.37  3888.1  340.27  4006.3     337  4152.5  333.21  4254.1  332.22
    4406  331.61  4436.4  329.54  4456.7  329.84  4466.8  331.28  4503.3  330.67
  4602.7  326.83    4629   328.6    4662  326.67  4702.1  326.84  4759.9  326.52
  4872.3  323.52  4953.4  324.56  4996.5  323.19  5007.4  319.72  5007.9  319.22
  5016.6  319.72  5024.9  319.91  5035.2  324.52  5053.2  329.54  5058.4  328.01
  5066.1  330.24  5086.7  331.03  5094.5  332.86  5144.7  334.45  5200.1  335.52
#Mann= 11 ,-1 , 0
  3777.4     .07       0  3888.1     .05       0  4006.3    .035       0
  4254.1     .07       0  4503.3     .12       0  4602.7     .07       0
  4702.1     .12       0  4759.9      .1       0  5007.4     .05       0
  5016.6      .1       0  5144.7     .07       0
Bank Sta=5007.4,5016.6
XS Rating Curve= 0 ,0
Exp/Cntr=0.3,0.1

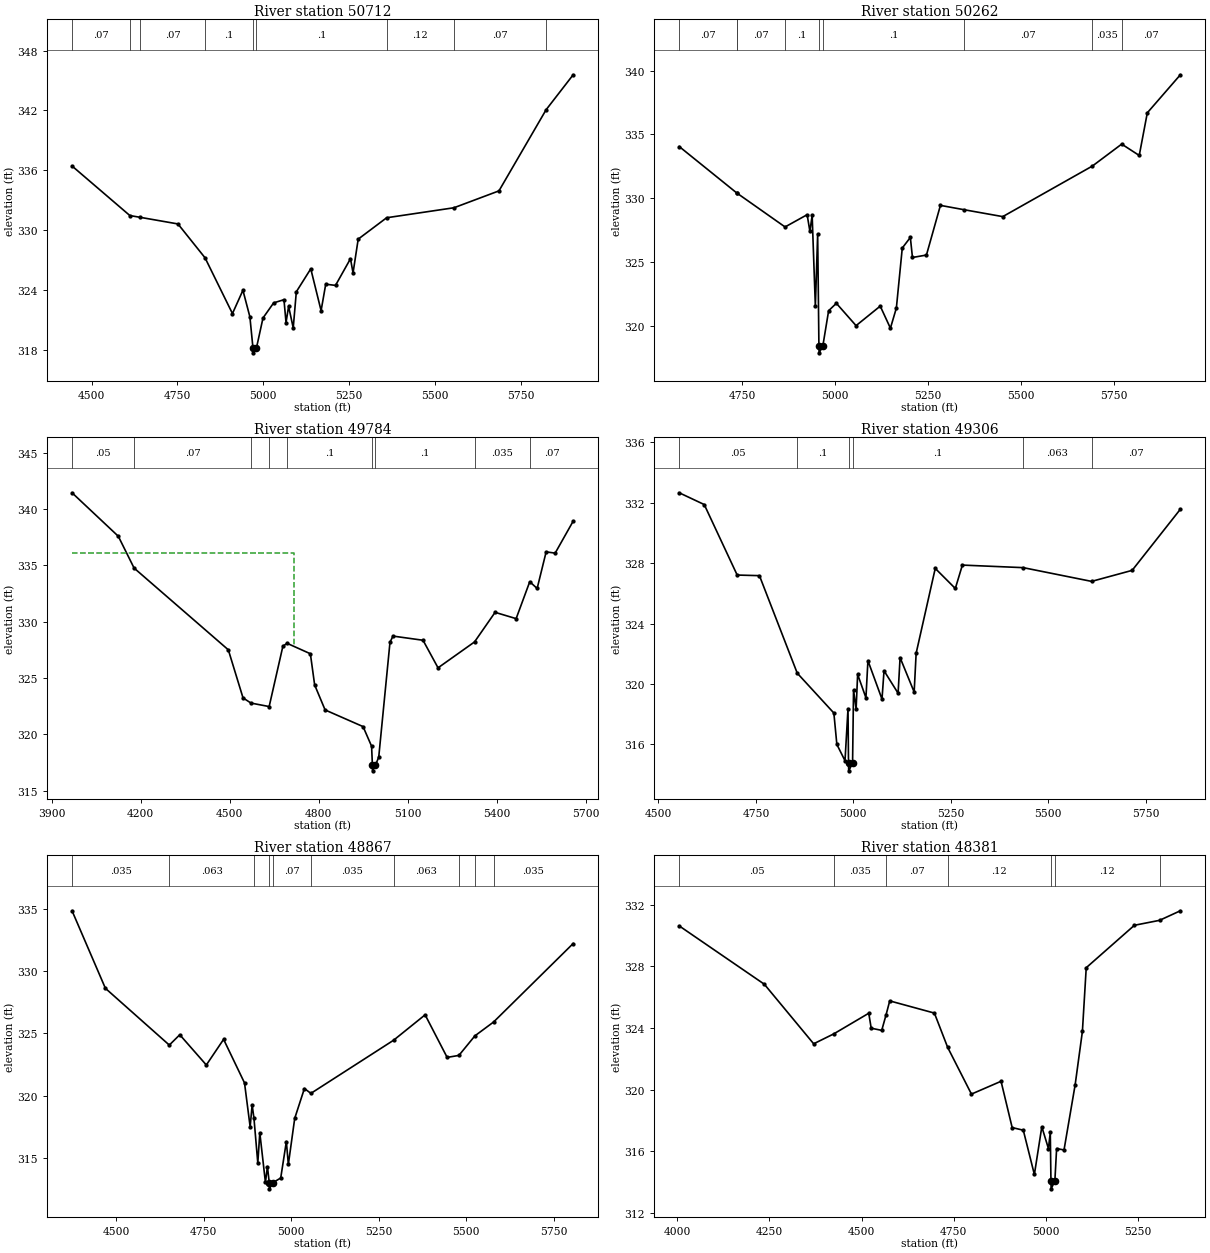
Type RM Length L Ch R = 1 ,50712   ,450,450,450
BEGIN DESCRIPTION:
WEST ROCKY CREEK 80.0
END DESCRIPTION:
XS GIS Cut Line= 3
        2411925.     13611724.98        2412025.       13611175.
      2412525.01     13610424.99
#Sta/Elev= 30
  4442.9  336.44  4611.4  331.48  4642.1   331.3  4751.6  330.64  4830.5  327.25
  4910.4  321.67  4940.9     324  4961.2  321.34  4970.1  318.24  4970.6  317.74
  4980.4  318.24  4999.4  321.23  5030.4  322.74  5060.5  323.06  5066.5  320.77
    5074  322.39  5087.5  320.24  5096.5  323.85  5138.6  326.15  5168.7  321.96
  5182.2  324.61  5210.7  324.49  5254.3  327.16  5261.8  325.74  5276.8  329.12
  5359.7  331.26  5555.8  332.26    5687  333.95  5824.4  342.07  5903.3  345.57
#Mann= 9 ,-1 , 0
  4442.9     .07       0  4611.4    .035       0  4642.1     .07       0
  4830.5      .1       0  4970.1     .05       0  4980.4      .1       0
  5359.7     .12       0  5555.8     .07       0  5824.4    .035       0
Bank Sta=4970.1,4980.4
XS Rating Curve= 0 ,0
Exp/Cntr=0.3,0.1

Type RM Length L Ch R = 1 ,50262   ,478,478,478
BEGIN DESCRIPTION:
WEST ROCKY CREEK 79.0
END DESCRIPTION:
XS GIS Cut Line= 3
        2412075.       13611725.        2412325.       13611375.
        2412775.       13610575.
#Sta/Elev= 30
  4580.7  334.05  4735.2  330.42  4735.6  330.41  4865.4  327.75  4924.8  328.71
  4932.2  327.41  4938.3  328.65  4946.9  321.53  4953.1   327.2  4956.5  318.39
    4957  317.89  4966.8  318.39  4982.6  321.19  5003.4  321.77  5056.4  320.02
  5121.4  321.55  5148.8  319.82  5164.8   321.4  5180.7   326.1  5202.4  326.93
  5208.1  325.36  5245.7  325.55  5283.3  329.44    5347   329.1    5451  328.56
    5692  332.52  5770.9  334.24  5818.1  333.35  5839.8  336.69  5928.7  339.67
#Mann= 9 ,-1 , 0
  4580.7     .07       0  4735.2    .035       0  4735.6     .07       0
  4865.4      .1       0  4956.5     .05       0  4966.8      .1       0
    5347     .07       0    5692    .035       0  5770.9     .07       0
Bank Sta=4956.5,4966.8
XS Rating Curve= 0 ,0
Exp/Cntr=0.3,0.1

Type RM Length L Ch R = 1 ,49784   ,478,478,478
BEGIN DESCRIPTION:
WEST ROCKY CREEK 78.0
END DESCRIPTION:
XS GIS Cut Line= 3
      2412075.01     13612074.99        2412725.       13611275.
        2412825.     13610625.01
#Sta/Elev= 30
  3968.8  341.45  4124.6  337.59  4177.9  334.76  4495.3   327.5  4544.9  323.23
  4571.6  322.77  4632.9  322.46  4679.2  327.82  4693.2  328.08  4771.8  327.15
  4786.2  324.38  4821.4  322.16  4949.3  320.68    4978  318.94  4980.8  317.25
  4981.3  316.75  4991.1  317.25  5002.1  317.97    5040  328.17  5050.1  328.72
  5151.3  328.35  5201.9   325.9  5324.8   328.2  5394.1  330.83    5465  330.27
  5510.9  333.55  5535.8  332.95  5566.1   336.2  5596.5  336.09  5657.2  338.93
#Mann= 9 ,-1 , 0
  3968.8     .05       0  4177.9     .07       0  4571.6      .1       0
  4632.9     .07       0  4693.2      .1       0  4980.8     .05       0
  4991.1      .1       0  5324.8    .035       0  5510.9     .07       0
#XS Ineff= 2 , 0
       0  4715.1  336.09               0
Permanent Ineff=
       F       F
Bank Sta=4980.8,4991.1
XS Rating Curve= 0 ,0
Exp/Cntr=0.3,0.1

Type RM Length L Ch R = 1 ,49306   ,439,439,439
BEGIN DESCRIPTION:
WEST ROCKY CREEK 77.0
END DESCRIPTION:
XS GIS Cut Line= 3
      2412475.02     13611974.98        2412825.       13611675.
      2413025.01     13610874.97
#Sta/Elev= 30
  4553.3  332.66  4617.5  331.88    4702  327.21  4759.1  327.17  4856.1  320.71
    4950  318.07  4957.7  315.99  4978.6  314.91  4986.3  318.36  4987.6  314.74
  4988.1  314.24    4998  314.74  5000.5  319.59  5007.1  318.34    5011  320.63
  5032.3  319.08  5037.4  321.54  5073.5  318.99  5078.7  320.87  5114.8  319.38
  5119.9  321.74    5156  319.46  5161.1  322.03  5210.1  327.65  5261.6  326.32
  5279.7  327.87  5435.9   327.7  5611.2  326.79  5715.2  327.52  5838.9  331.57
#Mann= 6 ,-1 , 0
  4553.3     .05       0  4856.1      .1       0  4987.6     .05       0
    4998      .1       0  5435.9    .063       0  5611.2     .07       0
Bank Sta=4987.6,4998
XS Rating Curve= 0 ,0
Exp/Cntr=0.3,0.1

Type RM Length L Ch R = 1 ,48867   ,486,486,486
BEGIN DESCRIPTION:
WEST ROCKY CREEK 76.0
END DESCRIPTION:
XS GIS Cut Line= 3
      2412775.01     13612224.98        2413075.       13611675.
        2413175.       13610875.
#Sta/Elev= 30
  4373.5  334.85  4468.9  328.62  4651.6  324.06  4681.5  324.89  4757.4  322.46
  4806.8  324.52  4866.6  321.02  4882.7  317.49  4888.4  319.25  4893.6  318.18
  4904.6  314.58  4910.3  317.02  4926.4  313.02  4932.1   314.3  4937.3  313.01
  4937.8  312.51  4947.8  313.01  4970.1  313.38  4986.2  316.31  4991.9  314.47
  5010.1  318.17  5037.8  320.57  5056.4  320.18  5292.8  324.45  5382.9  326.49
  5445.9  323.07  5479.5  323.23  5525.2   324.8  5578.5  325.91  5806.2  332.22
#Mann= 10 ,-1 , 0
  4373.5    .035       0  4651.6    .063       0  4893.6     .07       0
  4937.3     .05       0  4947.8     .07       0  5056.4    .035       0
  5292.8    .063       0  5479.5    .035       0  5525.2     .12       0
  5578.5    .035       0
Bank Sta=4937.3,4947.8
XS Rating Curve= 0 ,0
Exp/Cntr=0.3,0.1

Type RM Length L Ch R = 1 ,48381   ,444,444,444
BEGIN DESCRIPTION:
H21764
END DESCRIPTION:
XS GIS Cut Line= 3
      2412957.91     13612212.85      2413383.39     13611705.82
      2413457.85      13611010.9
#Sta/Elev= 30
  4004.9  330.62    4236  326.84    4370  322.98  4424.4  323.62  4519.6  324.96
  4526.2  323.99  4554.8  323.85  4566.3  324.83  4576.5  325.76  4697.8  324.97
  4733.8  322.75  4798.4  319.72  4878.8  320.55    4909  317.55  4939.2  317.38
  4969.3  314.51  4989.5   317.6  5007.5  316.19  5012.5  317.24  5014.3  314.08
  5014.8  313.58  5024.9  314.08  5029.7  316.19  5049.8   316.1    5080  320.32
  5099.7  323.78  5110.1  327.91  5240.9  330.66  5309.1  330.98  5365.7   331.6
#Mann= 7 ,-1 , 0
  4004.9     .05       0  4424.4    .035       0  4566.3     .07       0
  4733.8     .12       0  5014.3     .05       0  5024.9     .12       0
  5309.1    .035       0
Bank Sta=5014.3,5024.9
XS Rating Curve= 0 ,0
Exp/Cntr=0.3,0.1