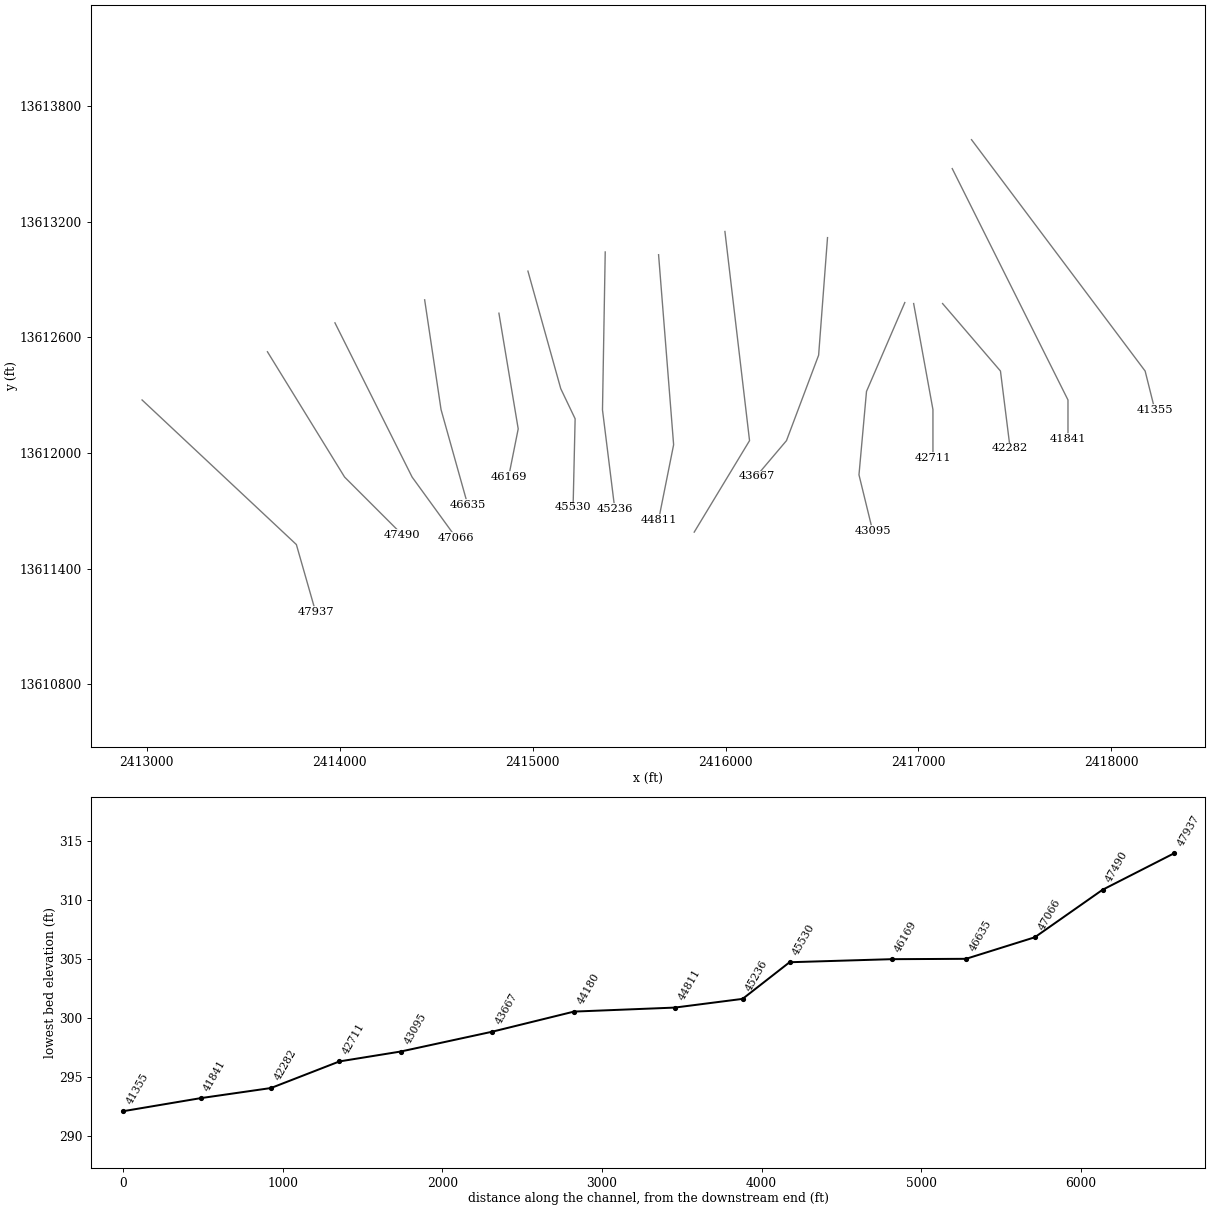
HEC-RAS study WEST ROCKY CREEK.prj: WEST ROCKY CREEK Base Level Engineering

--- WEST ROCKY CREEK.g01 (geometry) --- (continued)

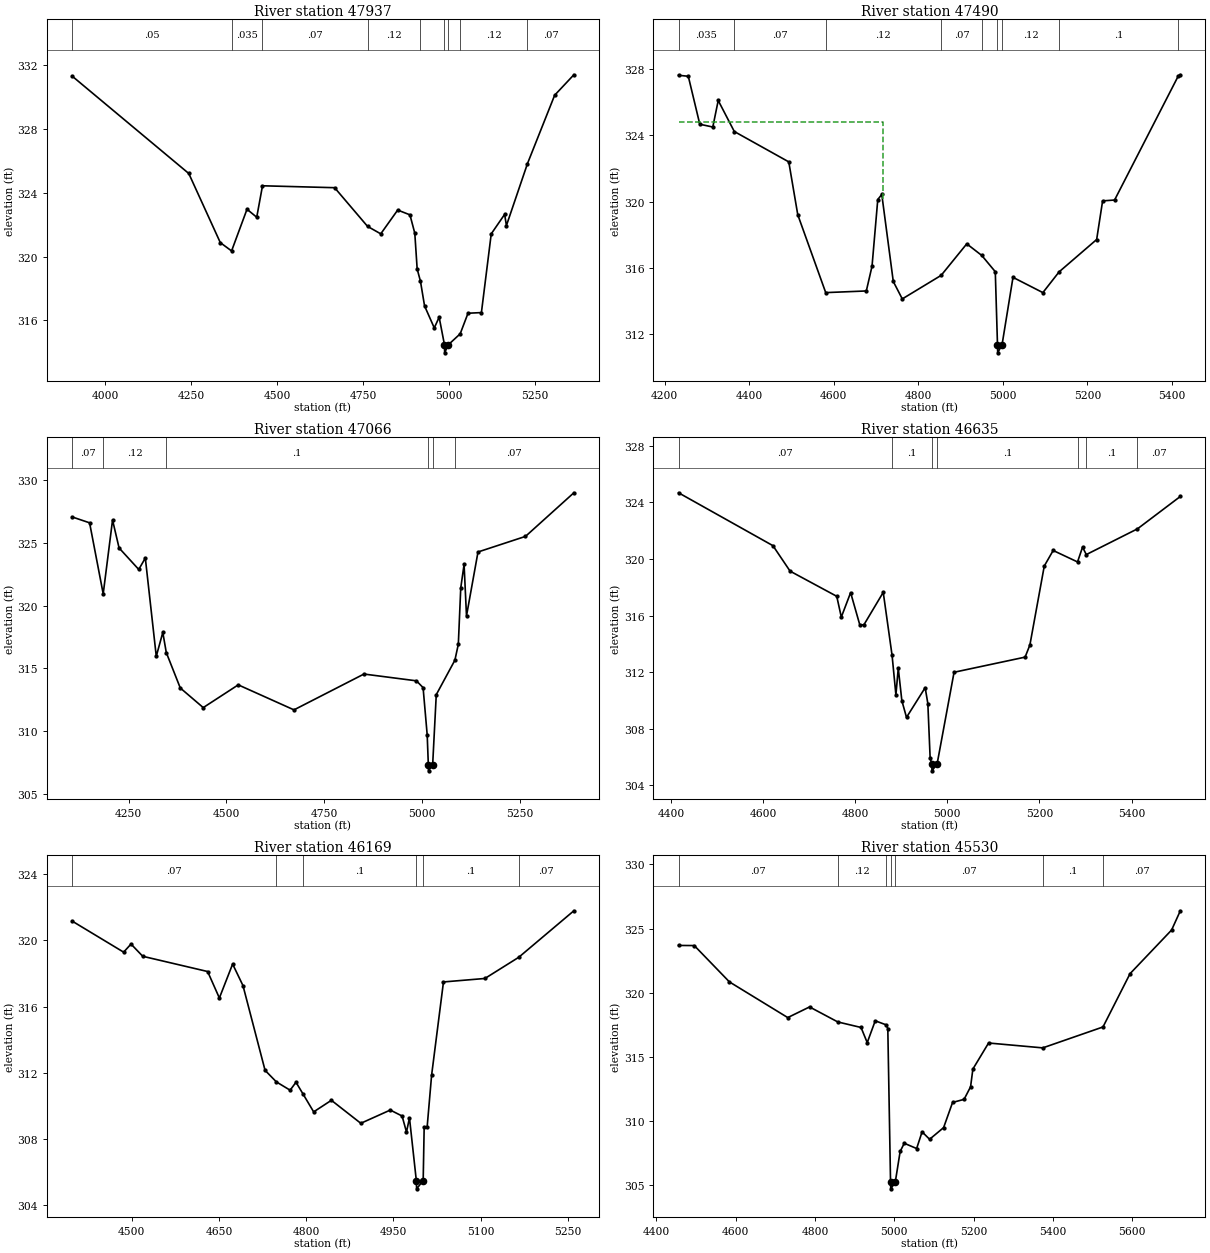
Type RM Length L Ch R = 1 ,47937   ,447,447,447
BEGIN DESCRIPTION:
WEST ROCKY CREEK 75.0
END DESCRIPTION:
XS GIS Cut Line= 3
      2412975.01     13612274.99        2413775.       13611525.
      2413875.01     13611174.97
#Sta/Elev= 30
  3903.3   331.3    4243   325.2  4334.8  320.87  4367.6  320.35  4412.5  322.96
  4440.8  322.46  4457.6  324.43  4667.5  324.31  4763.3  321.89  4801.8  321.42
  4851.1  322.91  4886.8  322.61  4900.9  321.46  4907.8  319.22  4917.4  318.45
  4929.3  316.91  4957.6  315.53  4971.8   316.2  4987.3  314.47  4987.8  313.97
  4998.2  314.47    5033  315.16  5055.8  316.45  5094.8  316.49  5123.4  321.42
  5162.4  322.64  5167.6  321.94  5228.9  325.82    5308   330.1  5363.9  331.38
#Mann= 9 ,-1 , 0
  3903.3     .05       0  4367.6    .035       0  4457.6     .07       0
  4763.3     .12       0  4917.4     .07       0  4987.3     .05       0
  4998.2     .07       0    5033     .12       0  5228.9     .07       0
Bank Sta=4987.3,4998.2
XS Rating Curve= 0 ,0
Exp/Cntr=0.3,0.1

Type RM Length L Ch R = 1 ,47490   ,424,424,424
BEGIN DESCRIPTION:
WEST ROCKY CREEK 74.0
END DESCRIPTION:
XS GIS Cut Line= 3
        2413625.       13612525.        2414025.       13611875.
      2414325.01     13611574.99
#Sta/Elev= 30
  4232.6  327.61  4255.7  327.55  4282.9  324.66  4313.7  324.49  4326.5  326.09
  4364.6  324.22  4493.5  322.39  4514.8   319.2  4580.9  314.51    4677  314.61
  4690.5   316.1  4704.1  320.12  4713.6  320.43  4740.8  315.18  4762.1  314.13
  4854.1  315.55  4914.7  317.45  4950.2  316.75  4982.2  315.77  4987.4  311.38
  4987.9  310.88  4998.3  311.38  5024.1  315.43  5094.8  314.51  5133.2  315.76
  5222.1  317.71  5236.2  320.04  5264.5  320.09  5414.7  327.54  5420.1  327.64
#Mann= 9 ,-1 , 0
  4232.6    .035       0  4364.6     .07       0  4580.9     .12       0
  4854.1     .07       0  4950.2     .12       0  4987.4     .05       0
  4998.3     .12       0  5133.2      .1       0  5414.7     .07       0
#XS Ineff= 2 , 0
       0  4715.5  324.81               0
Permanent Ineff=
       F       F
Bank Sta=4987.4,4998.3
XS Rating Curve= 0 ,0
Exp/Cntr=0.3,0.1

Type RM Length L Ch R = 1 ,47066   ,431,431,431
BEGIN DESCRIPTION:
WEST ROCKY CREEK 73.0
END DESCRIPTION:
XS GIS Cut Line= 3
      2413974.99     13612675.03        2414375.       13611875.
      2414603.11     13611560.47
#Sta/Elev= 30
  4105.5  327.05  4150.3  326.58  4185.1  320.93    4209   326.8  4225.7  324.58
    4276  322.87  4292.8  323.78  4320.8  315.96  4337.5  317.86  4346.4  316.26
  4382.2  313.44  4440.9  311.88  4530.4  313.69  4672.9   311.7  4851.8  314.55
    4986  314.01    5003  313.47  5013.5  309.71  5016.4  307.35  5016.9  306.85
  5027.5  307.35  5036.7  312.91  5084.3  315.65  5093.1  316.92  5099.3   321.4
  5107.8  323.27    5114  319.18  5143.4  324.26  5264.8   325.5  5388.5  328.97
#Mann= 6 ,-1 , 0
  4105.5     .07       0  4185.1     .12       0  4346.4      .1       0
  5016.4     .05       0  5027.5      .1       0  5084.3     .07       0
Bank Sta=5016.4,5027.5
XS Rating Curve= 0 ,0
Exp/Cntr=0.3,0.1

Type RM Length L Ch R = 1 ,46635   ,466,466,466
BEGIN DESCRIPTION:
WEST ROCKY CREEK 72.0
END DESCRIPTION:
XS GIS Cut Line= 3
      2414440.02      13612794.4        2414525.       13612225.
      2414663.41     13611730.62
#Sta/Elev= 30
  4416.6  324.68  4621.5  320.94  4658.7  319.14    4760  317.36  4769.9  315.89
  4790.1  317.62  4810.3  315.31  4819.2  315.36  4860.9  317.64  4880.1  313.18
  4888.4  310.39  4893.5  312.28  4901.3  309.98  4911.4   308.8  4951.9   310.9
  4957.7  309.78  4962.7  305.92  4966.2  305.52  4966.7  305.02  4977.9  305.52
  5014.6  311.99  5168.8  313.06  5179.2  313.92  5210.4   319.5  5229.7   320.6
  5282.6  319.79  5293.5  320.84  5301.6  320.31  5412.7  322.13  5505.7  324.42
#Mann= 7 ,-1 , 0
  4416.6     .07       0  4880.1      .1       0  4966.2     .05       0
  4977.9      .1       0  5282.6     .07       0  5301.6      .1       0
  5412.7     .07       0
Bank Sta=4966.2,4977.9
XS Rating Curve= 0 ,0
Exp/Cntr=0.3,0.1

Type RM Length L Ch R = 1 ,46169   ,639,639,639
BEGIN DESCRIPTION:
WEST ROCKY CREEK 71.0
END DESCRIPTION:
XS GIS Cut Line= 3
        2414825.     13612724.99        2414925.       13612125.
        2414875.     13611875.01
#Sta/Elev= 30
  4397.3  321.17    4486  319.29  4498.7  319.78  4518.9  319.04  4630.5  318.12
  4650.7  316.52  4673.5  318.57  4691.3  317.27  4729.3  312.15  4748.8  311.45
  4772.4  310.95  4782.5  311.43  4794.1  310.75  4812.9  309.64  4843.4  310.34
    4894  308.95  4944.7  309.75    4965  309.39  4972.6  308.42  4977.7  309.28
  4989.5  305.49    4990  304.99  5001.3  305.49    5003  308.72  5008.1  308.72
  5015.8  311.86  5036.2  317.49  5107.5   317.7  5165.7  318.98  5260.5  321.79
#Mann= 6 ,-1 , 0
  4397.3     .07       0  4748.8     .12       0  4794.1      .1       0
  4989.5     .05       0  5001.3      .1       0  5165.7     .07       0
Bank Sta=4989.5,5001.3
XS Rating Curve= 0 ,0
Exp/Cntr=0.3,0.1

Type RM Length L Ch R = 1 ,45530   ,294,294,294
BEGIN DESCRIPTION:
H21763
END DESCRIPTION:
XS GIS Cut Line= 4
      2414975.43     13612943.26      2415145.62     13612333.42
      2415220.08      13612177.4      2415209.49     13611718.25
#Sta/Elev= 30
    4456  323.69  4495.7  323.68  4584.3  320.85  4731.4  318.07  4786.4   318.9
  4857.6  317.73  4916.2   317.3  4931.8  316.12    4952  317.82  4979.9   317.5
  4983.7  317.21  4990.6  305.23  4991.1  304.73  5002.4  305.23  5014.8  307.64
  5025.2  308.28  5056.4  307.87  5070.1  309.17  5089.1  308.59  5124.4   309.5
    5147  311.46    5176   311.7  5192.4  312.68  5198.2  314.06  5237.8  316.09
  5374.4  315.71  5526.3  317.34  5594.5  321.49  5699.3  324.89  5721.3  326.39
#Mann= 7 ,-1 , 0
    4456     .07       0  4857.6     .12       0  4979.9     .07       0
  4990.6     .05       0  5002.4     .07       0  5374.4      .1       0
  5526.3     .07       0
Bank Sta=4990.6,5002.4
XS Rating Curve= 0 ,0
Exp/Cntr=0.3,0.1

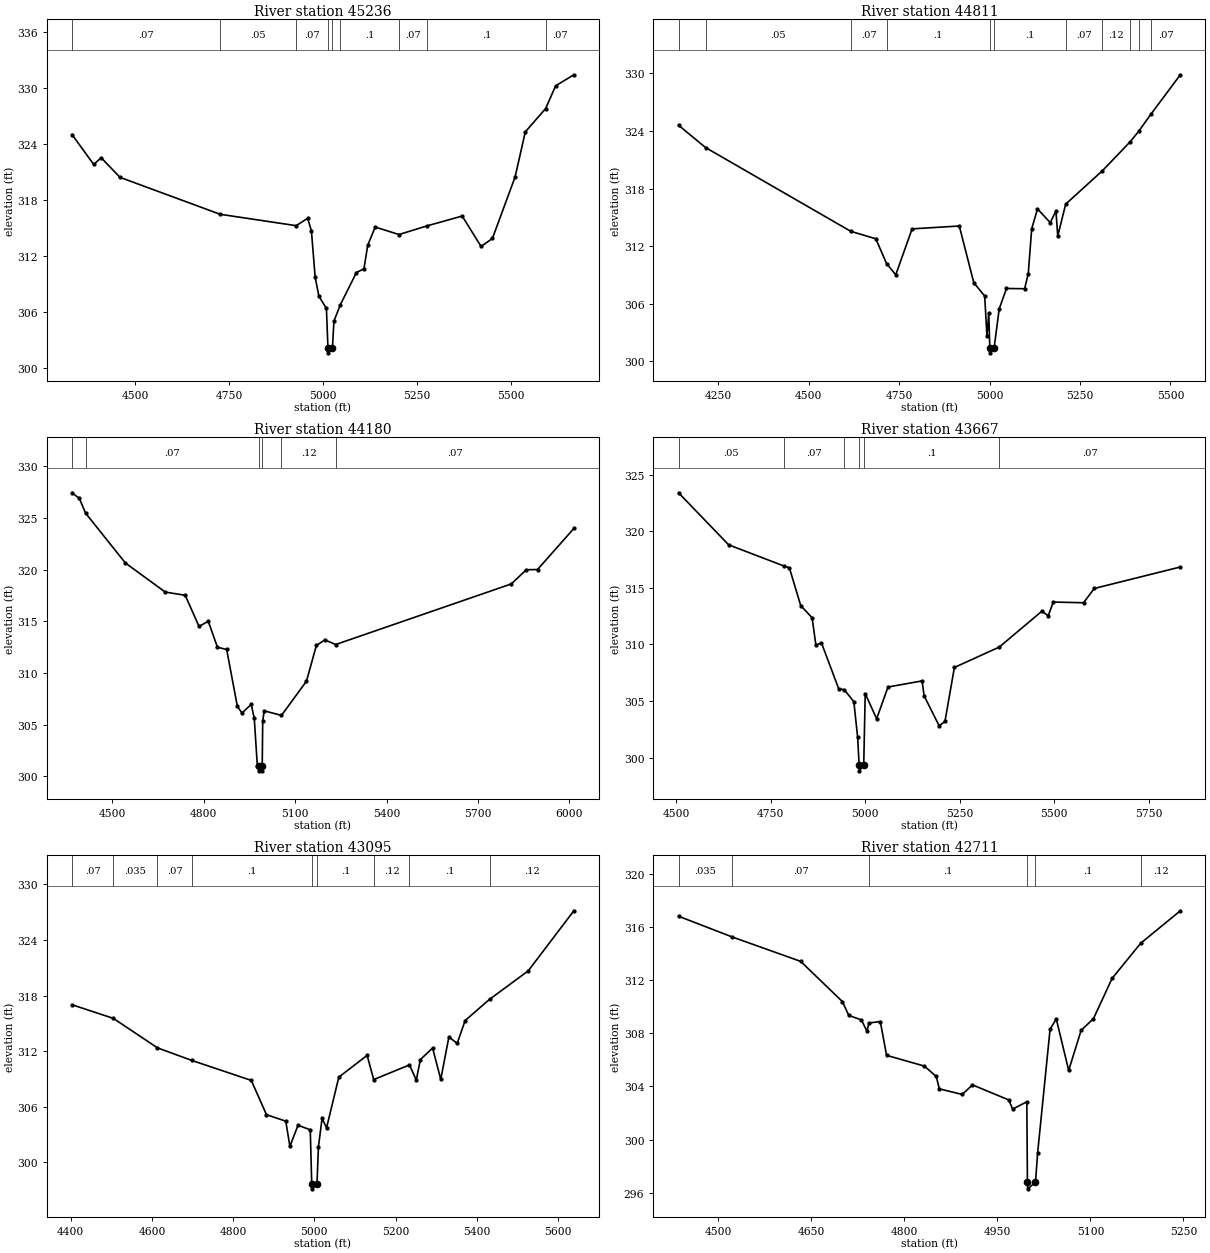
Type RM Length L Ch R = 1 ,45236   ,425,425,425
BEGIN DESCRIPTION:
H21762
END DESCRIPTION:
XS GIS Cut Line= 3
       2415376.1     13613042.61      2415361.91      13612223.5
       2415425.7     13611709.68
#Sta/Elev= 30
  4331.6  325.01  4389.2  321.81  4409.2  322.53  4459.2  320.43  4726.1  316.47
  4928.5  315.25  4959.3  316.03  4969.3  314.71  4979.3  309.72  4989.3  307.68
  5009.3  306.38  5013.4  302.12  5013.9  301.62  5025.3  302.12  5029.3  305.02
  5046.7   306.8  5089.3  310.23  5109.3  310.62  5119.3  313.14  5139.3   315.1
  5202.6   314.3  5278.6  315.24    5371  316.28  5421.4  313.02  5451.6  313.88
  5512.1  320.48  5539.2   325.3  5593.4   327.8  5620.1  330.24  5668.6  331.42
#Mann= 9 ,-1 , 0
  4331.6     .07       0  4726.1     .05       0  4928.5     .07       0
  5013.4     .05       0  5025.3     .07       0  5046.7      .1       0
  5202.6     .07       0  5278.6      .1       0  5593.4     .07       0
Bank Sta=5013.4,5025.3
XS Rating Curve= 0 ,0
Exp/Cntr=0.3,0.1

Type RM Length L Ch R = 1 ,44811   ,631,631,631
BEGIN DESCRIPTION:
H21761
END DESCRIPTION:
XS GIS Cut Line= 3
      2415652.66     13613028.38      2415730.67     13612042.67
      2415652.65     13611652.59
#Sta/Elev= 30
  4140.7   324.6  4215.6  322.27  4616.9  313.54  4685.8  312.77  4715.5  310.19
  4740.9  309.01  4786.1   313.8  4916.5   314.1  4956.6  308.19  4986.7   306.8
    4993  302.62    4998  305.05  5000.8  301.38  5001.3  300.88  5012.7  301.38
  5026.8  305.46  5046.9  307.59  5097.1  307.56  5107.1  309.14  5116.6   313.8
  5132.6  315.88  5167.9  314.45  5183.6  315.67  5188.6  313.05  5210.5  316.38
  5311.5  319.84  5389.1  322.89  5412.6  323.99  5446.4  325.77  5527.3  329.86
#Mann= 11 ,-1 , 0
  4140.7     .07       0  4215.6     .05       0  4616.9     .07       0
  4715.5      .1       0  5000.8     .05       0  5012.7      .1       0
  5210.5     .07       0  5311.5     .12       0  5389.1     .07       0
  5412.6     .12       0  5446.4     .07       0
Bank Sta=5000.8,5012.7
XS Rating Curve= 0 ,0
Exp/Cntr=0.3,0.1

Type RM Length L Ch R = 1 ,44180   ,513,513,513
BEGIN DESCRIPTION:
H21760
END DESCRIPTION:
XS GIS Cut Line= 3
       2415996.6     13613148.88      2416124.24     13612063.94
      2415837.41     13611589.42
#Sta/Elev= 30
  4367.9  327.42  4391.9  326.87    4412  325.46    4543  320.63  4673.9  317.82
  4739.3  317.51  4784.6   314.5  4814.8     315  4845.1  312.49  4875.3  312.27
  4910.5  306.76  4925.6  306.13  4955.8  306.96  4965.9  305.61  4975.9  301.05
    4980  301.04  4980.5  300.54  4991.5  300.54    4992  301.04  4993.6  305.37
  4998.6  306.34  5055.2   305.9  5137.1   309.2  5169.8  312.66  5197.5   313.2
  5233.1  312.75  5809.6  318.61  5858.7  319.98  5895.5     320  6014.8  323.97
#Mann= 6 ,-1 , 0
  4367.9     .05       0    4412     .07       0    4980     .05       0
    4992     .07       0  5055.2     .12       0  5233.1     .07       0
Bank Sta=4980,4992
XS Rating Curve= 0 ,0
Exp/Cntr=0.3,0.1

Type RM Length L Ch R = 1 ,43667   ,572,572,572
BEGIN DESCRIPTION:
H21759
END DESCRIPTION:
XS GIS Cut Line= 4
      2416528.46       13613117.      2416482.36     13612507.16
      2416315.71     13612063.94      2416160.04     13611879.96
#Sta/Elev= 30
  4506.8  323.41  4639.2  318.81  4785.1  316.94  4799.6  316.79  4829.7  313.44
  4859.8  312.36  4869.8  309.94  4884.4  310.15    4930  306.09  4944.8     306
  4970.1  304.94  4980.1   301.8  4984.1  299.33  4984.6  298.83  4996.2  299.33
  5000.2  305.66  5030.3  303.43  5060.4  306.24  5150.5  306.78  5155.8  305.46
  5195.5  302.81  5210.9   303.2  5235.8  307.97  5354.4  309.77    5467  312.94
  5483.9  312.54  5497.2  313.75  5577.2  313.69  5605.4  314.95  5832.9  316.85
#Mann= 6 ,-1 , 0
  4506.8     .05       0  4785.1     .07       0  4944.8      .1       0
  4984.1     .05       0  4996.2      .1       0  5354.4     .07       0
Bank Sta=4984.1,4996.2
XS Rating Curve= 0 ,0
Exp/Cntr=0.3,0.1

Type RM Length L Ch R = 1 ,43095   ,384,384,384
BEGIN DESCRIPTION:
H21758
END DESCRIPTION:
XS GIS Cut Line= 4
      2416929.13     13612780.18      2416730.56     13612319.23
      2416691.56     13611886.65      2416762.48     13611595.91
#Sta/Elev= 30
  4403.4  317.01  4505.1  315.54  4613.7  312.36  4697.8  311.01  4844.6  308.85
  4882.1  305.15  4929.6  304.45  4939.7  301.73  4959.7  304.01  4989.9  303.52
  4993.5  297.65    4994  297.15  5006.4  297.65    5010  301.68    5019  304.76
    5030  303.73  5060.2   309.2  5129.9  311.55    5146  308.94  5234.2  310.52
  5250.9  308.88    5261   311.1  5291.1  312.34  5311.2  308.96  5331.2  313.54
  5351.6  312.84  5371.2  315.31  5431.2  317.59  5526.6  320.67  5638.9  327.15
#Mann= 9 ,-1 , 0
  4403.4     .07       0  4505.1    .035       0  4613.7     .07       0
  4697.8      .1       0  4993.5     .05       0  5006.4      .1       0
    5146     .12       0  5234.2      .1       0  5431.2     .12       0
Bank Sta=4993.5,5006.4
XS Rating Curve= 0 ,0
Exp/Cntr=0.3,0.1

Type RM Length L Ch R = 1 ,42711   ,429,429,429
BEGIN DESCRIPTION:
WEST ROCKY CREEK 64.0
END DESCRIPTION:
XS GIS Cut Line= 3
        2416975.       13612775.        2417075.       13612225.
        2417075.     13611975.02
#Sta/Elev= 30
  4435.9  316.79  4522.6  315.23  4632.8   313.4  4700.2  310.37  4710.3  309.34
  4730.7     309  4739.6  308.16  4742.9  308.77  4761.2  308.88  4771.3  306.34
  4832.3  305.53  4851.4  304.75  4856.4  303.82  4893.3   303.4  4909.8  304.12
  4968.2  302.99  4974.6   302.3  4997.4  302.85  4998.4  296.81  4998.9  296.31
  5011.4  296.81  5014.9  299.04  5034.9   308.3  5044.9  309.08  5064.9  305.21
  5084.9  308.21  5104.9   309.1  5134.9  312.12    5181  314.76  5244.9   317.2
#Mann= 6 ,-1 , 0
  4435.9    .035       0  4522.6     .07       0  4742.9      .1       0
  4998.4     .05       0  5011.4      .1       0    5181     .12       0
Bank Sta=4998.4,5011.4
XS Rating Curve= 0 ,0
Exp/Cntr=0.3,0.1

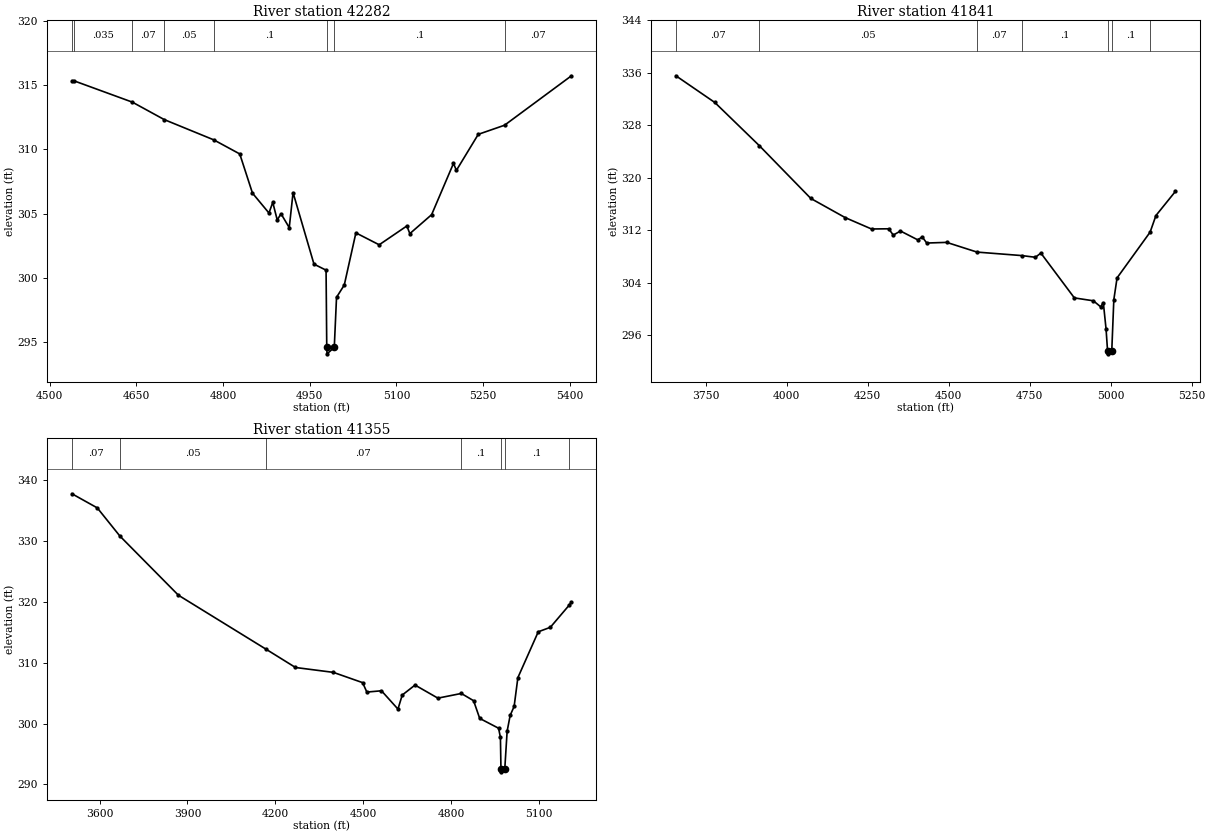
Type RM Length L Ch R = 1 ,42282   ,441,441,441
BEGIN DESCRIPTION:
WEST ROCKY CREEK 63.0
END DESCRIPTION:
XS GIS Cut Line= 3
      2417124.98     13612775.02        2417425.       13612425.
        2417475.     13612025.01
#Sta/Elev= 30
  4538.7  315.36    4542  315.36  4643.3  313.69  4698.4  312.33    4784  310.75
    4829  309.65    4851  306.59  4879.5  305.04  4886.1  305.87  4893.8   304.5
  4900.4  304.98  4914.6   303.9  4921.2  306.63  4957.4  301.05  4978.3  300.58
  4979.5  294.55    4980  294.05  4992.5  294.55  4996.4  298.46  5009.8  299.42
  5029.9  303.49  5070.2  302.56  5118.1  304.03  5123.2  303.43  5160.9  304.91
  5198.7  308.91  5203.8  308.37  5241.6  311.18    5287  311.89  5402.8  315.75
#Mann= 8 ,-1 , 0
  4538.7     .07       0    4542    .035       0  4643.3     .07       0
  4698.4     .05       0    4784      .1       0  4979.5     .05       0
  4992.5      .1       0    5287     .07       0
Bank Sta=4979.5,4992.5
XS Rating Curve= 0 ,0
Exp/Cntr=0.3,0.1

Type RM Length L Ch R = 1 ,41841   ,486,486,486
BEGIN DESCRIPTION:
WEST ROCKY CREEK 62.0
END DESCRIPTION:
XS GIS Cut Line= 3
      2417174.99     13613475.03        2417775.       13612275.
        2417775.     13612074.97
#Sta/Elev= 30
  3657.9  335.55  3778.1  331.48  3915.3  324.91  4074.4  316.86  4180.6  313.94
  4261.7  312.21  4314.8  312.24  4328.8  311.28  4351.1   311.9  4404.2  310.56
  4418.2     311  4432.2  310.07  4493.7  310.17  4587.4  308.69  4725.4  308.16
  4767.6   307.9  4784.4  308.54  4887.8  301.71  4946.5  301.27  4968.8  300.36
  4977.2  300.98  4985.6  296.99  4990.2  293.69  4990.7  293.19  5003.3  293.69
  5009.6  301.44  5019.6  304.76  5121.6  311.73  5139.6  314.26  5199.6  317.93
#Mann= 7 ,-1 , 0
  3657.9     .07       0  3915.3     .05       0  4587.4     .07       0
  4725.4      .1       0  4990.2     .05       0  5003.3      .1       0
  5121.6     .12       0
Bank Sta=4990.2,5003.3
XS Rating Curve= 0 ,0
Exp/Cntr=0.3,0.1

Type RM Length L Ch R = 1 ,41355   ,659,659,659
BEGIN DESCRIPTION:
WEST ROCKY CREEK 61.0
END DESCRIPTION:
XS GIS Cut Line= 3
      2417274.97     13613625.04        2418175.       13612425.
        2418225.       13612225.
#Sta/Elev= 30
  3505.4  337.81  3591.9  335.49  3669.1  330.86    3869  321.13  4166.6   312.3
    4269  309.24  4398.2  308.44  4498.2  306.75  4512.7   305.2  4562.7  305.41
    4619   302.4  4633.6  304.71  4677.3  306.35  4755.4   304.2  4835.4  304.97
  4877.3  303.78  4898.2  300.87  4962.7  299.25    4969  297.74  4970.8  292.58
  4971.3  292.08  4983.9  292.58  4991.9  298.75  5002.3  301.37  5015.8  302.83
  5028.6  307.57  5098.2  315.11  5139.5  315.85  5203.7  319.48  5211.6     320
#Mann= 7 ,-1 , 0
  3505.4     .07       0  3669.1     .05       0  4166.6     .07       0
  4835.4      .1       0  4970.8     .05       0  4983.9      .1       0
  5203.7     .07       0
Bank Sta=4970.8,4983.9
XS Rating Curve= 0 ,0
Exp/Cntr=0.3,0.1