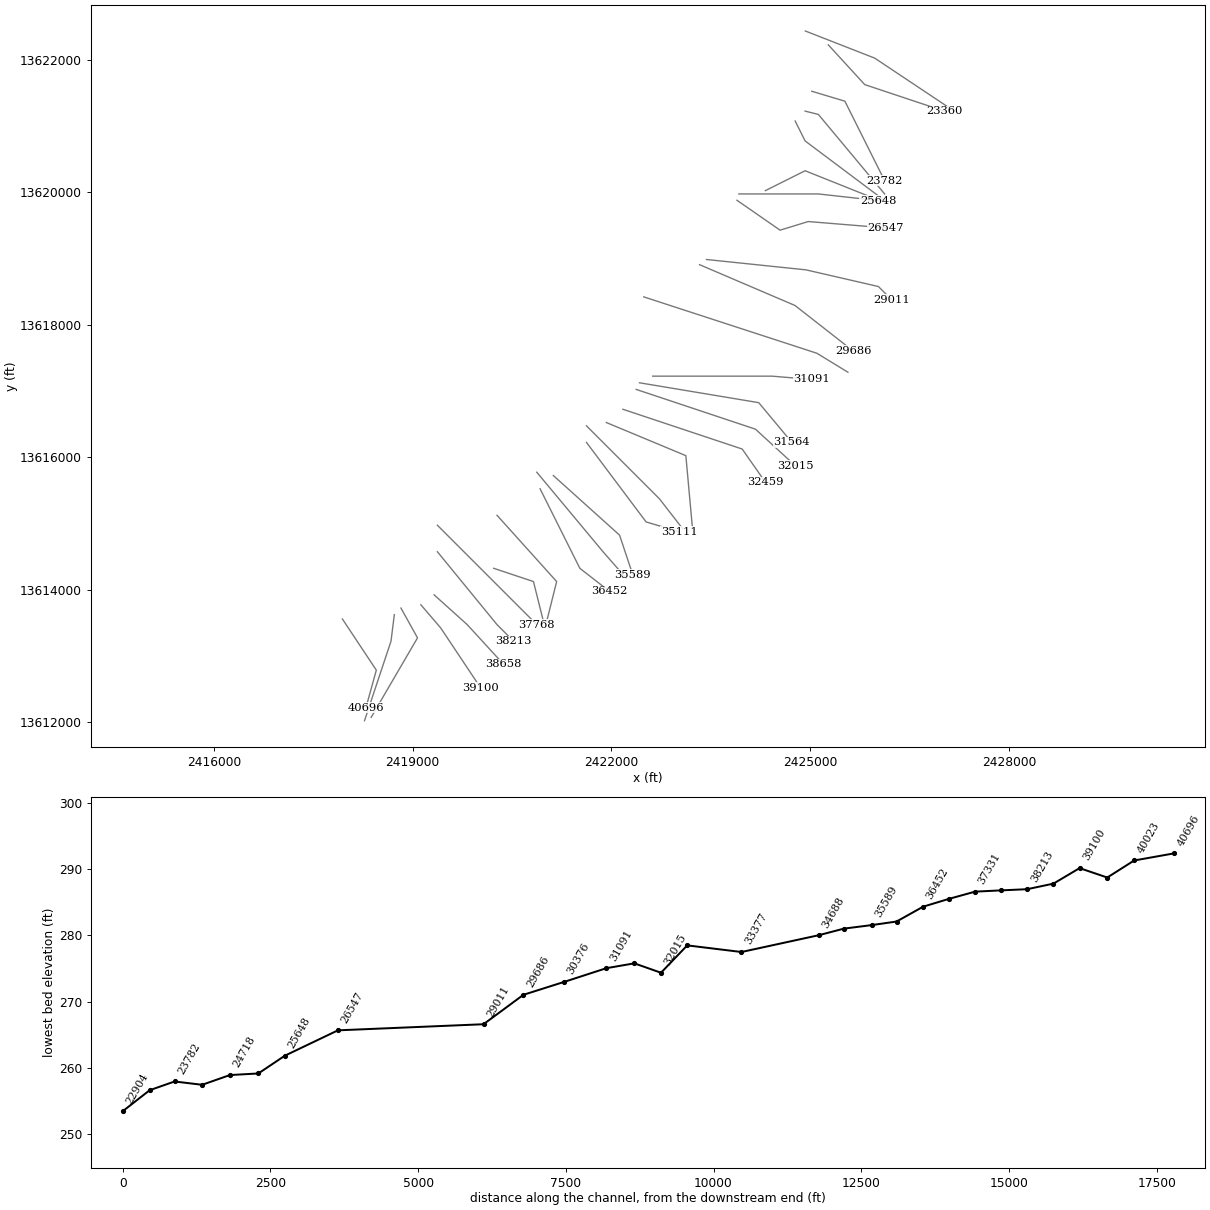
HEC-RAS study WEST ROCKY CREEK.prj: WEST ROCKY CREEK Base Level Engineering

--- WEST ROCKY CREEK.g01 (geometry) --- (continued)

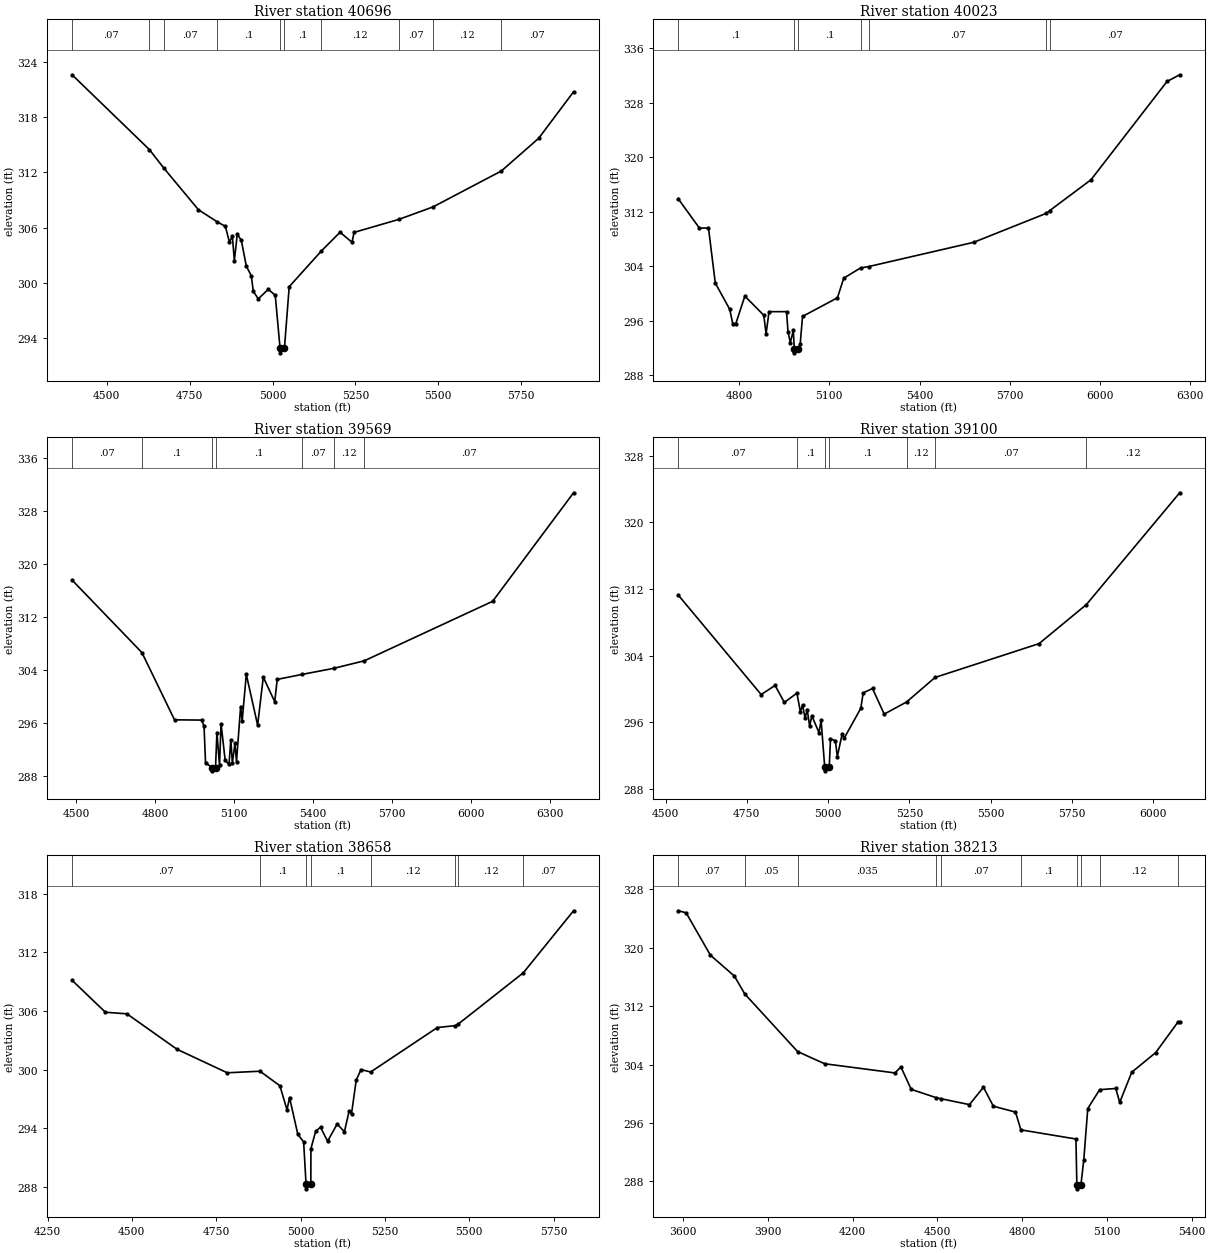
Type RM Length L Ch R = 1 ,40696   ,673,673,673
BEGIN DESCRIPTION:
H21757
END DESCRIPTION:
XS GIS Cut Line= 3
      2417941.08     13613560.29      2418453.25     13612787.68
      2418297.01     13612223.47
#Sta/Elev= 30
  4395.3   322.6  4628.6  314.47  4671.1   312.5  4776.5  307.93  4833.4  306.61
  4857.6  306.13  4869.7  304.44  4878.8  305.03  4884.8   302.4  4893.6  305.28
  4905.8   304.6  4920.9   301.8  4935.9  300.75  4941.9  299.06    4957  298.25
  4987.1  299.28  5008.1  298.64  5022.6  292.88  5023.1  292.38  5035.8  292.88
  5050.2  299.57  5147.2  303.45  5203.6  305.49  5239.7  304.39  5245.7  305.47
  5380.6  306.88  5483.9  308.24  5689.8  312.14  5802.4  315.69  5907.7  320.75
#Mann= 10 ,-1 , 0
  4395.3     .07       0  4628.6     .05       0  4671.1     .07       0
  4833.4      .1       0  5022.6     .05       0  5035.8      .1       0
  5147.2     .12       0  5380.6     .07       0  5483.9     .12       0
  5689.8     .07       0
Bank Sta=5022.6,5035.8
XS Rating Curve= 0 ,0
Exp/Cntr=0.3,0.1

Type RM Length L Ch R = 1 ,40023   ,454,454,454
BEGIN DESCRIPTION:
WEST ROCKY CREEK 60.0
END DESCRIPTION:
XS GIS Cut Line= 3
        2418725.       13613625.        2418675.       13613225.
      2418275.01     13612025.02
#Sta/Elev= 30
  4597.3  313.91  4667.8  309.61  4698.1  309.61  4720.7  301.54  4768.6  297.71
  4778.7   295.6  4788.8  295.57    4819  299.63    4882  296.82  4889.6  294.13
  4899.6  297.35  4957.6  297.35  4962.6  294.42  4970.2   292.8  4980.3   294.6
  4983.5  291.81    4984  291.31  4997.1  291.81    5003  292.56  5010.9  296.65
  5126.9  299.38    5148  302.26  5203.8  303.76  5231.6  303.97  5580.2  307.52
  5821.2  311.76    5833  312.17  5970.2  316.69  6223.2  331.11  6265.3  332.09
#Mann= 7 ,-1 , 0
  4597.3      .1       0  4983.5     .05       0  4997.1      .1       0
  5203.8     .12       0  5231.6     .07       0  5821.2     .12       0
    5833     .07       0
Bank Sta=4983.5,4997.1
XS Rating Curve= 0 ,0
Exp/Cntr=0.3,0.1

Type RM Length L Ch R = 1 ,39569   ,469,469,469
BEGIN DESCRIPTION:
WEST ROCKY CREEK 59.0
END DESCRIPTION:
XS GIS Cut Line= 3
      2418824.98     13613725.03        2419075.       13613275.
      2418374.98     13612074.97
#Sta/Elev= 30
  4484.2  317.57  4749.5  306.61  4873.2  296.45  4976.1  296.41  4985.3   295.5
    4991  289.97  5015.3  289.24  5015.8  288.74    5029  289.24  5034.2  294.53
  5044.1  289.59  5049.9  295.87  5065.6  290.31  5080.1  289.71  5087.1  293.45
  5092.9   289.9  5102.8  292.89  5108.6  290.15  5124.3  298.46  5130.1   296.3
  5145.8  303.31  5188.8  295.65  5210.3   302.9  5253.7  299.19  5263.2  302.56
  5356.1   303.3  5477.9  304.23    5594  305.37  6081.1  314.36  6388.3  330.76
#Mann= 7 ,-1 , 0
  4484.2     .07       0  4749.5      .1       0  5015.3     .05       0
    5029      .1       0  5356.1     .07       0  5477.9     .12       0
    5594     .07       0
Bank Sta=5015.3,5029
XS Rating Curve= 0 ,0
Exp/Cntr=0.3,0.1

Type RM Length L Ch R = 1 ,39100   ,442,442,442
BEGIN DESCRIPTION:
WEST ROCKY CREEK 58.0
END DESCRIPTION:
XS GIS Cut Line= 3
      2419125.01     13613774.99        2419425.       13613425.
      2420024.98     13612525.03
#Sta/Elev= 30
    4539  311.27  4794.2  299.32    4837  300.41  4865.5  298.37  4904.2  299.49
  4914.9  297.24  4921.5  298.07  4929.2  296.48  4935.8  297.52  4943.4  295.51
    4950  296.77    4972  294.76  4978.6  296.23  4989.6  290.66  4990.1  290.16
  5003.7  290.66  5007.5  294.02  5022.5  293.77  5028.5  291.87  5043.5  294.63
  5049.5  294.07  5100.6  297.66  5108.1  299.52  5136.7  300.05  5172.7  296.97
  5241.7  298.43  5329.1  301.37    5649  305.43  5794.6  310.12  6081.6  323.54
#Mann= 7 ,-1 , 0
    4539     .07       0  4904.2      .1       0  4989.6     .05       0
  5003.7      .1       0  5241.7     .12       0  5329.1     .07       0
  5794.6     .12       0
Bank Sta=4989.6,5003.7
XS Rating Curve= 0 ,0
Exp/Cntr=0.3,0.1

Type RM Length L Ch R = 1 ,38658   ,445,445,445
BEGIN DESCRIPTION:
WEST ROCKY CREEK 57.0
END DESCRIPTION:
XS GIS Cut Line= 3
      2419325.01     13613924.99        2419825.       13613475.
      2420374.99     13612875.01
#Sta/Elev= 30
  4322.7  309.15  4421.7  305.88  4485.3  305.72    4634  302.09  4782.7  299.69
  4879.9  299.85  4938.9  298.36  4959.9  295.89  4967.3  297.16    4992  293.39
  5009.2  292.62  5016.3  288.32  5016.8  287.82  5030.5  288.32  5030.8  291.94
    5045  293.72  5059.2  294.12  5080.2  292.69  5108.5  294.45  5130.1  293.66
  5144.3  295.82  5151.1   295.5  5165.2  298.96  5179.4  300.02  5207.8  299.77
  5405.7  304.32  5458.6  304.51  5466.2  304.64  5660.2  309.91  5809.3  316.26
#Mann= 8 ,-1 , 0
  4322.7     .07       0  4879.9      .1       0  5016.3     .05       0
  5030.5      .1       0  5207.8     .12       0  5458.6     .07       0
  5466.2     .12       0  5660.2     .07       0
Bank Sta=5016.3,5030.5
XS Rating Curve= 0 ,0
Exp/Cntr=0.3,0.1

Type RM Length L Ch R = 1 ,38213   ,445,445,445
BEGIN DESCRIPTION:
WEST ROCKY CREEK 56.0
END DESCRIPTION:
XS GIS Cut Line= 3
      2419375.03     13614574.97        2420275.       13613475.
      2420525.02     13613224.98
#Sta/Elev= 30
  3582.7  325.08  3610.7  324.81  3696.8  318.99  3781.5  316.14  3818.2  313.69
  4005.2  305.79  4100.9  304.12    4350  302.86  4370.8  303.69  4407.4  300.61
  4495.9  299.47  4511.2  299.34  4613.4  298.52    4663   300.9  4698.1   298.3
  4776.4   297.5  4795.5  295.06  4990.3  293.81  4993.6  287.48  4994.1  286.98
  5007.8  287.48  5018.1  290.95  5032.2  297.98  5074.3  300.57  5131.2  300.73
  5145.3  298.83  5187.8  302.95  5272.6  305.65  5350.8   309.8  5357.5  309.89
#Mann= 10 ,-1 , 0
  3582.7     .07       0  3818.2     .05       0  4005.2    .035       0
  4495.9     .05       0  4511.2     .07       0  4795.5      .1       0
  4993.6     .05       0  5007.8      .1       0  5074.3     .12       0
  5350.8     .07       0
Bank Sta=4993.6,5007.8
XS Rating Curve= 0 ,0
Exp/Cntr=0.3,0.1

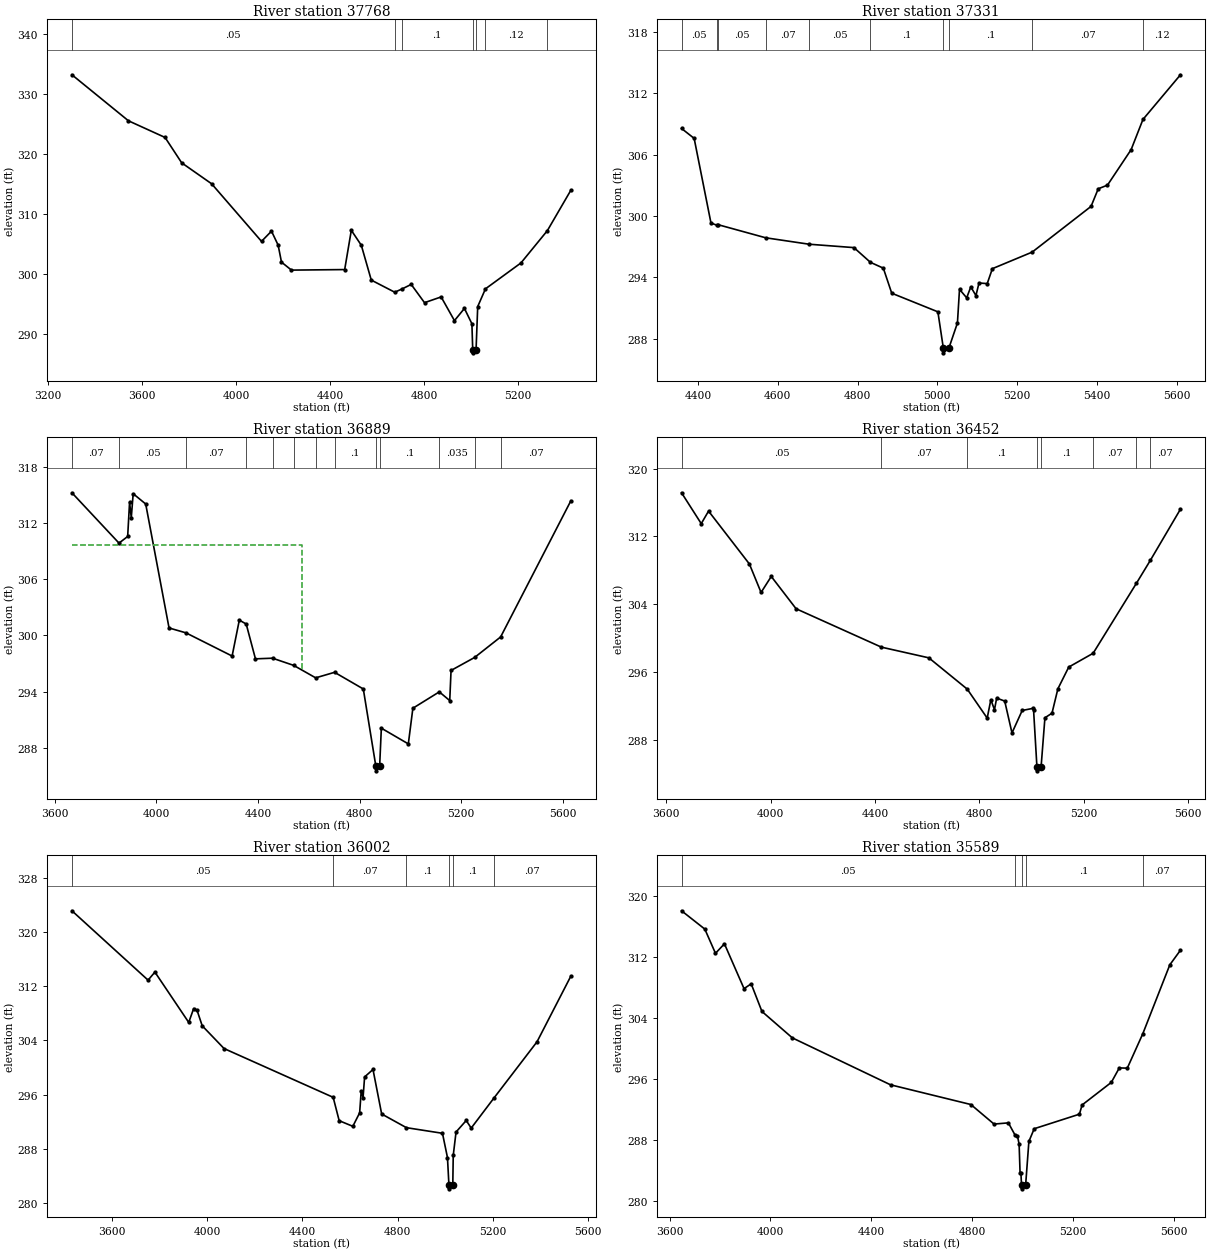
Type RM Length L Ch R = 1 ,37768   ,437,437,437
BEGIN DESCRIPTION:
WEST ROCKY CREEK 55.0
END DESCRIPTION:
XS GIS Cut Line= 3
      2419374.99     13614975.01        2420575.       13613775.
      2420874.98     13613475.02
#Sta/Elev= 30
  3302.7  333.25  3543.1  325.56  3698.7  322.78  3769.4  318.54  3896.7  315.04
  4108.8  305.42  4151.2  307.13  4179.5  304.79  4193.7  301.95  4236.1  300.62
  4462.4  300.71  4490.6  307.27  4533.1  304.77  4575.5  298.95  4675.1  296.93
  4705.1  297.45  4745.2  298.23  4801.8  295.18  4872.5  296.14  4929.1  292.18
  4971.5  294.22  5003.3  291.66  5006.8   287.3  5007.3   286.8    5021   287.3
    5028  294.53  5060.9  297.49  5211.9  301.82  5324.1  307.21    5424  313.96
#Mann= 7 ,-1 , 0
  3302.7     .05       0  4675.1     .07       0  4705.1      .1       0
  5006.8     .05       0    5021      .1       0  5060.9     .12       0
  5324.1     .07       0
Bank Sta=5006.8,5021
XS Rating Curve= 0 ,0
Exp/Cntr=0.3,0.1

Type RM Length L Ch R = 1 ,37331   ,442,442,442
BEGIN DESCRIPTION:
WEST ROCKY CREEK 54.0
END DESCRIPTION:
XS GIS Cut Line= 3
      2420225.03     13614324.99        2420825.       13614125.
        2420975.     13613524.99
#Sta/Elev= 30
  4358.8  308.55  4390.4  307.58  4432.6   299.3  4446.8   299.1  4450.5  299.14
  4569.8  297.86  4678.9  297.23    4791   296.9  4832.4  295.46  4864.7  294.89
  4885.8  292.44  5001.5  290.62    5015  287.11  5015.5  286.61  5029.4  287.11
  5050.5  289.53  5055.7  292.82  5073.7  291.99    5084  293.06  5096.9  292.21
  5104.6  293.44  5125.2  293.38  5138.1  294.84  5237.9  296.46  5385.5  300.93
  5403.5  302.65  5426.7  303.01    5486  306.48  5515.6  309.43  5609.7   313.8
#Mann= 10 ,-1 , 0
  4358.8     .05       0  4446.8     .07       0  4450.5     .05       0
  4569.8     .07       0  4678.9     .05       0  4832.4      .1       0
    5015     .05       0  5029.4      .1       0  5237.9     .07       0
  5515.6     .12       0
Bank Sta=5015,5029.4
XS Rating Curve= 0 ,0
Exp/Cntr=0.3,0.1

Type RM Length L Ch R = 1 ,36889   ,437,437,437
BEGIN DESCRIPTION:
WEST ROCKY CREEK 53.0
END DESCRIPTION:
XS GIS Cut Line= 3
      2420274.99     13615125.01        2421175.       13614125.
      2421025.01     13613525.04
#Sta/Elev= 30
  3667.6  315.24  3852.9  309.86    3887  310.57  3894.5  314.23  3901.2  312.57
  3908.7  315.14    3958  314.04  4049.9  300.79  4116.3  300.27  4298.1  297.79
  4326.5  301.63  4353.6  301.21    4390  297.49  4457.2  297.56  4540.6  296.79
    4627  295.46  4701.4  296.05  4814.5  294.27  4863.8  286.02  4864.3  285.52
  4878.8  286.02  4885.5  290.08  4991.7   288.4  5009.6  292.21  5113.6  293.96
  5154.7  293.03  5159.9  296.25  5252.7  297.64    5355  299.83  5631.4  314.38
#Mann= 13 ,-1 , 0
  3667.6     .07       0  3852.9     .05       0  4116.3     .07       0
  4353.6      .1       0  4457.2     .07       0  4540.6      .1       0
    4627     .07       0  4701.4      .1       0  4863.8     .05       0
  4878.8      .1       0  5113.6    .035       0  5252.7      .1       0
    5355     .07       0
#XS Ineff= 2 , 0
       0    4573  309.67               0
Permanent Ineff=
       F       F
Bank Sta=4863.8,4878.8
XS Rating Curve= 0 ,0
Exp/Cntr=0.3,0.1

Type RM Length L Ch R = 1 ,36452   ,450,450,450
BEGIN DESCRIPTION:
WEST ROCKY CREEK 52.0
END DESCRIPTION:
XS GIS Cut Line= 3
      2420924.98     13615525.03        2421525.       13614325.
      2421975.03     13613974.98
#Sta/Elev= 30
  3658.3  317.14  3733.8   313.5  3761.8  314.98  3918.3  308.74    3963  305.38
  4002.1  307.27  4097.2  303.46  4424.1  298.93  4605.9  297.67    4753  293.98
  4829.5  290.56  4843.5  292.73  4857.4  291.55  4865.8  292.92  4896.6  292.57
  4924.5  288.81  4963.6  291.46  5003.1   291.7  5007.2  291.52    5020  284.84
  5020.5  284.34  5036.1  284.84  5050.7   290.6  5077.8  291.14  5100.4  294.02
    5142  296.58  5235.5  298.21  5401.6  306.48  5454.7  309.17  5570.1  315.21
#Mann= 8 ,-1 , 0
  3658.3     .05       0  4424.1     .07       0    4753      .1       0
    5020     .05       0  5036.1      .1       0  5235.5     .07       0
  5401.6     .12       0  5454.7     .07       0
Bank Sta=5020,5036.1
XS Rating Curve= 0 ,0
Exp/Cntr=0.3,0.1

Type RM Length L Ch R = 1 ,36002   ,413,413,413
BEGIN DESCRIPTION:
WEST ROCKY CREEK 51.0
END DESCRIPTION:
XS GIS Cut Line= 3
      2420875.03     13615774.97        2421875.       13614575.
      2422224.99     13614175.01
#Sta/Elev= 30
  3433.1  323.15  3752.6  312.91  3781.3   314.1  3923.2  306.67    3944  308.72
  3958.3  308.44  3979.8  306.17  4071.5  302.81  4529.3  295.61  4554.5  292.16
  4611.8  291.33  4640.4  293.32  4646.9  296.53  4654.7  295.57  4661.2  298.62
  4696.4  299.72  4732.8  293.15  4836.7  291.13  4987.9   290.3  5008.9  286.72
  5015.1   282.6  5015.6   282.1  5031.2   282.6  5033.1  287.03  5044.9  290.49
  5087.6  292.19  5108.5  291.07  5202.5  295.44  5384.7  303.81  5526.6   313.5
#Mann= 6 ,-1 , 0
  3433.1     .05       0  4529.3     .07       0  4836.7      .1       0
  5015.1     .05       0  5031.2      .1       0  5202.5     .07       0
Bank Sta=5015.1,5031.2
XS Rating Curve= 0 ,0
Exp/Cntr=0.3,0.1

Type RM Length L Ch R = 1 ,35589   ,478,478,478
BEGIN DESCRIPTION:
WEST ROCKY CREEK 50.0
END DESCRIPTION:
XS GIS Cut Line= 3
      2421125.03     13615724.97        2422125.       13614825.
      2422325.01     13614224.98
#Sta/Elev= 30
  3647.4  318.11  3739.7   315.7  3781.9  312.52  3817.4  313.77  3895.1  307.88
  3923.5  308.51  3966.1  304.88  4086.5  301.41  4475.9  295.24  4794.3  292.65
  4886.2  290.08    4943  290.24  4968.7  288.68  4978.9  288.53  4985.6  287.44
  4989.4   283.6  4992.7   283.6  4995.2  282.07  4995.7  281.57  5011.4  282.07
  5024.3   287.8  5045.4  289.47  5224.6  291.38  5235.2  292.59  5351.1  295.56
  5382.7  297.46  5414.4  297.43    5476  301.96    5583  311.01  5625.2  312.93
#Mann= 5 ,-1 , 0
  3647.4     .05       0  4968.7      .1       0  4995.2     .05       0
  5011.4      .1       0    5476     .07       0
Bank Sta=4995.2,5011.4
XS Rating Curve= 0 ,0
Exp/Cntr=0.3,0.1

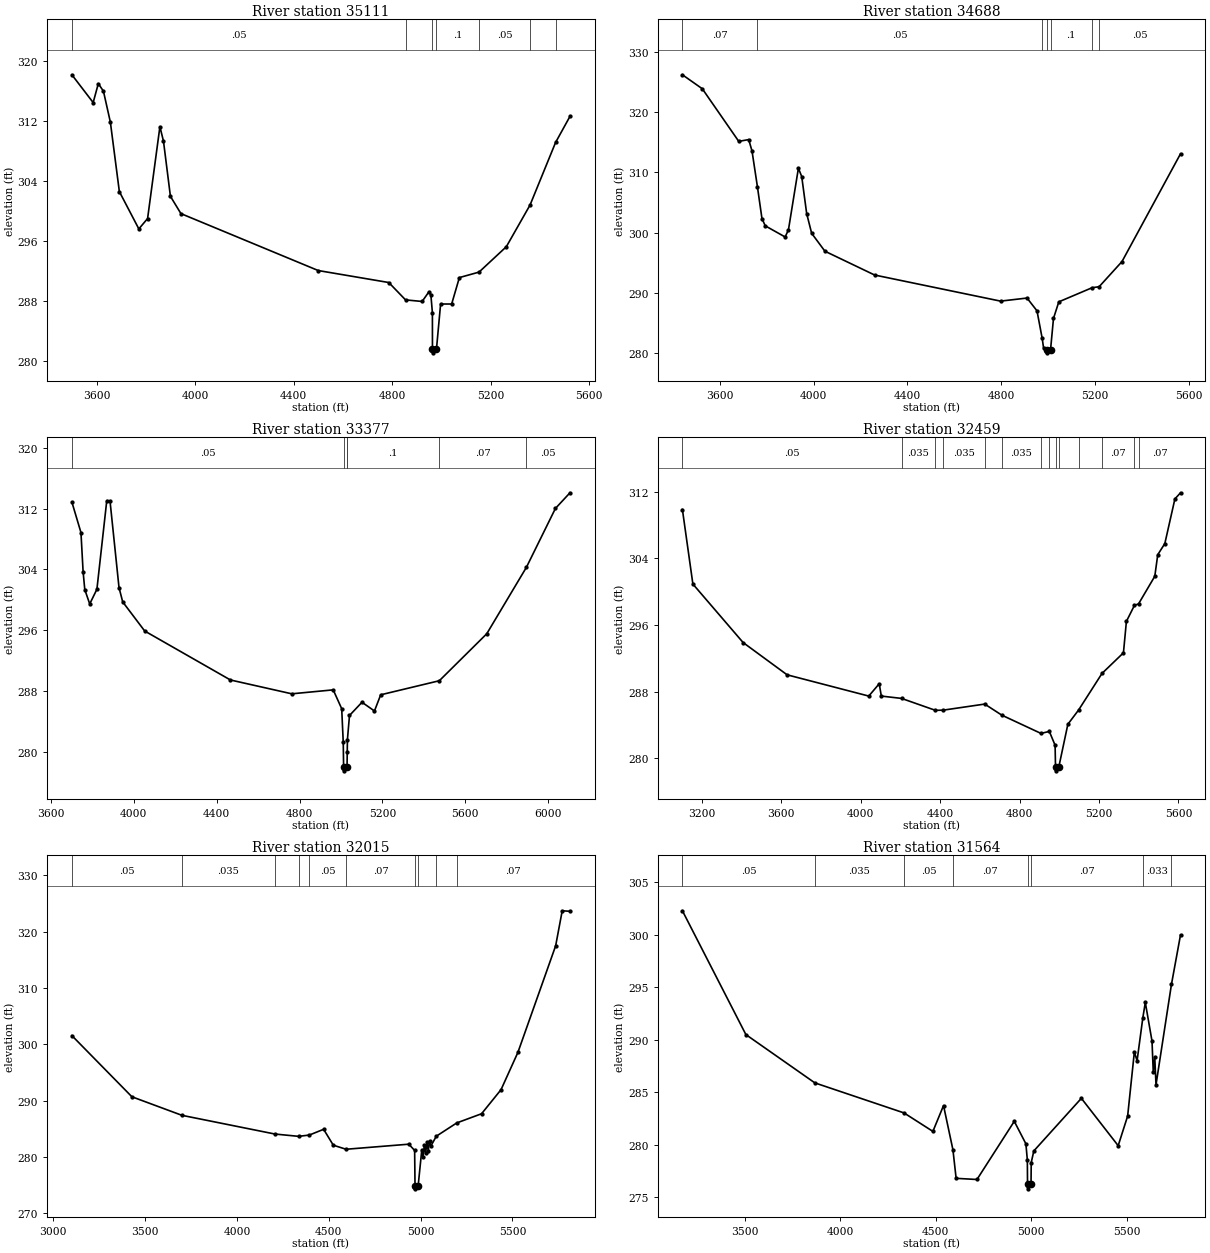
Type RM Length L Ch R = 1 ,35111   ,423,423,423
BEGIN DESCRIPTION:
WEST ROCKY CREEK 49.0
END DESCRIPTION:
XS GIS Cut Line= 3
      2421625.02     13616224.97        2422525.       13615025.
      2423025.02     13614874.99
#Sta/Elev= 30
  3499.8  318.16  3586.2  314.45  3607.1  316.98  3627.9  315.97    3656  311.84
  3692.5  302.56  3771.6  297.58  3807.1  298.96  3857.1  311.23  3871.6   309.3
  3899.8  301.93  3942.5  299.62  4499.8  292.02  4786.2  290.42  4854.3   288.1
  4921.6  287.89  4949.8  289.21  4957.1  288.77  4963.3  286.38  4963.5  281.53
    4964  281.03  4979.8  281.53  4996.6  287.55  5041.5  287.55  5072.8  291.08
  5152.5  291.81  5263.4   295.2  5359.7  300.77  5463.3  309.12  5521.8  312.61
#Mann= 7 ,-1 , 0
  3499.8     .05       0  4854.3      .1       0  4963.5     .05       0
  4979.8      .1       0  5152.5     .05       0  5359.7     .07       0
  5463.3     .05       0
Bank Sta=4963.5,4979.8
XS Rating Curve= 0 ,0
Exp/Cntr=0.3,0.1

Type RM Length L Ch R = 1 ,34688   ,1311,1311,1311
BEGIN DESCRIPTION:
WEST ROCKY CREEK 48.0
END DESCRIPTION:
XS GIS Cut Line= 3
      2421624.97     13616475.03        2422725.       13615375.
      2423075.02     13614924.97
#Sta/Elev= 30
  3439.8  326.17  3524.7  323.85  3680.3  315.12  3722.7  315.42  3736.8  313.54
  3759.9   307.6  3779.3  302.32  3793.4  301.11  3878.3  299.26  3892.4  300.46
  3934.8  310.66    3949  309.29  3970.2  303.13  3991.4  299.87    4048   296.9
  4260.1  292.95  4797.5  288.62  4910.6  289.13  4953.1  287.01  4975.1  282.47
  4981.3  280.83  4994.5  280.54    4995  280.04  5010.9  280.54  5023.5  285.75
  5046.2   288.5  5188.1  290.84  5218.3  291.01  5315.8  295.18  5565.6  313.06
#Mann= 7 ,-1 , 0
  3439.8     .07       0  3759.9     .05       0  4975.1      .1       0
  4994.5     .05       0  5010.9      .1       0  5188.1     .07       0
  5218.3     .05       0
Bank Sta=4994.5,5010.9
XS Rating Curve= 0 ,0
Exp/Cntr=0.3,0.1

Type RM Length L Ch R = 1 ,33377   ,918,918,918
BEGIN DESCRIPTION:
WEST ROCKY CREEK 47.0
END DESCRIPTION:
XS GIS Cut Line= 3
      2421925.04     13616524.98        2423125.       13616025.
        2423225.       13614925.
#Sta/Elev= 30
  3701.2  312.85    3745  308.84  3755.3  303.71  3763.5  301.33  3787.3  299.45
    3822  301.38  3869.6  313.03  3885.3  312.99  3928.7   301.6  3946.5  299.72
  4052.7  295.89  4466.5  289.45  4762.8  287.63  4962.7  288.15  5003.7  285.67
  5011.2  281.23  5012.9     278  5013.4   277.5  5029.5     278  5030.5  280.01
  5031.3  281.61  5041.3  284.78  5101.6  286.52  5161.8  285.37  5191.9   287.5
  5474.9  289.35    5704  295.53    5895  304.25  6035.4  312.01  6105.7  314.07
#Mann= 6 ,-1 , 0
  3701.2     .05       0  5012.9     .05       0  5029.5     .05       0
  5030.5      .1       0  5474.9     .07       0    5895     .05       0
Bank Sta=5012.9,5029.5
XS Rating Curve= 0 ,0
Exp/Cntr=0.3,0.1

Type RM Length L Ch R = 1 ,32459   ,444,444,444
BEGIN DESCRIPTION:
WEST ROCKY CREEK 46.0
END DESCRIPTION:
XS GIS Cut Line= 3
      2422174.97     13616725.01        2423975.       13616125.
      2424324.99     13615625.02
#Sta/Elev= 30
  3102.6  309.85  3155.3  300.91  3408.3  293.89  3629.7  290.02  4040.8  287.47
  4093.5  288.95    4104  287.47  4205.7  287.19  4376.3  285.76  4415.2  285.78
  4624.6  286.51  4710.7  285.18  4907.8  282.99  4949.9  283.23  4978.9  281.57
    4981     279  4981.5   278.5  4997.9     279  5043.2  284.09  5097.3   285.8
  5215.2  290.19    5323  292.66  5337.9  296.43  5378.3  298.35    5399  298.53
  5480.8  301.84  5495.7  304.43  5531.4  305.77    5582  311.12  5610.3  311.86
#Mann= 14 ,-1 , 0
  3102.6     .05       0  4205.7    .035       0  4376.3     .05       0
  4415.2    .035       0  4624.6     .05       0  4710.7    .035       0
  4907.8     .05       0  4949.9      .1       0    4981     .05       0
  4997.9      .1       0  5097.3    .035       0  5215.2     .07       0
  5378.3    .035       0    5399     .07       0
Bank Sta=4981,4997.9
XS Rating Curve= 0 ,0
Exp/Cntr=0.3,0.1

Type RM Length L Ch R = 1 ,32015   ,451,451,451
BEGIN DESCRIPTION:
WEST ROCKY CREEK 45.0
END DESCRIPTION:
XS GIS Cut Line= 3
      2422375.04     13617024.99        2424175.       13616425.
      2424775.03     13615874.97
#Sta/Elev= 30
  3101.8  301.55  3428.5   290.7  3700.8  287.41  4207.1  284.09  4336.2  283.68
  4394.3  283.91  4472.1  284.93  4524.8  282.11  4594.3  281.39  4935.9  282.29
  4967.5  281.18  4969.6  274.87  4970.1  274.37  4986.5  274.87  5006.2   281.2
    5013  280.04  5020.4  282.09  5027.2  280.66  5034.6  282.62  5041.4  281.12
  5048.8  282.88  5055.5  281.94  5085.6  283.71  5196.7  286.06  5331.8  287.69
  5437.8  291.96  5529.7  298.58  5735.1  317.48  5770.8  323.69  5813.1   323.6
#Mann= 10 ,-1 , 0
  3101.8     .05       0  3700.8    .035       0  4207.1     .05       0
  4336.2    .035       0  4394.3     .05       0  4594.3     .07       0
  4969.6     .05       0  4986.5     .07       0  5085.6      .1       0
  5196.7     .07       0
Bank Sta=4969.6,4986.5
XS Rating Curve= 0 ,0
Exp/Cntr=0.3,0.1

Type RM Length L Ch R = 1 ,31564   ,473,473,473
BEGIN DESCRIPTION:
WEST ROCKY CREEK 44.0
END DESCRIPTION:
XS GIS Cut Line= 3
      2422424.96     13617125.01        2424225.       13616825.
        2424725.       13616225.
#Sta/Elev= 30
  3174.5  302.27  3506.6  290.48  3867.4  285.88  4333.9  283.02  4484.9  281.26
  4540.6  283.72  4589.8  279.51  4606.5  276.79  4715.5  276.68  4910.7  282.22
  4971.5  280.08  4979.1  278.53    4980  276.29  4980.5  275.79  4998.4  276.29
  4999.4  278.29    5013   279.4  5261.7  284.41  5454.3   279.9  5503.8  282.72
  5538.9  288.82  5553.2  287.99  5583.3  292.08  5596.2  293.54  5631.3  289.86
  5637.9  286.89  5645.7   288.3  5652.2   285.7  5732.9  295.25  5780.4  299.97
#Mann= 8 ,-1 , 0
  3174.5     .05       0  3867.4    .035       0  4333.9     .05       0
  4589.8     .07       0    4980     .05       0  4998.4     .07       0
  5583.3    .033       0  5732.9     .07       0
Bank Sta=4980,4998.4
XS Rating Curve= 0 ,0
Exp/Cntr=0.3,0.1

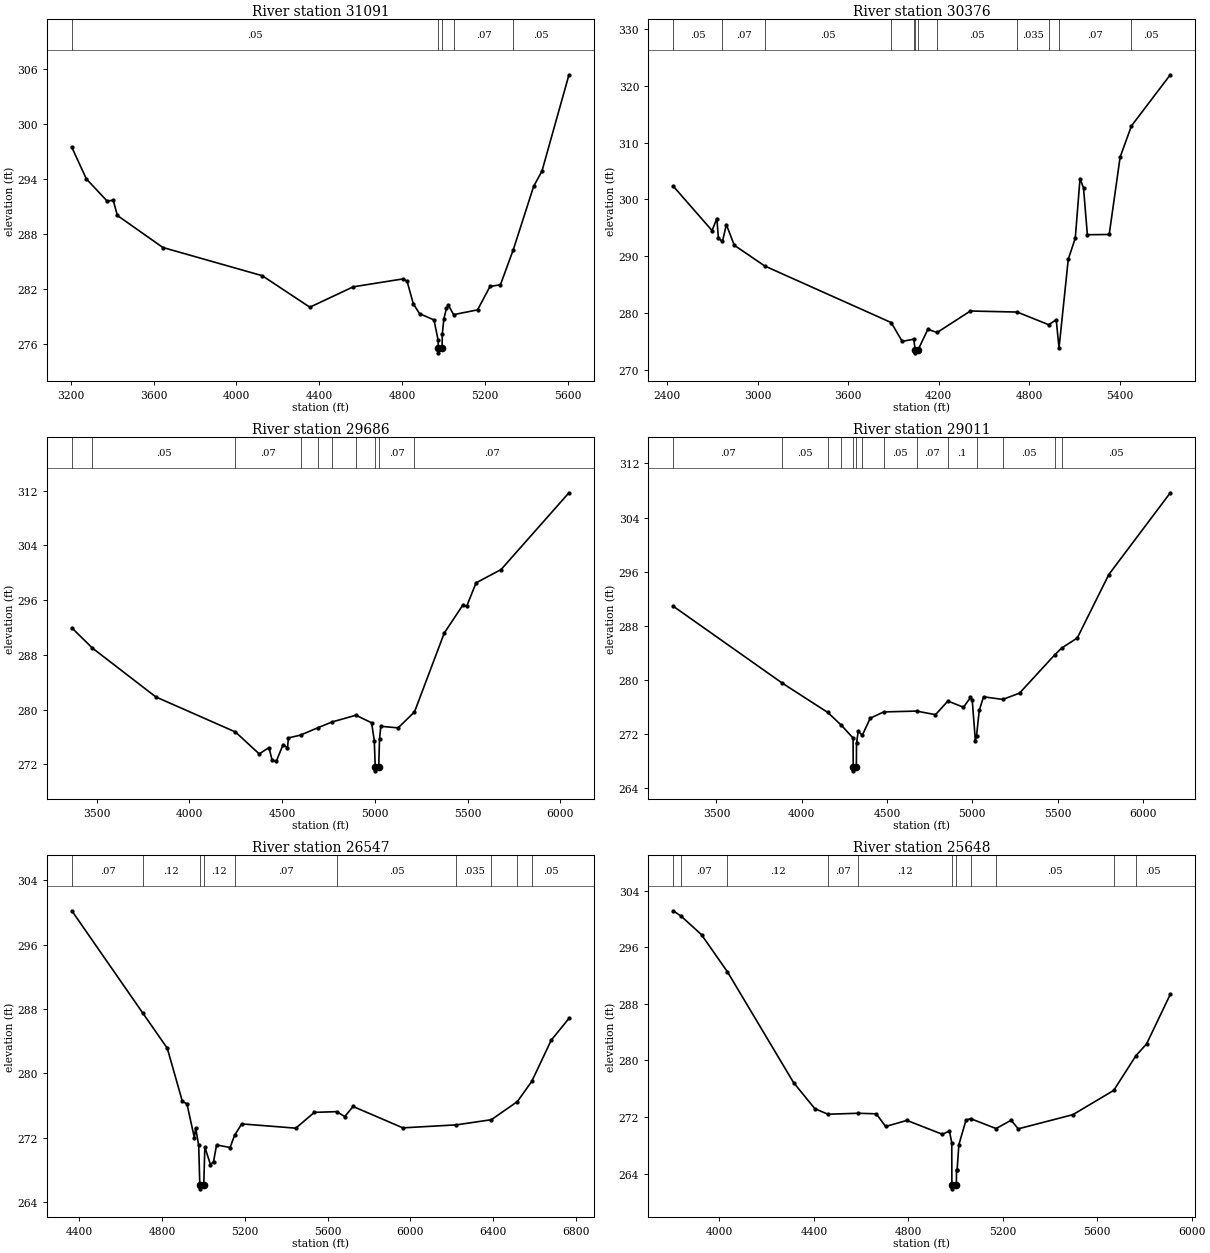
Type RM Length L Ch R = 1 ,31091   ,715,715,715
BEGIN DESCRIPTION:
WEST ROCKY CREEK 43.0
END DESCRIPTION:
XS GIS Cut Line= 3
      2422625.02       13617225.        2424425.       13617225.
      2425025.04       13617175.
#Sta/Elev= 30
  3204.8  297.44  3274.8  294.01  3374.8   291.6  3404.8  291.67  3424.8  290.02
  3644.8  286.53  4124.8  283.46  4354.8  280.03  4564.8  282.25  4804.8  283.11
  4824.8  282.85  4854.8   280.4  4884.8  279.33  4954.8  278.64  4974.8  276.42
  4975.6  275.56  4976.1  275.06    4994  275.56  4994.8   277.1  5002.3  278.74
  5014.8  279.89  5024.8  280.22  5049.7  279.22  5165.3  279.74  5225.5  282.29
  5275.7  282.47  5337.9  286.29  5436.3  293.19  5476.4  294.85  5606.9  305.34
#Mann= 5 ,-1 , 0
  3204.8     .05       0  4975.6     .05       0    4994     .05       0
  5049.7     .07       0  5337.9     .05       0
Bank Sta=4975.6,4994
XS Rating Curve= 0 ,0
Exp/Cntr=0.3,0.1

Type RM Length L Ch R = 1 ,30376   ,690,690,690
BEGIN DESCRIPTION:
H21756
END DESCRIPTION:
XS GIS Cut Line= 3
      2422489.73     13618421.35      2425102.56     13617570.67
      2425570.65     13617284.61
#Sta/Elev= 30
  2438.9  302.34  2696.6  294.51  2728.4  296.62  2739.1  293.14  2765.9   292.6
  2791.5  295.56  2844.1  291.93  3046.4  288.27  3884.5  278.32  3957.5  275.01
  4034.3  275.39    4044  273.49  4044.5  272.99  4062.5  273.49  4127.7  277.13
    4189  276.57  4409.7  280.35    4720  280.17  4928.9  277.94    4979  278.81
  4997.4  273.83  5058.8  289.47  5105.2  293.16  5136.7  303.67  5159.8  302.02
  5185.4  293.78  5330.2  293.82  5402.7  307.45  5477.6  312.93  5735.3  321.93
#Mann= 12 ,-1 , 0
  2438.9     .05       0  2765.9     .07       0  3046.4     .05       0
  3884.5     .07       0  4034.3     .12       0    4044     .05       0
  4062.5     .12       0    4189     .05       0    4720    .035       0
  4928.9      .1       0  4997.4     .07       0  5477.6     .05       0
Bank Sta=4044,4062.5
XS Rating Curve= 0 ,0
Exp/Cntr=0.3,0.1

Type RM Length L Ch R = 1 ,29686   ,675,675,675
BEGIN DESCRIPTION:
H21755
END DESCRIPTION:
XS GIS Cut Line= 3
      2423331.71     13618907.48       2424772.7     13618291.15
      2425649.41     13617605.41
#Sta/Elev= 30
  3366.7  291.94  3477.3  288.99  3819.8  281.84  4248.7  276.72  4376.9  273.52
  4429.5  274.43    4447  272.57  4468.8  272.43  4505.7  274.87  4529.3  274.42
  4534.7  275.85  4600.3  276.27  4694.1  277.35  4771.9   278.2  4898.6  279.17
  4982.9  278.06  4997.4  275.45  5002.6  271.54  5003.1  271.04  5021.1  271.54
  5025.7  275.73  5032.7  277.55  5125.8  277.32  5214.2  279.65  5374.5  291.17
    5474  295.24  5495.5  295.09  5546.3  298.52    5681  300.46    6047  311.68
#Mann= 10 ,-1 , 0
  3366.7     .07       0  3477.3     .05       0  4248.7     .07       0
  4600.3     .05       0  4694.1     .07       0  4771.9     .05       0
  4898.6     .07       0  5002.6     .05       0  5021.1     .07       0
  5214.2     .07       0
Bank Sta=5002.6,5021.1
XS Rating Curve= 0 ,0
Exp/Cntr=0.3,0.1

Type RM Length L Ch R = 1 ,29011   ,2464,2464,2464
BEGIN DESCRIPTION:
H21754
END DESCRIPTION:
XS GIS Cut Line= 4
       2423435.9      13618985.6      2424937.63     13618829.35
      2426031.38     13618577.61      2426231.01     13618377.98
#Sta/Elev= 30
  3246.5  290.91  3884.9  279.57  4152.9  275.22  4232.6  273.33  4301.3  271.44
  4302.1   267.1  4302.6   266.6  4320.6   267.1  4321.4  270.69  4331.4  272.44
  4355.2  271.85  4401.8  274.37  4481.1   275.3    4674  275.42  4784.4  274.89
  4856.8   276.9  4948.6  275.99  4989.6  277.43  4999.9  277.02  5018.1  271.06
    5025  271.76    5041  275.53  5066.1  277.53  5178.6  277.14    5277  278.07
  5482.5   283.7  5525.3  284.75  5615.6  286.21  5800.3  295.57    6161  307.65
#Mann= 14 ,-1 , 0
  3246.5     .07       0  3884.9     .05       0  4152.9     .07       0
  4232.6     .05       0  4302.1     .05       0  4320.6     .05       0
  4355.2     .07       0  4481.1     .05       0    4674     .07       0
  4856.8      .1       0    5025     .07       0  5178.6     .05       0
  5482.5    .035       0  5525.3     .05       0
Bank Sta=4302.1,4320.6
XS Rating Curve= 0 ,0
Exp/Cntr=0.3,0.1

Type RM Length L Ch R = 1 ,26547   ,899,899,899
BEGIN DESCRIPTION:
WEST ROCKY CREEK 39.0
END DESCRIPTION:
XS GIS Cut Line= 4
      2423895.95      13619879.7        2424547.     13619428.31
      2424972.35     13619558.51      2426135.58     13619463.02
#Sta/Elev= 30
  4363.4  300.19  4707.8  287.45    4825  283.13  4897.7  276.56  4920.2  276.21
    4956  272.02  4962.1  273.26  4976.9  271.07  4982.3  266.18  4982.8  265.68
  5001.4  266.18  5006.7  270.87  5033.7  268.69  5048.6  269.05  5063.4  271.13
  5128.9  270.81  5150.1   272.3  5184.9  273.74  5446.4  273.21  5536.2  275.17
  5644.1  275.26  5683.4  274.65  5723.5   275.9  5964.3  273.25  6223.1  273.62
  6392.4  274.26  6518.1  276.51  6588.2  279.04    6682  284.14  6767.6  286.83
#Mann= 10 ,-1 , 0
  4363.4     .07       0  4707.8     .12       0  4982.3     .05       0
  5001.4     .12       0  5150.1     .07       0  5644.1     .05       0
  6223.1    .035       0  6392.4     .05       0  6518.1    .035       0
  6588.2     .05       0
Bank Sta=4982.3,5001.4
XS Rating Curve= 0 ,0
Exp/Cntr=0.3,0.1

Type RM Length L Ch R = 1 ,25648   ,448,448,448
BEGIN DESCRIPTION:
WEST ROCKY CREEK 38.0
END DESCRIPTION:
XS GIS Cut Line= 3
      2423925.04       13619975.        2425125.       13619975.
        2426025.       13619875.
#Sta/Elev= 30
    3804  301.14  3837.7  300.38    3924  297.76  4033.4  292.54    4314  276.86
    4404  273.18  4459.4  272.39  4586.5  272.53    4664  272.45    4704  270.66
    4794  271.52    4944  269.56    4974  270.02    4984  268.36  4984.4  262.35
  4984.9  261.85  5003.5  262.35    5004  264.48  5006.5  264.48    5014  268.09
  5044.2  271.55  5063.7  271.77  5171.4  270.37  5235.4  271.54  5265.6  270.33
    5497  272.33  5669.9  275.76  5764.3  280.68  5808.9  282.32  5909.5  289.34
#Mann= 11 ,-1 , 0
    3804     .12       0  3837.7     .07       0  4033.4     .12       0
  4459.4     .07       0  4586.5     .12       0  4984.4     .05       0
  5003.5     .12       0  5063.7    .035       0  5171.4     .05       0
  5669.9    .035       0  5764.3     .05       0
Bank Sta=4984.4,5003.5
XS Rating Curve= 0 ,0
Exp/Cntr=0.3,0.1

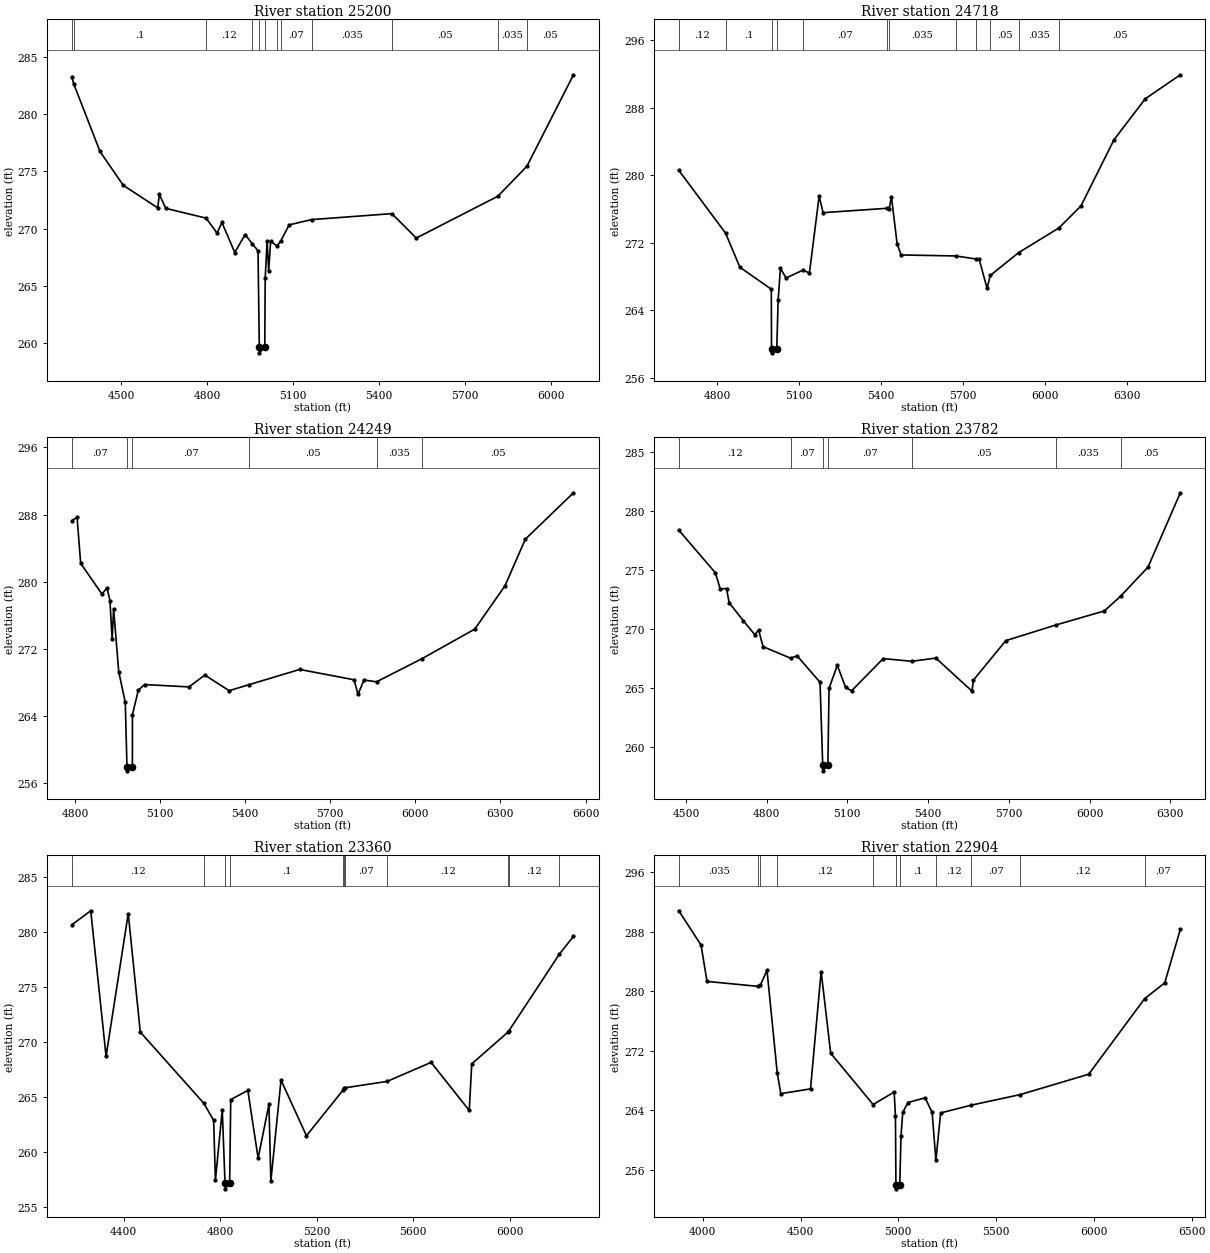
Type RM Length L Ch R = 1 ,25200   ,482,482,482
BEGIN DESCRIPTION:
WEST ROCKY CREEK 37.0
END DESCRIPTION:
XS GIS Cut Line= 3
        2424325.       13620025.        2424925.       13620325.
      2425924.95     13619925.02
#Sta/Elev= 30
  4329.2  283.19  4335.1  282.65    4427  276.73  4508.1  273.78  4628.3  271.81
  4633.9  272.99  4656.2  271.77  4796.6  270.92  4835.1  269.61  4851.9  270.54
  4896.6  267.92  4932.9  269.49  4958.4  268.65  4977.7  268.08  4982.1  259.67
  4982.6  259.17  5001.2  259.67  5002.7  265.68  5009.4   268.9  5014.8  266.29
  5021.6   268.9    5044  268.49    5057  268.93  5086.2  270.33  5164.2  270.79
  5444.1  271.31  5529.1  269.18  5813.6  272.83  5914.6  275.44    6077  283.42
#Mann= 12 ,-1 , 0
  4329.2     .12       0  4335.1      .1       0  4796.6     .12       0
  4958.4     .07       0  4982.1     .05       0  5001.2     .07       0
    5044     .12       0    5057     .07       0  5164.2    .035       0
  5444.1     .05       0  5813.6    .035       0  5914.6     .05       0
Bank Sta=4982.1,5001.2
XS Rating Curve= 0 ,0
Exp/Cntr=0.3,0.1

Type RM Length L Ch R = 1 ,24718   ,469,469,469
BEGIN DESCRIPTION:
WEST ROCKY CREEK 36.0
END DESCRIPTION:
XS GIS Cut Line= 3
      2424774.98     13621075.04        2424925.       13620775.
      2426125.04     13619874.97
#Sta/Elev= 30
  4660.2  280.56  4831.3  273.12  4883.9  269.07  4998.8  266.47  4999.6  259.43
  5000.1  258.93  5018.8  259.43  5023.8  265.16  5032.1  268.94  5052.9   267.8
  5113.5  268.72  5138.4  268.41  5173.8  277.49  5188.4  275.54    5423  276.06
  5429.8  275.92  5438.4  277.45  5459.2  271.85  5473.8  270.53  5674.4  270.41
  5746.1  270.06  5759.2  270.05  5788.4  266.58  5800.1   268.1  5904.2  270.81
  6051.5  273.73  6132.1  276.34  6252.9  284.18  6367.5  289.04  6495.7  291.88
#Mann= 12 ,-1 , 0
  4660.2     .12       0  4831.3      .1       0  4999.6     .05       0
  5018.8      .1       0  5113.5     .07       0    5423     .05       0
  5429.8    .035       0  5674.4     .05       0  5746.1    .035       0
  5800.1     .05       0  5904.2    .035       0  6051.5     .05       0
Bank Sta=4999.6,5018.8
XS Rating Curve= 0 ,0
Exp/Cntr=0.3,0.1

Type RM Length L Ch R = 1 ,24249   ,467,467,467
BEGIN DESCRIPTION:
WEST ROCKY CREEK 35.0
END DESCRIPTION:
XS GIS Cut Line= 3
      2424924.98     13621225.01        2425125.       13621175.
      2426124.98     13619975.02
#Sta/Elev= 30
  4789.4  287.28  4807.5  287.66  4820.3  282.18  4895.1  278.53  4913.1  279.24
  4923.4  277.75  4931.2  273.15  4936.3  276.77  4954.3  269.29  4977.5  265.61
  4983.4  257.96  4983.9  257.46  5002.6  257.96  5002.7  264.15  5023.6  267.08
  5045.7  267.74  5201.9  267.46  5257.9  268.87  5343.8  267.01  5414.2  267.73
  5592.4  269.54  5783.8  268.31  5798.1  266.57  5818.9  268.28  5863.4  268.07
  6023.2  270.82  6209.4  274.34  6316.2  279.51  6387.8  285.06  6557.6  290.59
#Mann= 6 ,-1 , 0
  4789.4     .07       0  4983.4     .05       0  5002.6     .07       0
  5414.2     .05       0  5863.4    .035       0  6023.2     .05       0
Bank Sta=4983.4,5002.6
XS Rating Curve= 0 ,0
Exp/Cntr=0.3,0.1

Type RM Length L Ch R = 1 ,23782   ,422,422,422
BEGIN DESCRIPTION:
WEST ROCKY CREEK 34.0
END DESCRIPTION:
XS GIS Cut Line= 3
      2425024.97     13621525.01        2425525.       13621375.
        2426125.     13620174.99
#Sta/Elev= 30
  4473.6  278.37  4609.4  274.76  4627.6  273.39  4651.1  273.42  4660.7  272.22
  4713.8  270.68  4755.5  269.52  4770.3  269.89  4786.8  268.49  4889.4  267.51
    4913  267.72  4998.4  265.47  5008.4  258.46  5008.9  257.96  5027.6  258.46
    5032  264.96  5062.7  266.91  5093.5  265.03  5115.8  264.75  5233.2  267.48
    5339  267.25  5428.9  267.52  5563.1  264.72  5568.6  265.66  5688.8     269
  5873.5  270.32    6055  271.52  6115.3  272.77  6217.1  275.23  6337.3  281.54
#Mann= 7 ,-1 , 0
  4473.6     .12       0  4889.4     .07       0  5008.4     .05       0
  5027.6     .07       0    5339     .05       0  5873.5    .035       0
  6115.3     .05       0
Bank Sta=5008.4,5027.6
XS Rating Curve= 0 ,0
Exp/Cntr=0.3,0.1

Type RM Length L Ch R = 1 ,23360   ,456,456,456
BEGIN DESCRIPTION:
WEST ROCKY CREEK 33.0
END DESCRIPTION:
XS GIS Cut Line= 3
      2425275.01     13622224.99        2425825.       13621625.
      2427024.96     13621225.01
#Sta/Elev= 30
  4185.6  280.66  4263.6  281.93  4327.1   268.7    4419  281.68  4468.9   270.9
  4731.9  264.43  4772.9  262.87  4780.3  257.43  4808.7  263.82  4820.1  257.14
  4820.6  256.64  4839.3  257.14  4843.8  264.76  4914.7  265.59  4957.3  259.43
  5002.2  264.32  5010.1  257.34  5052.2  266.53  5157.6  261.47  5310.1  265.64
  5314.1  265.78    5318  265.83  5491.5  266.41  5674.2  268.14  5832.3  263.77
  5842.8  268.01  5994.3  270.92  5995.6  270.97  6206.1  277.99  6264.4  279.61
#Mann= 11 ,-1 , 0
  4185.6     .12       0  4731.9      .1       0  4820.1     .05       0
  4839.3      .1       0  5310.1     .07       0  5314.1     .12       0
    5318     .07       0  5491.5     .12       0  5994.3     .07       0
  5995.6     .12       0  6206.1     .07       0
Bank Sta=4820.1,4839.3
XS Rating Curve= 0 ,0
Exp/Cntr=0.3,0.1

Type RM Length L Ch R = 1 ,22904   ,560,560,560
BEGIN DESCRIPTION:
WEST ROCKY CREEK 32.0
END DESCRIPTION:
XS GIS Cut Line= 3
      2424928.95     13622433.95        2425975.       13622025.
      2427175.03     13621224.98
#Sta/Elev= 30
  3877.4  290.83  3991.3  286.22  4021.8  281.34  4284.5  280.67  4294.5  280.81
  4328.6  282.84    4381  269.04  4399.3  266.26  4551.2   266.9  4605.5  282.67
  4654.4  271.69  4871.5   264.8  4979.1  266.48  4985.6  263.26  4988.1  253.97
  4988.6  253.47  5007.6  253.97  5014.1  260.62  5023.1  263.77  5050.1  265.07
  5137.3   265.7  5173.3  263.73  5192.4  257.31  5216.9  263.67  5374.4  264.72
    5625  266.14    5974  268.87  6259.9  279.01  6363.1  281.15  6442.8  288.34
#Mann= 11 ,-1 , 0
  3877.4    .035       0  4284.5     .12       0  4294.5    .035       0
    4381     .12       0  4871.5      .1       0  4988.1     .05       0
  5007.6      .1       0  5192.4     .12       0  5374.4     .07       0
    5625     .12       0  6259.9     .07       0
Bank Sta=4988.1,5007.6
XS Rating Curve= 0 ,0
Exp/Cntr=0.3,0.1