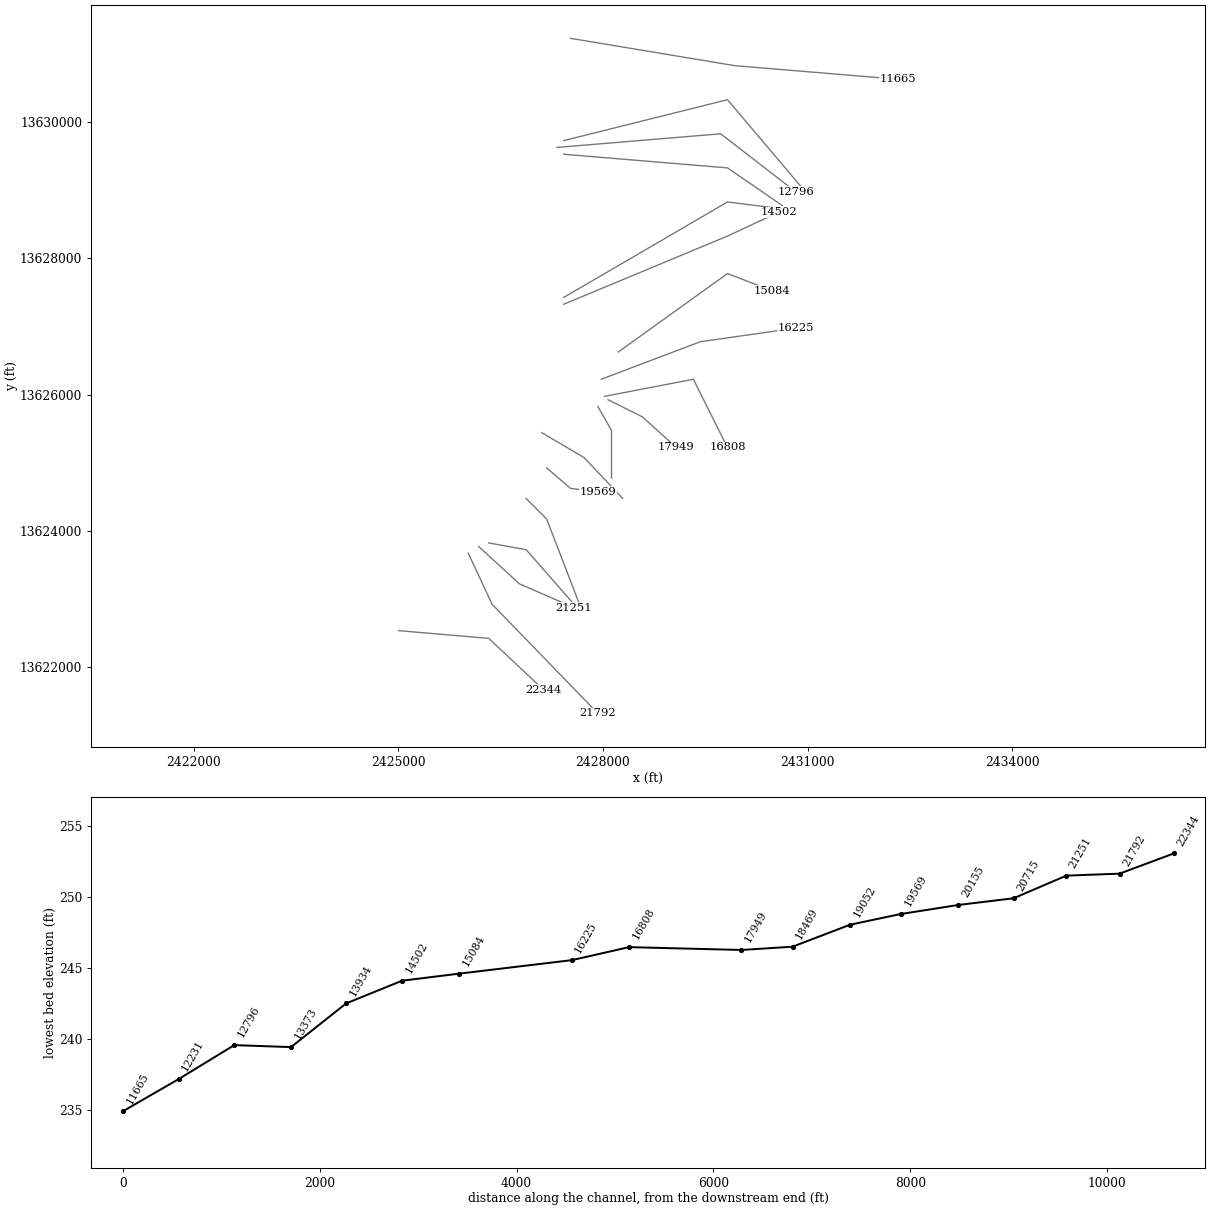
HEC-RAS study WEST ROCKY CREEK.prj: WEST ROCKY CREEK Base Level Engineering

--- WEST ROCKY CREEK.g01 (geometry) --- (continued)

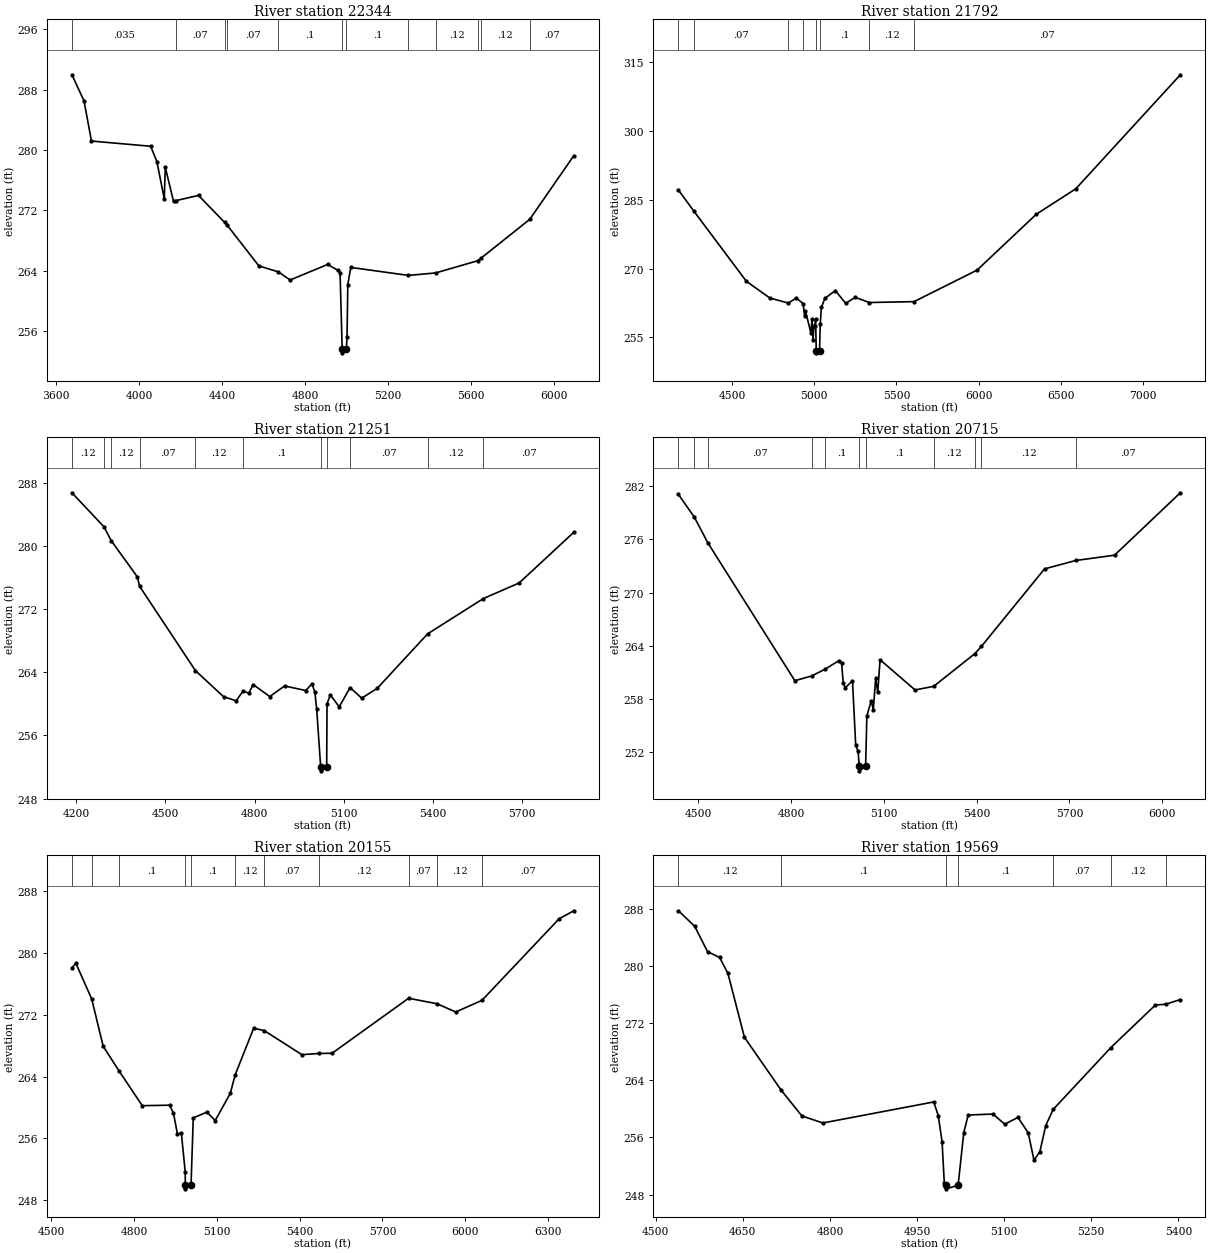
Type RM Length L Ch R = 1 ,22344   ,552,552,552
BEGIN DESCRIPTION:
WEST ROCKY CREEK 31.0
END DESCRIPTION:
XS GIS Cut Line= 3
      2425007.09     13622538.11        2426325.       13622425.
      2427124.97     13621675.03
#Sta/Elev= 30
    3677  289.97  3735.1  286.51  3771.1  281.18  4056.3  280.49  4086.4  278.46
  4122.1  273.53  4127.1  277.69  4166.7  273.18    4177  273.27  4287.1  273.97
  4413.3  270.38    4423   270.1  4578.2  264.62    4672  263.83  4728.8  262.75
  4909.4  264.81  4959.6  264.03  4969.6  263.66  4979.7  253.59  4980.2  253.09
  4999.8  253.59  5003.2  255.19  5006.8  262.11    5021  264.42  5299.1  263.36
  5430.8  263.69  5632.2   265.3  5648.8  265.64  5883.7  270.79  6096.3  279.24
#Mann= 12 ,-1 , 0
    3677    .035       0    4177     .07       0  4413.3     .12       0
    4423     .07       0    4672      .1       0  4979.7     .05       0
  4999.8      .1       0  5299.1     .07       0  5430.8     .12       0
  5632.2     .07       0  5648.8     .12       0  5883.7     .07       0
Bank Sta=4979.7,4999.8
XS Rating Curve= 0 ,0
Exp/Cntr=0.3,0.1

Type RM Length L Ch R = 1 ,21792   ,541,541,541
BEGIN DESCRIPTION:
WEST ROCKY CREEK 30.0
END DESCRIPTION:
XS GIS Cut Line= 3
      2426025.01     13623674.98        2426375.       13622925.
        2427925.       13621325.
#Sta/Elev= 30
  4173.4  287.07  4265.2  282.58  4587.2  267.21  4729.9  263.59  4842.5  262.49
  4889.9  263.58  4932.3  262.37  4941.1  259.77  4946.6  260.79    4979  256.04
  4986.8  259.05  4992.4   254.5  4998.3  257.42  5004.5  257.42  5008.1  259.04
  5012.2  252.16  5012.7  251.66  5032.3  252.16  5036.4  257.85  5043.4  261.53
  5064.7  263.51  5128.2  265.21    5192  262.41  5248.6  263.74  5335.7  262.61
  5607.2   262.8    5991  269.65  6351.7  281.81  6592.2  287.35  7228.7  312.16
#Mann= 8 ,-1 , 0
  4173.4     .12       0  4265.2     .07       0  4842.5     .12       0
  4932.3      .1       0  5012.2     .05       0  5032.3      .1       0
  5335.7     .12       0  5607.2     .07       0
Bank Sta=5012.2,5032.3
XS Rating Curve= 0 ,0
Exp/Cntr=0.3,0.1

Type RM Length L Ch R = 1 ,21251   ,536,536,536
BEGIN DESCRIPTION:
WEST ROCKY CREEK 29.0
END DESCRIPTION:
XS GIS Cut Line= 3
      2426174.98     13623775.02        2426775.       13623225.
      2427575.01     13622874.99
#Sta/Elev= 30
    4186  286.73  4293.3  282.44  4318.3  280.65  4405.2  276.12  4413.8  274.87
  4601.1  264.21  4695.7  260.91  4738.2  260.39  4761.4  261.63  4780.8  261.35
  4794.9  262.45  4851.1  260.93    4901  262.27  4971.9  261.69  4992.9  262.54
  5002.7  261.49  5008.9   259.3  5022.2  252.02  5022.7  251.52  5042.4  252.02
  5043.6  259.99  5054.5  261.13  5084.6  259.63  5121.1  262.07  5160.2  260.72
  5212.4  261.97  5381.9  268.87  5569.4  273.34  5689.6  275.31  5873.2  281.73
#Mann= 11 ,-1 , 0
    4186     .12       0  4293.3     .07       0  4318.3     .12       0
  4413.8     .07       0  4601.1     .12       0  4761.4      .1       0
  5022.2     .05       0  5042.4      .1       0  5121.1     .07       0
  5381.9     .12       0  5569.4     .07       0
Bank Sta=5022.2,5042.4
XS Rating Curve= 0 ,0
Exp/Cntr=0.3,0.1

Type RM Length L Ch R = 1 ,20715   ,560,560,560
BEGIN DESCRIPTION:
WEST ROCKY CREEK 28.0
END DESCRIPTION:
XS GIS Cut Line= 3
      2426324.98       13623825.        2426875.       13623725.
      2427574.97     13622925.04
#Sta/Elev= 30
  4436.3  281.04  4487.4   278.5  4530.6  275.63  4812.4  260.07  4866.6   260.6
  4908.8  261.34  4954.7  262.32  4963.6  262.06  4968.7  259.86    4975  259.26
  4998.7  260.08  5009.1  252.81  5016.7  252.11  5020.8  250.42  5021.3  249.92
  5041.1  250.42  5045.2  256.12  5059.4  257.81    5066  256.79  5073.6  260.32
  5080.3  258.76  5087.9  262.43  5200.8  259.03  5260.9  259.43  5393.7   263.1
  5415.4  263.93  5619.4  272.66    5721  273.61  5845.7   274.2  6058.3  281.23
#Mann= 11 ,-1 , 0
  4436.3     .07       0  4487.4     .12       0  4530.6     .07       0
  4866.6     .12       0  4908.8      .1       0  5020.8     .05       0
  5041.1      .1       0  5260.9     .12       0  5393.7     .07       0
  5415.4     .12       0    5721     .07       0
Bank Sta=5020.8,5041.1
XS Rating Curve= 0 ,0
Exp/Cntr=0.3,0.1

Type RM Length L Ch R = 1 ,20155   ,586,586,586
BEGIN DESCRIPTION:
WEST ROCKY CREEK 27.0
END DESCRIPTION:
XS GIS Cut Line= 3
      2426874.97     13624475.03        2427175.       13624175.
      2427674.98     13622875.04
#Sta/Elev= 30
  4575.7  278.09  4589.9  278.69  4647.4  274.04  4688.9  267.92  4746.4  264.72
  4830.3  260.23  4929.3  260.29  4943.4  259.25  4957.6  256.55  4971.7  256.72
  4985.9  251.63  4986.1  249.95  4986.6  249.45  5006.9  249.95    5015  258.65
  5064.3  259.39  5094.3   258.3  5148.9  261.81    5167  264.25  5233.6  270.27
  5271.4  269.97  5408.2  266.84  5471.9     267  5517.5  267.02  5794.6  274.15
  5897.8  273.44  5965.3  272.37  6060.3  273.88  6339.3  284.44  6392.8  285.49
#Mann= 11 ,-1 , 0
  4575.7     .07       0  4647.4     .12       0  4746.4      .1       0
  4986.1     .05       0  5006.9      .1       0    5167     .12       0
  5271.4     .07       0  5471.9     .12       0  5794.6     .07       0
  5897.8     .12       0  6060.3     .07       0
Bank Sta=4986.1,5006.9
XS Rating Curve= 0 ,0
Exp/Cntr=0.3,0.1

Type RM Length L Ch R = 1 ,19569   ,517,517,517
BEGIN DESCRIPTION:
WEST ROCKY CREEK 26.0
END DESCRIPTION:
XS GIS Cut Line= 3
      2427174.97     13624925.02        2427525.       13624625.
      2427924.97       13624575.
#Sta/Elev= 30
  4539.3  287.69  4567.3  285.51  4589.3  281.98  4610.1  281.16  4624.4  278.94
  4652.9  269.99  4716.1  262.61  4751.7  259.01  4787.9  258.02  4978.9  260.96
  4986.6  259.04  4993.2  255.37    4997   249.6  4999.9  249.31  5000.4  248.81
  5020.8  249.31  5030.5  256.64  5038.1  259.13  5080.9  259.27  5101.1  257.84
  5123.8   258.8  5141.4  256.65  5151.5  252.81  5161.6  254.01  5171.6  257.64
  5184.4  259.91  5283.9  268.57  5360.6  274.52  5378.4  274.62  5403.4  275.28
#Mann= 7 ,-1 , 0
  4539.3     .12       0  4716.1      .1       0  4999.9     .05       0
  5020.8      .1       0  5184.4     .07       0  5283.9     .12       0
  5378.4     .07       0
Bank Sta=4999.9,5020.8
XS Rating Curve= 0 ,0
Exp/Cntr=0.3,0.1

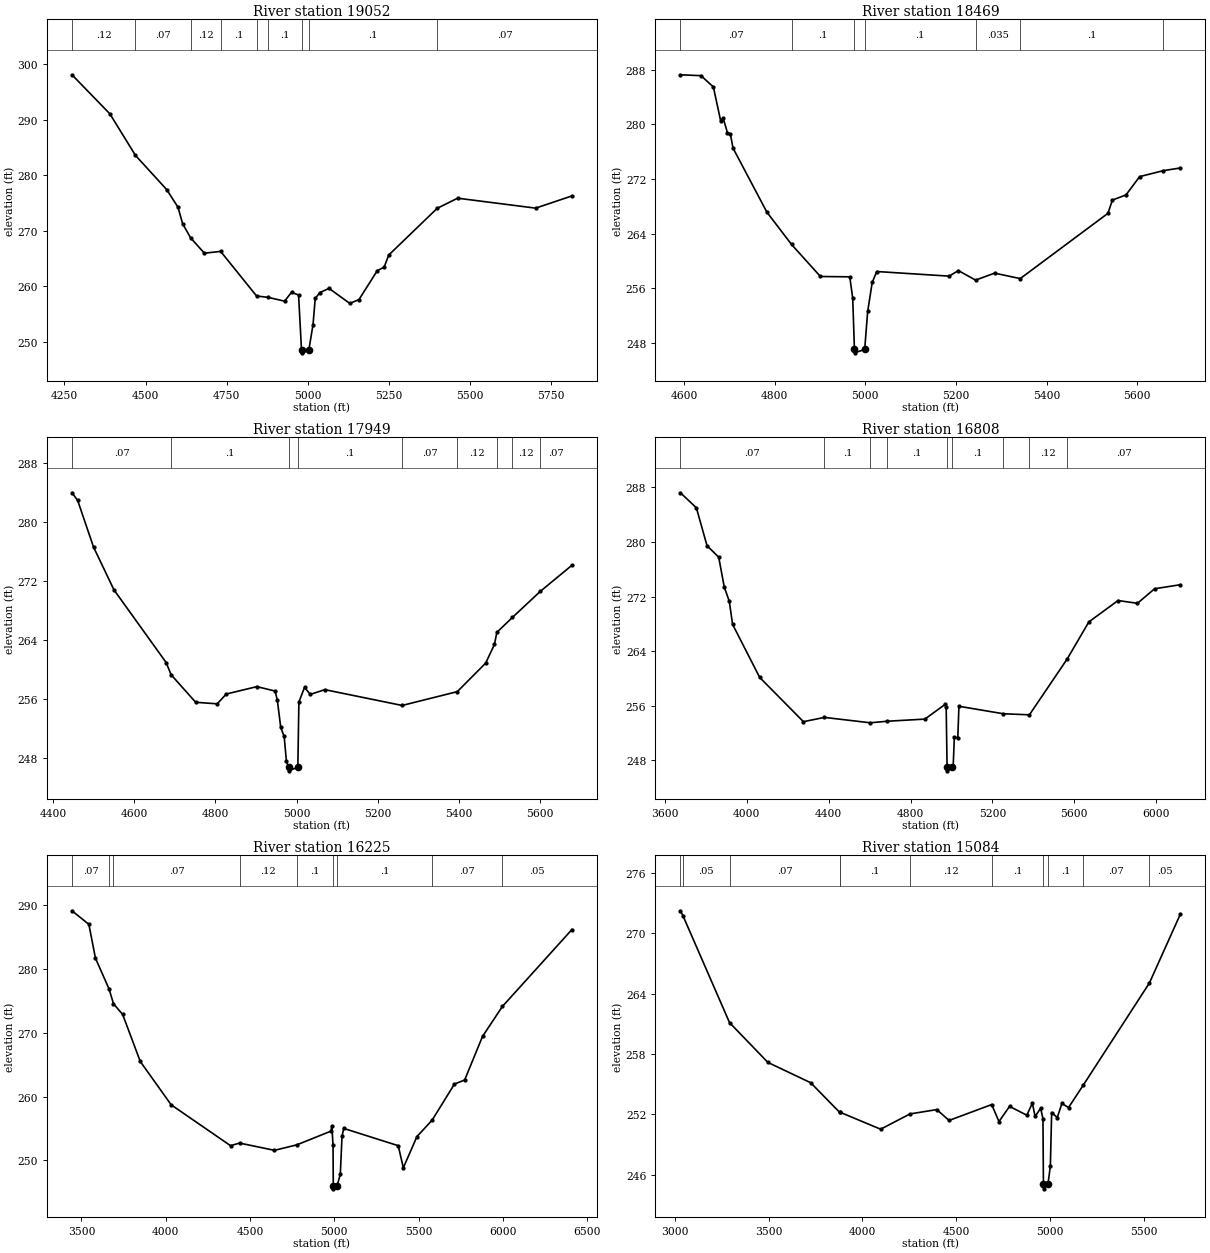
Type RM Length L Ch R = 1 ,19052   ,583,583,583
BEGIN DESCRIPTION:
WEST ROCKY CREEK 25.0
END DESCRIPTION:
XS GIS Cut Line= 3
      2427103.42     13625441.76        2427725.       13625075.
      2428287.52     13624479.07
#Sta/Elev= 30
  4273.2  298.09    4390  291.06  4468.9  283.58  4565.3  277.42  4600.1  274.24
  4614.4  271.27  4639.1  268.73  4681.4  265.98  4731.4  266.31  4842.2  258.28
  4878.1  258.03  4928.5  257.35    4950  258.95  4971.7  258.45  4980.7  248.55
  4981.2  248.05  5003.3  248.55  5016.2  253.11    5023  257.83  5037.2  258.89
  5065.5  259.65  5129.4  256.95  5157.8  257.63  5214.4  262.85  5235.4  263.46
  5249.6  265.65    5399  274.06    5462  275.88  5702.3  274.09  5814.4  276.29
#Mann= 9 ,-1 , 0
  4273.2     .12       0  4468.9     .07       0  4639.1     .12       0
  4731.4      .1       0  4842.2     .12       0  4878.1      .1       0
  4980.7     .05       0  5003.3      .1       0    5399     .07       0
Bank Sta=4980.7,5003.3
XS Rating Curve= 0 ,0
Exp/Cntr=0.3,0.1

Type RM Length L Ch R = 1 ,18469   ,520,520,520
BEGIN DESCRIPTION:
WEST ROCKY CREEK 24.0
END DESCRIPTION:
XS GIS Cut Line= 3
      2427924.99     13625825.02        2428125.       13625475.
        2428125.     13624775.04
#Sta/Elev= 30
  4592.1  287.29  4637.5  287.16  4664.8   285.5  4680.7  280.58  4686.4  280.94
  4695.8  278.79  4702.3  278.62    4708  276.55  4782.9  267.13  4837.2   262.4
  4900.9   257.7  4965.7  257.65  4972.2  254.51    4976     247  4976.5   246.5
  4998.6     247  5005.2  252.57  5015.2  256.82  5025.2  258.43  5185.2  257.75
  5205.2  258.57  5243.3  257.17  5285.2  258.19  5341.8  257.39  5535.2  266.96
  5545.2  268.91  5575.2  269.67  5605.2  272.35  5657.8  273.23  5695.2  273.62
#Mann= 7 ,-1 , 0
  4592.1     .07       0  4837.2      .1       0    4976     .05       0
  4998.6      .1       0  5243.3    .035       0  5341.8      .1       0
  5657.8     .07       0
Bank Sta=4976,4998.6
XS Rating Curve= 0 ,0
Exp/Cntr=0.3,0.1

Type RM Length L Ch R = 1 ,17949   ,1141,1141,1141
BEGIN DESCRIPTION:
WEST ROCKY CREEK 23.0
END DESCRIPTION:
XS GIS Cut Line= 3
      2428074.98     13625925.01        2428575.       13625675.
      2429074.98     13625225.02
#Sta/Elev= 30
  4446.8  283.91  4460.8  282.88  4499.9  276.56  4550.2  270.77  4678.8  260.93
    4691  259.28  4751.5  255.55  4804.6  255.34    4827  256.67  4902.4  257.67
  4947.1  257.07  4952.7  255.84  4961.1  252.14  4969.5  250.92  4975.1  247.55
  4980.6  246.77  4981.1  246.27  5003.2  246.77  5005.8  255.59  5019.7  257.56
  5033.9  256.62  5069.7  257.26  5260.1  255.12    5396  256.99  5465.9  260.85
  5487.6  263.39  5493.4  265.01  5531.9  267.04  5600.2  270.55  5678.5   274.1
#Mann= 9 ,-1 , 0
  4446.8     .07       0    4691      .1       0  4980.6     .05       0
  5003.2      .1       0  5260.1     .07       0    5396     .12       0
  5493.4     .07       0  5531.9     .12       0  5600.2     .07       0
Bank Sta=4980.6,5003.2
XS Rating Curve= 0 ,0
Exp/Cntr=0.3,0.1

Type RM Length L Ch R = 1 ,16808   ,583,583,583
BEGIN DESCRIPTION:
WEST ROCKY CREEK 22.0
END DESCRIPTION:
XS GIS Cut Line= 3
      2428024.99       13625975.        2429325.       13626225.
      2429825.01     13625224.97
#Sta/Elev= 30
  3676.2  287.21  3754.1  285.01    3806  279.46  3863.1  277.78  3890.1  273.42
    3915  271.29  3930.8  267.94  4063.2  260.16    4277  253.67  4379.5   254.3
  4603.6  253.51  4687.4  253.74  4870.2  254.05    4969  256.21  4974.1  255.81
  4978.5  246.97    4979  246.47  5001.2  246.97  5008.4  247.22    5014  251.42
  5030.8  251.29  5036.4  255.93    5254  254.83  5380.7  254.68  5565.3  262.87
  5670.9  268.29  5813.4  271.42  5908.4  271.02  5992.3  273.15  6118.1  273.74
#Mann= 9 ,-1 , 0
  3676.2     .07       0  4379.5      .1       0  4603.6     .12       0
  4687.4      .1       0  4978.5     .05       0  5001.2      .1       0
    5254    .035       0  5380.7     .12       0  5565.3     .07       0
Bank Sta=4978.5,5001.2
XS Rating Curve= 0 ,0
Exp/Cntr=0.3,0.1

Type RM Length L Ch R = 1 ,16225   ,1141,1141,1141
BEGIN DESCRIPTION:
WEST ROCKY CREEK 21.0
END DESCRIPTION:
XS GIS Cut Line= 3
      2427974.95     13626224.98        2429425.       13626775.
      2430825.03       13626975.
#Sta/Elev= 30
    3444  289.17  3544.2  287.04  3583.1  281.74  3664.3  276.88  3690.1  274.58
  3744.5  272.91    3849  265.53  4032.3  258.73  4384.3  252.32  4437.8  252.73
  4644.8  251.59  4777.4  252.45  4979.8   254.6  4985.1  255.46  4992.2  252.35
  4993.6  246.05  4994.1  245.55  5016.3  246.05  5035.3  247.81  5045.4  253.77
  5055.5  255.03  5378.7  252.32    5409  248.85  5489.8  253.75  5579.7  256.32
  5712.1  261.98  5772.7  262.62  5878.7  269.46  5996.5  274.16  6409.1  286.23
#Mann= 9 ,-1 , 0
    3444     .07       0  3664.3     .12       0  3690.1     .07       0
  4437.8     .12       0  4777.4      .1       0  4993.6     .05       0
  5016.3      .1       0  5579.7     .07       0  5996.5     .05       0
Bank Sta=4993.6,5016.3
XS Rating Curve= 0 ,0
Exp/Cntr=0.3,0.1

Type RM Length L Ch R = 1 ,15084   ,582,582,582
BEGIN DESCRIPTION:
WEST ROCKY CREEK 20.0
END DESCRIPTION:
XS GIS Cut Line= 3
      2428225.03     13626625.02        2429825.       13627775.
      2430475.01       13627525.
#Sta/Elev= 30
  3029.6  272.25  3043.3  271.75  3291.4  261.13  3496.1  257.17  3724.4  255.15
  3878.6  252.21  3880.3  252.22  4097.6  250.53  4254.2  252.05  4397.2  252.48
  4462.3   251.4  4689.8  252.98  4728.6  251.29  4785.1   252.8  4877.2  251.92
  4906.7  253.12  4921.4   251.8  4950.7  252.61  4963.2  251.59  4965.7   245.1
  4966.2   244.6  4990.1   245.1  5002.7  246.86  5009.6  252.19  5039.6  251.69
  5064.3  253.09  5099.6  252.68  5177.8   254.9    5531  265.07  5696.4  271.93
#Mann= 11 ,-1 , 0
  3029.6     .07       0  3043.3     .05       0  3291.4     .07       0
  3878.6     .12       0  3880.3      .1       0  4254.2     .12       0
  4689.8      .1       0  4965.7     .05       0  4990.1      .1       0
  5177.8     .07       0    5531     .05       0
Bank Sta=4965.7,4990.1
XS Rating Curve= 0 ,0
Exp/Cntr=0.3,0.1

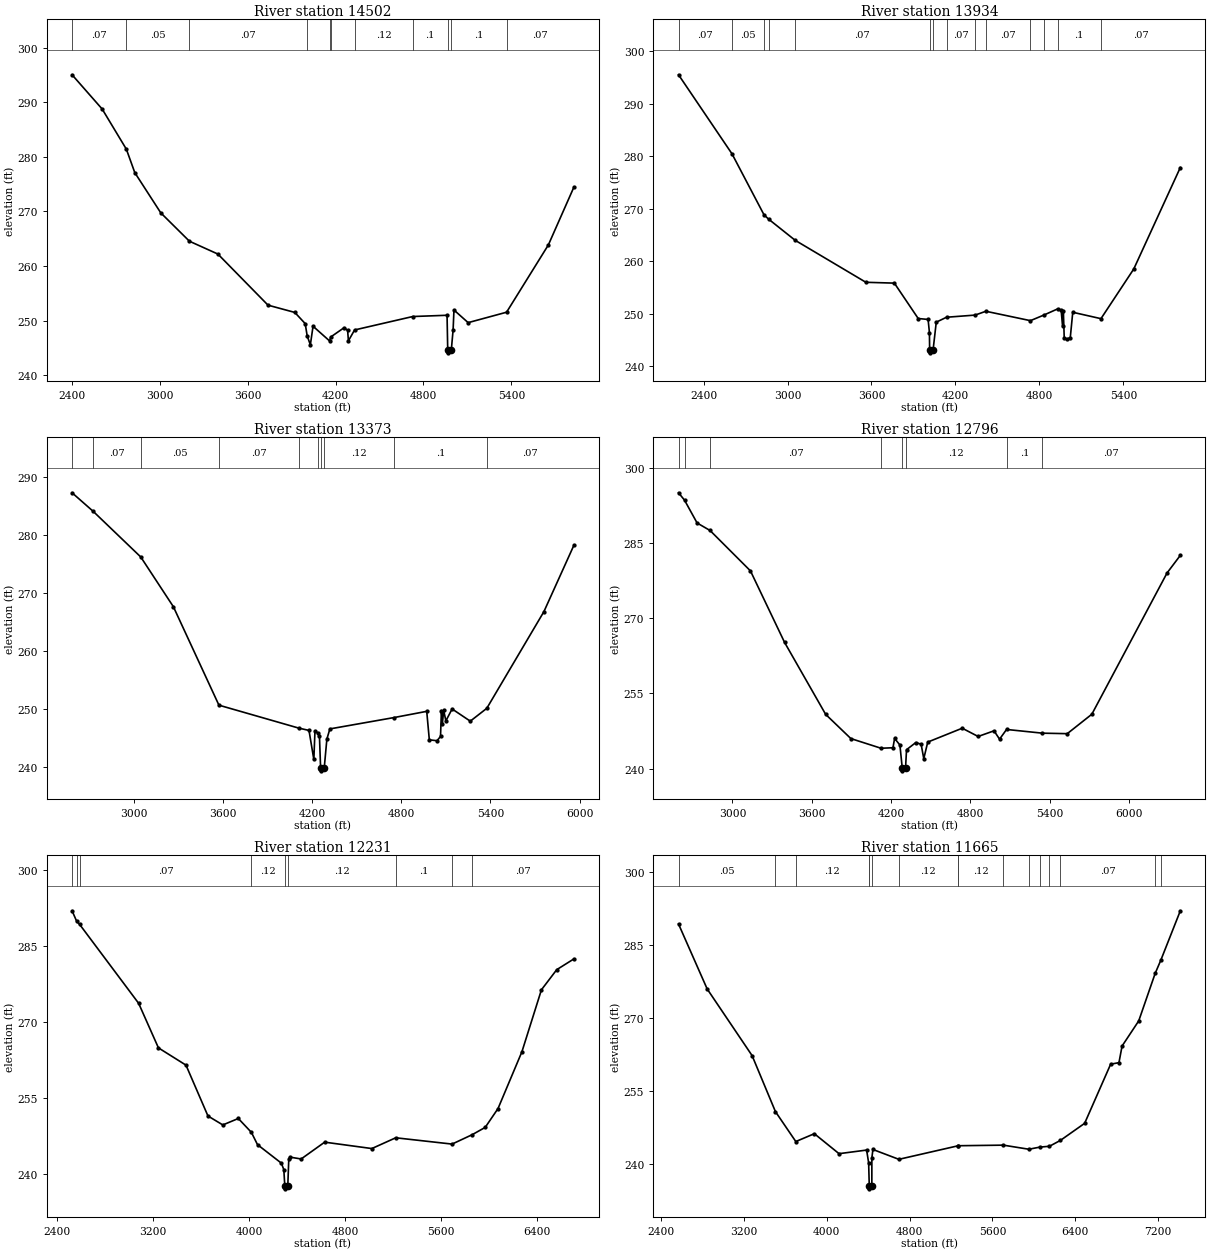
Type RM Length L Ch R = 1 ,14502   ,568,568,568
BEGIN DESCRIPTION:
WEST ROCKY CREEK 19.0
END DESCRIPTION:
XS GIS Cut Line= 3
      2427424.99       13627325.        2429825.       13628325.
      2430575.04     13628675.02
#Sta/Elev= 30
  2399.5  295.02  2605.3  288.74  2770.4  281.39    2828   277.1  3005.6  269.73
  3201.1  264.54  3395.6  262.19    3738  252.83    3921   251.5    3992  249.45
  4005.6  247.19  4027.2  245.57  4045.6  248.97  4158.9  246.27  4166.4     247
    4258  248.71  4281.8   248.2  4287.2   246.3  4329.3  248.29  4726.7  250.75
    4961  250.98  4965.6   244.6  4966.1   244.1    4990   244.6  5002.3  248.28
  5008.2  251.94  5105.1  249.63  5367.6  251.54    5653  263.86  5827.2  274.43
#Mann= 11 ,-1 , 0
  2399.5     .07       0  2770.4     .05       0  3201.1     .07       0
  4005.6      .1       0  4158.9     .07       0  4166.4      .1       0
  4329.3     .12       0  4726.7      .1       0  4965.6     .05       0
    4990      .1       0  5367.6     .07       0
Bank Sta=4965.6,4990
XS Rating Curve= 0 ,0
Exp/Cntr=0.3,0.1

Type RM Length L Ch R = 1 ,13934   ,561,561,561
BEGIN DESCRIPTION:
WEST ROCKY CREEK 18.0
END DESCRIPTION:
XS GIS Cut Line= 3
      2427424.97     13627424.98        2429825.       13628825.
      2430625.05     13628724.99
#Sta/Elev= 30
  2221.5  295.55  2603.4  280.47  2832.2  268.83  2864.8  268.01  3054.8  263.97
  3559.9  255.96  3763.4   255.8  3933.7  249.05  4004.4  248.87  4013.9  246.36
  4015.4     243  4015.9   242.5  4039.8     243  4062.7  248.35  4135.9  249.29
  4339.9   249.7  4417.1  250.43  4735.4  248.64    4829  249.68  4929.7  250.88
    4955  250.64  4964.9   247.6  4970.7  250.45  4976.9  245.35  4997.1   245.1
  5020.2  245.42  5037.8  250.24  5239.3  249.02  5473.7   258.5  5806.3  277.86
#Mann= 14 ,-1 , 0
  2221.5     .07       0  2603.4     .05       0  2832.2     .07       0
  2864.8     .05       0  3054.8     .07       0  4015.4     .05       0
  4039.8     .07       0  4135.9     .07       0  4339.9     .12       0
  4417.1     .07       0  4735.4      .1       0    4829     .07       0
  4929.7      .1       0  5239.3     .07       0
Bank Sta=4015.4,4039.8
XS Rating Curve= 0 ,0
Exp/Cntr=0.3,0.1

Type RM Length L Ch R = 1 ,13373   ,577,577,577
BEGIN DESCRIPTION:
WEST ROCKY CREEK 17.0
END DESCRIPTION:
XS GIS Cut Line= 3
        2427425.       13629525.        2429825.       13629325.
      2430624.96     13628775.03
#Sta/Elev= 30
  2582.3  287.22  2724.4  284.03  3044.9  276.18  3264.7  267.62  3571.3   250.7
    4110  246.75  4177.8  246.36  4210.4  241.36    4218  246.22  4240.7  245.88
  4248.1  245.43  4255.9  239.91  4256.4  239.41  4280.4  239.91  4298.2  244.87
  4318.3  246.62  4750.3  248.57  4970.6  249.64  4988.1  244.74    5040  244.59
  5063.4  245.32  5069.8  249.78  5075.8  247.49  5084.7   249.8  5099.6     248
  5141.5  250.05  5263.9  247.95  5375.1  250.16  5759.8  266.79  5961.4  278.18
#Mann= 10 ,-1 , 0
  2582.3     .05       0  2724.4     .07       0  3044.9     .05       0
  3571.3     .07       0    4110      .1       0  4240.7     .12       0
  4255.9     .05       0  4280.4     .12       0  4750.3      .1       0
  5375.1     .07       0
Bank Sta=4255.9,4280.4
XS Rating Curve= 0 ,0
Exp/Cntr=0.3,0.1

Type RM Length L Ch R = 1 ,12796   ,565,565,565
BEGIN DESCRIPTION:
WEST ROCKY CREEK 16.0
END DESCRIPTION:
XS GIS Cut Line= 3
      2427325.03       13629625.        2429725.       13629825.
      2430824.98     13628975.02
#Sta/Elev= 30
  2591.8  295.06  2637.3  293.58  2732.3  289.03  2830.4  287.53  3136.1  279.47
  3394.5  265.19  3705.6  250.82  3896.3  245.99  4124.5  244.06  4214.9  244.16
  4227.4  246.02  4267.6   244.7  4285.4  240.05  4285.9  239.55    4310  240.05
  4317.7  243.77    4388   245.2  4428.1  244.86  4448.2  241.99  4478.3  245.29
  4739.2  248.06  4859.6  246.41    4980  247.54  5021.8  245.87  5074.9  247.81
  5346.2  247.07  5534.4  246.97  5720.4  250.85  6289.7  279.05  6390.2  282.57
#Mann= 8 ,-1 , 0
  2591.8    .035       0  2637.3     .05       0  2830.4     .07       0
  4124.5     .12       0  4285.4     .05       0    4310     .12       0
  5074.9      .1       0  5346.2     .07       0
Bank Sta=4285.4,4310
XS Rating Curve= 0 ,0
Exp/Cntr=0.3,0.1

Type RM Length L Ch R = 1 ,12231   ,566,566,566
BEGIN DESCRIPTION:
WEST ROCKY CREEK 15.0
END DESCRIPTION:
XS GIS Cut Line= 3
      2427425.04     13629725.01        2429825.       13630325.
      2430925.03     13629024.97
#Sta/Elev= 30
  2526.6  291.89  2564.6  289.84  2589.7   289.2  3080.6  273.68  3245.5   264.9
  3474.9   261.5  3657.8  251.49  3781.5  249.73  3910.4     251  4019.2  248.27
  4070.1  245.85  4268.6  242.21  4289.2  240.93  4297.5  237.65    4298  237.15
  4322.1  237.65  4330.4  242.96  4340.7  243.39  4433.5  243.03  4629.3  246.34
  5021.9  245.08  5220.6   247.2  5689.6  245.96    5857  247.81  5965.6  249.25
  6072.2  252.96  6271.1  264.14  6433.6  276.34    6561   280.3  6703.4  282.41
#Mann= 9 ,-1 , 0
  2526.6    .035       0  2564.6     .05       0  2589.7     .07       0
  4019.2     .12       0  4297.5     .05       0  4322.1     .12       0
  5220.6      .1       0  5689.6     .12       0    5857     .07       0
Bank Sta=4297.5,4322.1
XS Rating Curve= 0 ,0
Exp/Cntr=0.3,0.1

Type RM Length L Ch R = 1 ,11665   ,1103,1103,1103
BEGIN DESCRIPTION:
WEST ROCKY CREEK 14.0
END DESCRIPTION:
XS GIS Cut Line= 3
      2427525.04     13631224.99        2429925.       13630825.
      2432325.01       13630625.
#Sta/Elev= 30
  2571.4  289.25  2847.6  275.92    3281  262.24  3506.2  250.74  3702.8  244.59
  3881.7   246.2  4119.9   242.1  4386.1  242.84  4405.6  240.22  4411.8  235.38
  4412.3  234.88  4436.4  235.38  4436.7  241.25  4446.9  242.96  4697.2  240.94
  5266.4  243.71  5266.9  243.73  5705.4  243.85  5951.3  243.01  6058.3  243.45
  6150.1  243.62  6256.2  244.83  6489.6  248.33  6740.5  260.47  6820.7  260.79
  6850.8   264.2  7011.4  269.36  7170.3  279.13    7224  281.79  7412.8  291.97
#Mann= 16 ,-1 , 0
  2571.4     .05       0  3506.2     .07       0  3702.8     .12       0
  4405.6      .1       0  4411.8     .05       0  4436.4      .1       0
  4697.2     .12       0  5266.4    .035       0  5266.9     .12       0
  5705.4      .1       0  5951.3     .12       0  6058.3     .07       0
  6150.1     .12       0  6256.2     .07       0  7170.3     .12       0
    7224     .07       0
Bank Sta=4411.8,4436.4
XS Rating Curve= 0 ,0
Exp/Cntr=0.3,0.1