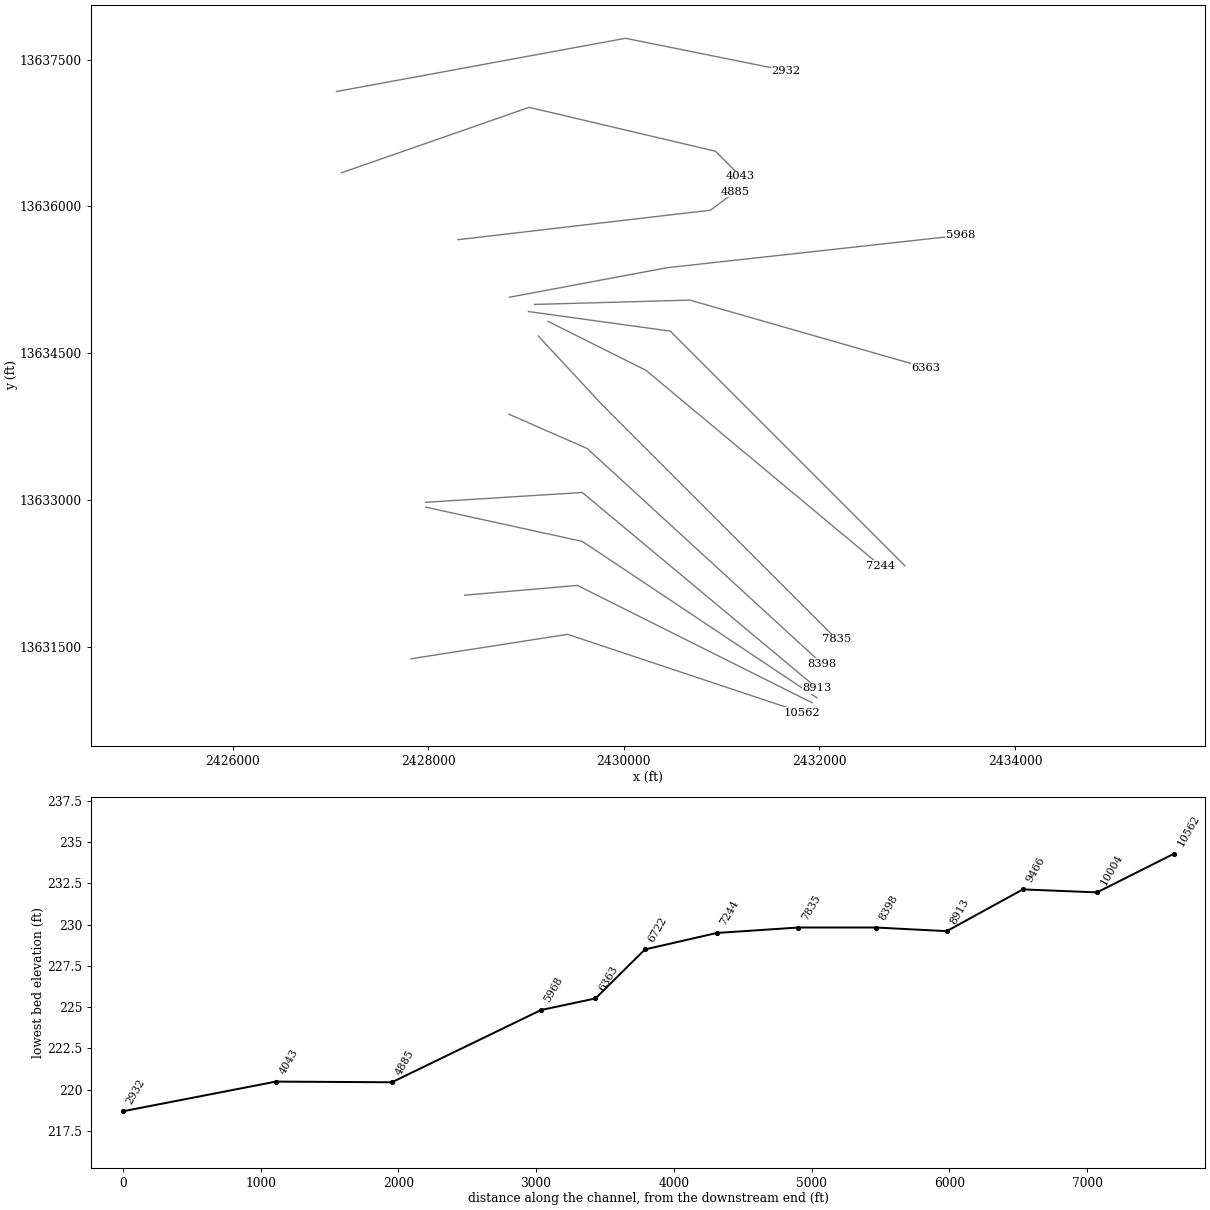
HEC-RAS study WEST ROCKY CREEK.prj: WEST ROCKY CREEK Base Level Engineering

--- WEST ROCKY CREEK.g01 (geometry) --- (continued)

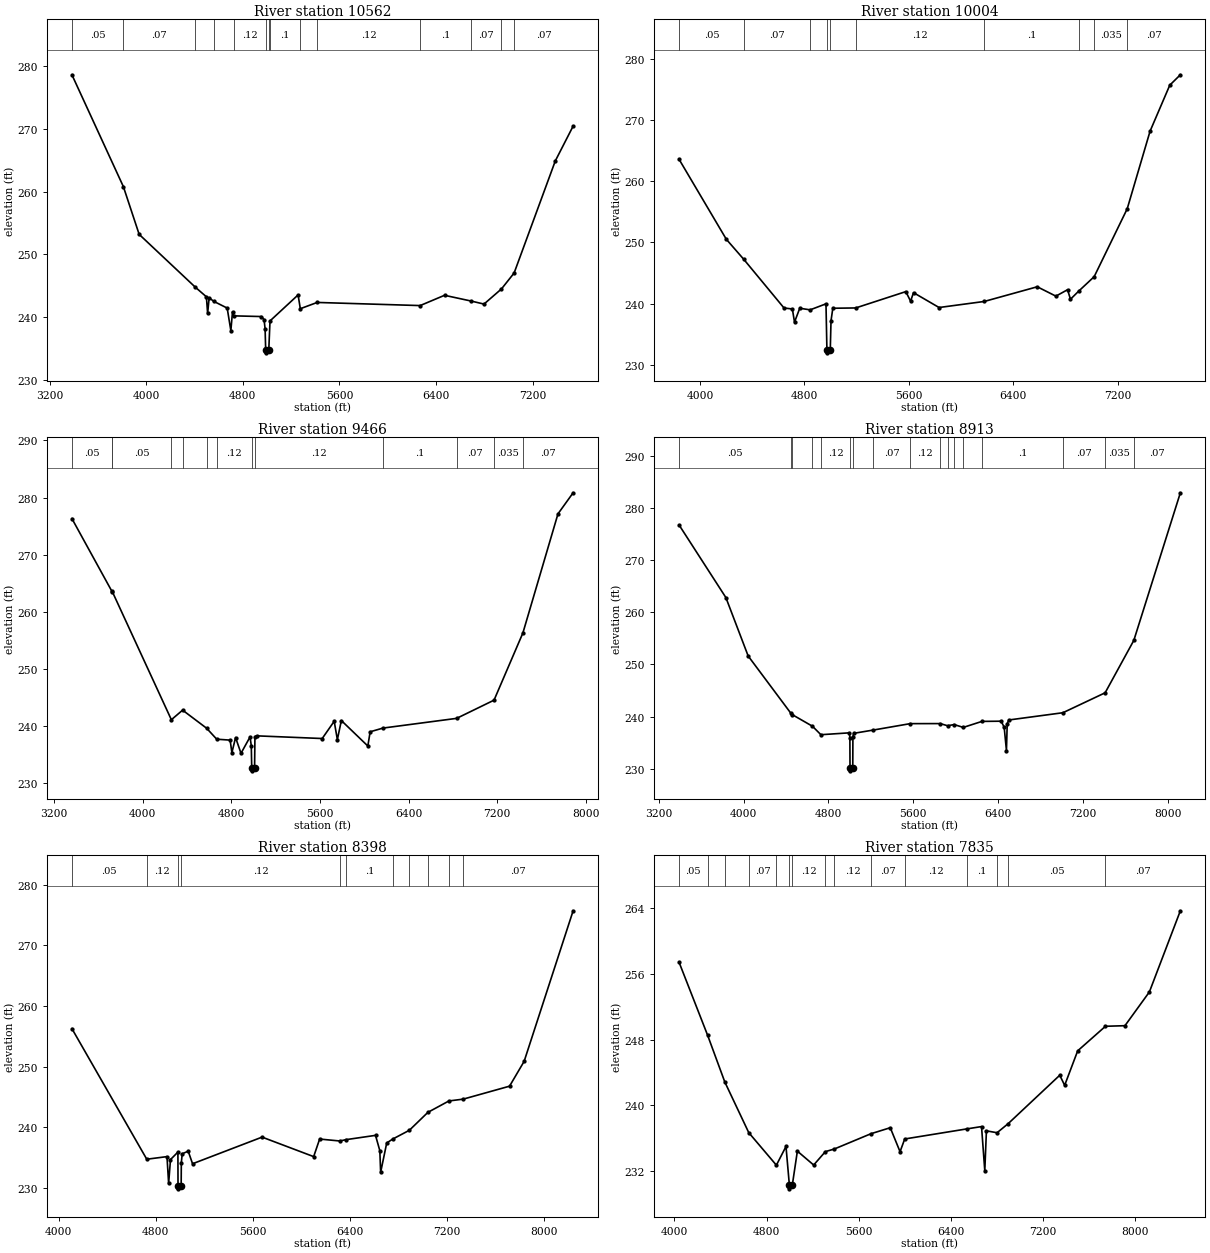
Type RM Length L Ch R = 1 ,10562   ,558,558,558
BEGIN DESCRIPTION:
WEST ROCKY CREEK 13.0
END DESCRIPTION:
XS GIS Cut Line= 3
      2427824.99       13631375.        2429425.       13631625.
      2431824.96     13630825.01
#Sta/Elev= 30
  3385.5  278.65  3811.6   260.8  3942.2  253.19  4408.3  244.74  4498.9  243.23
    4509  240.57  4521.6  243.08  4558.4  242.52  4670.9  241.43  4701.3  237.83
  4714.9  240.85    4725  240.19  4954.3  240.08  4976.1  239.59  4984.7  238.15
  4989.5  234.79    4990  234.29  5015.3  234.79  5025.4  239.38  5257.9  243.53
  5276.3  241.33  5415.7  242.33  6268.3  241.83  6470.1  243.47  6688.5  242.56
  6796.9  242.07  6941.7  244.49  7046.3  247.03  7387.2  264.91  7534.7  270.46
#Mann= 14 ,-1 , 0
  3385.5     .05       0  3811.6     .07       0  4408.3     .05       0
  4558.4     .07       0    4725     .12       0  4989.5     .05       0
  5015.3     .12       0  5025.4      .1       0  5276.3     .07       0
  5415.7     .12       0  6268.3      .1       0  6688.5     .07       0
  6941.7    .035       0  7046.3     .07       0
Bank Sta=4989.5,5015.3
XS Rating Curve= 0 ,0
Exp/Cntr=0.3,0.1

Type RM Length L Ch R = 1 ,10004   ,538,538,538
BEGIN DESCRIPTION:
WEST ROCKY CREEK 12.0
END DESCRIPTION:
XS GIS Cut Line= 3
      2428374.97       13632025.        2429525.       13632125.
      2431924.96     13630925.02
#Sta/Elev= 30
  3841.1  263.57  4202.5  250.51  4335.1  247.26  4644.1  239.28  4708.1  239.12
  4724.4  236.97  4764.6  239.24    4844  238.98  4965.4  239.96  4972.5  232.45
    4973  231.95  4998.3  232.45  5003.9  237.19  5017.8  239.24    5193  239.29
  5576.8  241.96  5613.2  240.39  5635.5  241.79  5831.2  239.36  6177.2  240.35
  6583.1  242.75  6725.6  241.22  6815.1  242.27  6837.4  240.71  6899.4  242.02
  7018.8   244.4  7271.8   255.5  7446.8  268.19  7597.7  275.71  7678.7  277.41
#Mann= 10 ,-1 , 0
  3841.1     .05       0  4335.1     .07       0    4844     .12       0
  4972.5     .05       0  4998.3     .12       0    5193     .12       0
  6177.2      .1       0  6899.4     .07       0  7018.8    .035       0
  7271.8     .07       0
Bank Sta=4972.5,4998.3
XS Rating Curve= 0 ,0
Exp/Cntr=0.3,0.1

Type RM Length L Ch R = 1 ,9466    ,553,553,553
BEGIN DESCRIPTION:
WEST ROCKY CREEK 11.0
END DESCRIPTION:
XS GIS Cut Line= 3
      2427975.03     13632924.99        2429575.       13632575.
      2431974.96     13630975.02
#Sta/Elev= 30
  3362.3  276.31  3721.1  263.64  3726.4  263.53  4259.6  241.08    4361  242.76
  4577.8  239.59  4668.9  237.67  4789.9  237.51  4805.6  235.31  4838.9  237.96
  4887.9   235.2  4969.4  238.07  4980.7  236.54  4984.6  232.63  4985.1  232.13
  5010.4  232.63  5013.6  238.13  5028.6  238.26  5620.6  237.79  5728.7  240.81
  5757.3   237.6  5793.3  240.94  6032.2  236.48  6053.2  238.97  6168.9  239.62
  6833.4  241.32  7170.9  244.51  7431.3  256.28  7747.8  277.14  7884.5  280.83
#Mann= 13 ,-1 , 0
  3362.3     .05       0  3721.1    .035       0  3726.4     .05       0
  4259.6     .07       0    4361     .12       0  4577.8     .07       0
  4668.9     .12       0  4984.6     .05       0  5010.4     .12       0
  6168.9      .1       0  6833.4     .07       0  7170.9    .035       0
  7431.3     .07       0
Bank Sta=4984.6,5010.4
XS Rating Curve= 0 ,0
Exp/Cntr=0.3,0.1

Type RM Length L Ch R = 1 ,8913    ,515,515,515
BEGIN DESCRIPTION:
WEST ROCKY CREEK 10.0
END DESCRIPTION:
XS GIS Cut Line= 3
      2427975.03       13632975.        2429575.       13633075.
      2431975.01     13631074.99
#Sta/Elev= 30
  3392.7  276.67  3833.5  262.79  4043.9  251.59  4447.2  240.61  4458.3  240.38
  4650.2  238.14  4729.6  236.52    4999  236.88    5003  235.91  5004.3   230.1
  5004.8   229.6  5030.2   230.1  5031.6  236.06  5038.1  236.78  5220.1   237.4
  5572.1  238.64  5855.1  238.65  5924.1  238.24  5986.3  238.46  6072.8  237.92
  6248.7  239.07  6429.6  239.11  6458.3  237.96  6479.7  233.49  6486.9  238.61
  6501.2  239.34    7012  240.73  7410.5  244.55  7681.1  254.59  8119.9  282.86
#Mann= 17 ,-1 , 0
  3392.7     .05       0  4447.2     .12       0  4458.3     .05       0
  4650.2     .07       0  4729.6     .12       0  5004.3     .05       0
  5030.2     .12       0  5220.1     .07       0  5572.1     .12       0
  5855.1     .07       0  5924.1     .12       0  5986.3     .07       0
  6072.8     .12       0  6248.7      .1       0    7012     .07       0
  7410.5    .035       0  7681.1     .07       0
Bank Sta=5004.3,5030.2
XS Rating Curve= 0 ,0
Exp/Cntr=0.3,0.1

Type RM Length L Ch R = 1 ,8398    ,563,563,563
BEGIN DESCRIPTION:
WEST ROCKY CREEK 9.0
END DESCRIPTION:
XS GIS Cut Line= 3
        2428825.       13633875.        2429625.       13633525.
      2432025.02     13631324.98
#Sta/Elev= 30
  4108.8  256.27  4725.4  234.71    4892  235.14  4905.6  230.71  4920.8  234.65
    4982  235.89  4982.9  230.32  4983.4  229.82  5008.8  230.32  5010.1  234.13
  5017.5  235.61  5066.8  236.04  5102.6  233.96  5675.4  238.36  6100.3  235.14
  6149.6  238.04  6316.1  237.72  6366.4  237.94  6609.9  238.65  6645.4  236.12
  6652.1  232.55  6702.1  237.39  6751.6  238.04  6888.7  239.49  7041.4  242.45
  7214.6  244.33  7332.1  244.63    7714  246.77  7834.2  250.87  8237.8  275.73
#Mann= 11 ,-1 , 0
  4108.8     .05       0  4725.4     .12       0  4982.9     .05       0
  5008.8     .12       0  6316.1    .035       0  6366.4      .1       0
  6751.6     .07       0  6888.7     .05       0  7041.4     .07       0
  7214.6     .05       0  7332.1     .07       0
Bank Sta=4982.9,5008.8
XS Rating Curve= 0 ,0
Exp/Cntr=0.3,0.1

Type RM Length L Ch R = 1 ,7835    ,591,591,591
BEGIN DESCRIPTION:
WEST ROCKY CREEK 8.0
END DESCRIPTION:
XS GIS Cut Line= 3
      2429125.01     13634674.99        2429775.       13633975.
      2432174.97     13631575.03
#Sta/Elev= 30
  4040.4  257.38  4287.4  248.52  4436.6  242.83  4644.5  236.66  4884.2   232.7
  4967.6  234.98  4996.7  230.32  4997.2  229.82  5022.9  230.32  5066.3  234.41
  5207.8  232.72  5309.3  234.35    5387  234.67  5704.9  236.53  5872.4  237.26
  5957.3  234.34  5997.9  235.89    6534  237.11  6664.4   237.4  6692.7  232.02
  6706.8  236.88  6799.2  236.65  6894.3  237.74  7343.2  243.65  7385.7  242.42
  7498.8  246.62  7739.8  249.61  7908.9  249.68    8121  253.79  8389.7  263.67
#Mann= 15 ,-1 , 0
  4040.4     .05       0  4287.4    .035       0  4436.6     .05       0
  4644.5     .07       0  4884.2     .12       0  4996.7     .05       0
  5022.9     .12       0  5309.3     .07       0    5387     .12       0
  5704.9     .07       0  5997.9     .12       0    6534      .1       0
  6799.2     .07       0  6894.3     .05       0  7739.8     .07       0
Bank Sta=4996.7,5022.9
XS Rating Curve= 0 ,0
Exp/Cntr=0.3,0.1

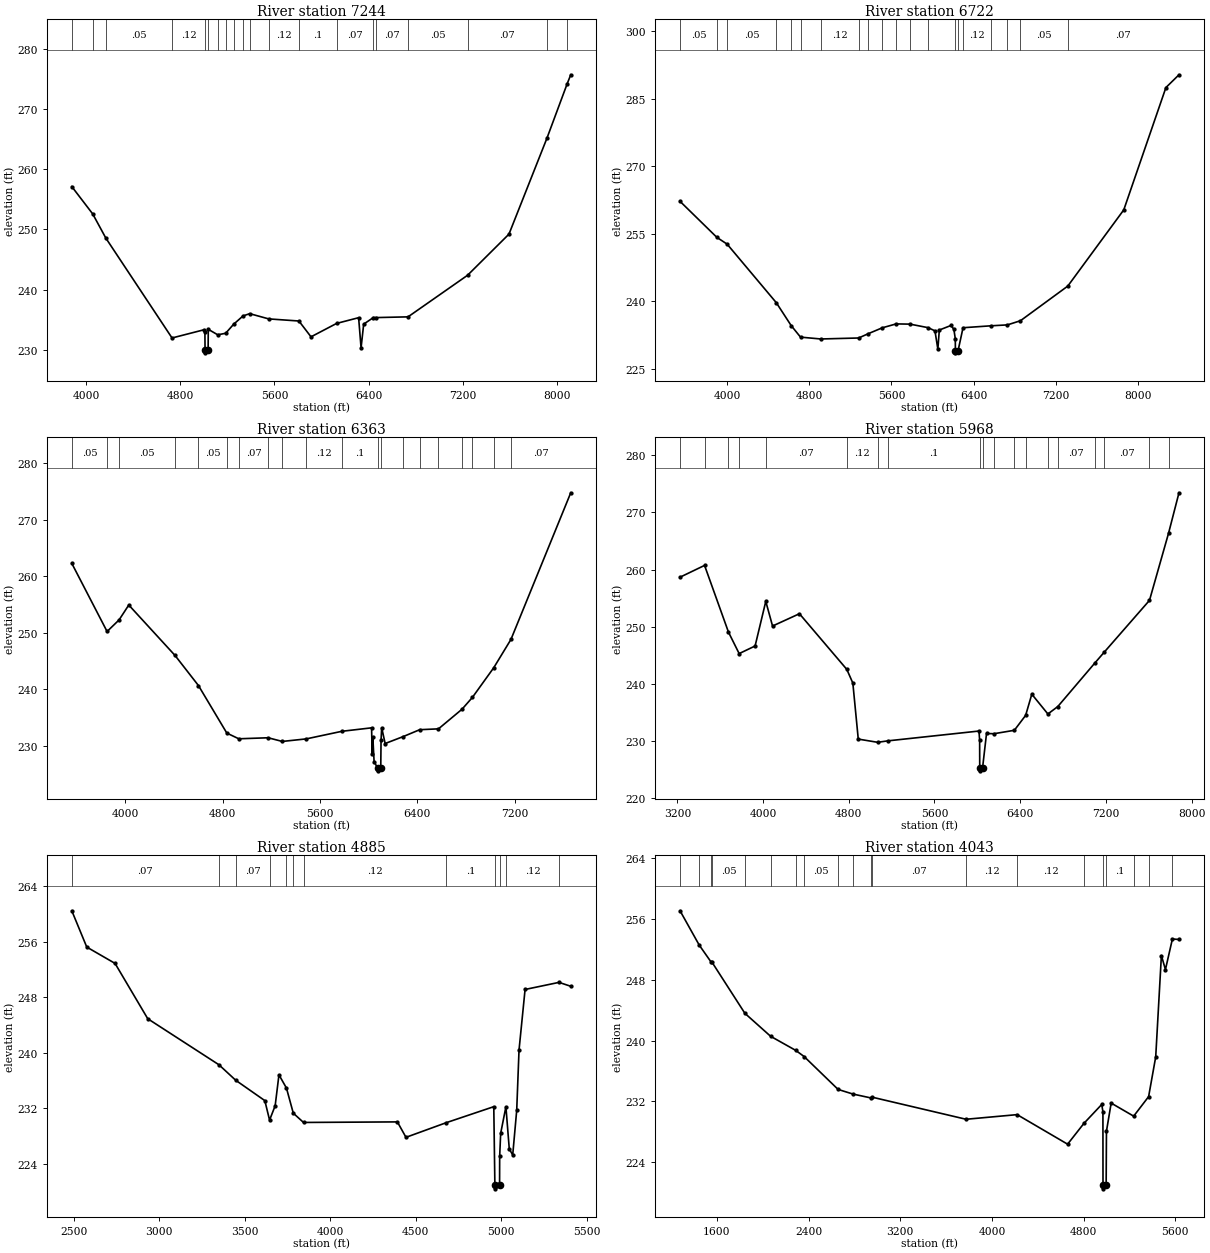
Type RM Length L Ch R = 1 ,7244    ,522,522,522
BEGIN DESCRIPTION:
WEST ROCKY CREEK 7.0
END DESCRIPTION:
XS GIS Cut Line= 3
        2429225.       13634825.        2430225.       13634325.
      2432624.97     13632325.02
#Sta/Elev= 30
  3876.9  257.12  4054.9  252.57  4166.5  248.55  4729.1  231.96  5002.1  233.33
  5008.6  233.02  5009.8  229.99  5010.3  229.49    5036  229.99  5037.2   233.4
  5117.4  232.49  5184.9  232.74  5253.7  234.26  5333.2  235.63  5389.6     236
  5551.2  235.13  5807.8  234.78  5910.7  232.15  6128.4  234.38  6315.5  235.33
  6336.3  230.31  6358.5  234.26  6441.5  235.36  6465.2  235.35  6735.7  235.47
  7241.6  242.38  7593.8  249.22  7917.2  265.19  8088.7  274.21    8119   275.7
#Mann= 20 ,-1 , 0
  3876.9     .05       0  4054.9    .035       0  4166.5     .05       0
  4729.1     .12       0  5009.8     .05       0    5036     .12       0
  5117.4     .07       0  5184.9     .12       0  5253.7     .07       0
  5333.2     .12       0  5389.6     .07       0  5551.2     .12       0
  5807.8      .1       0  6128.4     .07       0  6441.5     .12       0
  6465.2     .07       0  6735.7     .05       0  7241.6     .07       0
  7917.2     .07       0  8088.7     .07       0
Bank Sta=5009.8,5036
XS Rating Curve= 0 ,0
Exp/Cntr=0.3,0.1

Type RM Length L Ch R = 1 ,6722    ,359,359,359
BEGIN DESCRIPTION:
WEST ROCKY CREEK 6.0
END DESCRIPTION:
XS GIS Cut Line= 3
      2429025.03       13634925.        2430475.       13634725.
      2432874.99     13632325.01
#Sta/Elev= 30
  3541.2  262.16    3900  254.15  3999.7  252.65  4478.7  239.63  4623.8  234.53
  4714.3  231.98  4911.9  231.57    5280  231.79  5374.2  232.75  5509.7  234.05
  5645.1  234.92  5780.5  234.87  5955.6  234.09  6023.1  233.38  6051.4  229.32
  6065.6  233.56  6178.7  234.57    6207  233.74  6221.1  231.65  6222.2  228.99
  6222.7  228.49  6248.4  228.99  6296.5  234.07  6569.3   234.5  6728.5   234.7
  6855.8  235.63  7316.6  243.33  7861.6  260.27  8271.7  287.45    8399  290.29
#Mann= 20 ,-1 , 0
  3541.2     .05       0    3900    .035       0  3999.7     .05       0
  4478.7     .07       0  4623.8     .05       0  4714.3     .07       0
  4911.9     .12       0    5280     .12       0  5374.2     .07       0
  5509.7     .12       0  5645.1     .07       0  5780.5     .12       0
  5955.6      .1       0  6222.2     .05       0  6248.4      .1       0
  6296.5     .12       0  6569.3     .12       0  6728.5     .07       0
  6855.8     .05       0  7316.6     .07       0
Bank Sta=6222.2,6248.4
XS Rating Curve= 0 ,0
Exp/Cntr=0.3,0.1

Type RM Length L Ch R = 1 ,6363    ,395,395,395
BEGIN DESCRIPTION:
H21753
END DESCRIPTION:
XS GIS Cut Line= 3
      2429087.05     13634997.87       2430675.6       13635042.
      2433087.93     13634350.66
#Sta/Elev= 30
    3562  262.28  3851.8  250.21  3950.2  252.26  4030.1   254.9  4410.2  245.96
  4602.4  240.63  4835.4  232.21  4933.7   231.2  5174.7  231.38  5291.1  230.73
  5487.8  231.18  5781.6  232.53  6024.4  233.14  6029.6   228.5  6034.8  231.48
  6045.2  227.16  6073.6  226.02  6074.1  225.52  6099.9  226.02  6102.3   230.9
  6107.6  233.16    6136  230.36  6285.4   231.6    6420  232.81  6574.2  232.96
  6767.6  236.44  6852.6  238.53    7028  243.79  7169.5  248.81  7660.6  274.79
#Mann= 20 ,-1 , 0
    3562     .05       0  3851.8    .035       0  3950.2     .05       0
  4410.2     .07       0  4602.4     .05       0  4835.4     .12       0
  4933.7     .07       0  5174.7     .12       0  5291.1      .1       0
  5487.8     .12       0  5781.6      .1       0  6073.6     .05       0
  6099.9      .1       0  6285.4     .12       0    6420     .07       0
  6574.2    .035       0  6767.6     .07       0  6852.6     .05       0
    7028     .05       0  7169.5     .07       0
Bank Sta=6073.6,6099.9
XS Rating Curve= 0 ,0
Exp/Cntr=0.3,0.1

Type RM Length L Ch R = 1 ,5968    ,1083,1083,1083
BEGIN DESCRIPTION:
H21752
END DESCRIPTION:
XS GIS Cut Line= 3
      2428829.61     13635071.41      2430440.25     13635372.95
      2433440.43     13635703.85
#Sta/Elev= 30
  3225.1  258.68    3454  260.74  3677.3  249.07  3776.9  245.32  3925.7  246.65
  4025.4  254.45  4088.6  250.14  4339.5  252.29  4781.7  242.56    4838  240.17
  4888.6  230.37  5069.4  229.81  5168.1  230.07  6015.4  231.78  6021.5  230.17
  6022.4  225.32  6022.9  224.82  6048.7  225.32  6085.8  231.35  6154.9  231.31
  6345.5  231.91  6450.9  234.52  6508.4  238.22  6658.6  234.76  6751.4  236.07
  7096.7  243.67  7182.5  245.53  7606.8  254.63  7785.1  266.39  7882.1  273.44
#Mann= 19 ,-1 , 0
  3225.1     .07       0    3454     .05       0  3677.3    .035       0
  3776.9     .05       0  4025.4     .07       0  4781.7     .12       0
  5069.4     .07       0  5168.1      .1       0  6022.4     .05       0
  6048.7      .1       0  6154.9     .12       0  6345.5    .035       0
  6450.9    .063       0  6658.6    .035       0  6751.4     .07       0
  7096.7     .05       0  7182.5     .07       0  7606.8    .035       0
  7785.1     .07       0
Bank Sta=6022.4,6048.7
XS Rating Curve= 0 ,0
Exp/Cntr=0.3,0.1

Type RM Length L Ch R = 1 ,4885    ,842,842,842
BEGIN DESCRIPTION:
H21751
END DESCRIPTION:
XS GIS Cut Line= 3
      2428303.77     13635659.78       2430885.2     13635961.31
      2431141.29     13636151.55
#Sta/Elev= 30
  2488.1  260.44  2575.6  255.22    2741  252.87  2932.3  244.91  3348.5  238.29
  3447.2  236.05    3617  233.13  3644.7  230.33  3677.4  232.39  3699.6  236.84
  3743.4  234.94  3783.5  231.32  3843.2  229.99  4392.2  230.07  4442.5  227.85
  4677.2  229.95    4956  232.26  4962.4  220.94  4962.9  220.44  4989.9  220.94
  4990.4  225.13  4996.3  228.42  5026.9  232.25  5046.6  226.18  5066.7  225.31
  5090.1  231.75  5103.6   240.4    5139  249.12  5337.4  250.14  5406.1  249.58
#Mann= 12 ,-1 , 0
  2488.1     .07       0  3348.5    .035       0  3447.2     .07       0
  3644.7     .05       0  3743.4    .035       0  3783.5     .07       0
  3843.2     .12       0  4677.2      .1       0  4962.4     .05       0
  4989.9      .1       0  5026.9     .12       0  5337.4     .07       0
Bank Sta=4962.4,4989.9
XS Rating Curve= 0 ,0
Exp/Cntr=0.3,0.1

Type RM Length L Ch R = 1 ,4043    ,1111,1111,1111
BEGIN DESCRIPTION:
H21750
END DESCRIPTION:
XS GIS Cut Line= 4
      2427112.35     13636343.76      2429031.86     13637013.01
      2430936.69     13636564.39      2431194.09     13636306.98
#Sta/Elev= 30
  1277.9  257.09  1445.4  252.57  1548.5  250.35  1558.1  250.29  1843.8  243.59
  2067.8  240.57  2287.2  238.71  2360.6   237.9  2657.1  233.57  2786.6  232.96
    2943  232.45  2956.6  232.54  3773.8  229.64  4219.3  230.25  4659.8  226.36
  4802.8  229.11  4957.7  231.59    4968  230.63  4968.7  220.98  4969.2  220.48
  4996.2  220.98  4998.8  228.06  5039.9  231.77  5236.3  230.05  5366.7  232.62
  5428.7  237.86  5478.2   251.2  5513.5  249.35  5574.3  253.38  5631.7  253.31
#Mann= 20 ,-1 , 0
  1277.9     .07       0  1445.4    .035       0  1548.5     .07       0
  1558.1     .05       0  1843.8    .035       0  2067.8     .05       0
  2287.2     .07       0  2360.6     .05       0  2657.1    .035       0
  2786.6     .07       0    2943    .035       0  2956.6     .07       0
  3773.8     .12       0  4219.3     .12       0  4802.8      .1       0
  4968.7     .05       0  4996.2      .1       0  5236.3    .035       0
  5366.7    .063       0  5574.3    .035       0
Bank Sta=4968.7,4996.2
XS Rating Curve= 0 ,0
Exp/Cntr=0.3,0.1

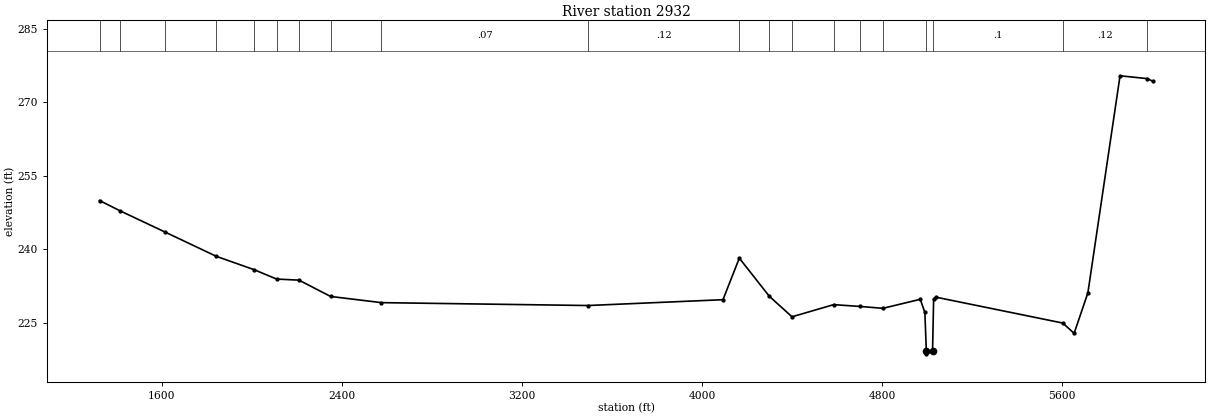
Type RM Length L Ch R = 1 ,2932    ,0,0,0
BEGIN DESCRIPTION:
H21749
END DESCRIPTION:
XS GIS Cut Line= 3
      2427060.81     13637174.81      2430017.37     13637719.05
      2431657.48     13637388.08
#Sta/Elev= 30
    1323  249.97    1413   247.9  1612.1  243.58  1841.6  238.59  2010.2  235.85
  2109.7  233.94  2209.2  233.72  2349.8  230.39  2575.5  229.13  3492.1  228.54
    4093  229.73  4165.5  238.21  4299.2  230.41  4399.7  226.24  4584.7  228.72
  4702.6  228.35  4803.5  227.97  4969.5  229.81  4989.9  227.14  4996.5  219.18
    4997  218.68  5024.1  219.18  5028.9  229.91  5040.9  230.23  5602.9  224.96
    5653  222.86  5714.2  231.13    5857  275.43  5978.2  274.85  6002.4  274.32
#Mann= 20 ,-1 , 0
    1323     .05       0    1413    .035       0  1612.1     .05       0
  1841.6    .035       0  2010.2     .05       0  2109.7     .07       0
  2209.2    .035       0  2349.8     .05       0  2575.5     .07       0
  3492.1     .12       0  4165.5    .063       0  4299.2    .035       0
  4399.7     .12       0  4584.7    .035       0  4702.6     .12       0
  4803.5      .1       0  4996.5     .05       0  5024.1      .1       0
  5602.9     .12       0  5978.2     .07       0
Bank Sta=4996.5,5024.1
XS Rating Curve= 0 ,0
Exp/Cntr=0.3,0.1

Chan Stop Cuts=-1
Use User Specified Reach Order=0
Composite Channel Slope=5