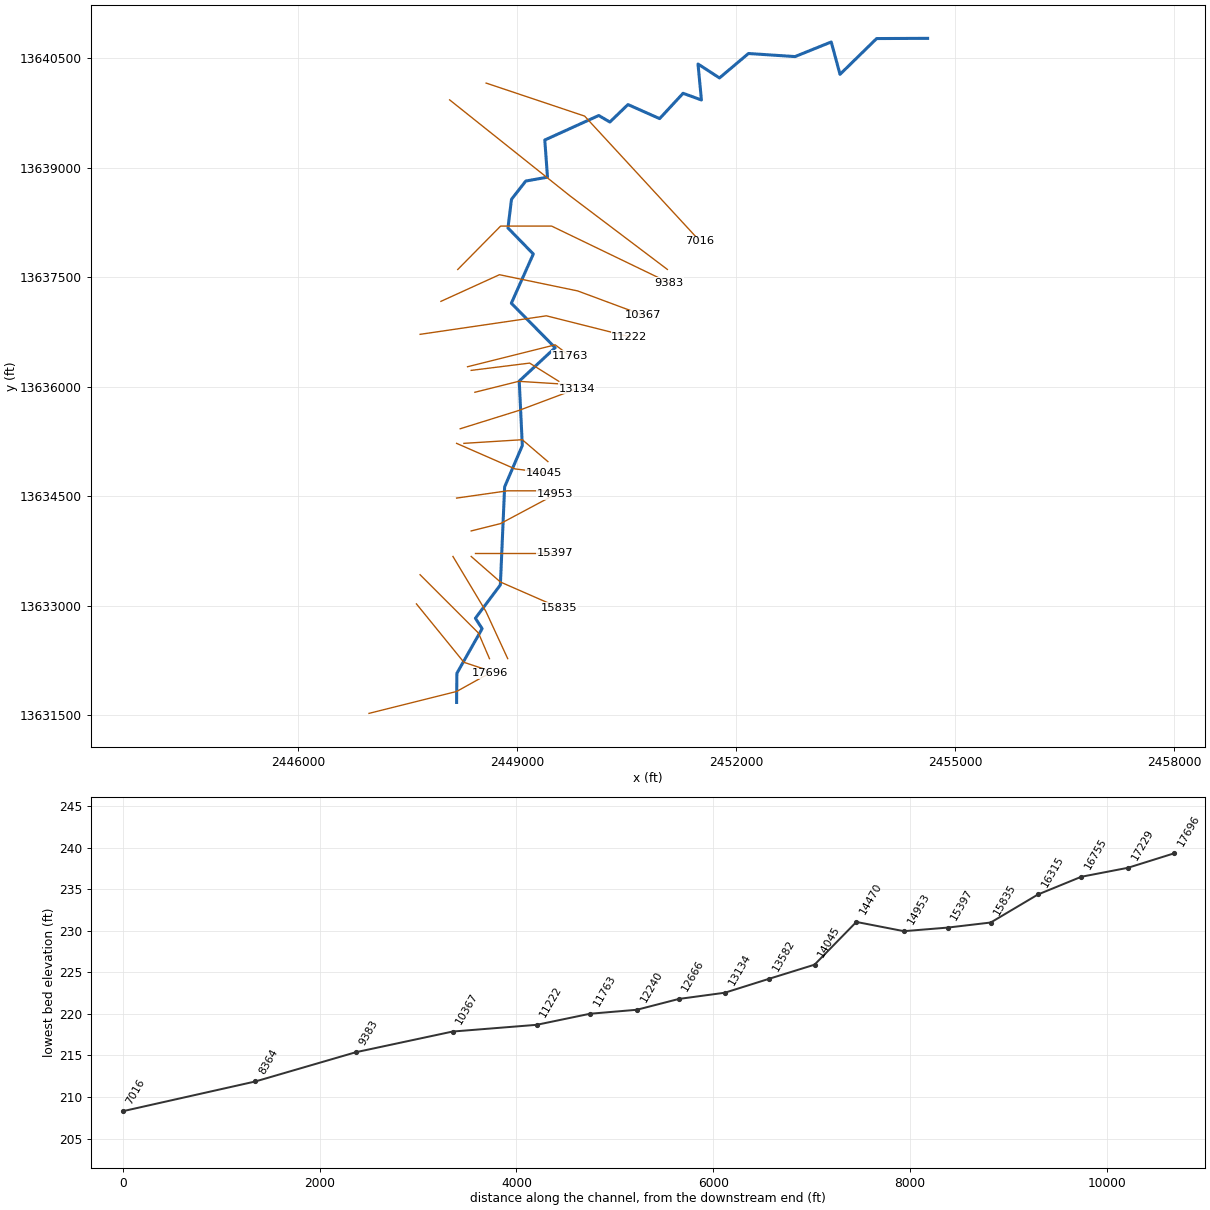
--- WHITE OAK BRANCH.prj (project) ---

Proj Title=WHITE OAK BRANCH Base Level Engineering
Current Plan=p01
Default Exp/Contr=0.3,0.1
English Units
Geom File=g01
Flow File=f01
Plan File=p01
Y Axis Title=Elevation
X Axis Title(PF)=Main Channel Distance
X Axis Title(XS)=Station
BEGIN DESCRIPTION:
WHITE OAK BRANCH
END DESCRIPTION:
DSS Export Rating Curves= 0
DSS Export Rating Curve Sorted= 0
DSS Export Volume Flow Curves= 0
DXF OffsetX= 0
DXF OffsetY= 0
DXF ScaleX= 1
DXF ScaleY= 10

--- WHITE OAK BRANCH.p01 (plan) ---

Plan Title=Multiple Run
Short Identifier=Multiple
Geom File=g01
Flow File=f01
Subcritical Flow
K Sum by GR= 0
Std Step Tol= 0.01
Critical Tol= 0.01
Num of Std Step Trials= 20
Max Error Tol= 0.3
Flow Tol Ratio= 0.001
Split Flow NTrial= 30
Split Flow Tol= 0.02
Split Flow Ratio= 0.02
Log Output Level= 0
Friction Slope Method= 1
Unsteady Friction Slope Method= 2
Unsteady Bridges Friction Slope Method= 1
Parabolic Critical Depth
Global Vel Dist=  1 , 1 , 1
Global Log Level= 0
CheckData=True
Encroach Param= -1, 0, 0, 0
BEGIN DESCRIPTION:
Multiple Run
END DESCRIPTION:

--- WHITE OAK BRANCH.f01 (steady flow) ---

Flow Title=Multiple
Number of Profiles=7
Profile Names=10-year,25-year,50-year,1pct_min,100-year,1pct_plu,500-year
River Rch & RM= WHITE OAK BRANCH,Reach-1,17696
     665    1070    1434     930    1856    3703    3081
River Rch & RM= WHITE OAK BRANCH,Reach-1,16755
     936    1529    2069    1354    2701    5389    4561
River Rch & RM= WHITE OAK BRANCH,Reach-1,10367
     990    1619    2192    1434    2861    5707    4831
River Rch & RM= WHITE OAK BRANCH,Reach-1,8364
    1745    2942    4068    2714    5415   10804    9512
Boundary for River Rch & Prof#=WHITE OAK BRANCH,Reach-1,1
Up Type=0
Dn Type=3
Dn Slope=0.005
Boundary for River Rch & Prof#=WHITE OAK BRANCH,Reach-1,2
Up Type=0
Dn Type=3
Dn Slope=0.005
Boundary for River Rch & Prof#=WHITE OAK BRANCH,Reach-1,3
Up Type=0
Dn Type=3
Dn Slope=0.005
Boundary for River Rch & Prof#=WHITE OAK BRANCH,Reach-1,4
Up Type=0
Dn Type=3
Dn Slope=0.005
Boundary for River Rch & Prof#=WHITE OAK BRANCH,Reach-1,5
Up Type=0
Dn Type=3
Dn Slope=0.005
Boundary for River Rch & Prof#=WHITE OAK BRANCH,Reach-1,6
Up Type=0
Dn Type=3
Dn Slope=0.005
Boundary for River Rch & Prof#=WHITE OAK BRANCH,Reach-1,7
Up Type=0
Dn Type=3
Dn Slope=0.005

--- WHITE OAK BRANCH.g01 (geometry) ---

Geom Title=Existing Conditions
Program Version=4.10

River Reach=WHITE OAK BRANCH,Reach-1
Reach XY= 30
        2448175.       13631675.      2448178.82     13632073.42
      2448524.44     13632685.64       2448432.5     13632828.58
      2448774.39     13633285.62      2448832.72     13634628.66
      2449074.96     13635195.03      2449032.82     13636078.44
      2449524.48     13636535.45      2448924.62     13637145.05
      2449225.45     13637819.82      2448878.37     13638176.28
      2448926.68     13638568.86       2449122.3     13638819.64
      2449419.75     13638872.35      2449382.67     13639381.52
      2450121.66      13639717.4      2450273.57     13639628.01
      2450521.85     13639867.47      2450955.14     13639674.91
      2451276.65     13640021.89      2451527.75     13639930.29
      2451480.65     13640423.42       2451774.7      13640232.2
      2452171.58     13640567.19      2452809.64      13640524.9
      2453305.06     13640725.26      2453425.29     13640281.46
      2453926.65      13640771.9        2454625.       13640775.

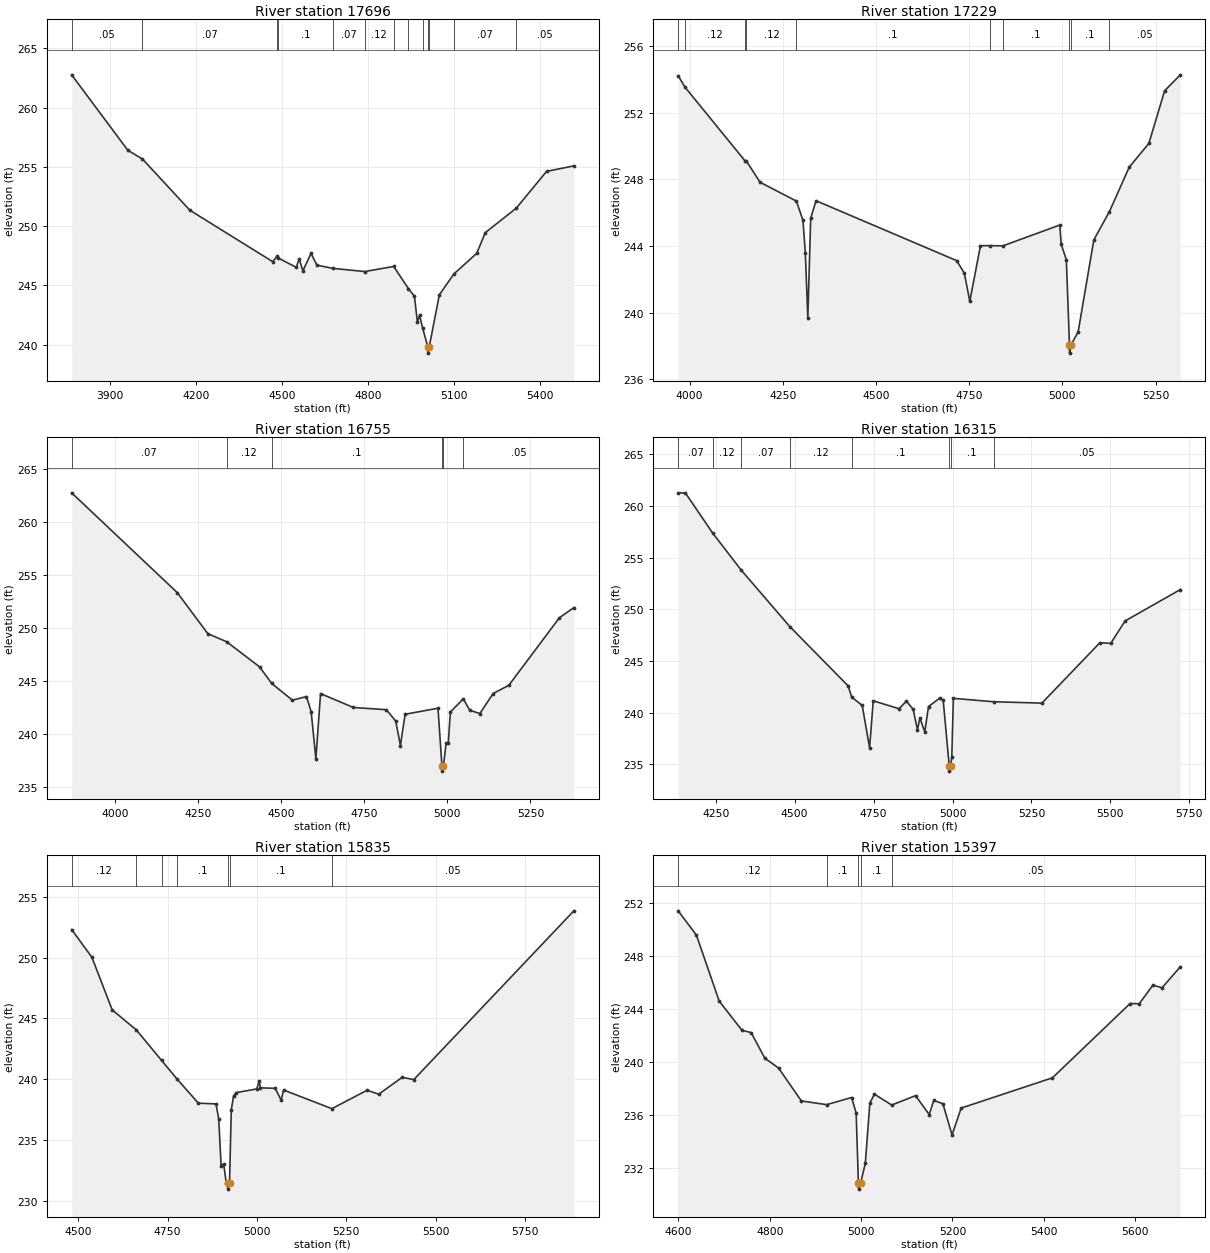
Type RM Length L Ch R = 1 ,17696   ,467,467,467
BEGIN DESCRIPTION:
WHITE OAK BRANCH 29.0
END DESCRIPTION:
XS GIS Cut Line= 3
      2446974.96     13631524.99        2448175.       13631825.
      2448625.04     13632075.02
#Sta/Elev= 30
  3767.2  262.76  3963.1   256.4  4014.2  255.66  4179.6  251.34  4468.2  247.01
  4483.3  247.44  4487.8  247.31  4550.6  246.53  4560.9  247.23  4573.8  246.23
  4602.2   247.7  4622.8  246.71  4677.5  246.44  4789.9  246.17  4890.6   246.6
    4942  244.73  4962.9  244.09  4973.3  241.92    4981  242.48  4991.3  241.42
    5010  239.79  5010.3  239.29  5014.3  239.79  5049.9  244.21  5100.8  245.97
  5180.3  247.71  5210.1  249.45  5318.4  251.52    5424  254.62    5519  255.08
#Mann= 13 ,-1 , 0
  3767.2     .05       0  4014.2     .07       0  4483.3     .12       0
  4487.8      .1       0  4677.5     .07       0  4789.9     .12       0
  4890.6     .07       0    4942     .12       0  4991.3      .1       0
    5010     .05       0  5014.3      .1       0  5100.8     .07       0
  5318.4     .05       0
Bank Sta=5010,5014.3
XS Rating Curve= 0 ,0
Exp/Cntr=0.3,0.1

Type RM Length L Ch R = 1 ,17229   ,474,474,474
BEGIN DESCRIPTION:
WHITE OAK BRANCH 28.0
END DESCRIPTION:
XS GIS Cut Line= 3
      2447624.98     13633025.02        2448275.       13632225.
      2448574.97     13632125.01
#Sta/Elev= 30
  3969.2  254.24  3987.6  253.55  4149.3   249.1  4152.4  249.11    4189  247.83
  4286.5   246.7    4304  245.55  4310.4  243.59  4317.1  239.67  4324.8  245.67
  4339.2  246.72  4716.3  243.12  4737.1  242.36  4751.5  240.67  4780.2  244.02
  4805.3  244.02  4840.5  244.01  4992.8  245.26  4996.8   244.1  5010.5  243.18
  5018.9  238.06  5019.2  237.56  5023.2  238.06  5042.2  238.84  5084.3  244.37
  5125.9  246.06  5179.2  248.74  5231.9  250.17  5274.1  253.33  5316.2  254.29
#Mann= 10 ,-1 , 0
  3969.2     .07       0  3987.6     .12       0  4149.3     .07       0
  4152.4     .12       0  4286.5      .1       0  4805.3     .12       0
  4840.5      .1       0  5018.9     .05       0  5023.2      .1       0
  5125.9     .05       0
Bank Sta=5018.9,5023.2
XS Rating Curve= 0 ,0
Exp/Cntr=0.3,0.1

Type RM Length L Ch R = 1 ,16755   ,440,440,440
BEGIN DESCRIPTION:
WHITE OAK BRANCH 27.0
END DESCRIPTION:
XS GIS Cut Line= 3
        2447675.       13633425.        2448475.       13632625.
      2448625.01     13632274.97
#Sta/Elev= 30
  3868.6  262.76  4186.8  253.33  4278.7  249.46  4335.2   248.7  4434.3  246.33
  4471.1  244.76  4533.3  243.18  4575.7  243.52  4589.9  242.09    4604  237.65
  4618.1   243.8  4717.1  242.49  4816.1  242.28  4844.4  241.21  4858.6   238.9
  4872.7  241.85  4971.7  242.42  4983.6  236.98  4983.9  236.48    4988  236.98
  4996.4  239.14  5002.7  239.14    5009  242.06    5048  243.31  5067.1  242.23
  5097.9  241.92  5137.8  243.81  5184.9  244.58  5337.2  250.96  5380.8  251.92
#Mann= 6 ,-1 , 0
  3868.6     .07       0  4335.2     .12       0  4471.1      .1       0
  4983.6     .05       0    4988      .1       0    5048     .05       0
Bank Sta=4983.6,4988
XS Rating Curve= 0 ,0
Exp/Cntr=0.3,0.1

Type RM Length L Ch R = 1 ,16315   ,480,480,480
BEGIN DESCRIPTION:
WHITE OAK BRANCH 26.0
END DESCRIPTION:
XS GIS Cut Line= 3
      2448125.02     13633674.97        2448575.       13632925.
        2448875.     13632274.99
#Sta/Elev= 30
  4130.9  261.27  4154.2  261.25    4240  257.39  4331.4  253.77    4485  248.32
  4669.3   242.6  4680.7  241.51    4714   240.7  4737.3  236.61  4748.9  241.15
  4830.6  240.39  4853.9  241.12  4875.3  240.33  4888.9  238.36  4896.7  239.49
  4912.2  238.16  4923.9   240.6  4960.8  241.44  4970.5  241.19  4989.6  234.85
    4990  234.35  4994.1  234.85  4997.7  235.74  5002.6  241.39  5130.7  241.06
  5283.1  240.93  5466.7  246.77  5501.1  246.71  5546.6  248.88  5721.4  251.91
#Mann= 8 ,-1 , 0
  4130.9     .07       0    4240     .12       0  4331.4     .07       0
    4485     .12       0  4680.7      .1       0  4989.6     .05       0
  4994.1      .1       0  5130.7     .05       0
Bank Sta=4989.6,4994.1
XS Rating Curve= 0 ,0
Exp/Cntr=0.3,0.1

Type RM Length L Ch R = 1 ,15835   ,438,438,438
BEGIN DESCRIPTION:
WHITE OAK BRANCH 25.0
END DESCRIPTION:
XS GIS Cut Line= 3
      2448374.97     13633675.03        2448775.       13633325.
      2449575.04     13632974.98
#Sta/Elev= 30
  4481.6   252.3  4538.1  250.03  4595.1   245.7  4662.5  244.06  4733.3  241.55
  4776.5  240.02  4836.1  238.04  4885.5  237.98  4893.1  236.72  4899.7  232.89
  4906.8  233.06    4914   231.5    4918  231.48  4918.4  230.98  4923.2  231.48
  4928.2  237.52  4934.8  238.65  4942.4  238.91  4999.4  239.21    5006  239.83
  5009.8   239.3    5051  239.26  5067.7  238.29  5074.4  239.12  5209.6  237.59
  5307.9   239.1  5340.6  238.78  5406.1  240.16  5438.8  239.98  5886.4  253.84
#Mann= 7 ,-1 , 0
  4481.6     .12       0  4662.5      .1       0  4733.3     .12       0
  4776.5      .1       0    4918     .05       0  4923.2      .1       0
  5209.6     .05       0
Bank Sta=4918,4923.2
XS Rating Curve= 0 ,0
Exp/Cntr=0.3,0.1

Type RM Length L Ch R = 1 ,15397   ,444,444,444
BEGIN DESCRIPTION:
WHITE OAK BRANCH 24.0
END DESCRIPTION:
XS GIS Cut Line= 3
        2448425.       13633725.        2448825.       13633725.
        2449525.       13633725.
#Sta/Elev= 30
  4599.2  251.42  4639.2  249.59  4689.2  244.59  4739.2  242.38  4759.2  242.21
  4789.2  240.27  4819.2  239.53  4869.2  237.04  4924.6  236.76  4979.2   237.3
  4989.2  236.12  4994.1  230.87  4994.5  230.37  4999.3  230.87  5009.2  232.32
  5019.2  236.88  5029.2  237.55  5067.1  236.73  5119.2  237.44  5149.2  236.01
  5159.2  237.08  5179.2  236.83  5199.2  234.47  5219.2   236.5  5419.2  238.79
  5589.2  244.41  5609.2  244.39  5639.2   245.8  5659.2   245.6  5699.2  247.19
#Mann= 5 ,-1 , 0
  4599.2     .12       0  4924.6      .1       0  4994.1     .05       0
  4999.3      .1       0  5067.1     .05       0
Bank Sta=4994.1,4999.3
XS Rating Curve= 0 ,0
Exp/Cntr=0.3,0.1

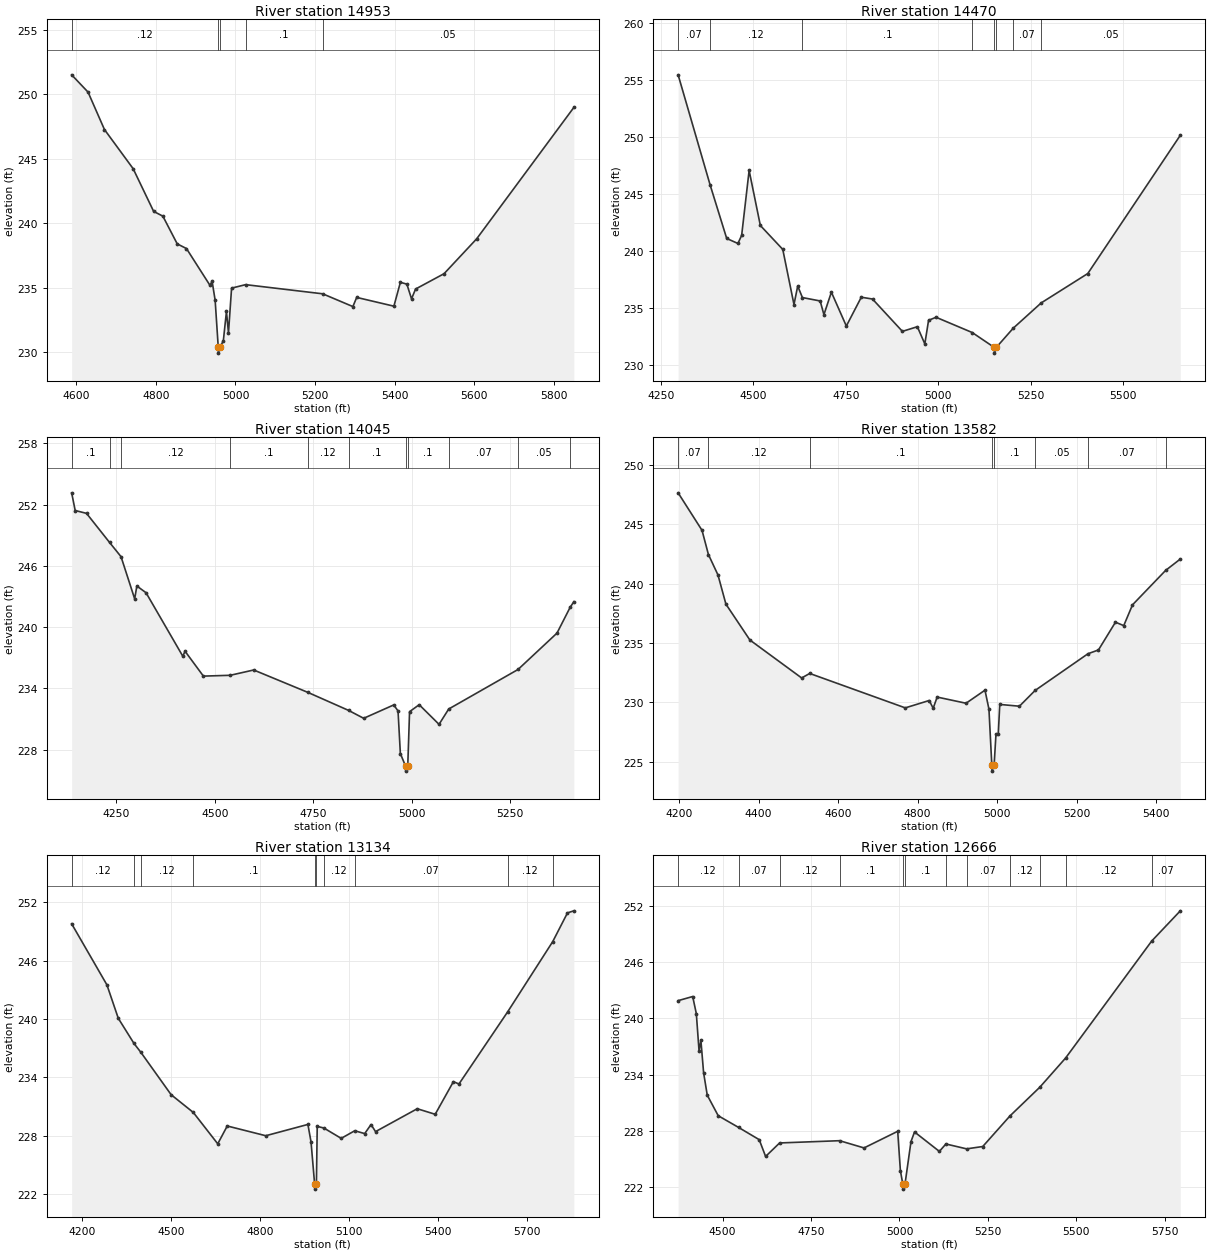
Type RM Length L Ch R = 1 ,14953   ,483,483,483
BEGIN DESCRIPTION:
WHITE OAK BRANCH 23.0
END DESCRIPTION:
XS GIS Cut Line= 3
      2448375.04     13634025.01        2448775.       13634125.
      2449525.03     13634525.02
#Sta/Elev= 30
  4588.2  251.52  4629.4  250.18  4670.6  247.28  4742.8  244.24  4794.3  240.93
  4817.5  240.56  4853.6  238.41  4876.8  238.05    4936  235.19  4941.2  235.52
  4948.9  234.04  4956.6  230.44    4957  229.94  4961.8  230.44  4969.5   230.9
  4977.3  233.17  4982.4  231.51  4990.2  234.98  5025.5  235.25  5219.2  234.54
  5295.1  233.55  5304.7  234.26  5398.2  233.58  5414.5  235.43  5430.8  235.29
  5442.5  234.15  5452.7  234.91  5524.3   236.1  5606.4  238.81  5850.5  248.99
#Mann= 5 ,-1 , 0
  4588.2     .12       0  4956.6     .05       0  4961.8     .12       0
  5025.5      .1       0  5219.2     .05       0
Bank Sta=4956.6,4961.8
XS Rating Curve= 0 ,0
Exp/Cntr=0.3,0.1

Type RM Length L Ch R = 1 ,14470   ,425,425,425
BEGIN DESCRIPTION:
WHITE OAK BRANCH 22.0
END DESCRIPTION:
XS GIS Cut Line= 3
      2448175.01       13634475.        2448875.       13634575.
        2449525.       13634575.
#Sta/Elev= 30
  4297.1  255.49  4383.5  245.83  4428.4  241.12  4458.7  240.68  4468.8  241.39
    4489  247.09  4519.3  242.26  4579.9  240.16  4610.2  235.32  4620.3  236.94
    4633  235.93    4681  235.63  4691.1  234.43  4711.3   236.4  4751.7  233.43
  4792.1  235.96  4822.4   235.8  4903.2  232.96  4943.6  233.37  4963.8  231.86
  4973.9  233.93  4994.1   234.2  5091.8  232.86  5151.5  231.55  5151.9  231.05
  5156.9  231.55  5202.7  233.24  5278.3  235.46  5404.2  238.04  5654.2  250.18
#Mann= 8 ,-1 , 0
  4297.1     .07       0  4383.5     .12       0    4633      .1       0
  5091.8     .05       0  5151.5     .05       0  5156.9     .05       0
  5202.7     .07       0  5278.3     .05       0
Bank Sta=5151.5,5156.9
XS Rating Curve= 0 ,0
Exp/Cntr=0.3,0.1

Type RM Length L Ch R = 1 ,14045   ,463,463,463
BEGIN DESCRIPTION:
WHITE OAK BRANCH 21.0
END DESCRIPTION:
XS GIS Cut Line= 3
      2448175.01     13635224.99        2448975.       13634875.
      2449374.99       13634825.
#Sta/Elev= 30
  4136.1  253.15  4145.1  251.42  4173.9  251.14  4232.3   248.3  4261.6   246.9
  4296.3  242.77  4301.8  244.03  4325.2  243.37  4418.7  237.15  4424.2  237.65
  4470.9  235.21  4539.1  235.29  4598.8  235.81  4736.9  233.61  4840.1  231.85
  4878.3  231.08  4954.7  232.39  4965.6   231.8  4971.5  227.63  4984.6  226.41
  4985.1  225.91  4990.3  226.41  4994.9  231.73  5019.4  232.41  5069.8  230.49
  5094.4  231.99  5270.6  235.86  5369.6  239.42  5402.8  241.93  5412.4  242.49
#Mann= 11 ,-1 , 0
  4136.1      .1       0  4232.3     .07       0  4261.6     .12       0
  4539.1      .1       0  4736.9     .12       0  4840.1      .1       0
  4984.6     .05       0  4990.3      .1       0  5094.4     .07       0
  5270.6     .05       0  5402.8     .07       0
Bank Sta=4984.6,4990.3
XS Rating Curve= 0 ,0
Exp/Cntr=0.3,0.1

Type RM Length L Ch R = 1 ,13582   ,448,448,448
BEGIN DESCRIPTION:
WHITE OAK BRANCH 20.0
END DESCRIPTION:
XS GIS Cut Line= 3
      2448274.99       13635225.        2449075.       13635275.
      2449425.04     13634974.97
#Sta/Elev= 30
  4197.8  247.66  4257.9   244.5    4274  242.46    4298  240.74    4318  238.28
  4378.2  235.26  4508.4  232.06  4528.7  232.44  4768.9  229.54    4829  230.16
  4839.1  229.51  4849.1  230.45  4921.7  229.93  4969.3  231.03  4979.3  229.43
  4986.5  224.71    4987  224.21  4992.3  224.71  4996.9   227.3  5002.7   227.3
  5006.5  229.83  5055.9  229.68  5095.4  231.01  5228.2   234.1  5254.6  234.42
  5297.4  236.76  5318.2  236.47  5340.2  238.22  5423.4  241.12  5460.4  242.08
#Mann= 8 ,-1 , 0
  4197.8     .07       0    4274     .12       0  4528.7      .1       0
  4986.5     .05       0  4992.3      .1       0  5095.4     .05       0
  5228.2     .07       0  5423.4     .05       0
Bank Sta=4986.5,4992.3
XS Rating Curve= 0 ,0
Exp/Cntr=0.3,0.1

Type RM Length L Ch R = 1 ,13134   ,468,468,468
BEGIN DESCRIPTION:
WHITE OAK BRANCH 19.0
END DESCRIPTION:
XS GIS Cut Line= 3
      2448224.97     13635424.99        2449025.       13635675.
      2449825.02     13635975.01
#Sta/Elev= 30
  4165.9  249.77  4284.8   243.5  4323.1  240.07    4376  237.49  4399.4  236.57
  4501.2  232.23  4575.9  230.41  4658.3  227.19  4690.3  229.02  4820.2  228.02
  4962.2  229.18  4972.7  227.39  4984.9  223.04  4985.4  222.54  4990.8  223.04
  4993.6  228.98    5016  228.81  5074.4  227.75    5120  228.53  5153.6  228.24
    5175  229.17  5190.1  228.44  5330.7  230.79  5391.2  230.22  5452.6  233.57
  5471.3  233.33  5635.8  240.75  5787.3  247.94  5837.1  250.89  5858.5   251.1
#Mann= 10 ,-1 , 0
  4165.9     .12       0    4376     .07       0  4399.4     .12       0
  4575.9      .1       0  4984.9     .05       0  4990.8      .1       0
    5016     .12       0    5120     .07       0  5635.8     .12       0
  5787.3     .07       0
Bank Sta=4984.9,4990.8
XS Rating Curve= 0 ,0
Exp/Cntr=0.3,0.1

Type RM Length L Ch R = 1 ,12666   ,426,426,426
BEGIN DESCRIPTION:
WHITE OAK BRANCH 18.0
END DESCRIPTION:
XS GIS Cut Line= 3
      2448425.03     13635925.01        2449025.       13636075.
        2449825.       13636025.
#Sta/Elev= 30
  4374.1  241.87  4415.3  242.31  4425.6  240.49  4433.3  236.51  4438.5  237.64
  4446.2  234.18  4456.5   231.8  4487.5  229.61  4545.2  228.36  4603.4  227.06
  4621.5  225.27  4661.1  226.71  4830.7  226.95  4899.8  226.18    4995  227.95
  5002.6  223.76  5009.6  222.29  5010.1  221.79  5015.5  222.29  5032.6  226.86
  5042.6  227.88  5112.8  225.81  5131.3   226.6  5189.9  226.08  5235.5  226.33
  5312.5  229.59  5396.9  232.65  5469.8  235.76  5713.2  248.22  5794.1  251.44
#Mann= 12 ,-1 , 0
  4374.1     .12       0  4545.2     .07       0  4661.1     .12       0
  4830.7      .1       0  5009.6     .05       0  5015.5      .1       0
  5131.3     .12       0  5189.9     .07       0  5312.5     .12       0
  5396.9     .07       0  5469.8     .12       0  5713.2     .07       0
Bank Sta=5009.6,5015.5
XS Rating Curve= 0 ,0
Exp/Cntr=0.3,0.1

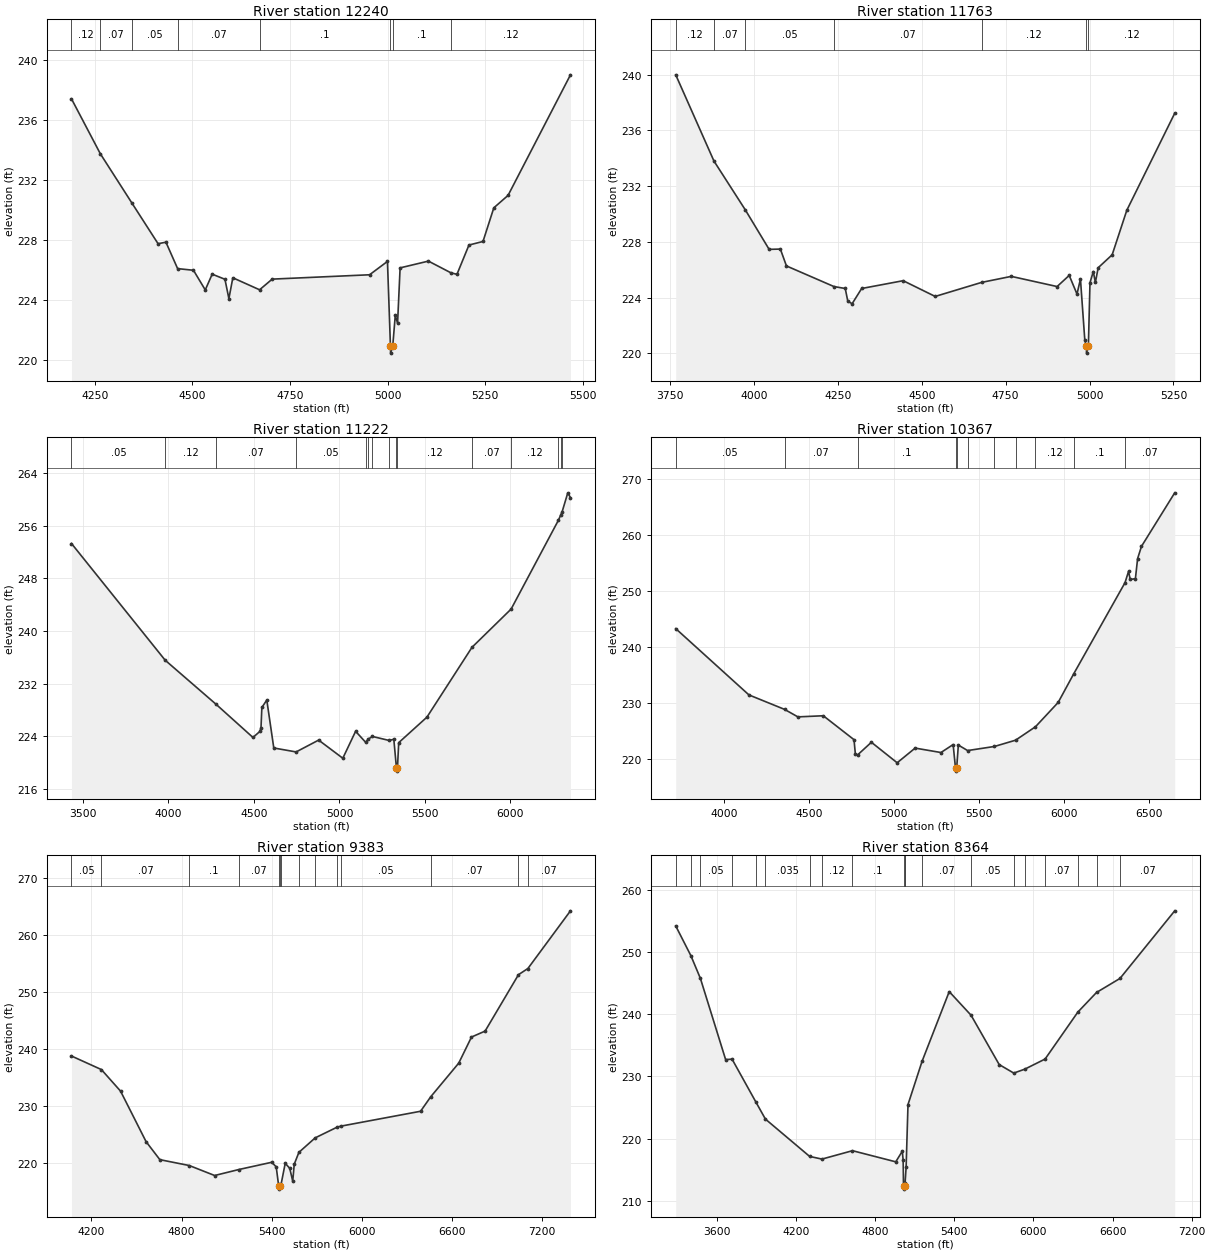
Type RM Length L Ch R = 1 ,12240   ,477,477,477
BEGIN DESCRIPTION:
WHITE OAK BRANCH 17.0
END DESCRIPTION:
XS GIS Cut Line= 3
      2448375.01       13636225.        2449175.       13636325.
      2449574.99     13636075.01
#Sta/Elev= 30
  4190.2  237.43  4264.1  233.77  4344.4  230.51  4411.9  227.78  4432.1  227.88
    4462  226.12  4502.6  226.01  4532.8   224.7  4550.5  225.75  4583.2  225.41
  4593.3  224.12  4603.4  225.51  4671.9  224.71  4704.2  225.42  4953.6  225.71
  4999.4   226.6    5007  220.99  5007.5  220.49    5013  220.99  5019.4     223
  5025.3  222.49  5031.8  226.17  5104.3  226.62    5162  225.84  5177.4  225.74
  5208.1  227.69  5244.1  227.93  5271.8  230.17  5308.3     231  5468.1  239.03
#Mann= 8 ,-1 , 0
  4190.2     .12       0  4264.1     .07       0  4344.4     .05       0
    4462     .07       0  4671.9      .1       0    5007     .05       0
    5013      .1       0    5162     .12       0
Bank Sta=5007,5013
XS Rating Curve= 0 ,0
Exp/Cntr=0.3,0.1

Type RM Length L Ch R = 1 ,11763   ,541,541,541
BEGIN DESCRIPTION:
WHITE OAK BRANCH 16.0
END DESCRIPTION:
XS GIS Cut Line= 3
      2448324.99       13636275.        2449525.       13636575.
      2449724.97     13636425.02
#Sta/Elev= 30
  3766.9  239.99  3880.8   233.8  3973.8  230.31  4045.2  227.46  4078.7  227.48
  4096.8  226.27  4238.3  224.79    4272  224.65  4279.7  223.73  4292.6  223.56
  4320.9  224.65  4444.6  225.21    4540  224.08  4678.7  225.09  4766.8  225.52
  4903.3  224.79  4939.4  225.59  4962.6  224.25  4972.9  225.33  4985.8  220.97
  4990.5  220.51    4991  220.01  4996.5  220.51  5001.3  225.06  5011.1  225.87
  5017.4  225.09  5025.7  226.14  5067.4  227.07  5111.1  230.27  5253.8  237.23
#Mann= 7 ,-1 , 0
  3766.9     .12       0  3880.8     .07       0  3973.8     .05       0
  4238.3     .07       0  4678.7     .12       0  4990.5     .05       0
  4996.5     .12       0
Bank Sta=4990.5,4996.5
XS Rating Curve= 0 ,0
Exp/Cntr=0.3,0.1

Type RM Length L Ch R = 1 ,11222   ,855,855,855
BEGIN DESCRIPTION:
H21782
END DESCRIPTION:
XS GIS Cut Line= 3
      2447675.05     13636718.85      2449404.51     13636972.72
      2450539.02     13636687.11
#Sta/Elev= 30
  3433.1   253.3  3980.9  235.55    4278  228.86  4494.3   223.8  4534.7  224.72
  4541.2  225.22  4546.3  228.36  4575.2  229.49  4616.1   222.2  4746.6   221.6
  4878.4   223.4  5019.7  220.64  5094.6  224.74    5153  223.07  5169.3  223.57
  5193.2  223.95  5289.9  223.35    5318  223.52  5333.3  219.18  5333.8  218.68
  5339.3  219.18  5346.6  223.01  5511.6  226.89    5775  237.51  6003.9  243.33
  6280.1  256.82  6293.1  257.58    6302  258.11  6335.3  261.01    6351  260.28
#Mann= 15 ,-1 , 0
  3433.1     .05       0  3980.9     .12       0    4278     .07       0
  4746.6     .05       0    5153     .07       0  5169.3     .12       0
  5193.2     .07       0  5289.9     .12       0  5333.3     .05       0
  5339.3     .12       0    5775     .07       0  6003.9     .12       0
  6280.1     .07       0  6293.1     .05       0    6302     .07       0
Bank Sta=5333.3,5339.3
XS Rating Curve= 0 ,0
Exp/Cntr=0.3,0.1

Type RM Length L Ch R = 1 ,10367   ,984,984,984
BEGIN DESCRIPTION:
H21781
END DESCRIPTION:
XS GIS Cut Line= 4
      2447960.64     13637171.04      2448761.92     13637535.98
      2449832.91     13637313.85      2450729.34     13636980.67
#Sta/Elev= 30
  3718.1   243.3  4147.9  231.47  4357.1  228.89  4435.5  227.55  4584.8  227.75
  4765.1  223.48    4773  220.95  4786.5  220.77  4867.2  223.02  5018.6  219.36
  5124.1  221.98  5275.8  221.19  5347.3  222.61  5361.3  218.37  5361.8  217.87
  5367.9  218.37  5377.9  222.52  5432.3  221.54  5589.8  222.27    5714  223.39
    5831  225.79  5964.2  230.13    6056  235.26  6356.8   251.5  6377.4   253.5
  6387.5  252.07  6417.8  252.21  6430.7  255.79  6453.5  257.98  6648.7  267.53
#Mann= 11 ,-1 , 0
  3718.1     .05       0  4357.1     .07       0  4786.5      .1       0
  5361.3     .05       0  5367.9      .1       0  5432.3     .07       0
  5589.8     .12       0    5714     .07       0    5831     .12       0
    6056      .1       0  6356.8     .07       0
Bank Sta=5361.3,5367.9
XS Rating Curve= 0 ,0
Exp/Cntr=0.3,0.1

Type RM Length L Ch R = 1 ,9383    ,1019,1019,1019
BEGIN DESCRIPTION:
H21780
END DESCRIPTION:
XS GIS Cut Line= 4
      2448190.69     13637607.35      2448777.79     13638202.38
      2449475.91     13638202.38      2451086.34     13637424.93
#Sta/Elev= 30
  4067.5  238.73  4266.7  236.35  4394.2  232.57  4563.9  223.72  4655.8  220.55
  4851.8  219.52  5020.6  217.77  5181.8  218.82  5400.6  220.09  5430.6  219.29
  5447.3  215.88  5447.8  215.38    5454  215.88  5460.5  215.89  5490.6  219.92
  5520.6  219.03  5540.6  216.78  5550.6  219.75  5581.6  221.83  5689.9  224.37
  5835.9  226.25  5861.5  226.43  6391.8  229.04    6459  231.57    6646  237.49
  6730.8  242.06  6821.3   243.1  7043.7     253  7106.3  254.08  7389.8   264.2
#Mann= 14 ,-1 , 0
  4067.5     .05       0  4266.7     .07       0  4851.8      .1       0
  5181.8     .07       0  5447.3     .05       0    5454     .07       0
  5460.5     .05       0  5581.6     .07       0  5689.9     .05       0
  5835.9     .07       0  5861.5     .05       0    6459     .07       0
  7043.7     .12       0  7106.3     .07       0
Bank Sta=5447.3,5454
XS Rating Curve= 0 ,0
Exp/Cntr=0.3,0.1

Type RM Length L Ch R = 1 ,8364    ,1348,1348,1348
BEGIN DESCRIPTION:
H21779
END DESCRIPTION:
XS GIS Cut Line= 3
      2448079.65     13639931.83      2449729.78     13638614.91
      2451061.31     13637608.33
#Sta/Elev= 30
    3291  254.19  3405.7  249.41  3477.9  245.75    3669   232.7  3717.8  232.77
  3899.1  225.84  3970.5  223.13  4305.4  217.13  4398.6   216.7  4630.1  218.05
  4957.9  216.26  5007.6  217.97    5014  216.51  5016.6  212.37  5017.1  211.87
  5027.3  212.37  5028.3  212.79  5036.4  215.38  5050.7  225.47  5157.2  232.42
    5363  243.63  5528.5  239.83  5741.5   231.9  5851.9  230.53  5935.5  231.16
  6089.4  232.79  6337.6  240.34  6478.8  243.49  6656.8  245.75  7071.4  256.62
#Mann= 20 ,-1 , 0
    3291     .05       0  3405.7    .035       0  3477.9     .05       0
  3717.8     .05       0  3899.1     .12       0  3970.5    .035       0
  4305.4     .07       0  4398.6     .12       0  4630.1      .1       0
  5016.6     .05       0  5027.3      .1       0  5028.3     .12       0
  5157.2     .07       0  5528.5     .05       0  5851.9     .07       0
  5935.5     .05       0  6089.4     .07       0  6337.6     .07       0
  6478.8     .12       0  6656.8     .07       0
Bank Sta=5016.6,5027.3
XS Rating Curve= 0 ,0
Exp/Cntr=0.3,0.1

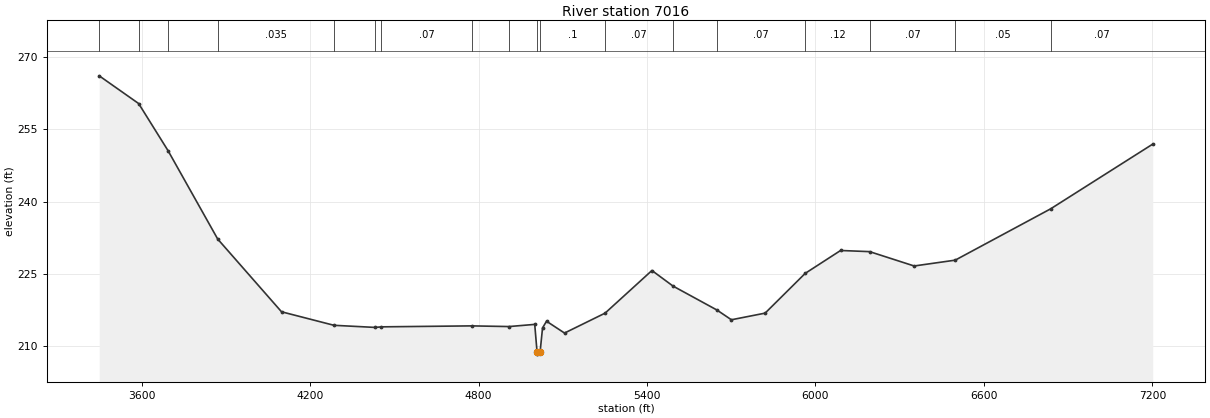
Type RM Length L Ch R = 1 ,7016    ,0,0,0
BEGIN DESCRIPTION:
H21778
END DESCRIPTION:
XS GIS Cut Line= 3
      2448579.43      13640161.9      2449928.11      13639709.7
      2451506.81     13637996.14
#Sta/Elev= 30
    3449  266.13  3589.4  260.37  3694.1  250.58  3871.1   232.2  4098.3  217.09
  4285.2  214.28    4432  213.84  4454.3  213.96  4775.9  214.16  4908.6  214.02
  5000.2  214.47  5008.4  208.79  5008.9  208.29  5019.4  208.79    5028  213.73
  5042.2  215.13  5106.3  212.67  5250.8  216.81  5417.6  225.67  5492.6  222.44
  5649.4  217.45  5700.6  215.43  5820.8  216.81  5963.7  225.08  6089.6  229.83
  6193.1  229.59  6351.6  226.61  6497.8  227.82  6837.6  238.48  7201.4  251.94
#Mann= 18 ,-1 , 0
    3449     .07       0  3589.4     .12       0  3694.1     .05       0
  3871.1    .035       0  4285.2     .07       0    4432    .035       0
  4454.3     .07       0  4775.9     .12       0  4908.6      .1       0
  5008.4     .05       0  5019.4      .1       0  5250.8     .07       0
  5492.6     .12       0  5649.4     .07       0  5963.7     .12       0
  6193.1     .07       0  6497.8     .05       0  6837.6     .07       0
Bank Sta=5008.4,5019.4
XS Rating Curve= 0 ,0
Exp/Cntr=0.3,0.1

Chan Stop Cuts=-1
Use User Specified Reach Order=0
Composite Channel Slope=5