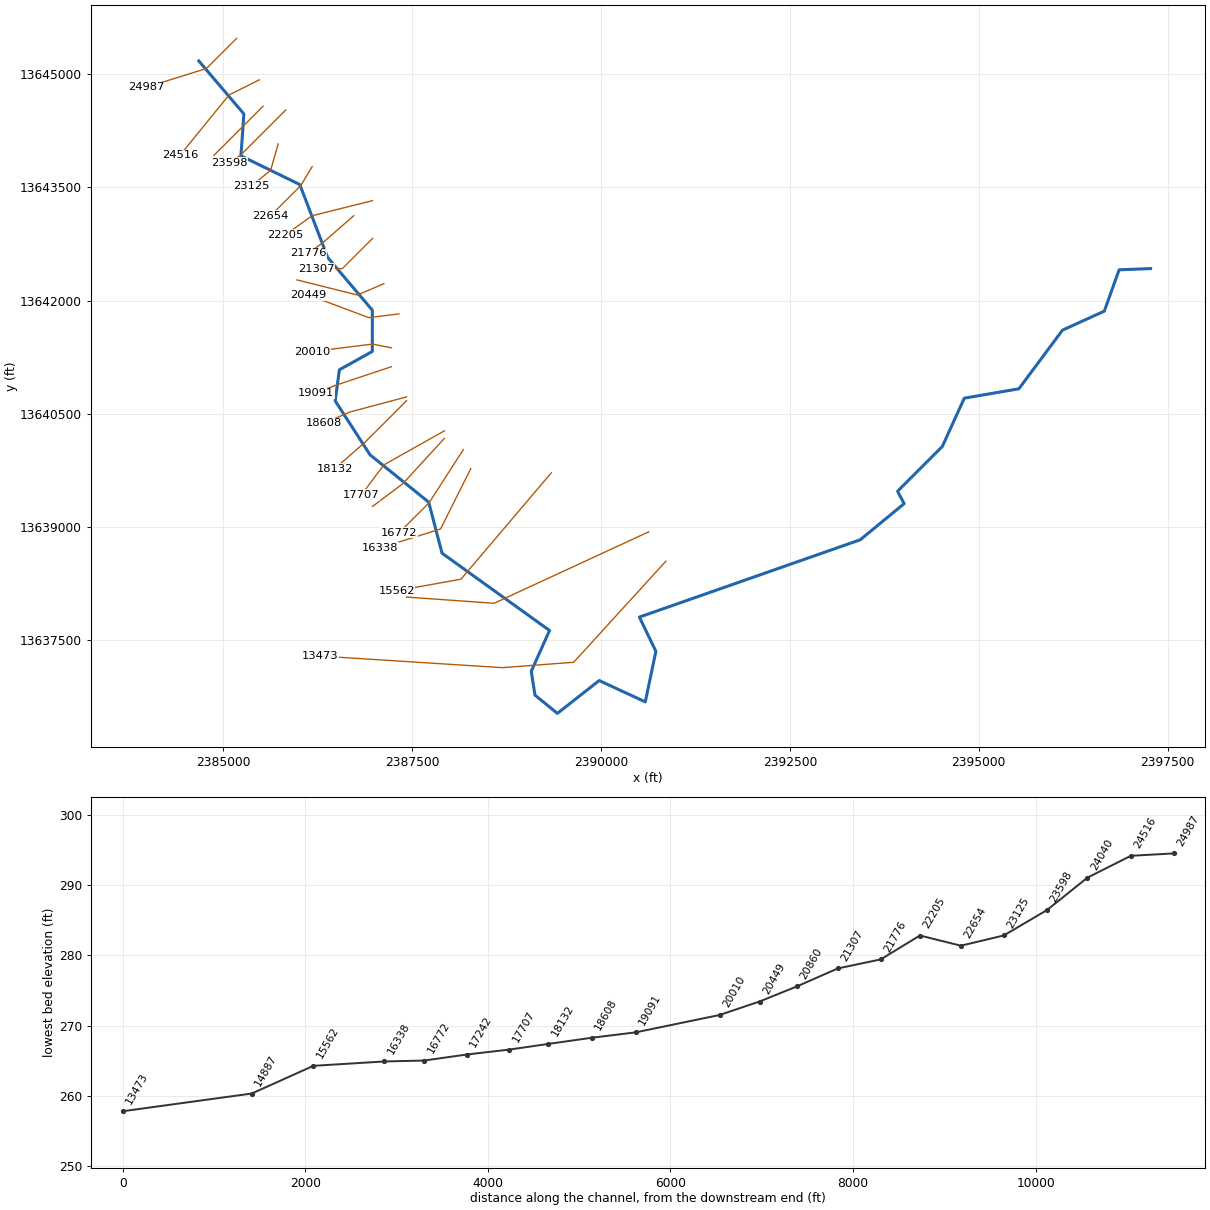
--- WICKEY BRANCH.prj (project) ---

Proj Title=WICKEY BRANCH Base Level Engineering
Current Plan=p01
Default Exp/Contr=0.3,0.1
English Units
Geom File=g01
Flow File=f01
Plan File=p01
BEGIN DESCRIPTION:
WICKEY BRANCH
END DESCRIPTION:

--- WICKEY BRANCH.p01 (plan) ---

Plan Title=Multiple Run
Short Identifier=Multiple
Geom File=g01
Flow File=f01
Subcritical Flow
K Sum by GR= 0
Std Step Tol= 0.01
Critical Tol= 0.01
Num of Std Step Trials= 20
Max Error Tol= 0.3
Flow Tol Ratio= 0.001
Split Flow NTrial= 30
Split Flow Tol= 0.02
Split Flow Ratio= 0.02
Log Output Level= 0
Friction Slope Method= 1
Unsteady Friction Slope Method= 2
Unsteady Bridges Friction Slope Method= 1
Parabolic Critical Depth
Global Vel Dist=  1 , 1 , 1
Global Log Level= 0
CheckData=True
Encroach Param= -1, 0, 0, 0
BEGIN DESCRIPTION:
Multiple Run
END DESCRIPTION:

--- WICKEY BRANCH.f01 (steady flow) ---

Flow Title=Multiple
Number of Profiles=7
Profile Names=10-year,25-year,50-year,1pct_min,100-year,1pct_plu,500-year
River Rch & RM= WICKEY BRANCH,Reach-1,24987
     652    1058    1426     930    1855    3702    3114
River Rch & RM= WICKEY BRANCH,Reach-1,22205
     779    1262    1699    1105    2206    4401    3685
Boundary for River Rch & Prof#=WICKEY BRANCH,Reach-1,1
Up Type=0
Dn Type=3
Dn Slope=0.005
Boundary for River Rch & Prof#=WICKEY BRANCH,Reach-1,2
Up Type=0
Dn Type=3
Dn Slope=0.005
Boundary for River Rch & Prof#=WICKEY BRANCH,Reach-1,3
Up Type=0
Dn Type=3
Dn Slope=0.005
Boundary for River Rch & Prof#=WICKEY BRANCH,Reach-1,4
Up Type=0
Dn Type=3
Dn Slope=0.005
Boundary for River Rch & Prof#=WICKEY BRANCH,Reach-1,5
Up Type=0
Dn Type=3
Dn Slope=0.005
Boundary for River Rch & Prof#=WICKEY BRANCH,Reach-1,6
Up Type=0
Dn Type=3
Dn Slope=0.005
Boundary for River Rch & Prof#=WICKEY BRANCH,Reach-1,7
Up Type=0
Dn Type=3
Dn Slope=0.005

--- WICKEY BRANCH.g01 (geometry) ---

Geom Title=Existing Conditions

River Reach=WICKEY BRANCH,Reach-1
Reach XY= 30
      2384675.00     13645175.00      2385271.46     13644473.54
      2385232.35     13643918.62      2386011.39     13643538.24
      2386380.82     13642572.69      2386971.90     13641873.35
      2386971.24     13641326.56      2386535.51     13641084.81
      2386480.34     13640672.26      2386941.44     13639958.21
      2387717.61     13639331.33      2387894.77     13638654.87
      2389317.53     13637631.07      2389075.49     13637090.22
      2389125.00     13636775.00      2389421.67     13636532.98
      2389975.00     13636967.92      2390585.16     13636685.28
      2390725.45     13637354.97      2390507.43     13637808.37
      2393431.17     13638832.86      2394011.77     13639311.24
      2393925.00     13639475.00      2394517.26     13640068.54
      2394808.32     13640708.36      2395531.17     13640832.86
      2396107.77     13641608.76      2396661.77     13641861.33
      2396857.86     13642408.73      2397275.00     13642425.00

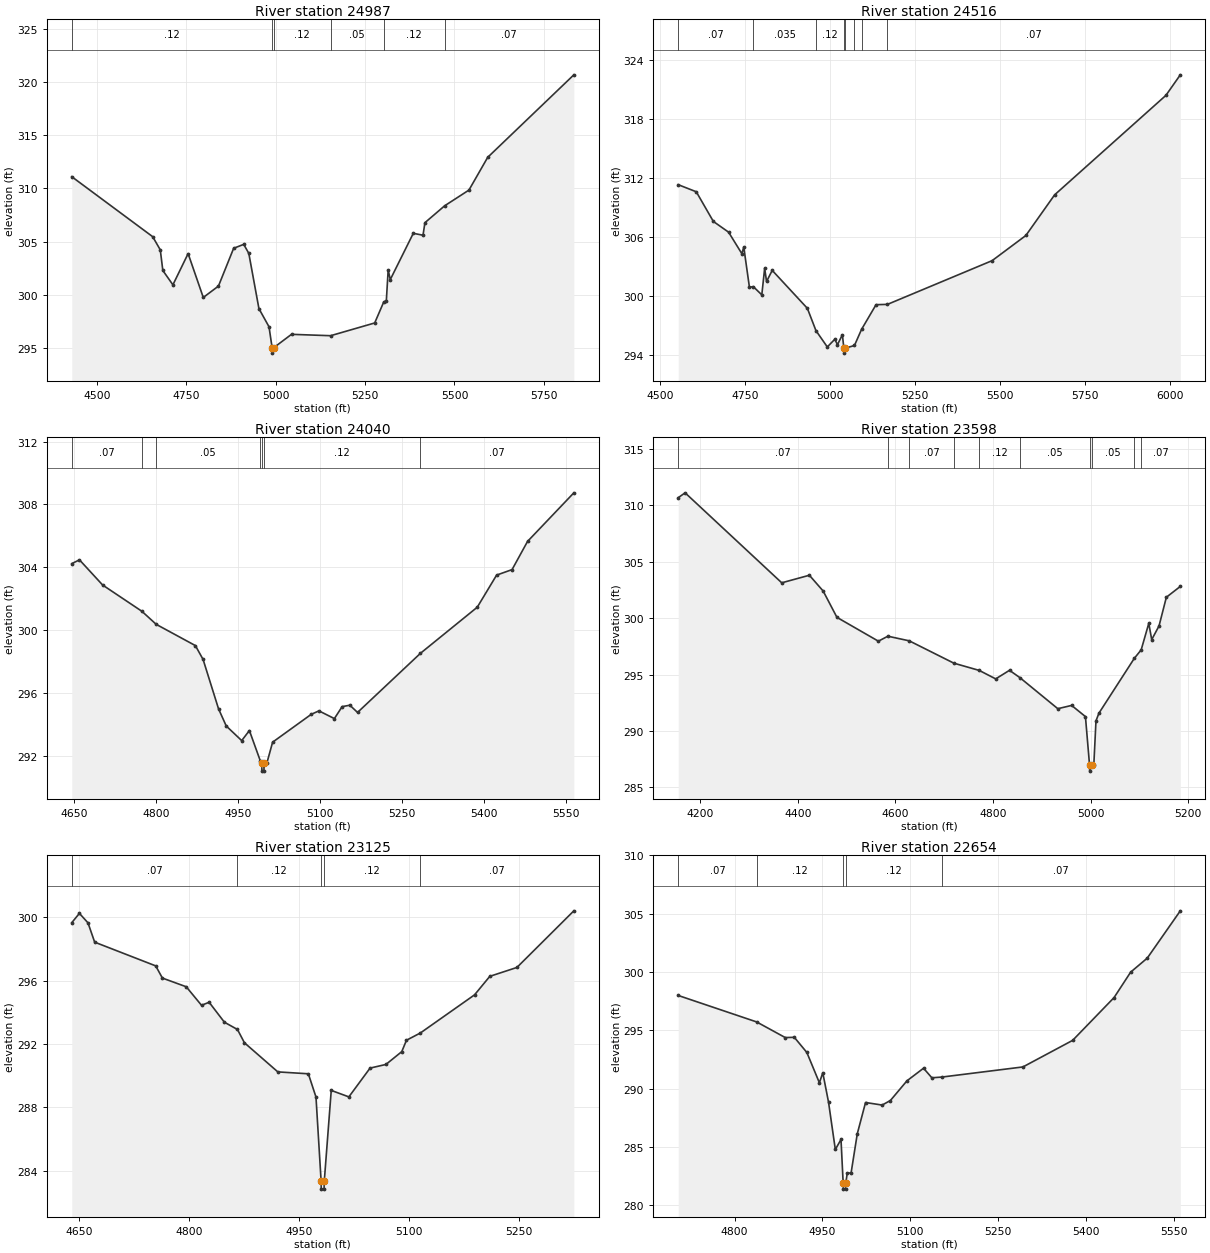
Type RM Length L Ch R = 1,24987,471,471,471
BEGIN DESCRIPTION:
WICKEY BRANCH 32.0
END DESCRIPTION:
XS GIS Cut Line= 3
      2385175.00     13645475.00      2384775.00     13645075.00
      2383975.04     13644825.01
#Sta/Elev= 30
  4430.0  311.11  4656.3  305.46  4677.5  304.22  4684.6  302.28  4712.8  300.93
  4755.3  303.87  4797.7  299.74  4840.1  300.81  4882.6  304.37  4910.8  304.74
  4925.0  303.89  4953.3  298.69  4981.5  296.98  4990.2  295.00  4990.4  294.50
  4994.2  295.00  5044.4  296.27  5153.7  296.14  5277.0  297.34  5302.3  299.32
  5309.5  299.42  5314.7  302.34  5320.5  301.42  5384.9  305.78  5412.1  305.60
  5417.4  306.78  5472.6  308.37  5540.5  309.85  5592.9  312.93  5833.8  320.70
#Mann=6,-1,0
  4430.0    0.12       0  4990.2    0.05       0  4994.2    0.12       0
  5153.7    0.05       0  5302.3    0.12       0  5472.6    0.07       0
Bank Sta=4990.2,4994.2
Exp/Cntr=0.3,0.1

Type RM Length L Ch R = 1,24516,476,476,476
BEGIN DESCRIPTION:
WICKEY BRANCH 31.0
END DESCRIPTION:
XS GIS Cut Line= 3
      2385475.02     13644925.01      2385075.00     13644725.00
      2384425.00     13643925.01
#Sta/Elev= 30
  4553.0  311.30  4606.1  310.58  4656.4  307.56  4701.2  306.47  4740.3  304.28
  4745.9  304.95  4762.6  300.86  4773.9  300.93  4799.0  300.09  4807.4  302.79
  4813.0  301.45  4829.7  302.58  4933.1  298.72  4958.4  296.45  4991.8  294.79
  5013.9  295.57  5021.8  295.02  5036.2  296.03  5040.6  294.66  5040.8  294.16
  5044.7  294.66  5071.8  294.94  5092.7  296.58  5135.3  299.09  5168.9  299.12
  5477.0  303.57  5576.3  306.13  5661.1  310.27  5988.6  320.39  6031.0  322.48
#Mann=8,-1,0
  4553.0    0.07       0  4773.9   0.035       0  4958.4    0.12       0
  5040.6    0.05       0  5044.7    0.12       0  5071.8   0.035       0
  5092.7    0.12       0  5168.9    0.07       0
Bank Sta=5040.6,5044.7
Exp/Cntr=0.3,0.1

Type RM Length L Ch R = 1,24040,442,442,442
BEGIN DESCRIPTION:
WICKEY BRANCH 30.0
END DESCRIPTION:
XS GIS Cut Line= 3
      2385524.98     13644574.98      2385275.00     13644325.00
      2384875.01     13643925.01
#Sta/Elev= 30
  4646.0  304.24  4660.1  304.48  4702.5  302.88  4774.4  301.21  4800.6  300.38
  4872.3  299.03  4886.4  298.15  4914.7  295.01  4928.8  293.92  4957.1  292.99
  4971.2  293.63  4991.1  291.71  4993.9  291.55  4994.1  291.05  4997.8  291.05
  4998.1  291.55  5003.1  291.55  5013.7  292.89  5084.4  294.66  5098.5  294.88
  5126.8  294.39  5141.0  295.15  5155.1  295.24  5169.2  294.78  5284.4  298.54
  5388.4  301.47  5423.8  303.51  5452.1  303.86  5480.4  305.65  5565.2  308.74
#Mann=7,-1,0
  4646.0    0.07       0  4774.4    0.12       0  4800.6    0.05       0
  4991.1    0.12       0  4993.9    0.05       0  4998.1    0.12       0
  5284.4    0.07       0
Bank Sta=4993.9,4998.1
Exp/Cntr=0.3,0.1

Type RM Length L Ch R = 1,23598,473,473,473
BEGIN DESCRIPTION:
WICKEY BRANCH 29.0
END DESCRIPTION:
XS GIS Cut Line= 3
      2385824.98     13644524.98      2385225.00     13643925.00
      2385074.98     13643824.99
#Sta/Elev= 30
  4155.2  310.67  4169.3  311.10  4367.3  303.13  4423.9  303.80  4452.2  302.40
  4480.4  300.07  4565.3  297.96  4584.8  298.40  4628.6  297.99  4720.1  296.01
  4772.0  295.37  4805.7  294.62  4834.0  295.38  4855.3  294.73  4933.0  291.98
  4961.3  292.27  4989.6  291.28  4998.1  286.95  4998.3  286.45  5002.3  286.95
  5006.7  286.95  5011.2  290.90  5017.2  291.58  5089.9  296.45  5103.8  297.19
  5119.4  299.54  5125.4  298.10  5140.4  299.31  5155.4  301.85  5184.0  302.81
#Mann=10,-1,0
  4155.2    0.07       0  4584.8    0.12       0  4628.6    0.07       0
  4720.1    0.05       0  4772.0    0.12       0  4855.3    0.05       0
  4998.1    0.05       0  5002.3    0.05       0  5089.9    0.12       0
  5103.8    0.07       0
Bank Sta=4998.1,5002.3
Exp/Cntr=0.3,0.1

Type RM Length L Ch R = 1,23125,471,471,471
BEGIN DESCRIPTION:
WICKEY BRANCH 28.0
END DESCRIPTION:
XS GIS Cut Line= 3
      2385725.01     13644075.03      2385625.00     13643725.00
      2385375.00     13643525.00
#Sta/Elev= 30
  4640.3  299.67  4650.7  300.26  4662.4  299.66  4671.5  298.44  4754.7  296.94
  4763.8  296.17  4796.3  295.62  4817.1  294.45  4827.5  294.64  4848.3  293.38
  4866.1  292.92  4875.6  292.08  4921.1  290.24  4962.7  290.12  4973.1  288.65
  4980.1  283.33  4980.3  282.83  4984.1  282.83  4984.4  283.33  4993.9  289.07
  5017.9  288.66  5046.8  290.48  5068.4  290.71  5090.0  291.52  5096.4  292.24
  5115.4  292.70  5189.2  295.11  5210.0  296.28  5246.9  296.84  5324.5  300.42
#Mann=5,-1,0
  4640.3    0.07       0  4866.1    0.12       0  4980.1    0.05       0
  4984.4    0.12       0  5115.4    0.07       0
Bank Sta=4980.1,4984.4
Exp/Cntr=0.3,0.1

Type RM Length L Ch R = 1,22654,449,449,449
BEGIN DESCRIPTION:
WICKEY BRANCH 27.0
END DESCRIPTION:
XS GIS Cut Line= 3
      2386174.99     13643774.99      2386025.00     13643525.00
      2385625.02     13643125.02
#Sta/Elev= 30
  4703.7  297.98  4837.6  295.71  4886.4  294.37  4901.9  294.39  4923.3  293.09
  4944.7  290.49  4950.5  291.35  4960.3  288.83  4971.9  284.77  4981.6  285.63
  4985.3  281.87  4985.6  281.37  4989.4  281.37  4989.7  281.87  4992.3  282.75
  4998.8  282.75  5009.4  286.12  5023.5  288.80  5051.8  288.58  5065.9  288.97
  5094.2  290.66  5122.5  291.74  5136.7  290.92  5153.5  290.98  5292.2  291.85
  5377.1  294.13  5447.8  297.80  5476.1  299.98  5504.4  301.18  5560.9  305.24
#Mann=5,-1,0
  4703.7    0.07       0  4837.6    0.12       0  4985.3    0.05       0
  4989.7    0.12       0  5153.5    0.07       0
Bank Sta=4985.3,4989.7
Exp/Cntr=0.3,0.1

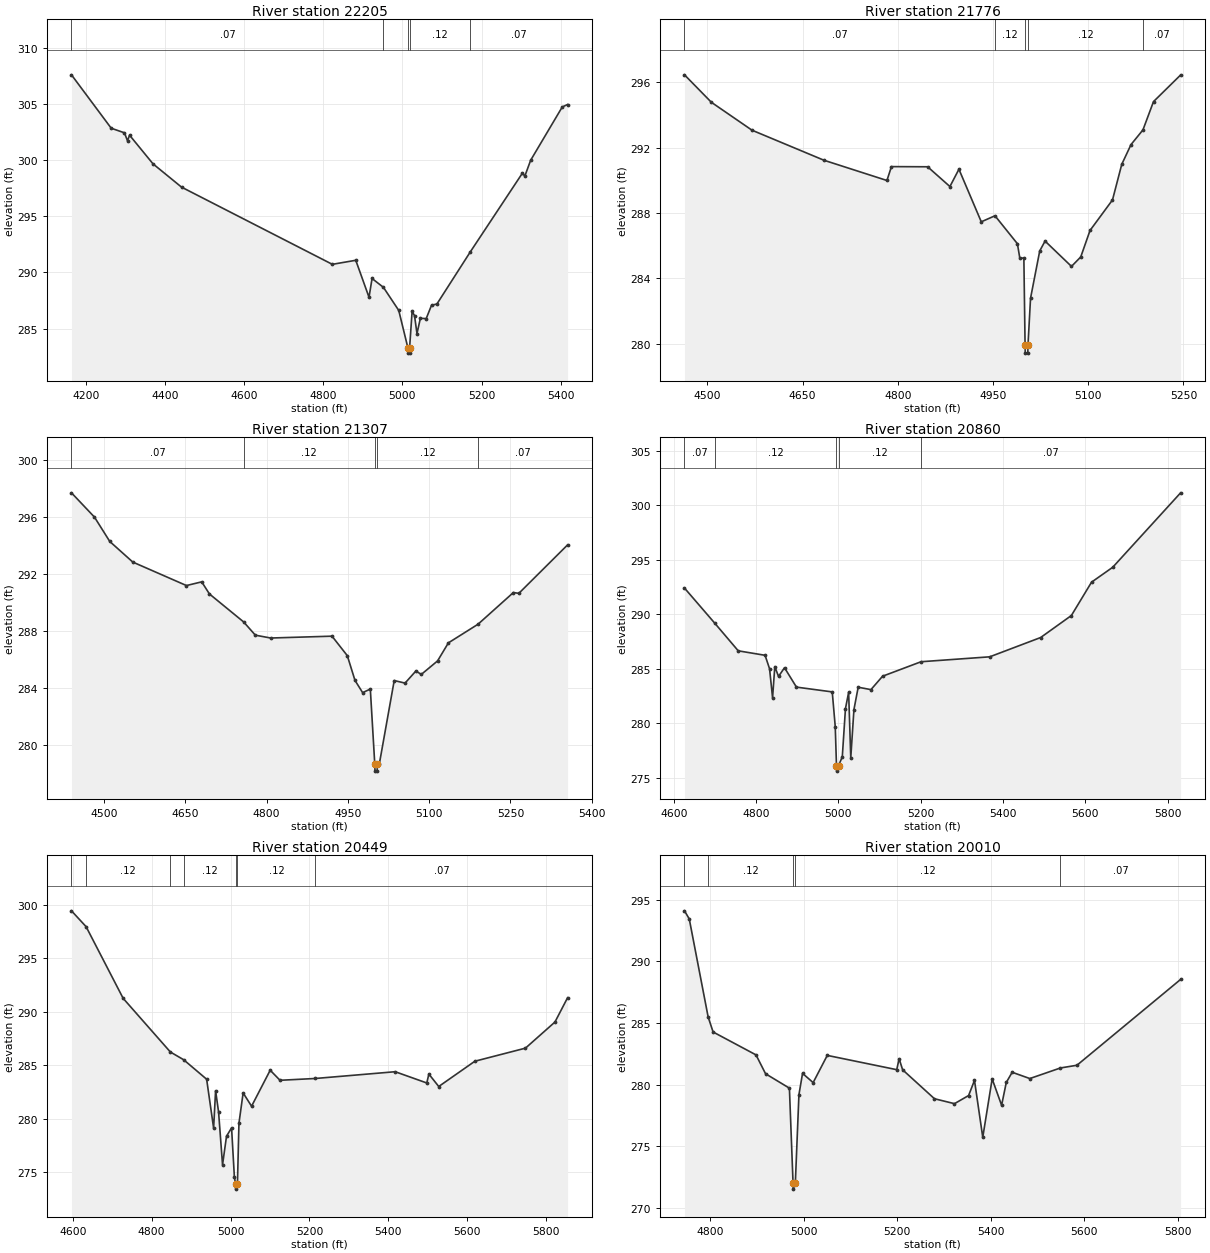
Type RM Length L Ch R = 1,22205,429,429,429
BEGIN DESCRIPTION:
WICKEY BRANCH 26.0
END DESCRIPTION:
XS GIS Cut Line= 3
      2386975.00     13643325.00      2386175.00     13643125.00
      2385825.03     13642875.02
#Sta/Elev= 30
  4163.0  307.58  4263.5  302.83  4297.0  302.42  4304.7  301.71  4309.9  302.21
  4369.2  299.66  4441.3  297.59  4822.7  290.72  4882.0  291.08  4915.5  287.79
  4923.2  289.46  4952.0  288.67  4990.7  286.62  5013.6  283.32  5013.9  282.82
  5017.9  282.82  5018.2  283.32  5024.5  286.54  5030.6  286.15  5036.8  284.56
  5045.4  285.92  5060.1  285.89  5073.6  287.08  5087.2  287.19  5171.7  291.83
  5303.4  298.83  5309.6  298.57  5324.3  299.98  5404.2  304.72  5417.7  304.94
#Mann=5,-1,0
  4163.0    0.07       0  4952.0    0.12       0  5013.6    0.05       0
  5018.2    0.12       0  5171.7    0.07       0
Bank Sta=5013.6,5018.2
Exp/Cntr=0.3,0.1

Type RM Length L Ch R = 1,21776,469,469,469
BEGIN DESCRIPTION:
WICKEY BRANCH 25.0
END DESCRIPTION:
XS GIS Cut Line= 3
      2386725.01     13643125.01      2386325.00     13642775.00
      2386125.02     13642625.01
#Sta/Elev= 30
  4464.1  296.46  4506.4  294.78  4570.4  293.07  4683.8  291.23  4783.0  289.99
  4790.1  290.84  4847.1  290.83  4882.2  289.62  4896.4  290.68  4931.6  287.46
  4953.2  287.83  4988.5  286.12  4992.3  285.24  4998.7  285.24  5000.6  279.92
  5000.9  279.42  5004.9  279.42  5005.2  279.92  5009.2  282.78  5023.7  285.68
  5032.1  286.28  5073.7  284.73  5088.3  285.31  5102.9  286.93  5138.3  288.80
  5152.9  290.98  5167.5  292.19  5186.3  293.09  5202.9  294.82  5245.6  296.45
#Mann=5,-1,0
  4464.1    0.07       0  4953.2    0.12       0  5000.6    0.05       0
  5005.2    0.12       0  5186.3    0.07       0
Bank Sta=5000.6,5005.2
Exp/Cntr=0.3,0.1

Type RM Length L Ch R = 1,21307,447,447,447
BEGIN DESCRIPTION:
WICKEY BRANCH 24.0
END DESCRIPTION:
XS GIS Cut Line= 3
      2386975.02     13642825.02      2386575.00     13642425.00
      2386225.01     13642425.00
#Sta/Elev= 30
  4439.7  297.71  4482.2  296.00  4510.4  294.29  4552.9  292.84  4651.9  291.19
  4680.1  291.45  4694.3  290.60  4757.5  288.63  4779.1  287.70  4807.4  287.50
  4920.6  287.63  4948.8  286.26  4963.0  284.52  4977.1  283.66  4991.3  283.91
  4999.5  278.64  4999.9  278.14  5003.9  278.14  5004.2  278.64  5007.9  278.64
  5035.4  284.51  5055.4  284.33  5075.4  285.18  5085.4  284.94  5115.4  285.89
  5135.4  287.16  5190.1  288.47  5255.4  290.70  5265.4  290.64  5355.4  294.05
#Mann=5,-1,0
  4439.7    0.07       0  4757.5    0.12       0  4999.5    0.05       0
  5004.2    0.12       0  5190.1    0.07       0
Bank Sta=4999.5,5004.2
Exp/Cntr=0.3,0.1

Type RM Length L Ch R = 1,20860,411,411,411
BEGIN DESCRIPTION:
WICKEY BRANCH 23.0
END DESCRIPTION:
XS GIS Cut Line= 3
      2387125.01     13642225.00      2386775.00     13642075.00
      2385975.02     13642275.00
#Sta/Elev= 30
  4626.1  292.39  4699.8  289.16  4756.7  286.63  4821.9  286.22  4832.8  284.98
  4840.1  282.32  4845.5  285.18  4854.6  284.28  4869.1  285.08  4898.1  283.30
  4985.1  282.86  4992.4  279.67  4995.4  276.09  4995.7  275.59  5000.3  276.09
  5009.5  276.90  5017.2  281.33  5024.9  282.82  5030.1  276.81  5037.8  281.24
  5048.1  283.29  5079.1  283.07  5107.4  284.30  5201.0  285.63  5367.7  286.08
  5491.4  287.85  5566.1  289.87  5615.1  292.93  5666.6  294.30  5831.5  301.13
#Mann=5,-1,0
  4626.1    0.07       0  4699.8    0.12       0  4995.4    0.05       0
  5000.3    0.12       0  5201.0    0.07       0
Bank Sta=4995.4,5000.3
Exp/Cntr=0.3,0.1

Type RM Length L Ch R = 1,20449,439,439,439
BEGIN DESCRIPTION:
WICKEY BRANCH 22.0
END DESCRIPTION:
XS GIS Cut Line= 3
      2387324.98     13641825.00      2386925.00     13641775.00
      2386124.99     13642075.00
#Sta/Elev= 30
  4596.9  299.41  4634.0  297.93  4727.9  291.24  4847.6  286.23  4881.2  285.51
  4939.5  283.69  4957.2  279.13  4962.2  282.62  4969.8  280.62  4979.8  275.70
  4989.9  278.37  5002.7  279.15  5009.8  274.57  5012.7  273.93  5013.0  273.43
  5017.6  273.93  5021.4  279.58  5032.0  282.41  5053.4  281.17  5100.6  284.53
  5125.5  283.59  5215.4  283.76  5417.4  284.39  5497.5  283.34  5502.8  284.17
  5527.8  283.01  5619.4  285.37  5747.6  286.59  5822.4  289.03  5854.4  291.30
#Mann=7,-1,0
  4596.9    0.07       0  4634.0    0.12       0  4847.6    0.07       0
  4881.2    0.12       0  5012.7    0.05       0  5017.6    0.12       0
  5215.4    0.07       0
Bank Sta=5012.7,5017.6
Exp/Cntr=0.3,0.1

Type RM Length L Ch R = 1,20010,919,919,919
BEGIN DESCRIPTION:
WICKEY BRANCH 21.0
END DESCRIPTION:
XS GIS Cut Line= 3
      2387225.05     13641374.99      2386975.00     13641425.00
      2386175.03     13641325.00
#Sta/Elev= 30
  4744.7  294.11  4754.9  293.45  4795.3  285.49  4805.9  284.27  4897.7  282.41
  4918.1  280.88  4969.1  279.71  4976.9  272.01  4977.2  271.51  4981.8  272.01
  4989.5  279.18  4997.2  280.91  5019.9  280.16  5050.1  282.37  5198.7  281.21
  5203.8  282.10  5211.3  281.20  5279.4  278.85  5322.2  278.45  5352.4  279.11
  5365.0  280.34  5382.7  275.72  5402.8  280.46  5423.0  278.32  5433.0  280.17
  5445.6  281.00  5483.4  280.49  5548.9  281.35  5584.2  281.57  5805.9  288.54
#Mann=5,-1,0
  4744.7    0.07       0  4795.3    0.12       0  4976.9    0.05       0
  4981.8    0.12       0  5548.9    0.07       0
Bank Sta=4976.9,4981.8
Exp/Cntr=0.3,0.1

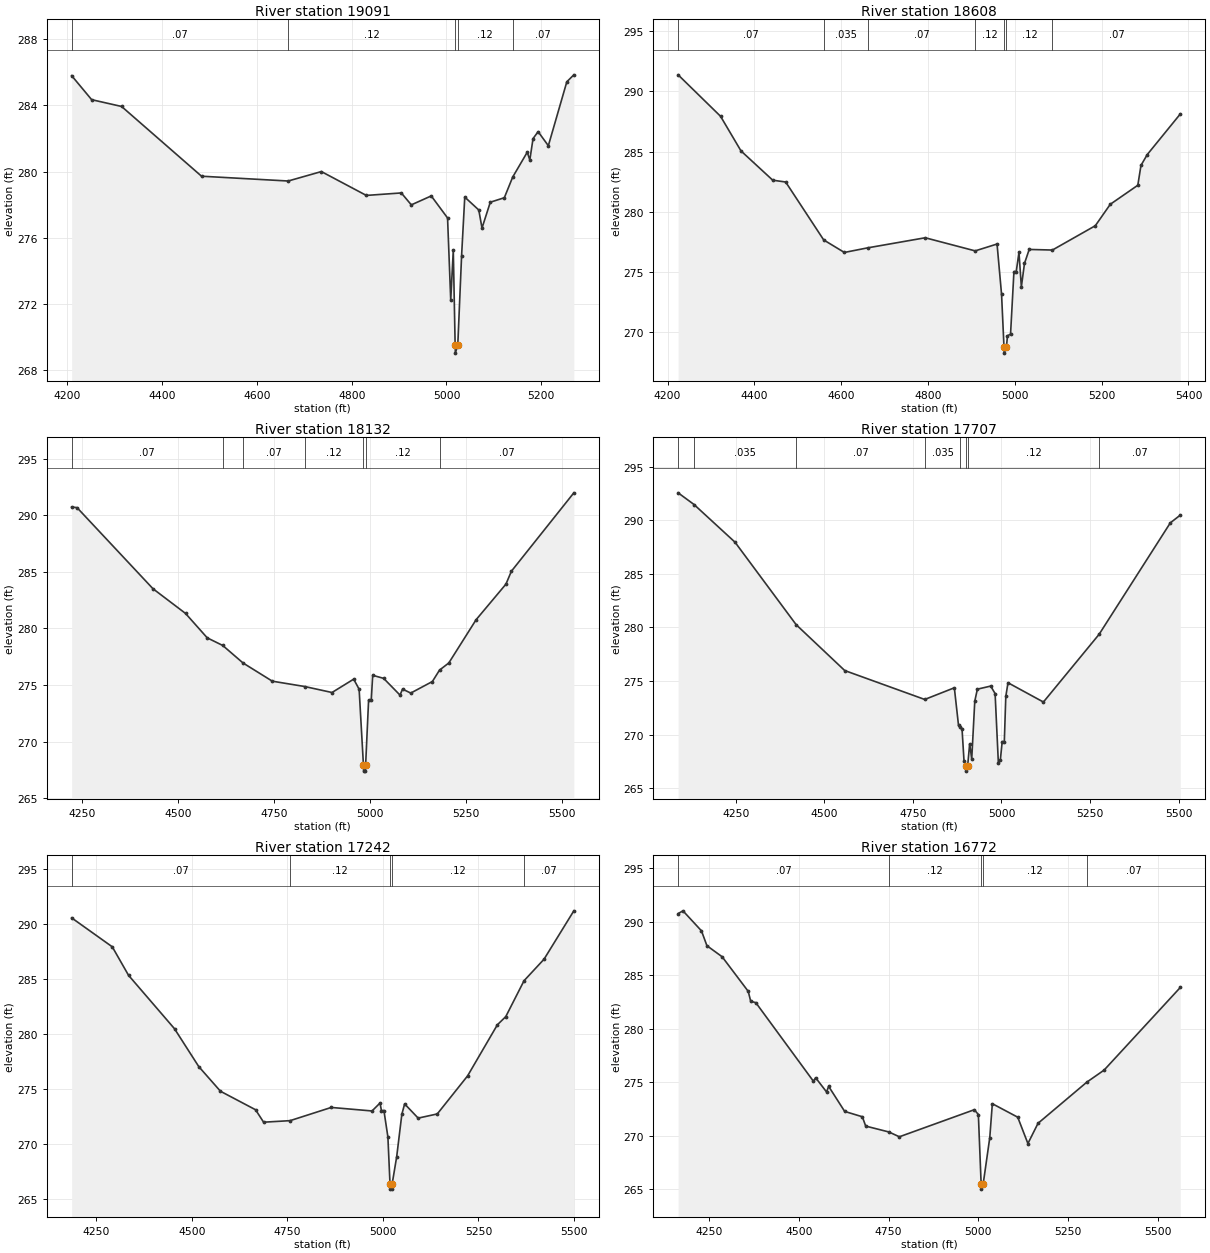
Type RM Length L Ch R = 1,19091,483,483,483
BEGIN DESCRIPTION:
WICKEY BRANCH 20.0
END DESCRIPTION:
XS GIS Cut Line= 3
      2387225.00     13641125.00      2386475.00     13640875.00
      2386225.02     13640775.01
#Sta/Elev= 30
  4209.0  285.79  4251.2  284.34  4314.4  283.93  4483.1  279.72  4665.9  279.43
  4736.0  280.00  4830.9  278.56  4904.7  278.71  4925.8  277.99  4967.9  278.53
  5002.3  277.20  5009.0  272.25  5014.4  275.25  5018.3  269.54  5018.8  269.04
  5023.9  269.54  5031.9  274.91  5038.6  278.46  5068.2  277.68  5075.0  276.59
  5092.5  278.15  5122.1  278.42  5139.8  279.67  5170.5  281.17  5175.9  280.70
  5182.7  281.99  5193.4  282.41  5215.0  281.56  5254.0  285.42  5268.8  285.84
#Mann=5,-1,0
  4209.0    0.07       0  4665.9    0.12       0  5018.3    0.05       0
  5023.9    0.12       0  5139.8    0.07       0
Bank Sta=5018.3,5023.9
Exp/Cntr=0.3,0.1

Type RM Length L Ch R = 1,18608,476,476,476
BEGIN DESCRIPTION:
WICKEY BRANCH 19.0
END DESCRIPTION:
XS GIS Cut Line= 3
      2387425.04     13640725.01      2386675.00     13640525.00
      2386325.03     13640375.01
#Sta/Elev= 30
  4224.2  291.38  4321.9  287.94  4369.1  285.06  4442.2  282.63  4472.0  282.48
  4559.6  277.67  4607.2  276.63  4660.6  277.01  4793.5  277.85  4908.6  276.76
  4959.0  277.33  4969.4  273.14  4975.0  268.77  4975.5  268.27  4980.6  268.77
  4983.0  269.71  4990.1  269.85  4997.9  275.04  5003.2  275.04  5009.5  276.64
  5015.0  273.77  5022.2  275.72  5033.1  276.88  5086.5  276.83  5185.4  278.85
  5219.9  280.63  5283.3  282.21  5290.6  283.86  5305.1  284.76  5381.2  288.13
#Mann=7,-1,0
  4224.2    0.07       0  4559.6   0.035       0  4660.6    0.07       0
  4908.6    0.12       0  4975.0    0.05       0  4980.6    0.12       0
  5086.5    0.07       0
Bank Sta=4975,4980.6
Exp/Cntr=0.3,0.1

Type RM Length L Ch R = 1,18132,425,425,425
BEGIN DESCRIPTION:
WICKEY BRANCH 18.0
END DESCRIPTION:
XS GIS Cut Line= 3
      2387424.97     13640674.97      2386875.00     13640125.00
      2386474.99     13639774.99
#Sta/Elev= 30
  4222.5  290.74  4236.6  290.68  4434.6  283.51  4519.4  281.33  4576.0  279.17
  4616.3  278.50  4669.3  276.95  4745.7  275.34  4829.9  274.87  4901.3  274.34
  4957.8  275.52  4972.0  274.63  4983.3  267.89  4983.8  267.39  4988.5  267.39
  4988.9  267.89  4996.7  273.67  5003.6  273.67  5007.4  275.86  5035.9  275.59
  5078.6  274.11  5085.2  274.64  5106.6  274.29  5163.0  275.31  5181.6  276.32
  5205.8  276.95  5276.9  280.77  5354.8  283.92  5369.0  285.06  5531.8  291.99
#Mann=7,-1,0
  4222.5    0.07       0  4616.3   0.035       0  4669.3    0.07       0
  4829.9    0.12       0  4983.3    0.05       0  4988.9    0.12       0
  5181.6    0.07       0
Bank Sta=4983.3,4988.9
Exp/Cntr=0.3,0.1

Type RM Length L Ch R = 1,17707,465,465,465
BEGIN DESCRIPTION:
WICKEY BRANCH 17.0
END DESCRIPTION:
XS GIS Cut Line= 3
      2387925.02     13640275.01      2387125.00     13639825.00
      2386825.00     13639425.00
#Sta/Elev= 30
  4087.1  292.57  4132.0  291.48  4247.8  287.96  4420.4  280.26  4557.5  275.98
  4783.4  273.28  4867.0  274.37  4878.8  270.86  4884.2  270.69  4888.7  270.55
  4894.4  267.50  4898.9  267.09  4899.3  266.59  4904.6  267.09  4910.3  269.15
  4916.1  267.72  4924.7  273.12  4932.0  274.24  4969.6  274.53  4982.1  273.83
  4991.3  267.36  4997.0  267.67  5002.1  269.34  5008.1  269.34  5012.3  273.56
  5018.5  274.84  5118.5  273.04  5275.7  279.36  5476.9  289.77  5505.0  290.49
#Mann=8,-1,0
  4087.1    0.07       0  4132.0   0.035       0  4420.4    0.07       0
  4783.4   0.035       0  4884.2    0.12       0  4898.9    0.05       0
  4904.6    0.12       0  5275.7    0.07       0
Bank Sta=4898.9,4904.6
Exp/Cntr=0.3,0.1

Type RM Length L Ch R = 1,17242,470,470,470
BEGIN DESCRIPTION:
WICKEY BRANCH 16.0
END DESCRIPTION:
XS GIS Cut Line= 3
      2387924.98     13640174.98      2387375.00     13639575.00
      2386975.01     13639275.00
#Sta/Elev= 30
  4185.6  290.53  4291.9  287.90  4334.5  285.31  4454.7  280.46  4518.2  277.02
  4575.0  274.78  4666.8  273.10  4687.8  271.97  4757.1  272.11  4864.8  273.31
  4971.5  272.99  4992.4  273.71  4996.1  273.03  5002.6  273.03  5013.0  270.63
  5018.5  266.39  5019.0  265.89  5023.8  265.89  5024.3  266.39  5036.0  268.83
  5049.5  272.69  5056.8  273.63  5092.2  272.34  5142.2  272.72  5221.4  276.17
  5299.5  280.82  5321.4  281.56  5369.2  284.82  5421.4  286.77  5499.5  291.17
#Mann=5,-1,0
  4185.6    0.07       0  4757.1    0.12       0  5018.5    0.05       0
  5024.3    0.12       0  5369.2    0.07       0
Bank Sta=5018.5,5024.3
Exp/Cntr=0.3,0.1

Type RM Length L Ch R = 1,16772,434,434,434
BEGIN DESCRIPTION:
WICKEY BRANCH 15.0
END DESCRIPTION:
XS GIS Cut Line= 3
      2388174.99     13640024.98      2387725.00     13639325.00
      2387325.02     13638925.02
#Sta/Elev= 30
  4164.1  290.77  4177.6  291.03  4229.1  289.16  4244.3  287.77  4286.6  286.74
  4359.2  283.51  4366.2  282.58  4380.4  282.45  4540.9  275.10  4546.8  275.44
  4577.2  274.11  4583.1  274.63  4627.7  272.29  4676.9  271.79  4686.2  270.92
  4750.8  270.37  4779.9  269.92  4988.6  272.45  4999.8  272.00  5007.5  265.53
  5007.9  265.03  5013.3  265.53  5031.6  269.85  5038.7  273.01  5109.4  271.75
  5137.7  269.29  5165.9  271.18  5301.9  275.03  5349.8  276.15  5561.9  283.87
#Mann=5,-1,0
  4164.1    0.07       0  4750.8    0.12       0  5007.5    0.05       0
  5013.3    0.12       0  5301.9    0.07       0
Bank Sta=5007.5,5013.3
Exp/Cntr=0.3,0.1

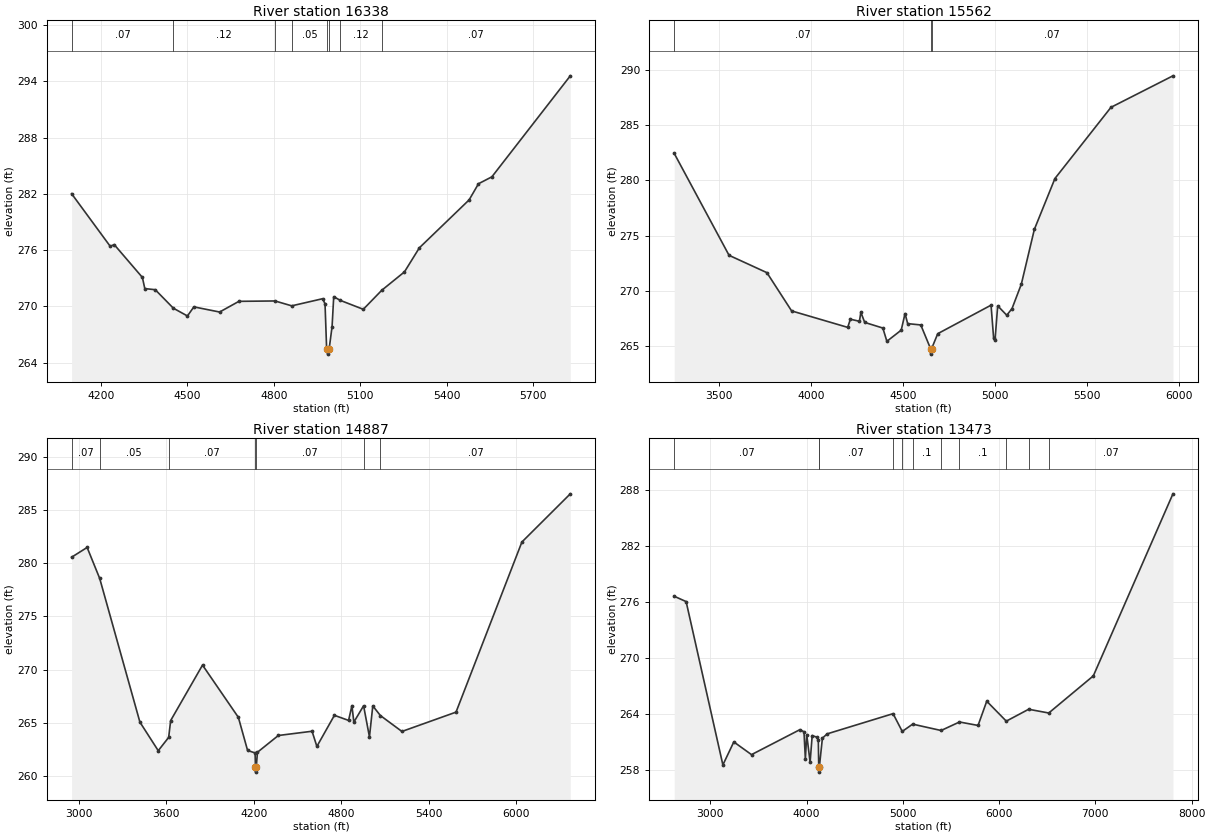
Type RM Length L Ch R = 1,16338,776,776,776
BEGIN DESCRIPTION:
WICKEY BRANCH 14.0
END DESCRIPTION:
XS GIS Cut Line= 3
      2388274.98     13639774.96      2387875.00     13638975.00
      2387075.03     13638725.01
#Sta/Elev= 30
  4097.5  282.01  4231.6  276.40  4245.6  276.58  4343.4  273.08  4351.8  271.89
  4388.1  271.77  4450.9  269.80  4499.9  268.97  4522.3  269.94  4611.7  269.39
  4678.8  270.53  4804.1  270.57  4862.2  270.05  4969.5  270.81  4977.9  270.27
  4983.5  265.45  4986.2  265.40  4986.6  264.90  4992.0  265.40  5002.4  267.84
  5008.1  271.03  5030.4  270.64  5110.8  269.68  5175.0  271.71  5253.8  273.67
  5305.7  276.24  5478.5  281.35  5511.0  283.07  5557.6  283.81  5830.0  294.58
#Mann=8,-1,0
  4097.5    0.07       0  4450.9    0.12       0  4804.1    0.07       0
  4862.2    0.05       0  4986.2    0.05       0  4992.0    0.05       0
  5030.4    0.12       0  5175.0    0.07       0
Bank Sta=4986.2,4992
Exp/Cntr=0.3,0.1

Type RM Length L Ch R = 1,15562,675,675,675
BEGIN DESCRIPTION:
H21785
END DESCRIPTION:
XS GIS Cut Line= 3
      2389341.22     13639719.59      2388145.48     13638310.75
      2387293.03     13638156.84
#Sta/Elev= 30
  3254.1  282.44  3552.4  273.22  3758.5  271.65  3892.9  268.19  4198.3  266.70
  4212.6  267.44  4262.0  267.25  4269.7  268.07  4290.6  267.15  4389.4  266.64
  4411.4  265.44  4489.4  266.45  4510.2  267.95  4524.5  267.04  4595.9  266.92
  4649.0  264.78  4649.5  264.28  4654.9  264.78  4688.2  266.13  4978.3  268.71
  4992.4  265.71  5000.1  265.58  5014.4  268.65  5063.8  267.80  5092.4  268.40
  5143.1  270.61  5214.0  275.57  5326.0  280.17  5630.9  286.61  5968.2  289.46
#Mann=3,-1,0
  3254.1    0.07       0  4649.0    0.05       0  4654.9    0.07       0
Bank Sta=4649,4654.9
Exp/Cntr=0.3,0.1

Type RM Length L Ch R = 1,14887,1414,1414,1414
BEGIN DESCRIPTION:
H21784
END DESCRIPTION:
XS GIS Cut Line= 3
      2390631.65     13638938.21      2388583.52     13637991.10
      2387423.29     13638073.97
#Sta/Elev= 30
  2951.2  280.58  3057.7  281.50  3143.9  278.58  3419.6  265.05  3545.3  262.36
  3616.7  263.61  3630.6  265.20  3848.9  270.42  4094.7  265.50  4158.0  262.38
  4209.3  262.15  4211.9  260.84  4212.4  260.34  4217.8  260.84  4225.5  262.21
  4368.8  263.79  4600.1  264.19  4633.1  262.76  4753.3  265.69  4850.5  265.21
  4873.4  266.60  4886.6  265.05  4953.4  266.59  4993.6  263.66  5016.5  266.58
  5068.5  265.67  5216.3  264.17  5587.2  265.99  6038.9  282.01  6370.9  286.55
#Mann=7,-1,0
  2951.2    0.07       0  3143.9    0.05       0  3616.7    0.07       0
  4211.9    0.05       0  4217.8    0.07       0  4953.4    0.12       0
  5068.5    0.07       0
Bank Sta=4211.9,4217.8
Exp/Cntr=0.3,0.1

Type RM Length L Ch R = 1,13473,0,0,0
BEGIN DESCRIPTION:
H21783
END DESCRIPTION:
XS GIS Cut Line= 4
      2390856.63     13638547.55      2389637.19     13637209.73
      2388690.07     13637138.69      2386274.95     13637292.60
#Sta/Elev= 30
  2625.6  276.62  2749.1  276.05  3130.9  258.59  3244.4  261.05  3428.2  259.69
  3930.8  262.36  3973.4  262.13  3987.6  259.23  4001.8  261.83  4036.9  258.88
  4058.5  261.73  4107.9  261.55  4122.1  261.21  4126.5  258.32  4127.0  257.82
  4132.4  258.32  4164.6  261.45  4213.9  261.91  4898.6  264.07  4994.0  262.17
  5102.0  262.95  5397.4  262.27  5588.5  263.18  5781.4  262.81  5871.6  265.40
  6074.6  263.27  6306.9  264.54  6515.6  264.14  6978.7  268.11  7805.6  287.57
#Mann=11,-1,0
  2625.6    0.07       0  4126.5    0.05       0  4132.4    0.07       0
  4898.6     0.1       0  4994.0    0.07       0  5102.0     0.1       0
  5397.4    0.07       0  5588.5     0.1       0  6074.6    0.12       0
  6306.9     0.1       0  6515.6    0.07       0
Bank Sta=4126.5,4132.4
Exp/Cntr=0.3,0.1

Chan Stop Cuts=-1