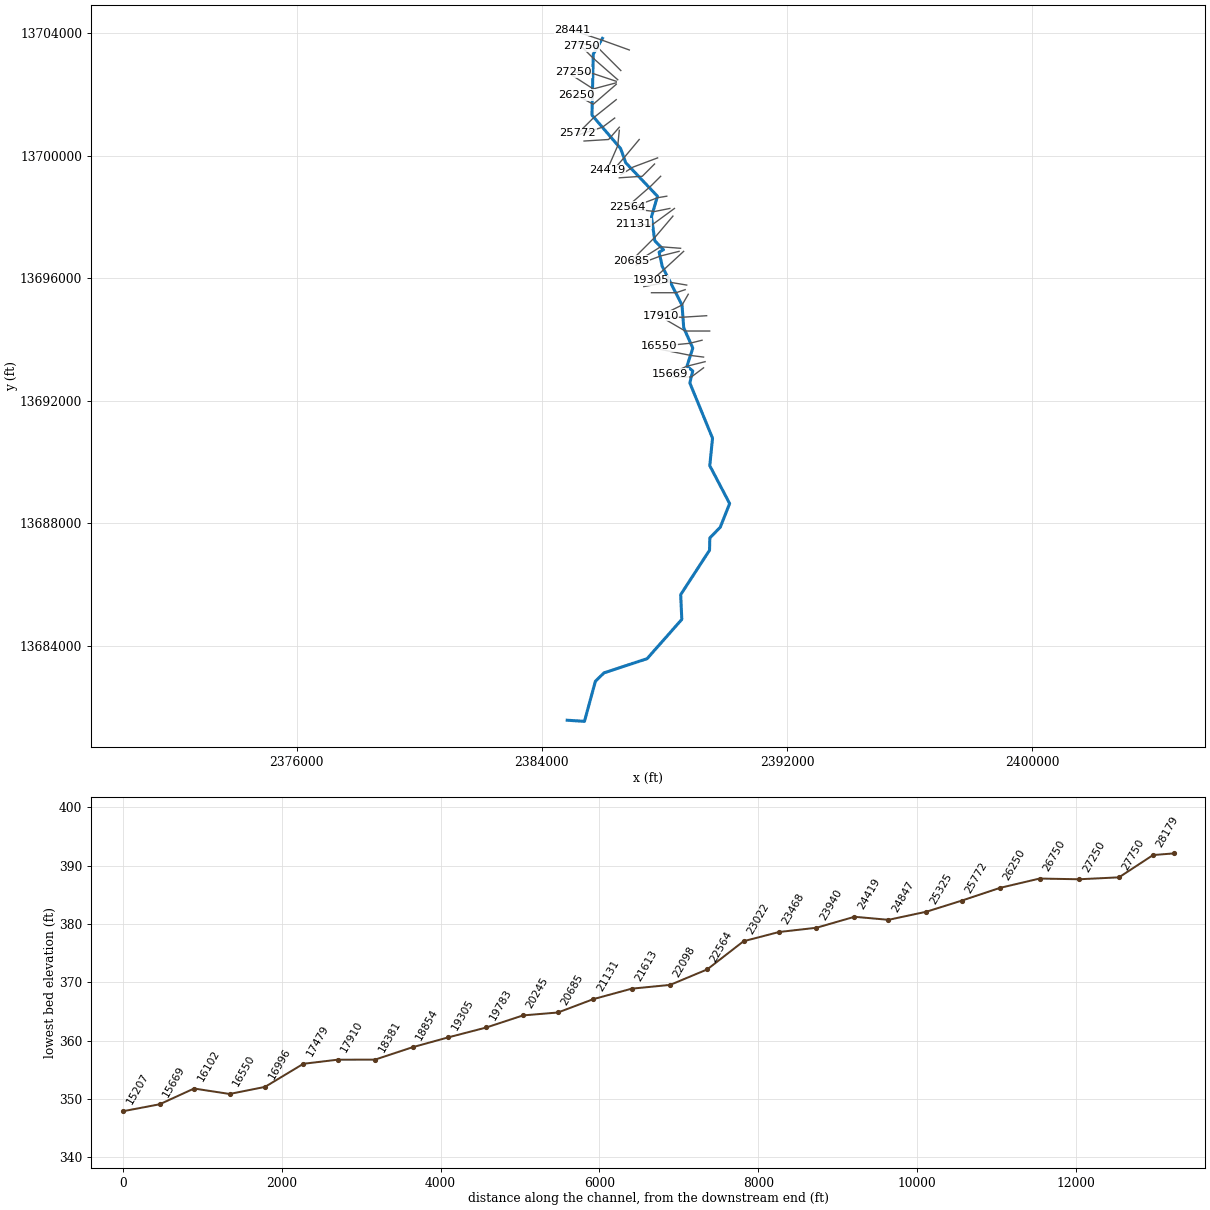
--- YOW BRANCH.prj (project) ---

Proj Title=YOW BRANCH Base Level Engineering
Current Plan=p01
Default Exp/Contr=0.3,0.1
English Units
Geom File=g01
Flow File=f01
Plan File=p01
Y Axis Title=Elevation
X Axis Title(PF)=Main Channel Distance
X Axis Title(XS)=Station
BEGIN DESCRIPTION:
YOW BRANCH
END DESCRIPTION:
DSS Export Rating Curves= 0
DSS Export Rating Curve Sorted= 0
DSS Export Volume Flow Curves= 0
DXF OffsetX= 0
DXF OffsetY= 0
DXF ScaleX= 1
DXF ScaleY= 10

--- YOW BRANCH.p01 (plan) ---

Plan Title=Multiple Run
Short Identifier=Multiple
Geom File=g01
Flow File=f01
Subcritical Flow
K Sum by GR= 0
Std Step Tol= 0.01
Critical Tol= 0.01
Num of Std Step Trials= 20
Max Error Tol= 0.3
Flow Tol Ratio= 0.001
Split Flow NTrial= 30
Split Flow Tol= 0.02
Split Flow Ratio= 0.02
Log Output Level= 0
Friction Slope Method= 1
Unsteady Friction Slope Method= 2
Unsteady Bridges Friction Slope Method= 1
Parabolic Critical Depth
Global Vel Dist=  1 , 1 , 1
Global Log Level= 0
CheckData=True
Encroach Param= -1, 0, 0, 0
BEGIN DESCRIPTION:
Multiple Run
END DESCRIPTION:

--- YOW BRANCH.f01 (steady flow) ---

Flow Title=Multiple
Number of Profiles=7
Profile Names=10-year,25-year,50-year,1pct_min,100-year,1pct_plu,500-year
River Rch & RM= YOW BRANCH,Reach-1,28441
     655    1060    1426     929    1853    3697    3101
River Rch & RM= YOW BRANCH,Reach-1,27250
     944    1553    2111    1387    2768    5524    4720
River Rch & RM= YOW BRANCH,Reach-1,23940
    1206    2001    2737    1808    3607    7197    6214
River Rch & RM= YOW BRANCH,Reach-1,18381
    1454    2432    3343    2218    4425    8829    7691
River Rch & RM= YOW BRANCH,Reach-1,14279
    1674    2816    3886    2587    5162   10299    9033
River Rch & RM= YOW BRANCH,Reach-1,10633
    1831    3084    4261    2837    5661   11295    9917
River Rch & RM= YOW BRANCH,Reach-1,5576
    1900    3205    4432    2954    5894   11760   10342
River Rch & RM= YOW BRANCH,Reach-1,2411
    2148    3640    5050    3376    6736   13439   11887
Boundary for River Rch & Prof#=YOW BRANCH,Reach-1,1
Up Type=0
Dn Type=3
Dn Slope=0.005
Boundary for River Rch & Prof#=YOW BRANCH,Reach-1,2
Up Type=0
Dn Type=3
Dn Slope=0.005
Boundary for River Rch & Prof#=YOW BRANCH,Reach-1,3
Up Type=0
Dn Type=3
Dn Slope=0.005
Boundary for River Rch & Prof#=YOW BRANCH,Reach-1,4
Up Type=0
Dn Type=3
Dn Slope=0.005
Boundary for River Rch & Prof#=YOW BRANCH,Reach-1,5
Up Type=0
Dn Type=3
Dn Slope=0.005
Boundary for River Rch & Prof#=YOW BRANCH,Reach-1,6
Up Type=0
Dn Type=3
Dn Slope=0.005
Boundary for River Rch & Prof#=YOW BRANCH,Reach-1,7
Up Type=0
Dn Type=3
Dn Slope=0.005

--- YOW BRANCH.g01 (geometry) ---

Geom Title=Existing Conditions
Program Version=4.10

River Reach=YOW BRANCH      ,Reach-1
Reach XY= 30
        2385975.       13703825.      2385675.52     13703309.78
      2385633.08      13701321.7      2386567.19     13700231.19
      2386735.52     13699765.21      2387771.25     13698673.45
      2387575.06     13698004.97       2387682.8     13697221.58
       2387967.5     13696928.13      2387824.39     13696850.31
      2387927.24     13696380.93      2388571.45     13695123.53
      2388627.24     13694380.93       2388923.2     13693718.89
      2388732.31     13693124.89      2388921.56     13692973.75
      2388826.54     13692580.85      2389567.21     13690778.42
      2389477.25     13689880.94      2390125.36     13688645.21
      2389819.54     13687872.55      2389478.61      13687523.5
       2389469.6     13687122.57      2388528.17     13685673.35
      2388564.57     13684865.21      2387431.47      13683582.7
       2386026.5     13683121.39      2385744.63     13682845.16
      2385388.32     13681538.37        2384825.       13681575.

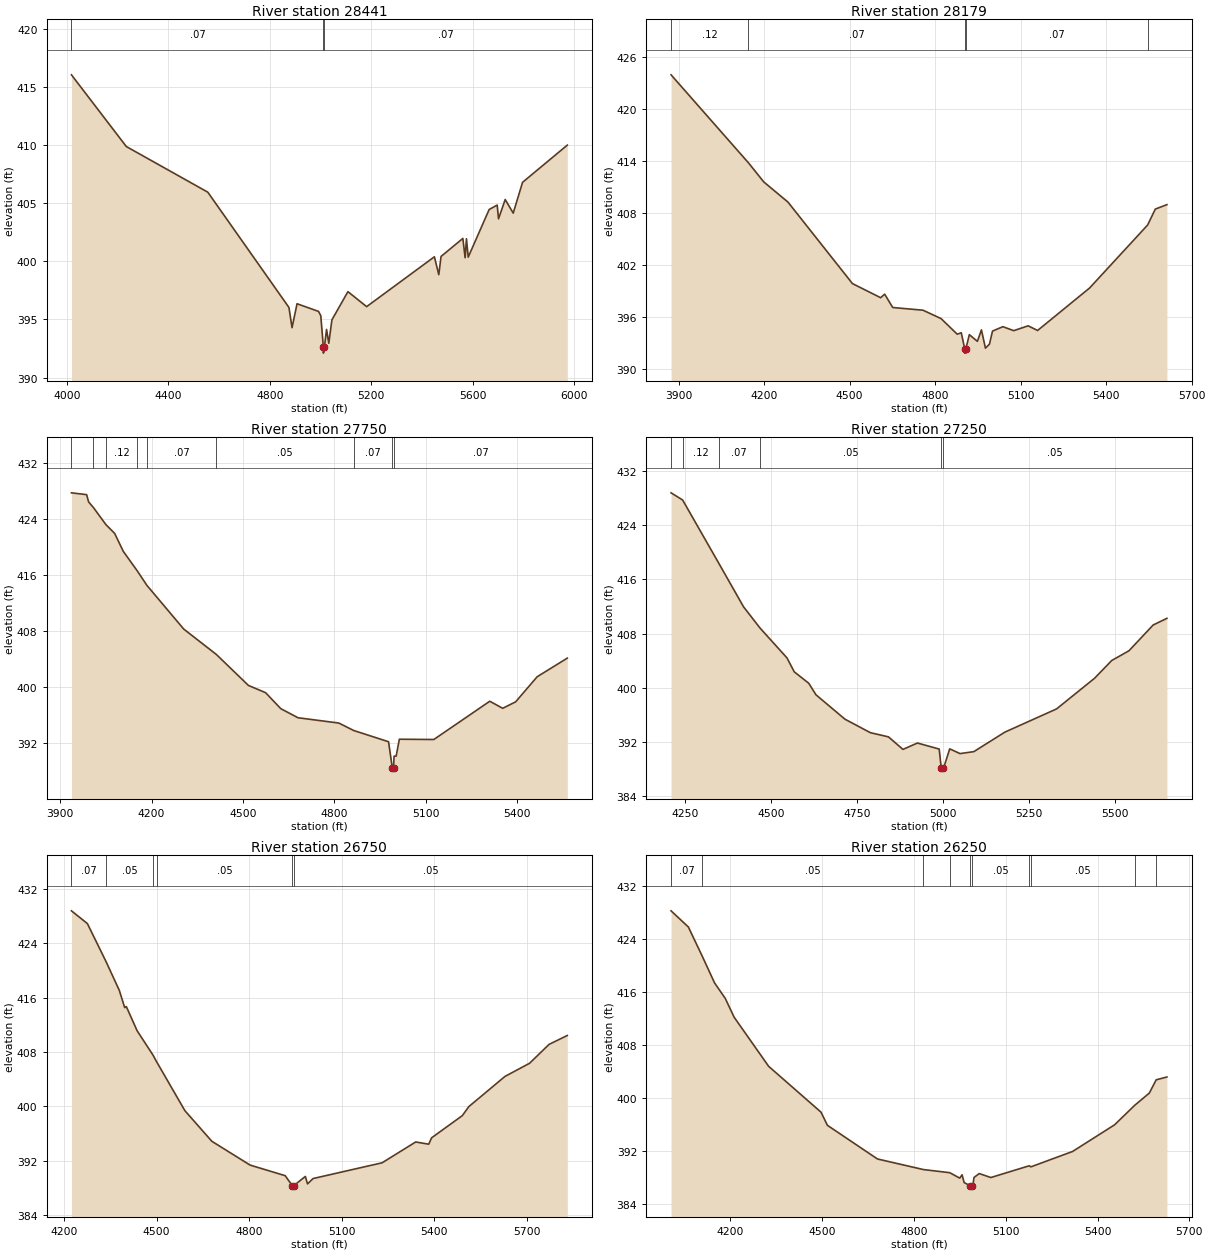
Type RM Length L Ch R = 1 ,28441   ,262,262,262
BEGIN DESCRIPTION:
J21884
END DESCRIPTION:
XS GIS Cut Line= 3
      2386851.92     13703446.06      2385964.59     13703766.17
      2385004.25     13704086.29
#Sta/Elev= 30
  4018.1  416.05  4234.4  409.88  4555.9  405.95  4875.9  396.03  4888.1  394.29
  4907.8  396.35  4992.6  395.69  5001.5  395.32  5011.7   392.6  5011.9   392.1
  5015.7   392.6  5024.2  394.14  5033.1  392.95  5045.3  394.96  5108.5  397.39
  5182.3   396.1  5449.5  400.39  5466.9  398.85  5475.8  400.42  5561.8  401.97
  5570.7  400.31    5576  401.94  5582.9  400.36  5665.6  404.46  5697.2  404.84
  5702.5  403.66  5728.8  405.32  5760.4  404.15  5797.3   406.8  5973.7     410
#Mann= 3 ,-1 , 0
  4018.1     .07       0  5011.7     .05       0  5015.7     .07       0
Bank Sta=5011.7,5015.7
XS Rating Curve= 0 ,0
Exp/Cntr=0.3,0.1

Type RM Length L Ch R = 1 ,28179   ,429,429,429
BEGIN DESCRIPTION:
YOW BRANCH 61.0
END DESCRIPTION:
XS GIS Cut Line= 3
      2386575.01     13702774.99        2385775.       13703575.
      2385174.96     13703675.01
#Sta/Elev= 30
  3873.4  423.91  4144.8  413.77  4198.7  411.56  4283.5  409.24  4509.8  399.84
  4608.8  398.21  4622.9  398.62  4651.2  397.08  4757.3  396.77  4820.9   395.8
  4877.5     394  4891.6  394.17  4903.8  392.32    4904  391.82  4907.5  391.82
  4907.8  392.32  4919.9  393.95  4948.2  393.18  4962.4   394.5  4976.5  392.39
  4990.6  392.86  5001.2  394.36  5037.7  394.87  5075.7  394.41  5126.4  394.97
  5159.4  394.43  5341.9  399.33  5545.4  406.59  5572.5  408.43  5613.1  408.94
#Mann= 5 ,-1 , 0
  3873.4     .12       0  4144.8     .07       0  4903.8     .05       0
  4907.8     .07       0  5545.4     .05       0
Bank Sta=4903.8,4907.8
XS Rating Curve= 0 ,0
Exp/Cntr=0.3,0.1

Type RM Length L Ch R = 1 ,27750   ,500,500,500
BEGIN DESCRIPTION:
YOW BRANCH 60.0
END DESCRIPTION:
XS GIS Cut Line= 3
      2386474.98     13702475.02        2385675.       13703175.
      2385274.98     13703575.02
#Sta/Elev= 30
    3937  427.78  3986.8  427.52  3993.4  426.48  4008.6  425.71  4050.3  423.23
  4078.9  421.98  4107.3  419.41  4153.4  416.61  4184.5  414.57  4305.7  408.31
  4413.1  404.67  4518.3  400.25  4574.8  399.21  4624.6  396.93  4681.1  395.63
  4815.4  394.87  4863.9  393.81  4978.6   392.2  4990.8   388.5  4991.1     388
    4995   388.5  4996.7  390.14  5003.5  390.14  5014.1  392.56  5127.3  392.52
  5311.1  397.99  5353.5  396.98    5396   397.9  5466.7  401.49  5565.7  404.15
#Mann= 9 ,-1 , 0
    3937     .07       0  4008.6     .05       0  4050.3     .12       0
  4153.4     .05       0  4184.5     .07       0  4413.1     .05       0
  4863.9     .07       0  4990.8     .05       0    4995     .07       0
Bank Sta=4990.8,4995
XS Rating Curve= 0 ,0
Exp/Cntr=0.3,0.1

Type RM Length L Ch R = 1 ,27250   ,500,500,500
BEGIN DESCRIPTION:
YOW BRANCH 59.0
END DESCRIPTION:
XS GIS Cut Line= 3
      2386425.02     13702424.99        2385675.       13702675.
      2385025.02       13702725.
#Sta/Elev= 30
  4209.4  428.78  4243.1  427.72  4347.9  418.41  4420.2  411.95  4467.7  408.84
  4546.7  404.39  4567.8  402.34    4610  400.65  4631.1  398.94  4715.4  395.34
  4789.2  393.35  4841.9  392.73    4884  390.88  4926.2  391.82  4989.5  390.93
  4995.3  388.17  4995.5  387.67  4999.2  387.67  4999.5  388.17  5002.5  388.17
  5020.1  390.96  5050.1  390.26  5090.3  390.55  5180.5  393.43    5331  396.86
  5441.3  401.38  5491.4  404.01  5541.6  405.45  5611.8  409.25  5651.9  410.24
#Mann= 6 ,-1 , 0
  4209.4     .07       0  4243.1     .12       0  4347.9     .07       0
  4467.7     .05       0  4995.3     .05       0  4999.5     .05       0
Bank Sta=4995.3,4999.5
XS Rating Curve= 0 ,0
Exp/Cntr=0.3,0.1

Type RM Length L Ch R = 1 ,26750   ,500,500,500
BEGIN DESCRIPTION:
YOW BRANCH 58.0
END DESCRIPTION:
XS GIS Cut Line= 3
      2386424.99       13702375.        2385675.       13702175.
      2384974.97     13702625.02
#Sta/Elev= 30
  4223.8   428.8  4275.5  426.92  4336.2   421.3    4379  417.08  4396.5  414.54
  4401.7   414.7  4436.6  411.15  4488.6  407.52  4499.7  406.59  4591.8  399.35
  4679.2  394.84  4803.4  391.33  4917.2  389.77  4940.3  388.29  4940.6  387.79
  4944.3  387.79  4944.6  388.29  4982.5  389.66  4989.6  388.56  5007.6  389.35
  5231.5  391.67  5340.5  394.74  5382.7  394.41    5392  395.35  5491.7  398.62
  5512.8  399.95  5630.1   404.4  5709.7  406.33  5773.1  409.12  5832.2  410.43
#Mann= 6 ,-1 , 0
  4223.8     .07       0  4336.2     .05       0  4488.6     .07       0
  4499.7     .05       0  4940.3     .05       0  4944.6     .05       0
Bank Sta=4940.3,4944.6
XS Rating Curve= 0 ,0
Exp/Cntr=0.3,0.1

Type RM Length L Ch R = 1 ,26250   ,478,478,478
BEGIN DESCRIPTION:
YOW BRANCH 57.0
END DESCRIPTION:
XS GIS Cut Line= 3
      2386425.02     13702325.02        2385675.       13701675.
        2385125.       13701975.
#Sta/Elev= 30
  4007.5  428.18    4064  425.74  4109.3  421.34  4149.5  417.31  4184.6  414.96
  4213.2  412.15  4326.1  404.72  4497.2   397.8    4518  395.82  4681.4  390.74
  4831.7  389.14  4917.4  388.67  4950.1  387.85  4957.8  388.35  4964.4  387.19
  4984.1  386.69  4984.4  386.19  4988.5  386.69  4992.9  386.74  4996.7  387.95
  5013.8  388.54  5051.7  387.94  5176.8  389.71  5182.4  389.55  5318.5  391.87
  5455.6  395.89  5521.5  398.84  5569.1  400.68  5591.5  402.68  5626.5  403.11
#Mann= 10 ,-1 , 0
  4007.5     .07       0  4109.3     .05       0  4831.7     .07       0
  4917.4     .05       0  4984.1     .05       0  4988.5     .05       0
  5176.8     .07       0  5182.4     .05       0  5521.5     .07       0
  5591.5     .05       0
Bank Sta=4984.1,4988.5
XS Rating Curve= 0 ,0
Exp/Cntr=0.3,0.1

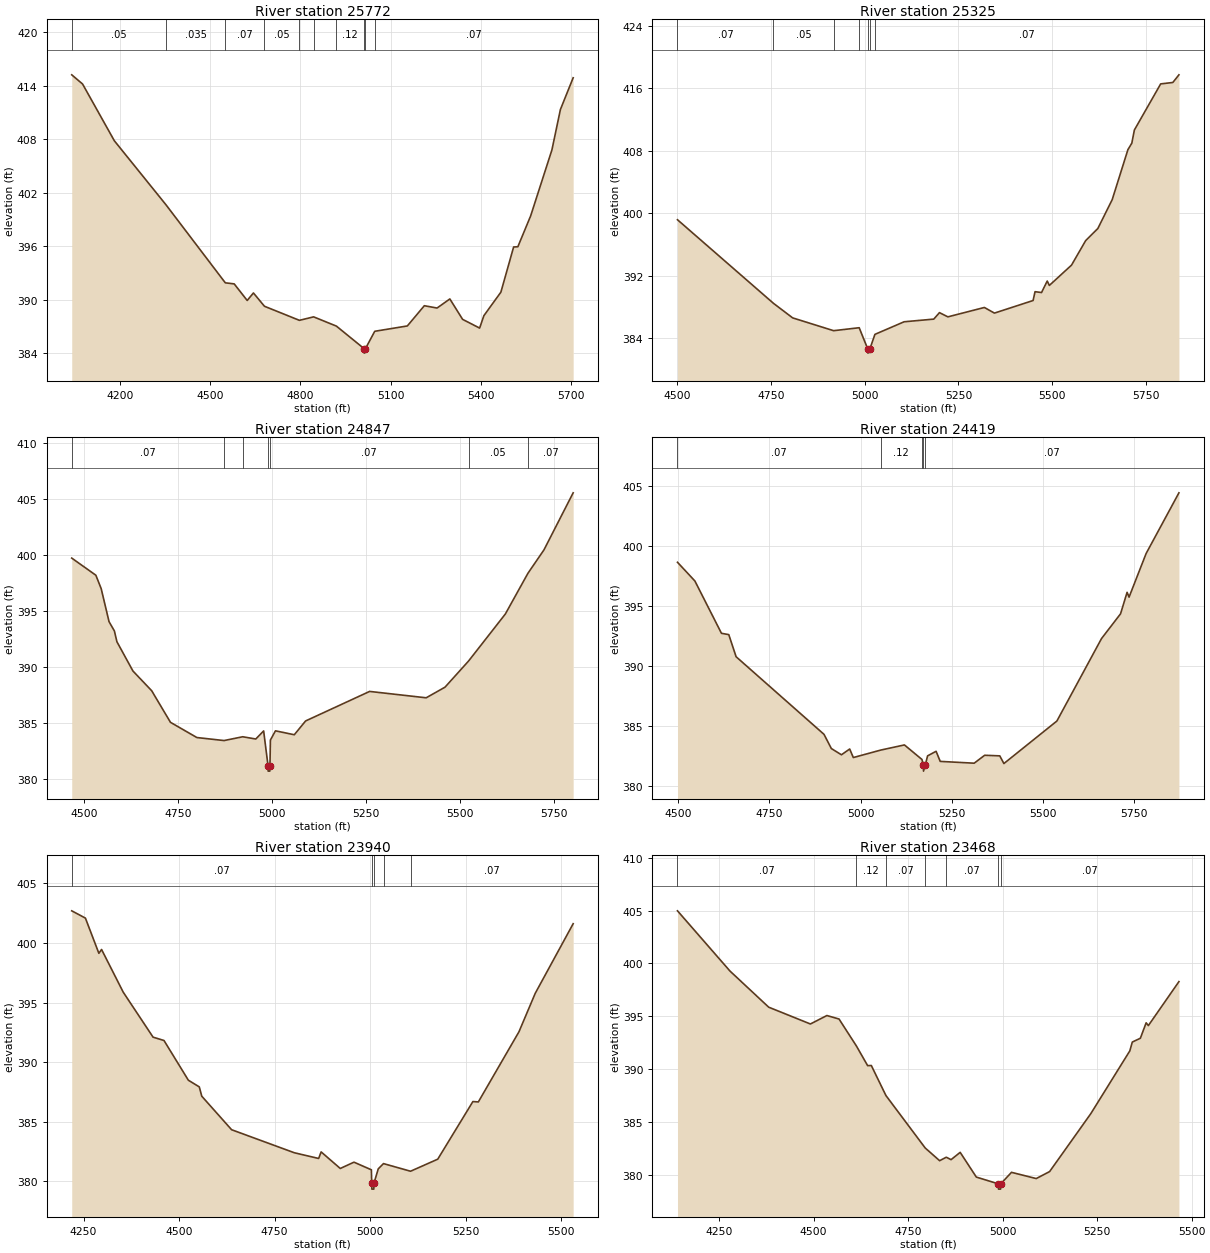
Type RM Length L Ch R = 1 ,25772   ,447,447,447
BEGIN DESCRIPTION:
YOW BRANCH 56.0
END DESCRIPTION:
XS GIS Cut Line= 3
      2386425.02     13701825.01        2385675.       13701225.
        2385175.       13700725.
#Sta/Elev= 30
  4039.4  415.25  4075.4  414.22  4181.1  407.85  4353.2  400.65  4550.1  391.91
  4579.7  391.79  4622.9  389.93  4643.7  390.77  4680.3  389.28  4796.5   387.7
  4843.9  388.09  4919.7  387.05  5011.8  384.52  5012.1  384.02  5016.2  384.52
  5047.1  386.47  5155.5  387.07    5212  389.34  5254.4  389.08  5296.9   390.1
  5339.3  387.81  5395.9  386.83    5410  388.22  5466.6  390.86    5509  395.93
  5523.1  395.96  5565.6  399.42  5636.3  406.82  5664.6  411.36    5707  414.92
#Mann= 10 ,-1 , 0
  4039.4     .05       0  4353.2    .035       0  4550.1     .07       0
  4680.3     .05       0  4796.5     .07       0  4843.9     .05       0
  4919.7     .12       0  5011.8     .05       0  5016.2     .12       0
  5047.1     .07       0
Bank Sta=5011.8,5016.2
XS Rating Curve= 0 ,0
Exp/Cntr=0.3,0.1

Type RM Length L Ch R = 1 ,25325   ,478,478,478
BEGIN DESCRIPTION:
YOW BRANCH 55.0
END DESCRIPTION:
XS GIS Cut Line= 3
      2386375.02     13701225.02        2385975.       13700925.
      2385174.98     13700674.99
#Sta/Elev= 30
  4500.2  399.17  4756.1  388.49  4807.5  386.62  4916.9  384.98  4985.1  385.36
  5008.2  382.61  5008.5  382.11  5013.3  382.61  5027.1  384.51    5105  386.12
  5184.1  386.46  5199.3  387.29  5221.8  386.75  5319.2  387.95    5346  387.23
  5449.2  388.84  5454.4  389.97  5471.7  389.86  5486.9  391.33  5492.6  390.77
  5551.8  393.37  5589.6  396.51    5622  398.05  5660.3  401.74  5702.2  408.13
  5712.7  408.97  5719.5  410.65  5789.7  416.55  5822.1  416.73  5838.4  417.71
#Mann= 7 ,-1 , 0
  4500.2     .07       0  4756.1     .05       0  4916.9     .07       0
  4985.1     .12       0  5008.2     .05       0  5013.3     .12       0
  5027.1     .07       0
Bank Sta=5008.2,5013.3
XS Rating Curve= 0 ,0
Exp/Cntr=0.3,0.1

Type RM Length L Ch R = 1 ,24847   ,428,428,428
BEGIN DESCRIPTION:
YOW BRANCH 54.0
END DESCRIPTION:
XS GIS Cut Line= 3
      2386525.02     13700925.02        2386175.       13700525.
      2385374.99       13700475.
#Sta/Elev= 30
  4467.7  399.75  4531.8  398.22    4546  397.02  4566.9  394.07  4581.1  393.24
  4587.8  392.28  4630.5  389.66  4680.3   387.9  4730.2  385.08  4800.4  383.72
  4872.6  383.45  4922.3  383.79    4957  383.59  4977.9  384.31  4989.5  381.22
  4989.9  380.72  4994.3  380.72  4994.7  381.22  4995.9   383.5  5009.3  384.32
  5059.4  383.97  5089.4   385.2  5259.7  387.84    5410  387.27  5460.1  388.22
  5522.6  390.55  5620.4  394.75  5680.5  398.39  5723.1  400.48  5800.8  405.58
#Mann= 7 ,-1 , 0
  4467.7     .07       0  4872.6     .12       0  4922.3     .07       0
  4989.5     .05       0  4994.7     .07       0  5522.6     .05       0
  5680.5     .07       0
Bank Sta=4989.5,4994.7
XS Rating Curve= 0 ,0
Exp/Cntr=0.3,0.1

Type RM Length L Ch R = 1 ,24419   ,479,479,479
BEGIN DESCRIPTION:
YOW BRANCH 53.0
END DESCRIPTION:
XS GIS Cut Line= 3
        2386525.     13700825.03        2386475.       13700325.
      2386125.01     13699525.03
#Sta/Elev= 30
  4497.8  398.62  4545.6  397.06  4618.4  392.71  4638.5   392.6  4658.6  390.76
  4899.8   384.3  4919.9  383.12  4947.6   382.6  4970.2  383.08  4980.2  382.37
  5055.3  382.99  5120.4  383.42  5168.5  382.21  5172.4  381.74  5172.8  381.24
  5177.6  381.74  5183.9  382.51  5207.3  382.89  5218.6  382.05  5311.8   381.9
  5340.6  382.56    5382  382.51  5393.3  381.87  5538.7  385.41  5661.1  392.27
  5713.3  394.33  5731.3  396.12  5736.7  395.72  5783.5  399.35  5873.5   404.4
#Mann= 5 ,-1 , 0
  4497.8     .07       0  5055.3     .12       0  5168.5     .07       0
  5172.4     .05       0  5177.6     .07       0
Bank Sta=5172.4,5177.6
XS Rating Curve= 0 ,0
Exp/Cntr=0.3,0.1

Type RM Length L Ch R = 1 ,23940   ,472,472,472
BEGIN DESCRIPTION:
YOW BRANCH 52.0
END DESCRIPTION:
XS GIS Cut Line= 3
      2387175.03     13700525.03        2386675.       13699925.
      2386324.98     13699524.98
#Sta/Elev= 30
  4219.2  402.69    4255  402.08  4290.2  399.13  4297.3  399.45    4354  395.87
  4432.1   392.1  4460.7  391.82  4524.5  388.49  4553.1  387.93  4559.6  387.15
  4637.7  384.34  4801.8  382.41  4865.5  381.93  4872.1  382.48  4922.2  381.09
    4958  381.62  5003.6  380.98  5004.4  379.86  5004.9  379.36  5009.9  379.36
  5010.4  379.86  5021.6  381.06  5035.3   381.5  5106.1  380.86  5177.3  381.87
  5269.3   386.7  5283.6  386.67  5389.9  392.55  5432.6  395.78  5531.8  401.61
#Mann= 5 ,-1 , 0
  4219.2     .07       0  5004.4     .05       0  5010.4     .07       0
  5035.3     .12       0  5106.1     .07       0
Bank Sta=5004.4,5010.4
XS Rating Curve= 0 ,0
Exp/Cntr=0.3,0.1

Type RM Length L Ch R = 1 ,23468   ,446,446,446
BEGIN DESCRIPTION:
YOW BRANCH 51.0
END DESCRIPTION:
XS GIS Cut Line= 3
      2387774.97     13699924.99        2386975.       13699625.
      2386574.97     13699374.98
#Sta/Elev= 30
  4140.3  404.97  4279.1  399.27  4381.5  395.85  4491.8  394.26  4535.4  395.06
  4567.5  394.73  4613.6  392.17  4643.1  390.32  4652.9  390.33  4691.5  387.49
  4795.5  382.52  4833.6  381.32  4851.1  381.65  4863.8  381.42  4887.9  382.11
  4930.6  379.77  4988.8  379.13  4989.3  378.63  4994.7  378.63  4995.2  379.13
  5023.6  380.22    5089  379.63  5124.4  380.29  5233.5  385.78  5336.6  391.72
  5343.1  392.55  5364.4  392.91  5379.7  394.37  5385.6  394.11  5466.4  398.27
#Mann= 7 ,-1 , 0
  4140.3     .07       0  4613.6     .12       0  4691.5     .07       0
  4795.5     .12       0  4851.1     .07       0  4988.8     .05       0
  4995.2     .07       0
Bank Sta=4988.8,4995.2
XS Rating Curve= 0 ,0
Exp/Cntr=0.3,0.1

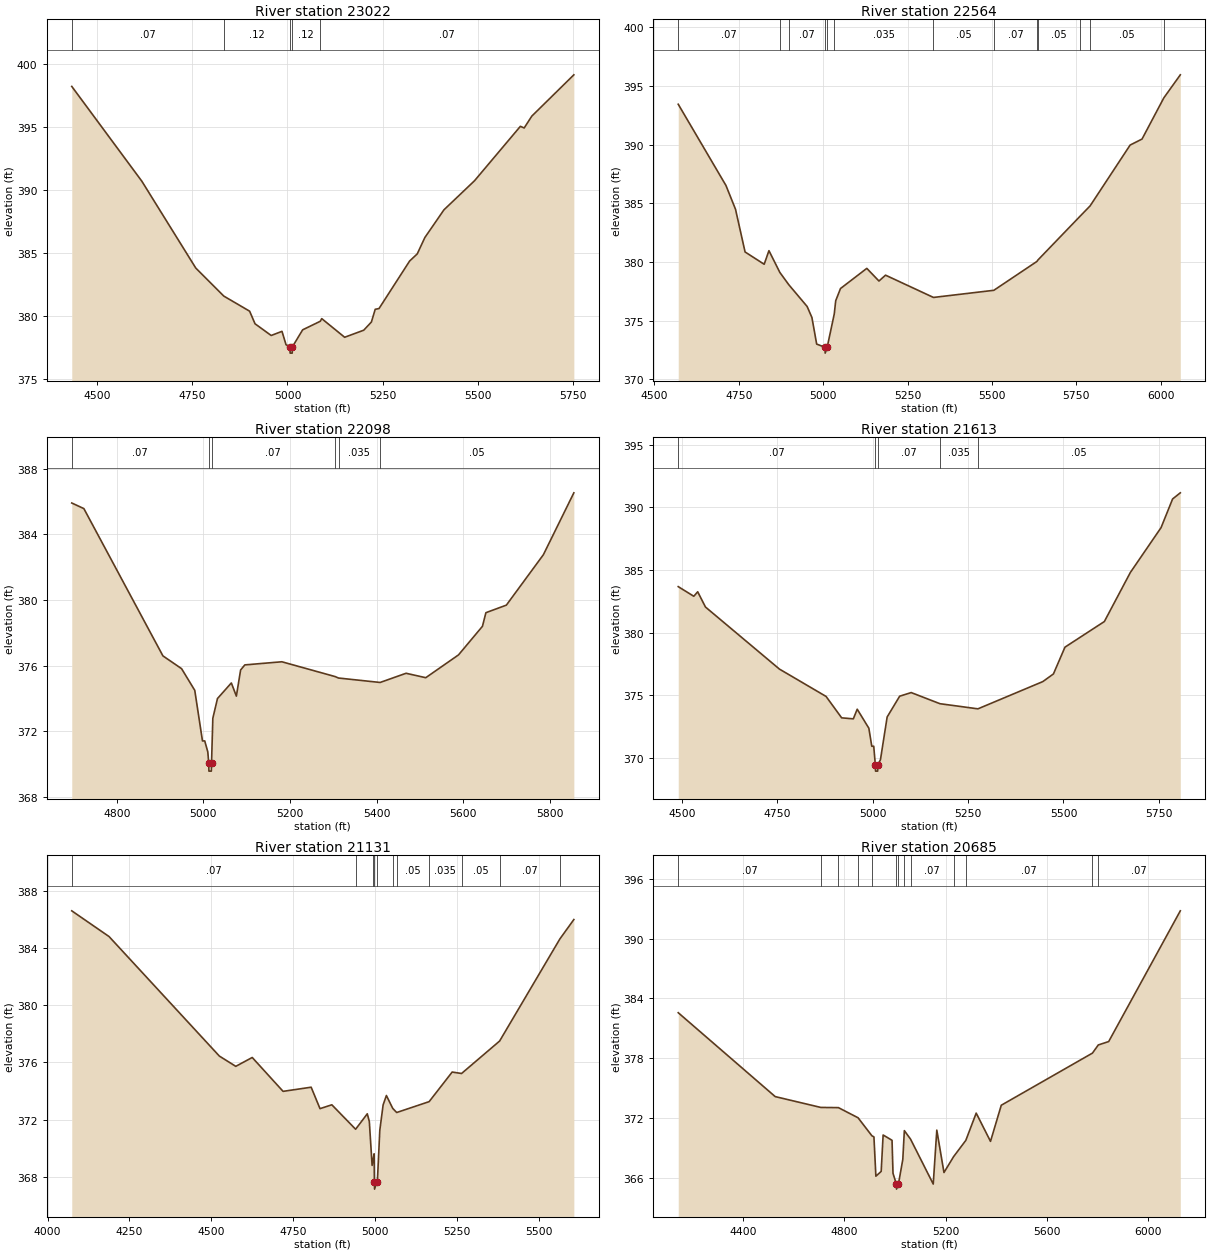
Type RM Length L Ch R = 1 ,23022   ,458,458,458
BEGIN DESCRIPTION:
YOW BRANCH 50.0
END DESCRIPTION:
XS GIS Cut Line= 3
      2387675.01     13699725.01        2387275.       13699325.
      2386524.97       13699275.
#Sta/Elev= 30
    4434  398.23  4617.9   390.7  4759.3  383.81  4832.9  381.58  4900.7  380.38
  4914.9  379.38  4957.3  378.45  4985.6  378.78  4996.2  377.72  5006.5  377.55
    5007  377.05  5012.4  377.05  5012.9  377.55  5039.8   378.9  5086.1  379.58
  5089.9  379.79    5150  378.31  5200.1  378.87  5220.2  379.52  5230.2  380.53
  5240.2  380.59  5320.4  384.36  5340.5  384.93  5360.5  386.23  5410.6  388.43
  5490.8  390.74  5611.1  395.06  5621.1  394.93  5641.1  395.87  5751.4  399.15
#Mann= 5 ,-1 , 0
    4434     .07       0  4832.9     .12       0  5006.5     .05       0
  5012.9     .12       0  5086.1     .07       0
Bank Sta=5006.5,5012.9
XS Rating Curve= 0 ,0
Exp/Cntr=0.3,0.1

Type RM Length L Ch R = 1 ,22564   ,466,466,466
BEGIN DESCRIPTION:
YOW BRANCH 49.0
END DESCRIPTION:
XS GIS Cut Line= 3
        2387875.       13699325.        2387575.       13699025.
      2386774.99     13698324.99
#Sta/Elev= 30
  4570.6  393.45    4712  386.52  4740.3  384.49  4768.6  380.85  4825.2   379.8
  4839.3  380.96  4871.7   379.1    4898  378.06  4952.4   376.2  4966.6  375.26
  4980.7  372.99  5005.4  372.72  5005.9  372.22  5011.8  372.72  5032.8  375.56
  5037.1  376.69  5051.3  377.73  5129.2  379.45  5165.2  378.37  5184.7  378.87
  5326.7  376.97  5505.6  377.58  5633.1  380.04    5636  380.16  5760.7  383.89
  5790.7  384.78  5909.3  389.97  5944.5  390.48    6009  393.99  6057.9  395.96
#Mann= 13 ,-1 , 0
  4570.6     .07       0  4871.7     .12       0    4898     .07       0
  5005.4     .05       0  5011.8     .07       0  5032.8    .035       0
  5326.7     .05       0  5505.6     .07       0  5633.1    .035       0
    5636     .05       0  5760.7    .035       0  5790.7     .05       0
    6009    .035       0
Bank Sta=5005.4,5011.8
XS Rating Curve= 0 ,0
Exp/Cntr=0.3,0.1

Type RM Length L Ch R = 1 ,22098   ,485,485,485
BEGIN DESCRIPTION:
YOW BRANCH 48.0
END DESCRIPTION:
XS GIS Cut Line= 3
      2388074.97       13698675.        2387775.       13698625.
      2386975.01       13698325.
#Sta/Elev= 30
  4696.3   385.9  4724.2  385.56  4906.6  376.59  4949.7  375.81  4980.1  374.49
  4997.9  371.41  5003.1  371.41  5010.2  370.74  5012.3  370.07  5012.8  369.57
  5018.3  369.57  5018.8  370.07  5021.8  372.79  5032.5  373.99  5064.5  374.94
  5076.1  374.14  5085.9  375.73  5095.6  376.04  5181.1  376.23  5303.8  375.33
  5311.8  375.24  5407.8  374.97  5467.7  375.53  5513.1  375.26  5588.7  376.65
  5643.9  378.39  5651.9  379.22  5699.1  379.68  5784.5  382.75  5854.8  386.52
#Mann= 6 ,-1 , 0
  4696.3     .07       0  5012.3     .05       0  5018.8     .07       0
  5303.8     .05       0  5311.8    .035       0  5407.8     .05       0
Bank Sta=5012.3,5018.8
XS Rating Curve= 0 ,0
Exp/Cntr=0.3,0.1

Type RM Length L Ch R = 1 ,21613   ,482,482,482
BEGIN DESCRIPTION:
YOW BRANCH 47.0
END DESCRIPTION:
XS GIS Cut Line= 3
      2388175.04     13698275.01        2387675.       13698175.
      2386874.97       13698275.
#Sta/Elev= 30
  4490.1  383.67  4530.9   382.9  4541.1  383.26  4561.5  382.04  4755.3  377.08
  4877.7  374.89  4918.5  373.18  4949.1   373.1  4959.3  373.87  4989.8  372.35
  4997.5  370.91  5002.6  370.91  5006.8  369.42  5007.3  368.92  5012.9  368.92
  5013.4  369.42  5020.2  369.83  5037.8  373.25  5070.6  374.91  5100.8   375.2
  5176.2  374.31  5275.8   373.9    5446  376.08  5473.7  376.69  5503.9  378.83
  5607.2  380.88  5675.3   384.8  5755.9  388.39  5786.1  390.68  5806.3  391.17
#Mann= 5 ,-1 , 0
  4490.1     .07       0  5006.8     .05       0  5013.4     .07       0
  5176.2    .035       0  5275.8     .05       0
Bank Sta=5006.8,5013.4
XS Rating Curve= 0 ,0
Exp/Cntr=0.3,0.1

Type RM Length L Ch R = 1 ,21131   ,446,446,446
BEGIN DESCRIPTION:
YOW BRANCH 46.0
END DESCRIPTION:
XS GIS Cut Line= 3
      2388324.96     13698274.97        2387575.       13697725.
      2386974.99       13697775.
#Sta/Elev= 30
    4074   386.6  4187.8   384.8  4524.3  376.44  4574.5  375.72  4624.7  376.34
  4718.8  373.97  4804.5  374.26  4831.5  372.76  4867.6  373.03  4940.2  371.32
  4975.8   372.4    4982  371.86  4990.5  368.79  4994.3  369.29  4996.7   369.6
  4997.5  367.63    4998  367.13  5004.3  367.63  5006.5  367.63    5014  371.25
  5024.1  373.02  5034.1  373.68  5053.4  372.78  5065.5  372.49  5164.5  373.25
  5234.8  375.32  5263.5  375.22  5379.6  377.49  5563.4  384.63  5606.1  385.99
#Mann= 11 ,-1 , 0
    4074     .07       0  4940.2     .12       0  4994.3     .07       0
  4997.5     .05       0  5004.3     .07       0  5053.4     .12       0
  5065.5     .05       0  5164.5    .035       0  5263.5     .05       0
  5379.6     .07       0  5563.4     .05       0
Bank Sta=4997.5,5004.3
XS Rating Curve= 0 ,0
Exp/Cntr=0.3,0.1

Type RM Length L Ch R = 1 ,20685   ,440,440,440
BEGIN DESCRIPTION:
YOW BRANCH 45.0
END DESCRIPTION:
XS GIS Cut Line= 3
      2388275.02     13698025.03        2387725.       13697375.
      2386924.98     13696574.98
#Sta/Elev= 30
    4144  382.57  4526.9  374.14    4707  373.05  4776.7  373.03  4854.3  372.01
  4908.9   370.2  4916.9  370.09  4924.6  366.14  4945.5  366.62  4953.2  370.28
  4988.4  369.75  4992.2  366.43  5005.6  365.34  5006.1  364.84  5013.6  365.34
  5030.9  367.82    5037  370.72  5061.6  369.86  5151.1  365.35  5165.2  370.77
  5193.5  366.51  5231.7  368.11  5279.8  369.74  5320.8  372.48  5377.3  369.64
  5419.8  373.27  5779.9  378.51    5803  379.33    5844  379.67  6126.9  392.81
#Mann= 13 ,-1 , 0
    4144     .07       0    4707     .12       0  4776.7     .07       0
  4854.3     .12       0  4908.9     .07       0  5005.6     .05       0
  5013.6     .07       0    5037     .12       0  5061.6     .07       0
  5231.7     .12       0  5279.8     .07       0  5779.9    .035       0
    5803     .07       0
Bank Sta=5005.6,5013.6
XS Rating Curve= 0 ,0
Exp/Cntr=0.3,0.1

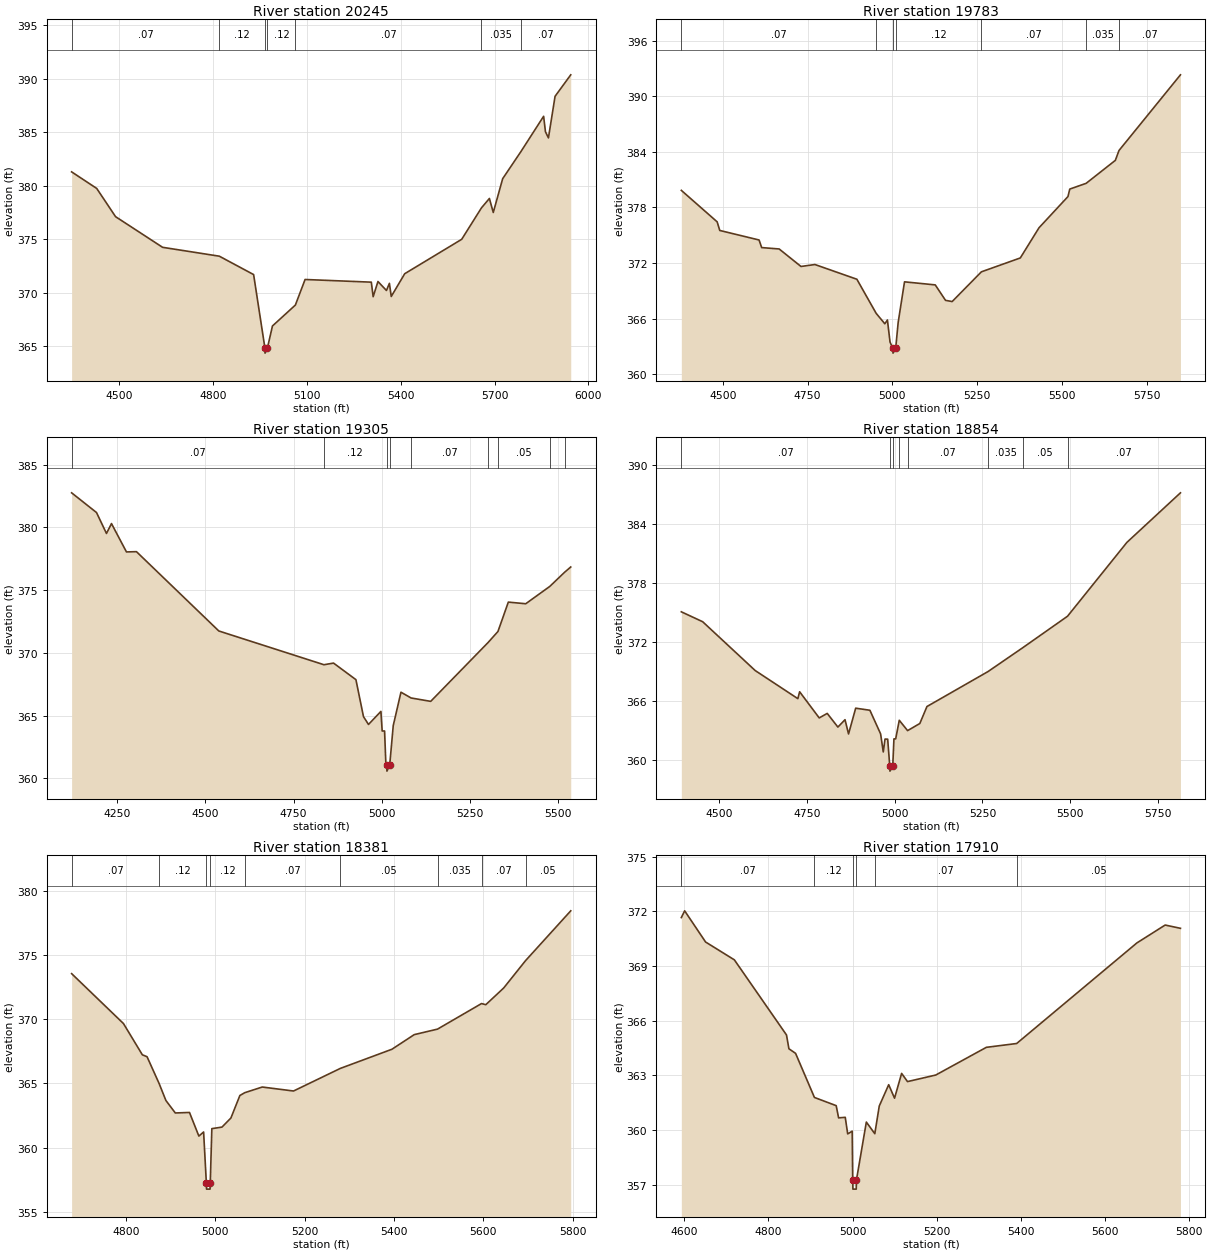
Type RM Length L Ch R = 1 ,20245   ,462,462,462
BEGIN DESCRIPTION:
YOW BRANCH 44.0
END DESCRIPTION:
XS GIS Cut Line= 3
      2388524.98       13696975.        2387875.       13697025.
        2387075.       13696525.
#Sta/Elev= 30
  4348.2   381.3  4428.4  379.75  4488.6  377.11    4639  374.24  4820.3  373.41
  4929.9  371.69  4965.9  364.84  4966.4  364.34  4974.2  364.84  4990.1  366.88
  5063.4  368.84  5094.4  371.23  5306.1  370.98    5312  369.62  5327.3  371.04
  5354.5   370.2  5363.9  370.87  5369.8  369.64  5412.8  371.77    5595  374.99
  5658.1  377.93  5683.5  378.81  5695.9   377.5  5725.9  380.66  5784.3   383.2
  5856.8   386.5  5862.7  385.05  5872.2  384.48  5893.4  388.37  5943.5  390.38
#Mann= 7 ,-1 , 0
  4348.2     .07       0  4820.3     .12       0  4965.9     .05       0
  4974.2     .12       0  5063.4     .07       0  5658.1    .035       0
  5784.3     .07       0
Bank Sta=4965.9,4974.2
XS Rating Curve= 0 ,0
Exp/Cntr=0.3,0.1

Type RM Length L Ch R = 1 ,19783   ,478,478,478
BEGIN DESCRIPTION:
YOW BRANCH 43.0
END DESCRIPTION:
XS GIS Cut Line= 3
      2388475.04     13696875.01        2387875.       13696725.
      2387075.01       13696425.
#Sta/Elev= 30
  4377.3  379.85    4483  376.45  4490.7  375.52  4606.7  374.49  4614.4  373.67
    4666  373.52  4730.4  371.63  4771.6  371.84  4895.3  370.25  4952.2  366.57
  4977.8  365.44  4985.5  365.85  4993.2  363.46  5001.5  362.77    5002  362.27
  5009.8  362.77  5017.2  365.59  5035.9  369.97  5126.6  369.64  5156.9  367.97
  5176.5  367.84  5262.7  371.05  5377.6  372.55  5432.8  375.81  5518.2  379.18
  5523.6  379.99  5571.9  380.61    5658  383.09  5668.9  384.16  5850.2  392.33
#Mann= 7 ,-1 , 0
  4377.3     .07       0  4952.2     .12       0  5001.5     .05       0
  5009.8     .12       0  5262.7     .07       0  5571.9    .035       0
  5668.9     .07       0
Bank Sta=5001.5,5009.8
XS Rating Curve= 0 ,0
Exp/Cntr=0.3,0.1

Type RM Length L Ch R = 1 ,19305   ,451,451,451
BEGIN DESCRIPTION:
YOW BRANCH 42.0
END DESCRIPTION:
XS GIS Cut Line= 3
      2388624.97     13696874.97        2387975.       13696275.
      2387574.97     13695924.97
#Sta/Elev= 30
  4120.4  382.76    4191  381.19  4219.3  379.52  4233.5  380.31    4276  378.05
  4304.4  378.07    4538  371.75  4836.3  369.06  4863.5  369.19    4927  367.87
  4948.5  364.92  4962.7   364.3  4997.9  365.34  5001.5  363.78  5008.3  363.78
  5012.1  361.08  5014.5  361.08    5015  360.58  5022.9  361.08  5032.9  364.21
  5054.8  366.87  5083.5  366.41  5139.2  366.14    5302  370.83    5330  371.71
  5359.4  374.05  5408.8  373.92    5477   375.3  5519.1  376.43  5536.5  376.85
#Mann= 9 ,-1 , 0
  4120.4     .07       0  4836.3     .12       0  5014.5     .05       0
  5022.9     .12       0  5083.5     .07       0    5302    .035       0
    5330     .05       0    5477    .035       0  5519.1     .05       0
Bank Sta=5014.5,5022.9
XS Rating Curve= 0 ,0
Exp/Cntr=0.3,0.1

Type RM Length L Ch R = 1 ,18854   ,473,473,473
BEGIN DESCRIPTION:
YOW BRANCH 41.0
END DESCRIPTION:
XS GIS Cut Line= 3
      2388725.03       13695775.        2388125.       13695875.
      2387325.04     13695725.01
#Sta/Elev= 30
  4392.1  375.09    4453  374.08  4602.5  369.12  4724.1  366.26  4729.2  366.96
    4785   364.3  4807.8  364.76  4838.2  363.37  4858.5  364.12  4868.6  362.67
  4888.9  365.29  4929.4  365.08  4959.9  362.68  4967.5  360.84  4972.5  362.15
  4980.1  362.14    4986  359.39  4986.5  358.89  4994.5  359.39  4997.9  362.17
  5002.9  362.17  5013.1  364.06  5036.8  363.01  5071.6  363.73    5092  365.46
  5265.8  369.01  5365.4  371.45  5492.5  374.64  5661.7  382.15  5814.3  387.19
#Mann= 8 ,-1 , 0
  4392.1     .07       0    4986     .05       0  4994.5     .07       0
  5013.1     .12       0  5036.8     .07       0  5265.8    .035       0
  5365.4     .05       0  5492.5     .07       0
Bank Sta=4986,4994.5
XS Rating Curve= 0 ,0
Exp/Cntr=0.3,0.1

Type RM Length L Ch R = 1 ,18381   ,471,471,471
BEGIN DESCRIPTION:
YOW BRANCH 40.0
END DESCRIPTION:
XS GIS Cut Line= 3
      2388675.04     13695625.01        2388375.       13695525.
      2387574.97       13695525.
#Sta/Elev= 30
    4679  373.54    4795  369.65  4837.2  367.22  4847.7  367.07  4874.6  364.99
  4889.9  363.66  4910.9  362.69  4942.6  362.73  4963.6  360.89  4974.2  361.21
  4980.3  357.26  4980.8  356.76  4988.6  356.76  4989.1  357.26  4992.6  361.47
  5015.3  361.59  5035.3   362.3  5055.3  364.05  5066.3  364.27  5105.3  364.71
  5175.3   364.4    5280  366.16  5395.3  367.65  5445.3  368.79  5497.4  369.22
  5595.8  371.21  5605.3  371.12  5645.3  372.42  5694.2  374.55  5795.3  378.43
#Mann= 9 ,-1 , 0
    4679     .07       0  4874.6     .12       0  4980.3     .05       0
  4989.1     .12       0  5066.3     .07       0    5280     .05       0
  5497.4    .035       0  5595.8     .07       0  5694.2     .05       0
Bank Sta=4980.3,4989.1
XS Rating Curve= 0 ,0
Exp/Cntr=0.3,0.1

Type RM Length L Ch R = 1 ,17910   ,431,431,431
BEGIN DESCRIPTION:
YOW BRANCH 39.0
END DESCRIPTION:
XS GIS Cut Line= 3
      2388775.01     13695475.01        2388575.       13695125.
      2387875.04     13694775.02
#Sta/Elev= 30
    4593  371.65  4600.9  372.02  4650.6  370.31    4719  369.33  4842.8  365.21
  4848.6  364.45  4864.4   364.2  4909.2  361.78  4960.9  361.33  4966.6  360.66
  4982.4  360.69  4988.2  359.78  4998.9  359.93  5000.1  357.25  5000.6  356.75
  5008.5  356.75    5009  357.25  5032.5  360.43  5052.6  359.79  5063.2  361.31
  5085.6  362.48  5099.5  361.74  5116.3   363.1  5130.3  362.65  5197.4  363.01
  5317.6  364.53  5389.6  364.74  5675.3  370.26  5742.4  371.24  5778.7  371.06
#Mann= 6 ,-1 , 0
    4593     .07       0  4909.2     .12       0  5000.1     .05       0
    5009     .12       0  5052.6     .07       0  5389.6     .05       0
Bank Sta=5000.1,5009
XS Rating Curve= 0 ,0
Exp/Cntr=0.3,0.1

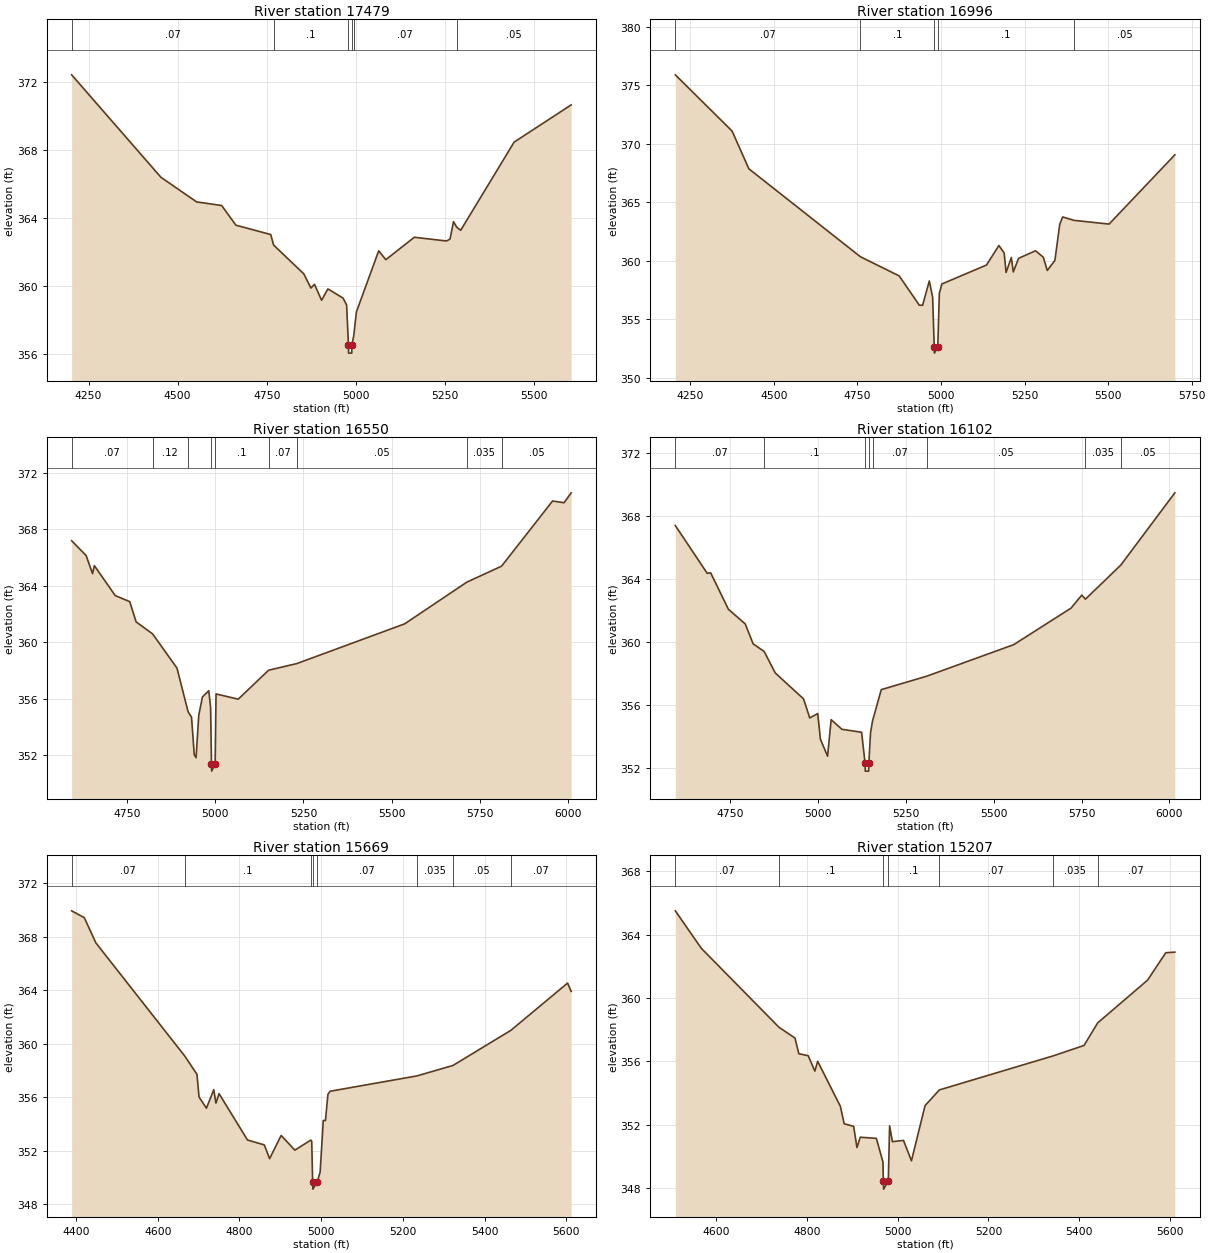
Type RM Length L Ch R = 1 ,17479   ,483,483,483
BEGIN DESCRIPTION:
YOW BRANCH 38.0
END DESCRIPTION:
XS GIS Cut Line= 3
      2389374.98       13694775.        2388575.       13694725.
      2387975.04       13694725.
#Sta/Elev= 30
  4202.6  372.43  4453.1   366.4  4553.3  364.95  4623.4  364.74  4663.5  363.58
  4761.2  363.03  4769.3  362.41  4853.8  360.72  4873.9  359.88  4883.9   360.1
  4903.9  359.16  4921.5  359.83  4964.1  359.29  4974.1  358.88  4979.2  356.55
  4979.7  356.05  4988.5  356.05    4989  356.55    4994  357.07  5001.6  358.48
  5064.1  362.07  5084.1  361.55  5164.1  362.87  5254.1  362.65  5264.1  362.76
  5274.1  363.79  5282.6  363.47  5294.1  363.28  5444.1  368.47  5604.1  370.66
#Mann= 6 ,-1 , 0
  4202.6     .07       0  4769.3      .1       0  4979.2     .05       0
    4989      .1       0    4994     .07       0  5282.6     .05       0
Bank Sta=4979.2,4989
XS Rating Curve= 0 ,0
Exp/Cntr=0.3,0.1

Type RM Length L Ch R = 1 ,16996   ,446,446,446
BEGIN DESCRIPTION:
YOW BRANCH 37.0
END DESCRIPTION:
XS GIS Cut Line= 3
      2389475.04       13694275.        2388675.       13694275.
      2388074.97     13694625.02
#Sta/Elev= 30
    4205  375.88    4375  371.07    4425  367.85  4758.8  360.33    4875  358.69
    4935  356.19    4945  356.18    4965  358.26    4975  356.87  4979.8  352.59
  4980.3  352.09  4990.3  352.59    4995  357.19  5002.5     358  5136.1  359.62
  5173.3  361.29    5189  360.65  5194.8  358.99  5210.5  360.26  5216.3  359.03
    5232  360.19  5282.9  360.84    5306  360.29    5318  359.16  5340.8  360.01
  5355.2  363.09  5363.9  363.73  5398.1  363.44  5502.9  363.12  5699.7  369.04
#Mann= 5 ,-1 , 0
    4205     .07       0  4758.8      .1       0  4979.8     .05       0
  4990.3      .1       0  5398.1     .05       0
Bank Sta=4979.8,4990.3
XS Rating Curve= 0 ,0
Exp/Cntr=0.3,0.1

Type RM Length L Ch R = 1 ,16550   ,448,448,448
BEGIN DESCRIPTION:
YOW BRANCH 36.0
END DESCRIPTION:
XS GIS Cut Line= 3
      2389224.99       13693975.        2388825.       13693875.
      2387824.98       13693775.
#Sta/Elev= 30
  4592.3  367.18  4633.5  366.13  4651.6  364.85  4656.7  365.42    4716   363.3
  4757.2  362.87  4775.2  361.44    4822  360.59  4891.2  358.17  4922.7  355.08
  4932.4   354.7  4940.2  352.04  4945.3  351.83  4953.1  354.85  4963.4  356.13
  4981.4  356.57  4986.6  355.38    4989  351.38  4989.5  350.88  4999.5  351.38
    5002  356.34  5064.9  355.97  5151.2  358.02  5231.4  358.49  5537.2   361.3
  5713.5  364.25  5812.1  365.38  5956.8  369.99  5989.5  369.87  6009.6  370.57
#Mann= 9 ,-1 , 0
  4592.3     .07       0    4822     .12       0  4922.7      .1       0
    4989     .05       0  4999.5      .1       0  5151.2     .07       0
  5231.4     .05       0  5713.5    .035       0  5812.1     .05       0
Bank Sta=4989,4999.5
XS Rating Curve= 0 ,0
Exp/Cntr=0.3,0.1

Type RM Length L Ch R = 1 ,16102   ,433,433,433
BEGIN DESCRIPTION:
YOW BRANCH 35.0
END DESCRIPTION:
XS GIS Cut Line= 3
      2389275.03       13693425.        2388875.       13693475.
      2387875.04     13693674.99
#Sta/Elev= 30
  4592.9  367.42  4683.6  364.39  4693.7  364.41  4744.1   362.1    4792  361.17
  4814.6   359.9  4845.9  359.42  4877.6  358.05  4958.2   356.4  4975.9  355.19
  4998.6  355.47  5006.2  353.84  5026.6  352.76  5036.8  355.08  5067.4  354.47
  5123.5  354.28  5133.5  352.31    5134  351.81  5143.7  351.81  5144.2  352.31
    5149  354.25  5154.8  355.01  5179.6  356.99  5308.5  357.84  5556.9  359.85
  5720.1  362.17  5750.7     363  5761.1  362.74    5862  364.91  6015.8   369.5
#Mann= 8 ,-1 , 0
  4592.9     .07       0  4845.9      .1       0  5133.5     .05       0
  5144.2      .1       0  5154.8     .07       0  5308.5     .05       0
  5761.1    .035       0    5862     .05       0
Bank Sta=5133.5,5144.2
XS Rating Curve= 0 ,0
Exp/Cntr=0.3,0.1

Type RM Length L Ch R = 1 ,15669   ,462,462,462
BEGIN DESCRIPTION:
YOW BRANCH 34.0
END DESCRIPTION:
XS GIS Cut Line= 3
      2389325.02     13693275.01        2388725.       13693125.
      2388175.04     13692875.02
#Sta/Elev= 30
  4389.4  369.95  4420.3  369.44  4448.7  367.55  4665.9  359.09  4696.1  357.71
  4701.2  356.01  4719.3  355.17  4737.3  356.56  4742.5  355.55  4750.2  356.26
  4819.8  352.79    4861  352.42  4873.9  351.39  4902.2  353.13  4935.7  352.03
  4974.7  352.78    4977   352.7  4979.3  349.61  4979.8  349.11  4990.1  349.61
  4997.6  350.39  5005.3  354.25  5010.6  354.25  5016.7  356.21  5022.2  356.44
  5234.8  357.59  5322.7  358.37  5464.4     361  5603.3  364.54    5612  363.92
#Mann= 8 ,-1 , 0
  4389.4     .07       0  4665.9      .1       0  4974.7     .07       0
  4979.3     .05       0  4990.1     .07       0  5234.8    .035       0
  5322.7     .05       0  5464.4     .07       0
Bank Sta=4979.3,4990.1
XS Rating Curve= 0 ,0
Exp/Cntr=0.3,0.1

Type RM Length L Ch R = 1 ,15207   ,456,456,456
BEGIN DESCRIPTION:
YOW BRANCH 33.0
END DESCRIPTION:
XS GIS Cut Line= 3
      2389274.98     13693074.99        2388875.       13692775.
      2388274.98       13692775.
#Sta/Elev= 30
  4510.5  365.51  4567.8  363.14  4738.8  358.15    4774  357.47  4782.4  356.48
  4803.2  356.35  4817.8  355.38    4824     356    4874  353.15  4882.4  352.05
  4903.2  351.89  4910.5  350.55  4917.8   351.2  4953.2  351.13  4967.8  349.63
  4968.6  348.42  4969.1  347.92  4979.5  348.42  4982.4  351.92  4988.6  350.92
    5013     351  5030.5  349.71  5060.5   353.2    5092  354.19  5342.3  356.34
  5410.5     357  5440.7  358.43  5550.5  361.13  5590.5  362.86  5610.5   362.9
#Mann= 7 ,-1 , 0
  4510.5     .07       0  4738.8      .1       0  4968.6     .05       0
  4979.5      .1       0    5092     .07       0  5342.3    .035       0
  5440.7     .07       0
Bank Sta=4968.6,4979.5
XS Rating Curve= 0 ,0
Exp/Cntr=0.3,0.1