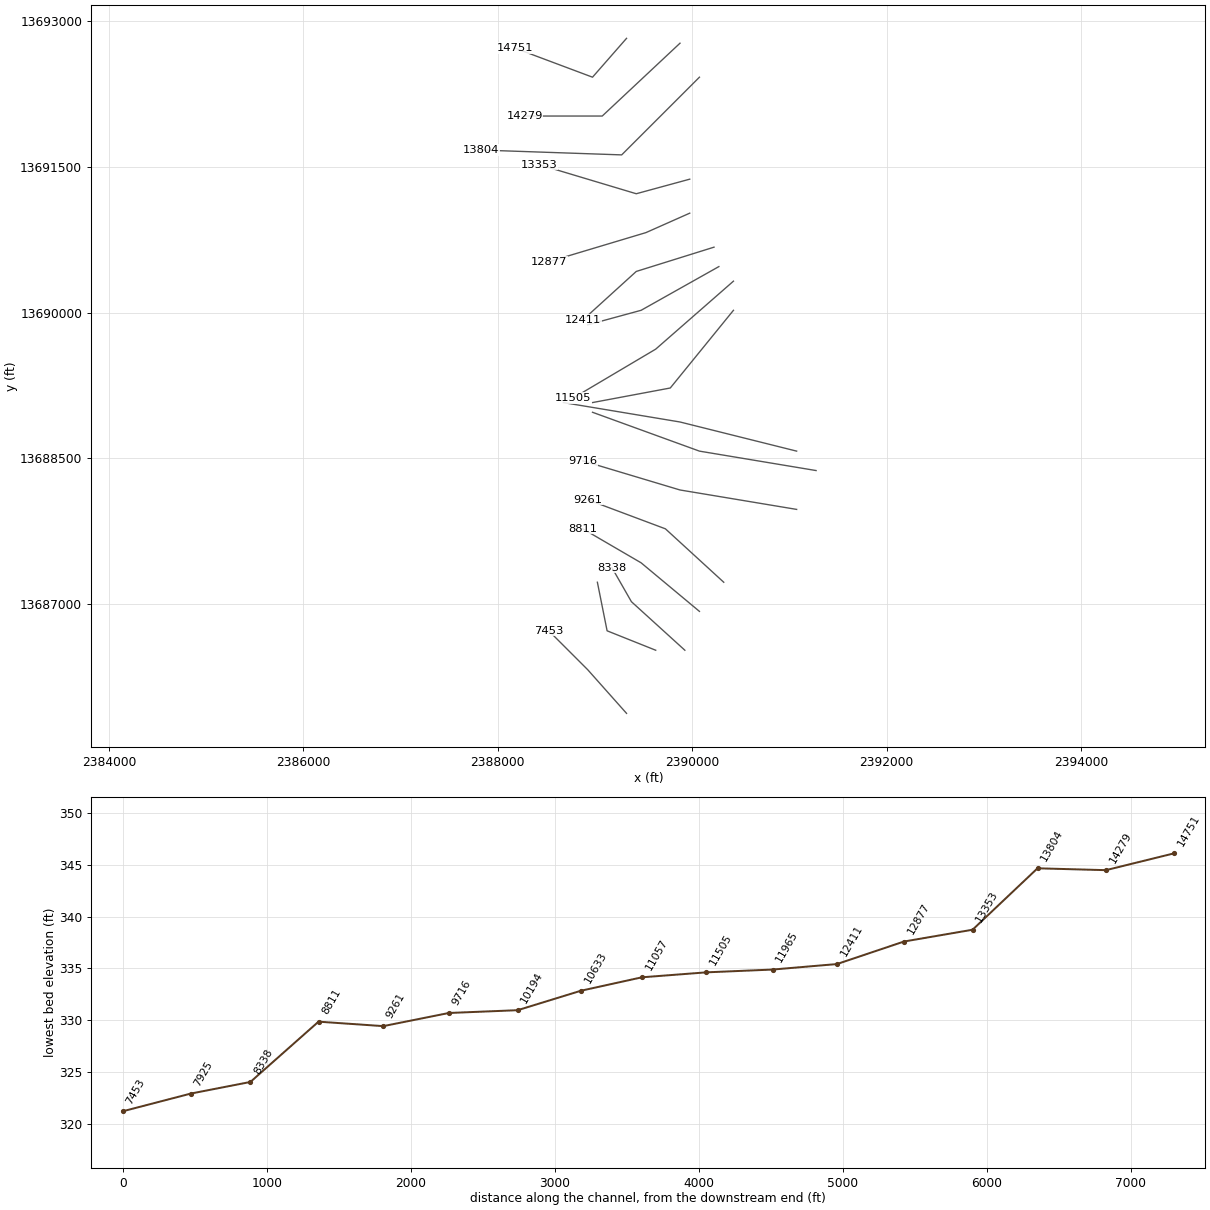
HEC-RAS study YOW BRANCH.prj: YOW BRANCH Base Level Engineering

--- YOW BRANCH.g01 (geometry) --- (continued)

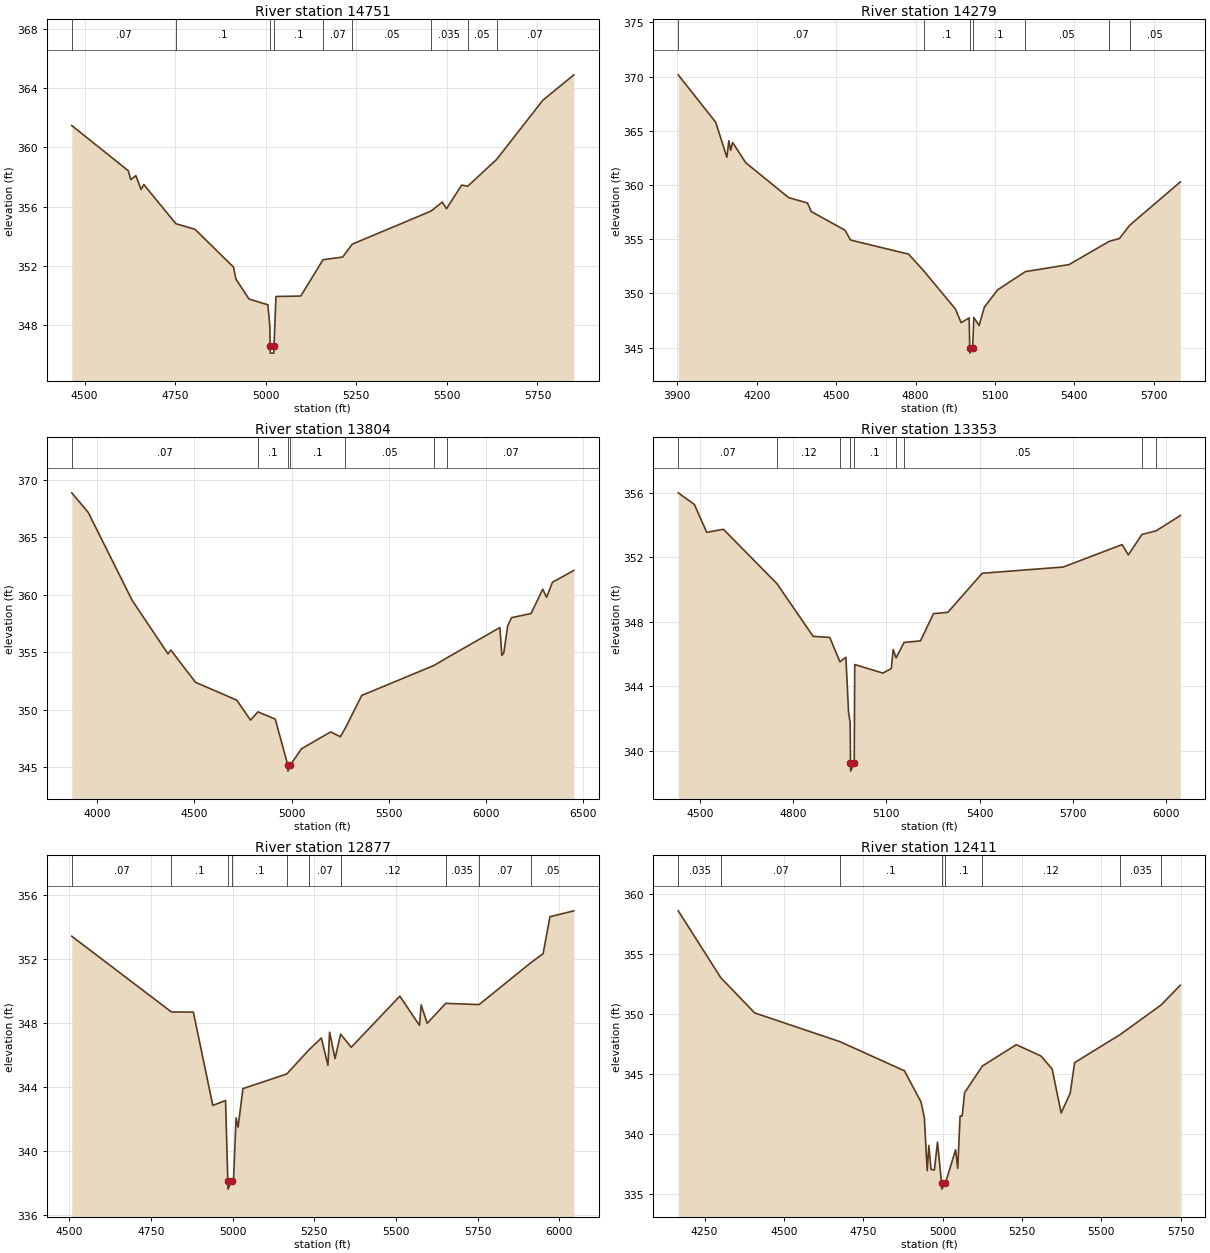
Type RM Length L Ch R = 1 ,14751   ,472,472,472
BEGIN DESCRIPTION:
YOW BRANCH 32.0
END DESCRIPTION:
XS GIS Cut Line= 3
      2389325.01     13692825.01        2388975.       13692425.
      2388175.03     13692724.99
#Sta/Elev= 30
  4464.5  361.47  4620.6  358.42  4627.3  357.82  4641.5  358.09  4655.8  357.16
  4663.4  357.49  4751.8  354.85  4804.8  354.47  4911.1  351.92  4917.7  351.11
  4953.8  349.77  5005.8  349.38  5011.2  347.95  5011.9  346.62  5012.4  346.12
  5022.3  346.12  5022.8  346.62  5028.1  349.94  5096.6  349.97  5158.1  352.42
  5212.3   352.6  5238.8  353.47  5456.2   355.7  5487.3  356.31  5498.9  355.86
  5540.7  357.45  5557.6  357.38  5637.1  359.18    5765  363.18  5850.4  364.89
#Mann= 9 ,-1 , 0
  4464.5     .07       0  4751.8      .1       0  5011.9     .05       0
  5022.8      .1       0  5158.1     .07       0  5238.8     .05       0
  5456.2    .035       0  5557.6     .05       0  5637.1     .07       0
Bank Sta=5011.9,5022.8
XS Rating Curve= 0 ,0
Exp/Cntr=0.3,0.1

Type RM Length L Ch R = 1 ,14279   ,475,475,475
BEGIN DESCRIPTION:
YOW BRANCH 31.0
END DESCRIPTION:
XS GIS Cut Line= 3
        2389875.       13692775.        2389075.       13692025.
      2388274.98       13692025.
#Sta/Elev= 30
  3903.4  370.17  4044.8   365.8  4087.3  362.56  4094.6  364.09  4101.5   363.2
  4108.8  363.93  4158.1  362.07  4320.8  358.84  4391.6  358.35  4405.8  357.56
  4533.3  355.84  4554.3  354.93  4773.6  353.63  4831.8  352.06  4950.4  348.57
  4971.9  347.31  5002.5  347.75  5004.5     345    5005   344.5  5015.5     345
    5020  347.79    5040  347.05    5060  348.75    5110  350.34  5214.8  352.02
    5380  352.67  5531.4  354.81    5570  355.07  5608.5  356.29    5800  360.29
#Mann= 7 ,-1 , 0
  3903.4     .07       0  4831.8      .1       0  5004.5     .05       0
  5015.5      .1       0  5214.8     .05       0  5531.4    .035       0
  5608.5     .05       0
Bank Sta=5004.5,5015.5
XS Rating Curve= 0 ,0
Exp/Cntr=0.3,0.1

Type RM Length L Ch R = 1 ,13804   ,451,451,451
BEGIN DESCRIPTION:
YOW BRANCH 30.0
END DESCRIPTION:
XS GIS Cut Line= 3
        2390075.       13692425.        2389275.       13691625.
      2387825.04       13691675.
#Sta/Elev= 30
  3868.9  368.87  3953.8  367.16    4180  359.51  4363.9  354.87    4378  355.21
  4505.3   352.4  4717.4  350.85  4788.1  349.12  4826.4  349.83  4915.4   349.2
  4980.4  345.18  4980.9  344.68  4991.8  345.18  5050.3  346.62  5200.4  348.09
  5250.4  347.67  5276.7  348.45  5360.5  351.26  5732.4  353.87  5798.5  354.53
  6070.9  357.16  6080.9  354.73  6090.9  354.97  6110.9  357.32  6130.9  358.02
    6231  358.38    6291  360.49  6311.1  359.79  6341.1   361.1  6451.1  362.12
#Mann= 7 ,-1 , 0
  3868.9     .07       0  4826.4      .1       0  4980.4     .05       0
  4991.8      .1       0  5276.7     .05       0  5732.4    .035       0
  5798.5     .07       0
Bank Sta=4980.4,4991.8
XS Rating Curve= 0 ,0
Exp/Cntr=0.3,0.1

Type RM Length L Ch R = 1 ,13353   ,476,476,476
BEGIN DESCRIPTION:
YOW BRANCH 29.0
END DESCRIPTION:
XS GIS Cut Line= 3
      2389975.04     13691375.01        2389425.       13691225.
      2388424.96     13691525.01
#Sta/Elev= 30
  4430.7     356  4482.6  355.28  4522.3  353.55  4575.9  353.74  4747.9  350.37
  4864.4   347.1  4917.9  347.03  4950.5  345.52  4969.7   345.8  4978.4  342.37
  4983.5  341.75  4984.5  339.24    4985  338.74  4996.5  339.24  4998.2  345.35
  5088.7  344.82  5115.7   345.1  5121.8  346.28  5131.1  345.76  5156.6  346.72
  5209.6  346.82  5251.4  348.51  5297.5  348.59    5408  351.01    5669   351.4
  5857.8  352.79  5877.8  352.15  5921.5  353.42  5966.7  353.64  6044.9  354.59
#Mann= 9 ,-1 , 0
  4430.7     .07       0  4747.9     .12       0  4950.5      .1       0
  4984.5     .05       0  4996.5      .1       0  5131.1     .12       0
  5156.6     .05       0  5921.5    .035       0  5966.7     .05       0
Bank Sta=4984.5,4996.5
XS Rating Curve= 0 ,0
Exp/Cntr=0.3,0.1

Type RM Length L Ch R = 1 ,12877   ,466,466,466
BEGIN DESCRIPTION:
YOW BRANCH 28.0
END DESCRIPTION:
XS GIS Cut Line= 3
      2389975.02     13691025.01        2389525.       13690825.
        2388525.       13690525.
#Sta/Elev= 30
  4507.9  353.43  4812.9  348.69    4880  348.68  4939.5  342.84  4978.5  343.15
  4985.5   338.1    4986   337.6  4997.5   338.1    5003  338.25  5010.8  342.06
  5016.9  341.48  5031.7  343.89    5166  344.81  5233.4  346.31  5271.8  347.06
  5291.8  345.35    5297  347.42  5313.6  345.77  5330.6   347.3  5363.2  346.48
  5511.9  349.68    5572  347.85  5577.2  349.13  5595.5  347.98  5652.5  349.23
  5754.4  349.15  5912.1  351.76  5950.4  352.34  5971.3  354.65  6044.4  355.02
#Mann= 10 ,-1 , 0
  4507.9     .07       0  4812.9      .1       0  4985.5     .05       0
  4997.5      .1       0    5166     .12       0  5233.4     .07       0
  5330.6     .12       0  5652.5    .035       0  5754.4     .07       0
  5912.1     .05       0
Bank Sta=4985.5,4997.5
XS Rating Curve= 0 ,0
Exp/Cntr=0.3,0.1

Type RM Length L Ch R = 1 ,12411   ,446,446,446
BEGIN DESCRIPTION:
YOW BRANCH 27.0
END DESCRIPTION:
XS GIS Cut Line= 3
      2390224.97     13690674.99        2389425.       13690425.
      2388875.02     13689925.02
#Sta/Elev= 30
  4167.1  358.56  4301.1     353    4408  350.07  4676.5  347.68  4879.5  345.26
  4931.9  342.66  4942.4  341.33  4951.3  336.95  4956.5  339.05  4963.3  337.06
  4973.8  337.01  4983.7  339.33  4996.6  335.92  4997.1  335.42  5008.6  335.92
  5040.7  338.69  5047.5  337.14  5054.9   341.5  5061.6  341.51  5069.1  343.44
  5125.2  345.66  5231.9  347.43  5309.6  346.49  5344.8  345.41  5373.2  341.75
  5401.5  343.38  5415.7  345.94  5558.4  348.26    5688  350.73  5748.5  352.37
#Mann= 8 ,-1 , 0
  4167.1    .035       0  4301.1     .07       0  4676.5      .1       0
  4996.6     .05       0  5008.6      .1       0  5125.2     .12       0
  5558.4    .035       0    5688     .07       0
Bank Sta=4996.6,5008.6
XS Rating Curve= 0 ,0
Exp/Cntr=0.3,0.1

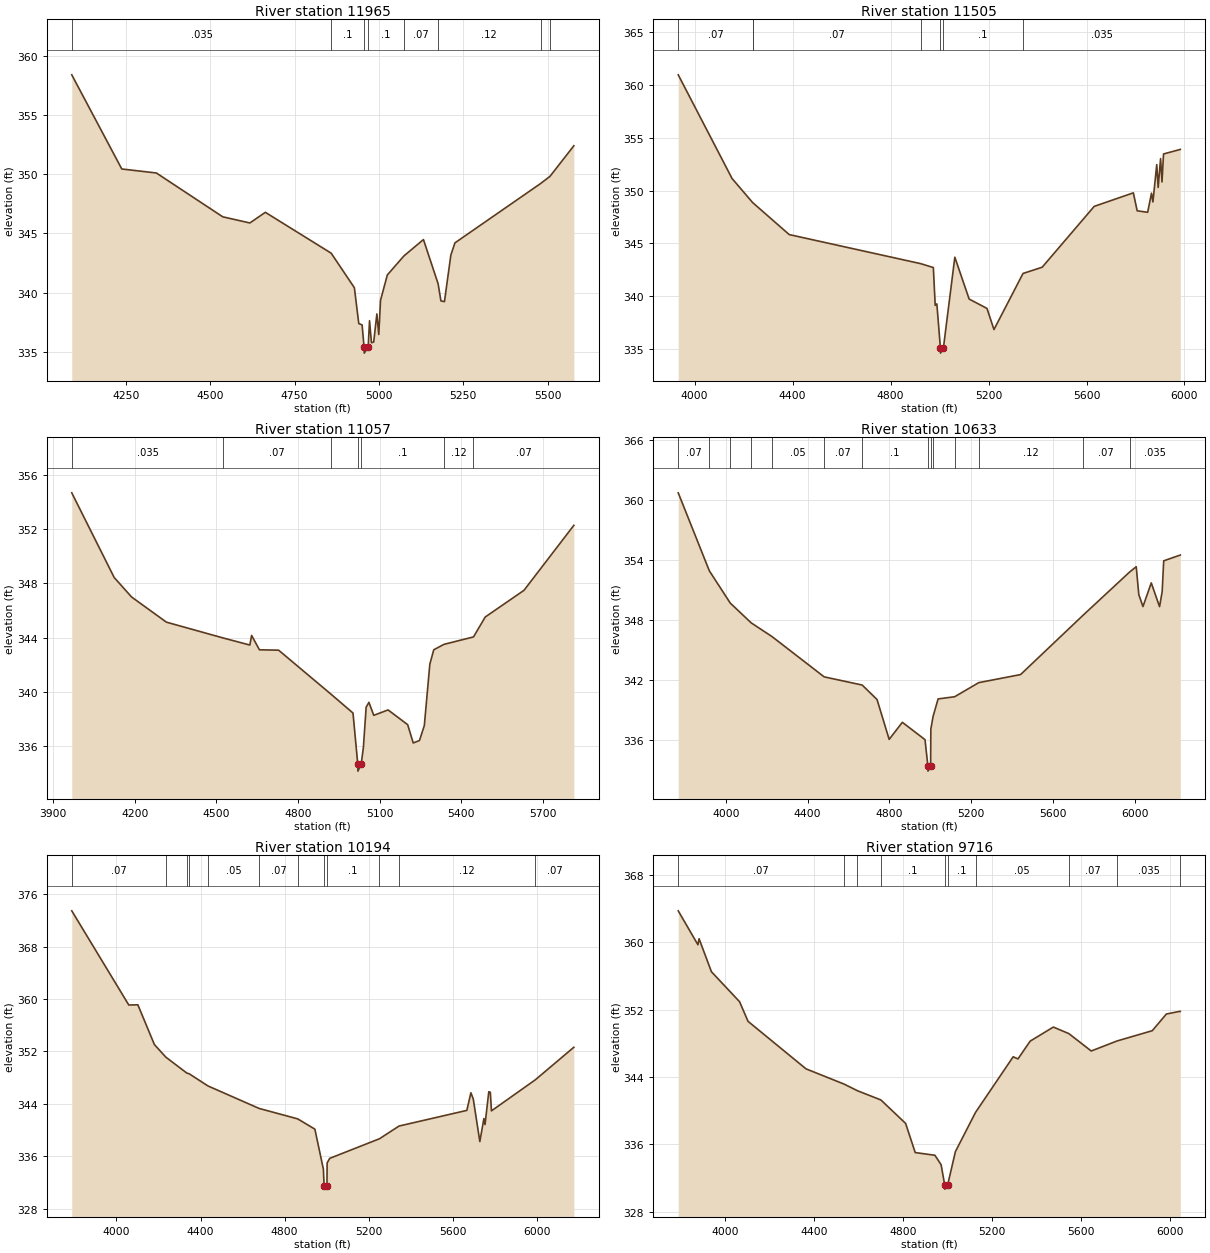
Type RM Length L Ch R = 1 ,11965   ,460,460,460
BEGIN DESCRIPTION:
YOW BRANCH 26.0
END DESCRIPTION:
XS GIS Cut Line= 3
        2390275.       13690475.        2389475.       13690025.
      2388924.97     13689874.99
#Sta/Elev= 30
  4089.8  358.39    4238  350.44  4340.6   350.1  4537.3   346.4  4617.6  345.88
  4663.5  346.78  4858.6  343.33  4927.4  340.41  4940.4  337.39  4950.3  337.27
  4956.1  335.39  4956.6  334.89  4968.2  335.39  4972.3  337.63    4978  335.77
  4984.7  335.83    4994   338.2  4999.7  336.46  5004.8  339.34    5025  341.49
  5074.3   343.1  5132.1  344.48  5175.5  340.75  5183.9   339.3  5194.3  339.24
  5213.3  343.17  5225.4   344.2  5479.2  349.21  5507.2  349.82  5577.8   352.4
#Mann= 8 ,-1 , 0
  4089.8    .035       0  4858.6      .1       0  4956.1     .05       0
  4968.2      .1       0  5074.3     .07       0  5175.5     .12       0
  5479.2    .035       0  5507.2     .05       0
Bank Sta=4956.1,4968.2
XS Rating Curve= 0 ,0
Exp/Cntr=0.3,0.1

Type RM Length L Ch R = 1 ,11505   ,448,448,448
BEGIN DESCRIPTION:
YOW BRANCH 25.0
END DESCRIPTION:
XS GIS Cut Line= 3
      2390424.97     13690324.97        2389625.       13689625.
      2388776.11      13689121.6
#Sta/Elev= 30
  3933.1  360.96  4152.8  351.15  4237.2  348.86  4238.9  348.83  4386.3  345.84
  4922.8  343.09  4974.7  342.72  4982.3  339.14    4989  339.28  5003.5  335.12
    5004  334.62  5015.8  335.12  5062.4   343.7  5120.8  339.74  5193.7  338.85
  5222.2  336.85  5340.8  342.16    5419  342.75  5631.5  348.51  5791.3  349.79
  5806.9  348.09  5849.7  347.95  5865.4  349.76  5871.2  348.93  5886.8  352.46
  5892.6   350.3  5902.4  353.03  5908.2  350.82  5914.5  353.47    5983   353.9
#Mann= 7 ,-1 , 0
  3933.1     .07       0  4237.2    .035       0  4238.9     .07       0
  4922.8      .1       0  5003.5     .05       0  5015.8      .1       0
  5340.8    .035       0
Bank Sta=5003.5,5015.8
XS Rating Curve= 0 ,0
Exp/Cntr=0.3,0.1

Type RM Length L Ch R = 1 ,11057   ,424,424,424
BEGIN DESCRIPTION:
YOW BRANCH 24.0
END DESCRIPTION:
XS GIS Cut Line= 3
      2390424.97     13690024.96        2389775.       13689225.
      2388974.97     13689074.99
#Sta/Elev= 30
    3969  354.69  4124.8  348.44  4188.7     347  4316.8  345.14  4525.7  343.97
  4623.3  343.45  4629.8  344.16  4658.5   343.1  4729.1  343.07    4921  339.83
  5002.3  338.43  5019.9  334.64  5020.4  334.14  5032.2  334.64  5040.4  335.88
  5050.6  338.86  5060.8  339.22  5078.6  338.26  5131.1  338.66  5203.2  337.57
  5223.6  336.22  5246.5   336.4  5264.3   337.5  5284.6  342.04    5299   343.1
  5336.4   343.5    5445  344.05  5488.1  345.52  5630.5  347.49  5813.7  352.29
#Mann= 7 ,-1 , 0
    3969    .035       0  4525.7     .07       0    4921      .1       0
  5019.9     .05       0  5032.2      .1       0  5336.4     .12       0
    5445     .07       0
Bank Sta=5019.9,5032.2
XS Rating Curve= 0 ,0
Exp/Cntr=0.3,0.1

Type RM Length L Ch R = 1 ,10633   ,439,439,439
BEGIN DESCRIPTION:
YOW BRANCH 23.0
END DESCRIPTION:
XS GIS Cut Line= 3
        2391075.       13688575.        2389875.       13688875.
      2388674.99       13689075.
#Sta/Elev= 30
  3767.7  360.71  3919.7   352.9  4021.9  349.67  4124.1  347.69  4226.3  346.31
  4480.8  342.28  4666.7  341.46  4739.2  340.01  4798.5  336.02  4862.9  337.73
  4973.7  335.99  4987.7  333.34  4988.2  332.84    5001  333.34  5002.1  337.05
  5013.2  338.33  5037.6  340.07  5118.6  340.29  5236.1   341.7  5440.6  342.51
    5745  348.43  5972.9  352.77  6005.8  353.31  6018.4  350.52  6038.7  349.32
  6079.3  351.69  6119.8  349.31  6132.5  350.81  6140.1   353.9  6221.2  354.48
#Mann= 14 ,-1 , 0
  3767.7     .07       0  3919.7    .035       0  4021.9     .05       0
  4124.1     .07       0  4226.3     .05       0  4480.8     .07       0
  4666.7      .1       0  4987.7     .05       0    5001      .1       0
  5013.2     .12       0  5118.6      .1       0  5236.1     .12       0
    5745     .07       0  5972.9    .035       0
Bank Sta=4987.7,5001
XS Rating Curve= 0 ,0
Exp/Cntr=0.3,0.1

Type RM Length L Ch R = 1 ,10194   ,478,478,478
BEGIN DESCRIPTION:
YOW BRANCH 22.0
END DESCRIPTION:
XS GIS Cut Line= 3
      2391275.05     13688374.99        2390075.       13688575.
      2388974.97     13688975.01
#Sta/Elev= 30
  3787.7  373.45  4058.9  359.07    4102   359.1  4180.6  353.03    4235  351.11
  4335.2  348.67  4344.9  348.59  4435.5  346.71  4678.4  343.28  4861.5  341.69
  4943.5  340.12    4984  334.01  4987.5  331.46    4988  330.96  5000.9  331.46
  5001.8  334.96  5014.3  335.66  5250.6  338.65  5343.6  340.59    5666  342.98
  5685.3  345.67  5696.6  344.73  5727.9  338.22  5747.1  341.74  5752.5  340.81
  5770.4  345.83  5777.7  345.75  5783.1  342.91  5991.6  347.65  6174.8  352.62
#Mann= 12 ,-1 , 0
  3787.7     .07       0    4235    .035       0  4335.2     .05       0
  4344.9     .07       0  4435.5     .05       0  4678.4     .07       0
  4861.5      .1       0  4987.5     .05       0  5000.9      .1       0
  5250.6     .07       0  5343.6     .12       0  5991.6     .07       0
Bank Sta=4987.5,5000.9
XS Rating Curve= 0 ,0
Exp/Cntr=0.3,0.1

Type RM Length L Ch R = 1 ,9716    ,455,455,455
BEGIN DESCRIPTION:
YOW BRANCH 21.0
END DESCRIPTION:
XS GIS Cut Line= 3
      2391074.99       13687975.        2389875.       13688175.
      2388874.97     13688475.01
#Sta/Elev= 30
  3787.9  363.73  3876.6   359.7  3881.7  360.42  3937.4   356.5  4064.1  352.94
  4102.2  350.61  4363.2  344.97  4534.6  343.16  4594.9  342.37  4700.2  341.28
  4811.8  338.49  4854.9  335.03  4943.6  334.71  4971.5  333.59  4987.6  331.19
  4988.1  330.69    5001  331.19  5035.8  335.14  5126.5   339.8  5295.9   346.4
  5317.6  346.15  5372.5  348.26  5476.9  349.93  5546.9  349.15  5647.4  347.09
  5763.8  348.28  5922.3   349.5  5985.8  351.48  6047.2   351.8  6048.5  351.79
#Mann= 10 ,-1 , 0
  3787.9     .07       0  4534.6     .12       0  4594.9     .07       0
  4700.2      .1       0  4987.6     .05       0    5001      .1       0
  5126.5     .05       0  5546.9     .07       0  5763.8    .035       0
  6047.2     .07       0
Bank Sta=4987.6,5001
XS Rating Curve= 0 ,0
Exp/Cntr=0.3,0.1

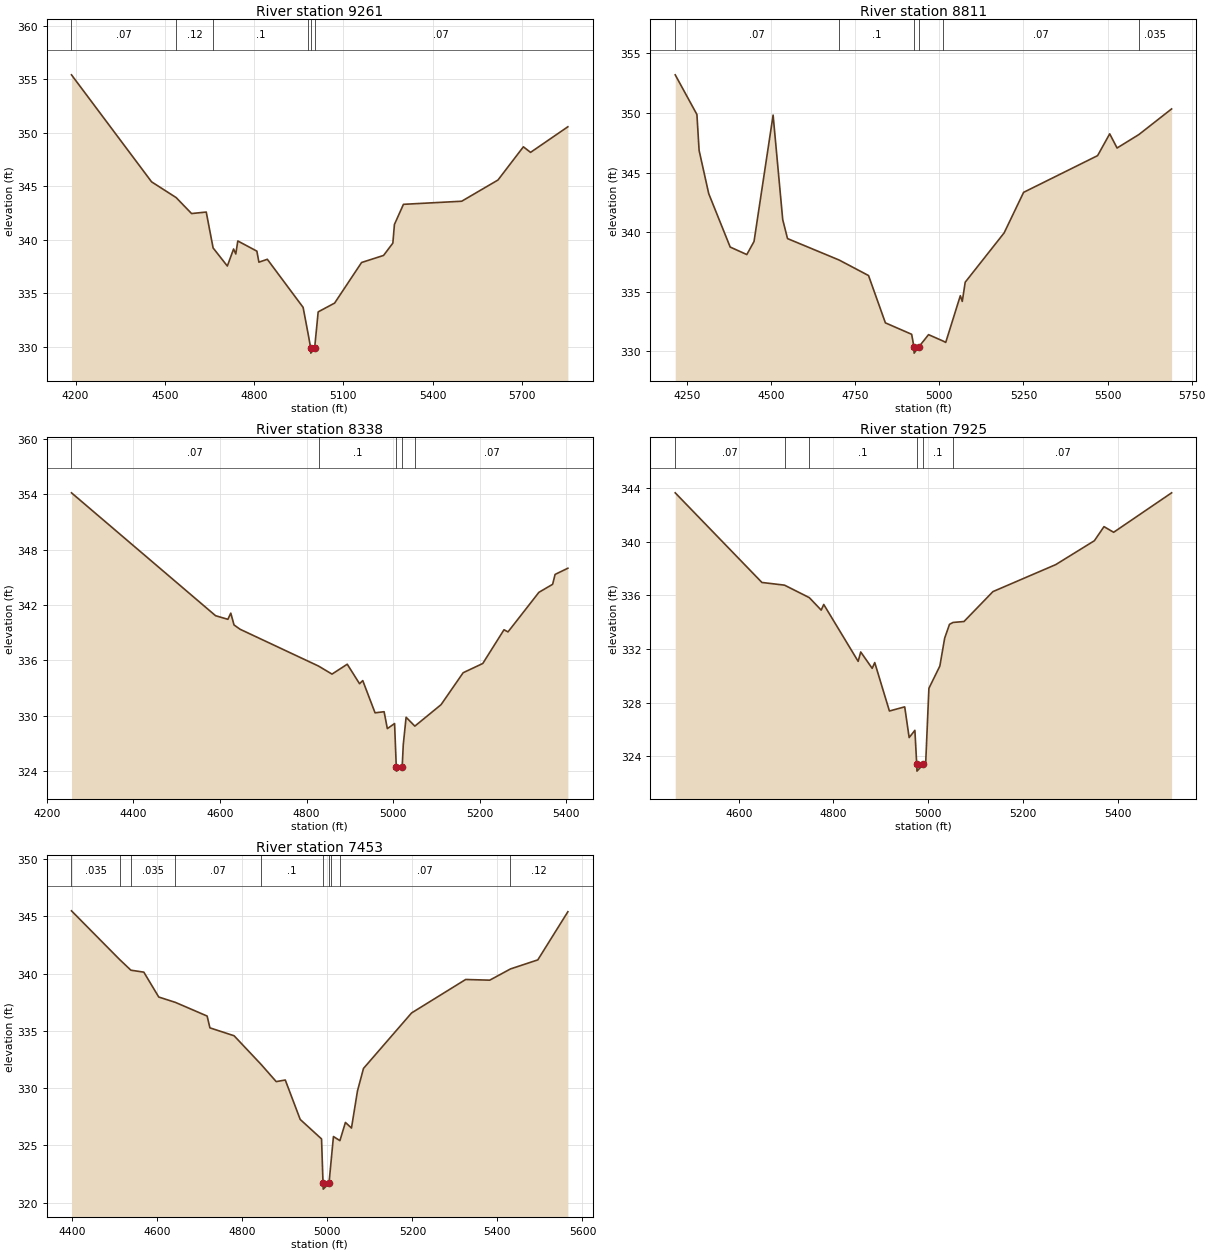
Type RM Length L Ch R = 1 ,9261    ,450,450,450
BEGIN DESCRIPTION:
YOW BRANCH 20.0
END DESCRIPTION:
XS GIS Cut Line= 3
        2390325.       13687225.        2389725.       13687775.
      2388925.04     13688074.98
#Sta/Elev= 30
  4186.1   355.4  4455.3  345.41  4537.9  343.94  4589.7  342.45    4639  342.59
  4662.1  339.24  4709.9  337.55  4730.9  339.14  4738.3  338.68  4745.1  339.89
  4809.2  338.94    4816  337.91  4844.3  338.18  4964.6  333.69  4982.6  331.05
  4989.9  329.92  4990.4  329.42  5003.4  329.92  5015.2  333.27  5070.4  334.09
  5161.1  337.88    5235  338.54  5266.2  339.69  5271.5  341.43  5301.8  343.31
  5497.6   343.6  5619.5  345.58  5704.9  348.68    5729  348.16  5854.4  350.55
#Mann= 6 ,-1 , 0
  4186.1     .07       0  4537.9     .12       0  4662.1      .1       0
  4982.6     .07       0  4989.9     .05       0  5003.4     .07       0
Bank Sta=4989.9,5003.4
XS Rating Curve= 0 ,0
Exp/Cntr=0.3,0.1

Type RM Length L Ch R = 1 ,8811    ,473,473,473
BEGIN DESCRIPTION:
YOW BRANCH 19.0
END DESCRIPTION:
XS GIS Cut Line= 3
      2390075.02     13686924.99        2389475.       13687425.
      2388874.97     13687775.02
#Sta/Elev= 30
  4214.7   353.2  4279.2  349.87  4285.7  346.86  4314.3  343.23  4378.1  338.75
  4427.5  338.12    4449  339.22  4505.7  349.82  4534.3  341.05  4548.6  339.46
  4702.1  337.66  4789.4  336.36  4839.5  332.39  4917.6  331.43  4924.5  330.35
    4925  329.85  4938.2  330.35  4967.8   331.4  5010.6  330.87  5018.9  330.75
  5062.3  334.67  5068.1  334.19  5076.8   335.8  5192.6  339.94  5250.4  343.34
  5470.4  346.42  5506.4  348.25  5528.3  347.06  5593.2  348.19  5690.4  350.34
#Mann= 6 ,-1 , 0
  4214.7     .07       0  4702.1      .1       0  4924.5     .05       0
  4938.2      .1       0  5010.6     .07       0  5593.2    .035       0
Bank Sta=4924.5,4938.2
XS Rating Curve= 0 ,0
Exp/Cntr=0.3,0.1

Type RM Length L Ch R = 1 ,8338    ,413,413,413
BEGIN DESCRIPTION:
YOW BRANCH 18.0
END DESCRIPTION:
XS GIS Cut Line= 3
      2389925.01     13686524.99        2389375.       13687025.
      2389175.01     13687374.98
#Sta/Elev= 30
  4256.9  354.14  4589.7  340.84  4618.1  340.45  4624.8  341.12  4632.3  339.84
  4646.5  339.37  4827.5  335.39  4858.6  334.52  4893.8  335.59  4922.2  333.48
  4929.6  333.82    4958  330.33  4978.9  330.45  4986.4  328.62  5003.1  329.17
    5007  324.52  5007.5  324.02  5020.7  324.52  5023.2   326.9  5029.7  329.85
  5049.9  328.89  5110.4  331.21  5161.5  334.67  5206.8  335.67  5255.8  339.32
  5265.1  339.09  5336.4  343.37  5368.1  344.24  5373.8  345.31  5403.3  345.98
#Mann= 5 ,-1 , 0
  4256.9     .07       0  4827.5      .1       0    5007     .05       0
  5020.7      .1       0  5049.9     .07       0
Bank Sta=5007,5020.7
XS Rating Curve= 0 ,0
Exp/Cntr=0.3,0.1

Type RM Length L Ch R = 1 ,7925    ,472,472,472
BEGIN DESCRIPTION:
YOW BRANCH 17.0
END DESCRIPTION:
XS GIS Cut Line= 3
        2389625.       13686525.        2389125.       13686725.
        2389025.     13687224.98
#Sta/Elev= 30
  4465.8  343.64  4648.9  336.96  4696.6  336.76    4749  335.83  4774.1   334.9
  4779.5  335.32  4852.2  331.08  4857.6  331.78  4881.8  330.56  4887.2  330.99
  4918.2  327.38  4950.5  327.69  4959.9   325.4    4972  325.94  4975.9   323.4
  4976.4   322.9  4989.7   323.4  4994.9  323.58  5001.6  329.07  5024.7  330.73
  5034.9  332.81  5045.1  333.84  5052.6  333.98  5075.7  334.05  5136.9  336.28
  5269.5  338.29  5351.1  340.07  5371.4  341.12  5391.8   340.7  5514.2  343.64
#Mann= 6 ,-1 , 0
  4465.8     .07       0  4696.6     .12       0    4749      .1       0
  4975.9     .05       0  4989.7      .1       0  5052.6     .07       0
Bank Sta=4975.9,4989.7
XS Rating Curve= 0 ,0
Exp/Cntr=0.3,0.1

Type RM Length L Ch R = 1 ,7453    ,470,470,470
BEGIN DESCRIPTION:
YOW BRANCH 16.0
END DESCRIPTION:
XS GIS Cut Line= 3
      2389325.03     13685874.97        2388925.       13686325.
        2388525.       13686725.
#Sta/Elev= 30
  4397.9  345.47  4511.2  341.22  4537.7  340.29  4568.1  340.12  4603.2  337.95
  4642.5  337.48    4717  336.29  4723.6  335.26  4780.5  334.57    4844  332.07
  4879.6  330.57  4900.9  330.71    4936  327.27  4986.2  325.57  4989.7  321.69
  4990.2  321.19  5003.7  321.69  5008.5  323.56  5014.2  325.78  5029.4  325.42
  5042.4  327.01  5056.6  326.52  5070.7  329.75  5084.9  331.72    5198  336.56
  5325.3  339.48  5381.9  339.42  5430.7   340.4    5495  341.19  5565.7  345.39
#Mann= 10 ,-1 , 0
  4397.9    .035       0  4511.2     .07       0  4537.7    .035       0
  4642.5     .07       0    4844      .1       0  4989.7     .05       0
  5003.7      .1       0  5008.5     .12       0  5029.4     .07       0
  5430.7     .12       0
Bank Sta=4989.7,5003.7
XS Rating Curve= 0 ,0
Exp/Cntr=0.3,0.1