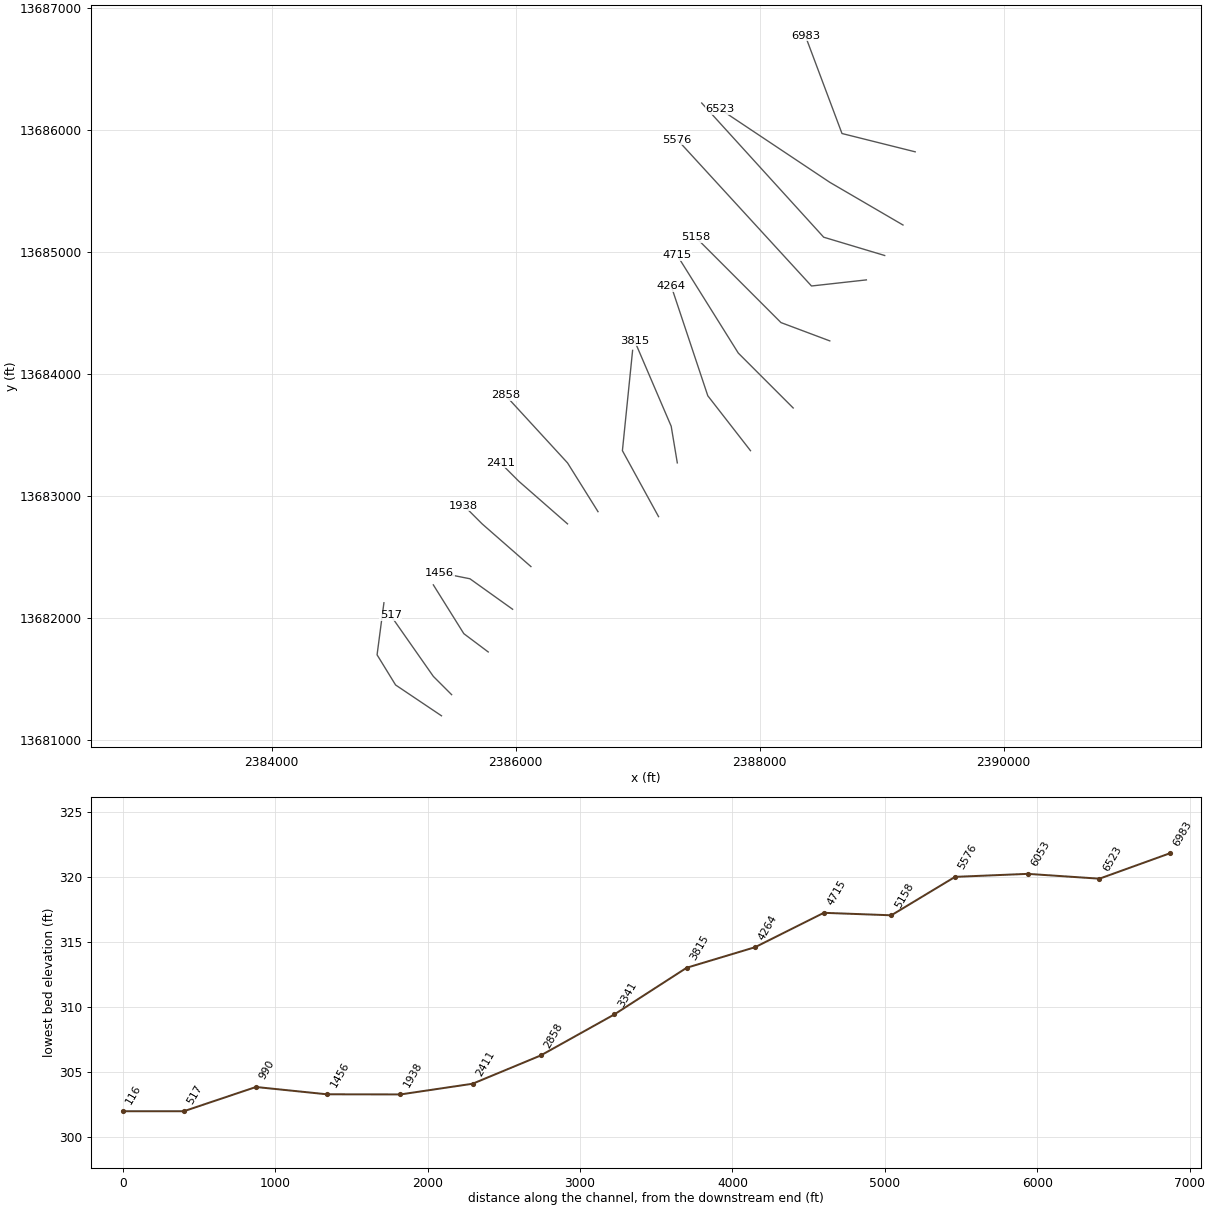
HEC-RAS study YOW BRANCH.prj: YOW BRANCH Base Level Engineering

--- YOW BRANCH.g01 (geometry) --- (continued)

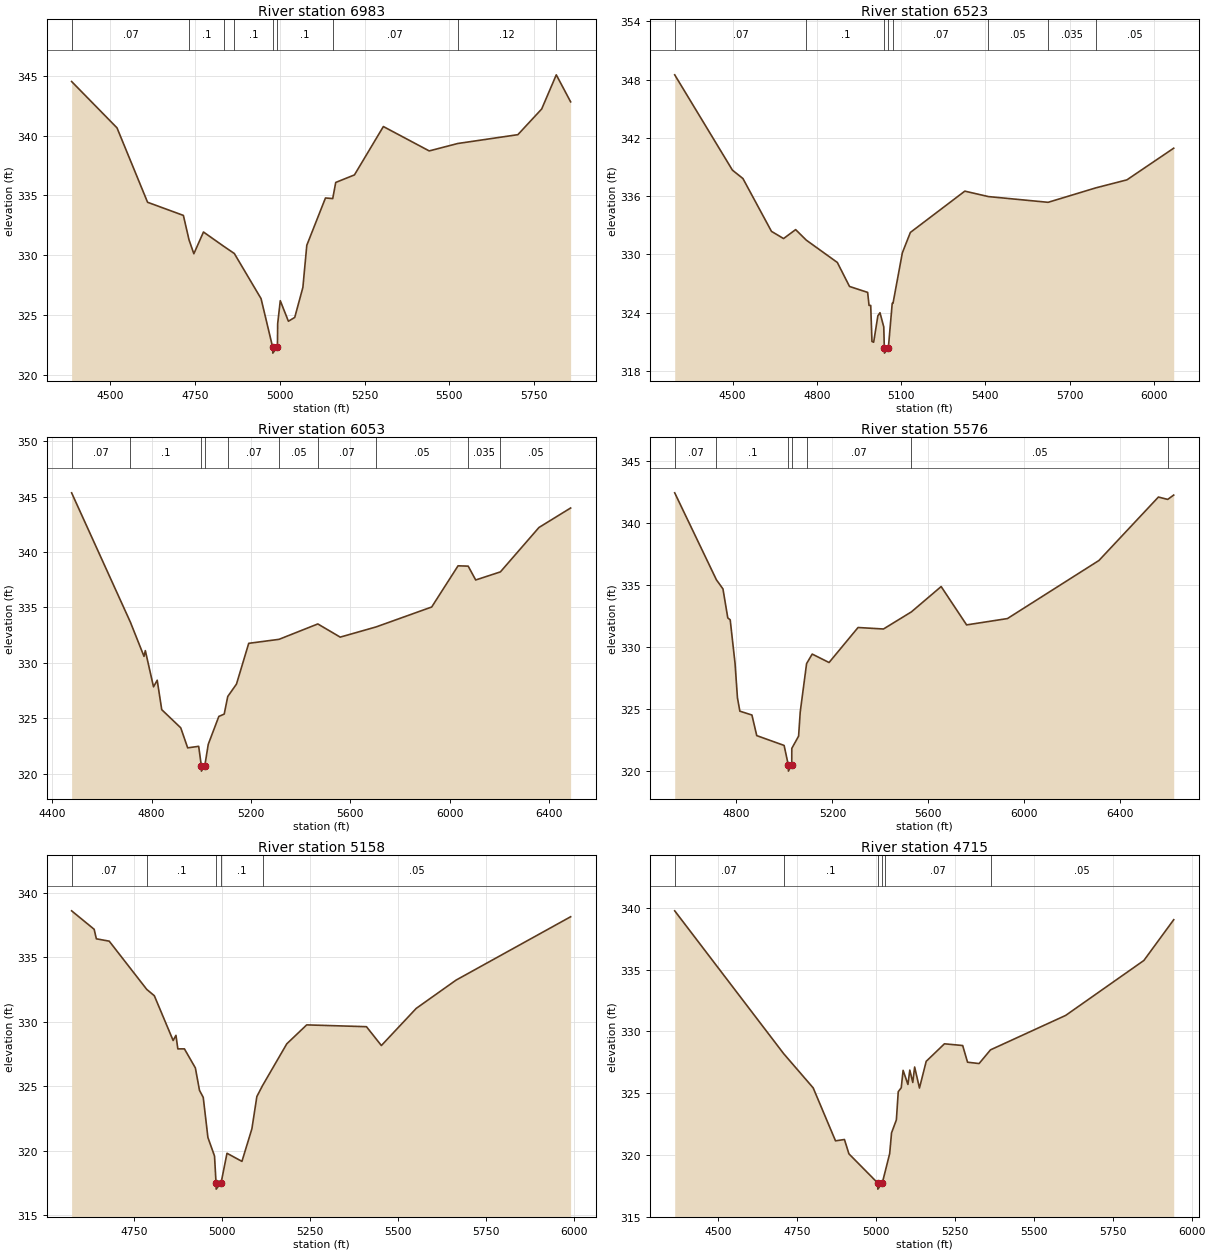
Type RM Length L Ch R = 1 ,6983    ,460,460,460
BEGIN DESCRIPTION:
YOW BRANCH 15.0
END DESCRIPTION:
XS GIS Cut Line= 3
      2389275.04     13685824.99        2388675.       13685975.
        2388375.     13686774.99
#Sta/Elev= 30
  4385.3  344.53  4519.3  340.65  4609.5  334.42  4715.2  333.32  4731.8  331.28
  4746.1  330.11  4774.5  331.93    4834  330.74  4865.6  330.13  4944.5  326.35
  4978.7  322.29  4979.2  321.79  4992.8  322.29  4993.5  324.25  5001.2  326.18
  5025.2  324.46  5043.9  324.78  5067.9  327.29  5079.5  330.82  5134.6  334.78
    5156  334.73  5164.9  336.08  5220.1  336.71  5305.5  340.76  5440.8  338.72
    5525  339.34  5702.5  340.08  5772.8  342.23  5815.9  345.09  5858.2  342.83
#Mann= 9 ,-1 , 0
  4385.3     .07       0  4731.8      .1       0    4834    .035       0
  4865.6      .1       0  4978.7     .05       0  4992.8      .1       0
    5156     .07       0    5525     .12       0  5815.9     .07       0
Bank Sta=4978.7,4992.8
XS Rating Curve= 0 ,0
Exp/Cntr=0.3,0.1

Type RM Length L Ch R = 1 ,6523    ,470,470,470
BEGIN DESCRIPTION:
YOW BRANCH 14.0
END DESCRIPTION:
XS GIS Cut Line= 3
      2389175.04     13685224.98        2388575.       13685575.
      2387675.03     13686174.98
#Sta/Elev= 30
  4294.1  348.49  4499.6  338.68  4536.9  337.82  4638.6  332.38  4681.6  331.64
  4724.6  332.56  4762.4  331.48    4873  329.18  4916.4  326.71  4980.9   326.1
  4985.9  324.76  4991.8  324.76  4996.3  321.05  5002.3  320.97  5017.3  323.69
  5024.8  324.01  5038.3  322.55  5040.3  320.35  5040.8  319.85  5054.5  320.35
  5068.4  324.98  5071.2  324.98  5104.4  330.17    5133  332.27  5326.8  336.52
  5410.8  335.96  5623.3  335.37  5793.5  336.86  5903.7  337.68  6070.4  340.94
#Mann= 8 ,-1 , 0
  4294.1     .07       0  4762.4      .1       0  5040.3     .05       0
  5054.5      .1       0  5071.2     .07       0  5410.8     .05       0
  5623.3    .035       0  5793.5     .05       0
Bank Sta=5040.3,5054.5
XS Rating Curve= 0 ,0
Exp/Cntr=0.3,0.1

Type RM Length L Ch R = 1 ,6053    ,477,477,477
BEGIN DESCRIPTION:
YOW BRANCH 13.0
END DESCRIPTION:
XS GIS Cut Line= 3
      2389024.97     13684975.01        2388525.       13685125.
        2387525.       13686225.
#Sta/Elev= 30
  4477.9  345.35  4714.7  333.66  4769.3  330.58  4774.6   331.1  4807.6  327.83
  4822.4  328.43  4840.7  325.77  4917.2  324.13  4945.1  322.32  4989.4  322.46
  4999.9  320.72  5000.4  320.22  5014.1  320.72  5027.9  322.64  5070.5  325.16
  5092.1  325.37  5106.4  326.96  5141.5  328.08  5190.8  331.76  5312.7  332.12
  5468.9  333.51  5559.1  332.32  5703.3  333.24  5927.3  335.04  6033.4  338.76
  6074.2  338.73  6104.4  337.48  6203.8  338.21  6359.1  342.22  6486.5  343.98
#Mann= 10 ,-1 , 0
  4477.9     .07       0  4714.7      .1       0  4999.9     .05       0
  5014.1      .1       0  5106.4     .07       0  5312.7     .05       0
  5468.9     .07       0  5703.3     .05       0  6074.2    .035       0
  6203.8     .05       0
Bank Sta=4999.9,5014.1
XS Rating Curve= 0 ,0
Exp/Cntr=0.3,0.1

Type RM Length L Ch R = 1 ,5576    ,418,418,418
BEGIN DESCRIPTION:
YOW BRANCH 12.0
END DESCRIPTION:
XS GIS Cut Line= 3
      2388875.02       13684775.        2388425.       13684725.
      2387324.98     13685925.02
#Sta/Elev= 30
  4542.5  342.41  4716.5   335.4  4743.7  334.67  4763.9  332.33  4773.9  332.18
  4794.1  328.67  4804.1   325.9  4814.2  324.82  4864.5  324.51  4884.6  322.85
  4998.7  322.06  5016.1  320.49  5016.6  319.99  5030.5  320.49  5030.7  321.82
  5059.1  322.81  5065.9  324.76  5092.4  328.65  5115.8  329.42  5186.1  328.74
    5307  331.56    5413  331.44  5529.5  332.82  5653.5  334.86  5759.6  331.77
  5929.8  332.28  6311.5  336.96  6559.4  342.07  6598.1  341.88  6623.2  342.23
#Mann= 7 ,-1 , 0
  4542.5     .07       0  4716.5      .1       0  5016.1     .05       0
  5030.5      .1       0  5092.4     .07       0  5529.5     .05       0
  6598.1    .035       0
Bank Sta=5016.1,5030.5
XS Rating Curve= 0 ,0
Exp/Cntr=0.3,0.1

Type RM Length L Ch R = 1 ,5158    ,443,443,443
BEGIN DESCRIPTION:
YOW BRANCH 11.0
END DESCRIPTION:
XS GIS Cut Line= 3
      2388574.95     13684275.02        2388175.       13684425.
        2387475.       13685125.
#Sta/Elev= 30
  4573.1  338.61  4637.1  337.18  4643.4  336.44  4679.9  336.26  4786.5  332.52
    4808  332.03  4861.4  328.56  4869.4  328.96  4874.8  327.91  4893.5  327.91
  4924.6  326.43  4936.2   324.7  4946.9  324.15  4960.2  321.04  4978.9  319.61
  4983.2  317.54  4983.7  317.04  4997.7  317.54  5014.4  319.82  5056.8  319.19
  5085.1  321.72  5099.2  324.22  5115.2  325.06  5184.1   328.3  5240.7  329.77
  5410.4  329.63  5452.8  328.17  5551.8  331.05  5664.9  333.24  5990.2  338.15
#Mann= 5 ,-1 , 0
  4573.1     .07       0  4786.5      .1       0  4983.2     .05       0
  4997.7      .1       0  5115.2     .05       0
Bank Sta=4983.2,4997.7
XS Rating Curve= 0 ,0
Exp/Cntr=0.3,0.1

Type RM Length L Ch R = 1 ,4715    ,451,451,451
BEGIN DESCRIPTION:
YOW BRANCH 10.0
END DESCRIPTION:
XS GIS Cut Line= 3
      2388274.99     13683725.01        2387825.       13684175.
      2387324.99     13684975.02
#Sta/Elev= 30
  4363.4  339.77  4708.4   328.2  4801.8  325.43  4872.5  321.14  4900.8  321.25
  4914.9  320.09    5006  317.73  5006.5  317.23  5020.6  317.73  5028.8  318.56
    5044  320.11  5049.9  321.79  5065.2  322.84  5071.1  325.12  5080.6  325.44
  5086.5  326.85  5101.8  325.71  5107.7  326.87  5117.1  325.87    5123  327.12
  5138.3  325.42  5159.6  327.58  5217.4     329  5275.1  328.86  5290.5  327.51
    5327   327.4  5363.2  328.51  5601.2   331.3  5848.8  335.75  5943.2  339.05
#Mann= 6 ,-1 , 0
  4363.4     .07       0  4708.4      .1       0    5006     .05       0
  5020.6      .1       0  5028.8     .07       0  5363.2     .05       0
Bank Sta=5006,5020.6
XS Rating Curve= 0 ,0
Exp/Cntr=0.3,0.1

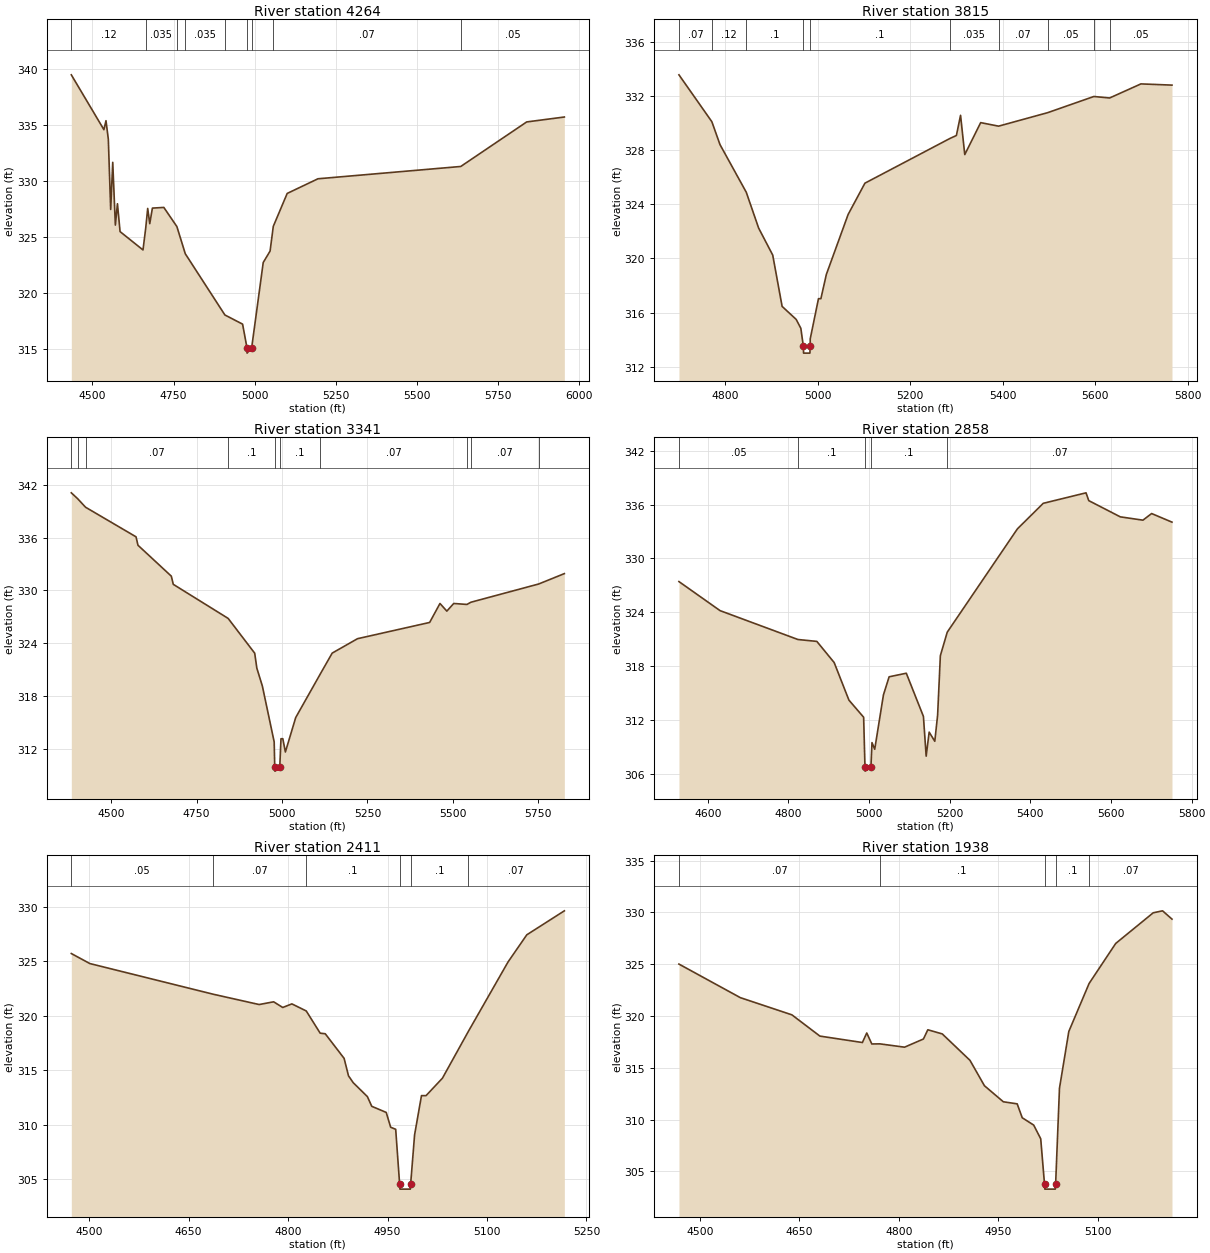
Type RM Length L Ch R = 1 ,4264    ,449,449,449
BEGIN DESCRIPTION:
YOW BRANCH 9.0
END DESCRIPTION:
XS GIS Cut Line= 3
        2387925.       13683375.        2387575.       13683825.
      2387274.99     13684725.03
#Sta/Elev= 30
  4435.1  339.46  4535.5  334.56  4541.9  335.36  4549.1  333.71  4556.4  327.43
  4562.7  331.64  4570.8  326.03  4577.2  327.94  4585.3  325.45  4655.9  323.81
  4664.2  325.74  4670.4  327.52  4676.7  326.16  4684.9  327.55  4720.1  327.61
  4760.3   325.9  4786.2  323.47  4908.2     318  4962.7  317.18  4976.1  315.09
  4976.6  314.59  4990.8  315.09  5026.3  322.69  5047.4  323.71  5057.3  325.92
  5100.1  328.86  5194.9  330.17  5634.8  331.27  5837.9  335.25  5953.9  335.69
#Mann= 9 ,-1 , 0
  4435.1     .12       0  4664.2    .035       0  4760.3     .12       0
  4786.2    .035       0  4908.2      .1       0  4976.1     .05       0
  4990.8      .1       0  5057.3     .07       0  5634.8     .05       0
Bank Sta=4976.1,4990.8
XS Rating Curve= 0 ,0
Exp/Cntr=0.3,0.1

Type RM Length L Ch R = 1 ,3815    ,474,474,474
BEGIN DESCRIPTION:
YOW BRANCH 8.0
END DESCRIPTION:
XS GIS Cut Line= 3
      2387324.99     13683275.04        2387275.       13683575.
      2386974.99     13684275.02
#Sta/Elev= 30
  4699.9  333.56    4771   330.1  4788.6  328.41  4845.4  324.89  4872.2  322.24
  4902.6  320.25  4922.9  316.46  4953.3   315.5  4963.4  314.84  4968.8  313.51
  4969.3  313.01    4983  313.01  4983.5  313.51  4983.7  314.07  5001.5  317.03
  5006.7  317.03  5018.5  318.82  5065.6  323.25  5101.9  325.56    5285  328.85
  5299.6  329.08  5308.6  330.57  5317.7  327.67  5352.1  330.03  5390.8  329.77
  5497.3  330.77  5596.7  331.96  5630.8  331.85  5698.5  332.89  5765.6   332.8
#Mann= 10 ,-1 , 0
  4699.9     .07       0    4771     .12       0  4845.4      .1       0
  4968.8     .05       0  4983.5      .1       0    5285    .035       0
  5390.8     .07       0  5497.3     .05       0  5596.7     .07       0
  5630.8     .05       0
Bank Sta=4968.8,4983.5
XS Rating Curve= 0 ,0
Exp/Cntr=0.3,0.1

Type RM Length L Ch R = 1 ,3341    ,483,483,483
BEGIN DESCRIPTION:
YOW BRANCH 7.0
END DESCRIPTION:
XS GIS Cut Line= 3
      2387171.27     13682834.37        2386875.       13683375.
      2386958.59     13684197.17
#Sta/Elev= 30
  4383.2  341.12  4401.5  340.46  4424.9  339.48  4572.6  336.11  4578.3  335.15
  4675.9  331.63  4681.6   330.7  4842.2  326.82  4919.9  322.86  4926.2  321.15
  4942.3  319.12  4976.9  312.76  4978.5  309.93    4979  309.43  4993.3  309.93
  4996.8  313.12  5002.2  313.12  5009.7  311.61  5039.9  315.53  5112.1  320.51
  5146.7  322.87  5220.8  324.51  5431.9  326.36  5462.1  328.52  5482.2  327.65
  5502.3  328.52  5541.1  328.41  5552.5  328.66  5751.1  330.74  5826.1  331.92
#Mann= 10 ,-1 , 0
  4383.2     .07       0  4401.5     .05       0  4424.9     .07       0
  4842.2      .1       0  4978.5     .05       0  4993.3      .1       0
  5112.1     .07       0  5541.1    .035       0  5552.5     .07       0
  5751.1     .05       0
Bank Sta=4978.5,4993.3
XS Rating Curve= 0 ,0
Exp/Cntr=0.3,0.1

Type RM Length L Ch R = 1 ,2858    ,447,447,447
BEGIN DESCRIPTION:
YOW BRANCH 6.0
END DESCRIPTION:
XS GIS Cut Line= 3
        2386675.       13682875.        2386425.       13683275.
      2385916.92     13683828.31
#Sta/Elev= 30
  4528.3  327.42  4630.3  324.18  4823.4  320.96  4870.3  320.75  4913.3  318.39
  4949.9   314.2  4986.4  312.29  4989.7  306.78  4990.2  306.28  5004.5  306.78
  5007.1  309.46  5013.9  308.72  5035.5  314.78  5049.6   316.8  5092.2   317.2
  5134.7  312.38  5141.5  307.95  5148.9  310.63  5162.9  309.61  5169.9  312.53
  5176.7  319.16  5193.8  321.78  5367.8   333.3  5431.9  336.15    5538  337.32
  5544.8  336.45    5623  334.64  5679.2  334.27  5700.7  335.01  5751.2  334.05
#Mann= 5 ,-1 , 0
  4528.3     .05       0  4823.4      .1       0  4989.7     .05       0
  5004.5      .1       0  5193.8     .07       0
Bank Sta=4989.7,5004.5
XS Rating Curve= 0 ,0
Exp/Cntr=0.3,0.1

Type RM Length L Ch R = 1 ,2411    ,473,473,473
BEGIN DESCRIPTION:
YOW BRANCH 5.0
END DESCRIPTION:
XS GIS Cut Line= 3
      2386425.01     13682774.99        2386025.       13683125.
      2385874.97     13683275.03
#Sta/Elev= 30
    4473  325.73    4501  324.81  4686.8     322  4756.3  321.05  4778.2   321.3
  4791.9  320.78  4805.7  321.11  4827.4  320.46  4848.4  318.42    4856  318.37
  4884.5  316.11  4891.1  314.51  4898.2  313.88  4919.6   312.6  4926.2  311.71
    4948  311.15  4954.7  309.79  4962.3   309.6  4968.2  304.61  4968.7  304.11
  4984.4  304.11  4984.9  304.61  4990.8  309.09  5001.2  312.69  5008.1  312.69
  5032.8  314.29  5071.6  318.55  5131.8  324.96  5160.1  327.45  5216.7  329.65
#Mann= 6 ,-1 , 0
    4473     .05       0  4686.8     .07       0  4827.4      .1       0
  4968.2     .05       0  4984.9      .1       0  5071.6     .07       0
Bank Sta=4968.2,4984.9
XS Rating Curve= 0 ,0
Exp/Cntr=0.3,0.1

Type RM Length L Ch R = 1 ,1938    ,482,482,482
BEGIN DESCRIPTION:
YOW BRANCH 4.0
END DESCRIPTION:
XS GIS Cut Line= 3
      2386125.01     13682424.99        2385725.       13682775.
      2385574.97     13682925.03
#Sta/Elev= 30
  4468.4  325.01    4561  321.77  4638.8  320.11    4681  318.06  4745.1  317.44
  4751.7  318.36  4759.3   317.3  4771.5  317.31  4808.7  316.99  4837.2  317.78
  4843.8  318.67  4865.6  318.27  4907.4  315.72  4929.2  313.27  4957.7  311.72
  4978.6  311.52  4986.2  310.18  5003.5  309.47  5014.1  308.15  5019.8  303.79
  5020.3  303.29  5036.1  303.29  5036.6  303.79  5042.4  313.03  5056.5  318.51
  5087.1  323.14  5127.2     327  5183.8  329.96  5197.9  330.15  5212.1  329.35
#Mann= 5 ,-1 , 0
  4468.4     .07       0  4771.5      .1       0  5019.8     .05       0
  5036.6      .1       0  5087.1     .07       0
Bank Sta=5019.8,5036.6
XS Rating Curve= 0 ,0
Exp/Cntr=0.3,0.1

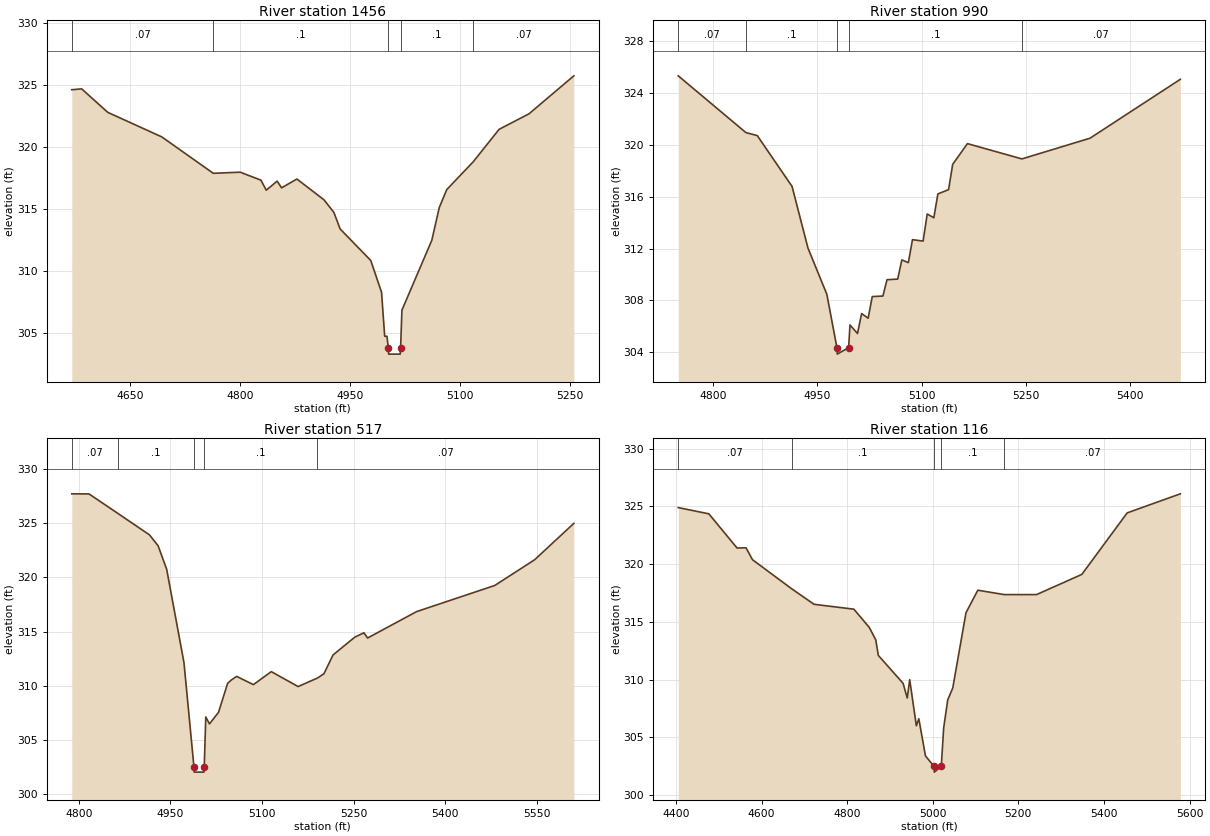
Type RM Length L Ch R = 1 ,1456    ,466,466,466
BEGIN DESCRIPTION:
YOW BRANCH 3.0
END DESCRIPTION:
XS GIS Cut Line= 3
      2385974.99     13682075.01        2385625.       13682325.
      2385374.96     13682375.01
#Sta/Elev= 30
    4570  324.59  4583.5  324.66  4619.1  322.77  4692.9  320.79  4763.1  317.86
  4799.8  317.95  4828.1  317.31  4835.4   316.5  4850.2  317.23  4856.3  316.69
  4877.2   317.4  4914.1  315.73  4927.6  314.72  4936.2  313.38    4978  310.84
  4992.7  308.28    4997  304.74  5000.1  304.74  5001.9   303.8  5002.4   303.3
  5018.2   303.3  5018.7   303.8  5020.5  306.84  5061.3  312.47  5071.5  315.11
  5081.7  316.55  5117.8  318.79  5153.1   321.4  5193.9  322.65  5255.1  325.71
#Mann= 5 ,-1 , 0
    4570     .07       0  4763.1      .1       0  5001.9     .05       0
  5018.7      .1       0  5117.8     .07       0
Bank Sta=5001.9,5018.7
XS Rating Curve= 0 ,0
Exp/Cntr=0.3,0.1

Type RM Length L Ch R = 1 ,990     ,473,473,473
BEGIN DESCRIPTION:
YOW BRANCH 2.0
END DESCRIPTION:
XS GIS Cut Line= 3
      2385775.01     13681724.99        2385575.       13681875.
      2385325.01     13682274.99
#Sta/Elev= 30
  4750.1  325.33  4847.4  320.95  4863.7  320.72  4913.7   316.8  4936.6  312.04
  4963.7  308.48  4978.2  304.36  4978.7  303.86    4995  304.36    4997  306.11
  5007.8  305.45  5013.7  306.99  5023.1  306.63    5029   308.3  5044.3  308.34
  5050.2   309.6  5065.6  309.65  5071.5  311.13  5080.9  310.92  5086.8  312.69
  5102.1  312.58    5108  314.67  5117.5  314.38  5123.3  316.22  5138.7  316.55
  5144.6   318.5  5165.8   320.1  5244.1  318.92  5342.1  320.52  5471.8  325.06
#Mann= 5 ,-1 , 0
  4750.1     .07       0  4847.4      .1       0  4978.2     .05       0
    4995      .1       0  5244.1     .07       0
Bank Sta=4978.2,4995
XS Rating Curve= 0 ,0
Exp/Cntr=0.3,0.1

Type RM Length L Ch R = 1 ,517     ,401,401,401
BEGIN DESCRIPTION:
YOW BRANCH 1.0
END DESCRIPTION:
XS GIS Cut Line= 3
      2385474.98     13681375.02        2385325.       13681525.
      2384975.02     13682024.98
#Sta/Elev= 30
  4788.5  327.73  4816.8  327.72    4864  325.92  4915.7  323.94  4929.9  322.93
    4944  320.75  4972.3  312.12  4988.6   302.5  4989.1     302    5005     302
  5005.5   302.5    5008   307.1  5014.1  306.46  5028.9  307.53  5043.8  310.21
  5049.9  310.52  5058.6  310.85    5086  310.09  5115.3  311.29  5159.3  309.91
    5191   310.7  5201.6   311.1  5216.4  312.83  5252.1  314.48    5267  314.88
  5273.1   314.4  5353.3  316.84  5481.5  319.26  5546.8  321.64  5610.9     325
#Mann= 5 ,-1 , 0
  4788.5     .07       0    4864      .1       0  4988.6     .05       0
  5005.5      .1       0    5191     .07       0
Bank Sta=4988.6,5005.5
XS Rating Curve= 0 ,0
Exp/Cntr=0.3,0.1

Type RM Length L Ch R = 1 ,116     ,0,0,0
BEGIN DESCRIPTION:
J21883
END DESCRIPTION:
XS GIS Cut Line= 4
      2385391.74     13681201.75      2385015.51     13681454.44
      2384863.88     13681701.54      2384920.02     13682128.14
#Sta/Elev= 30
  4405.1  324.89  4476.6  324.35  4542.6  321.39  4563.6  321.41  4578.6  320.38
  4670.4  317.86  4722.6  316.52  4815.6   316.1  4851.6  314.52  4866.8  313.44
  4872.7   312.1  4930.7  309.68  4940.3  308.41  4946.1     310  4961.6  306.01
  4967.4  306.62  4982.9   303.4    5003   302.5  5003.5     302  5019.9   302.5
  5025.4  305.81    5035  308.26  5046.7  309.28  5077.6  315.79  5105.3  317.74
  5167.3  317.36  5242.5  317.36  5348.4  319.11  5454.3  324.43  5578.5  326.08
#Mann= 5 ,-1 , 0
  4405.1     .07       0  4670.4      .1       0    5003     .05       0
  5019.9      .1       0  5167.3     .07       0
Bank Sta=5003,5019.9
XS Rating Curve= 0 ,0
Exp/Cntr=0.3,0.1

Chan Stop Cuts=-1
Use User Specified Reach Order=0
Composite Channel Slope=5