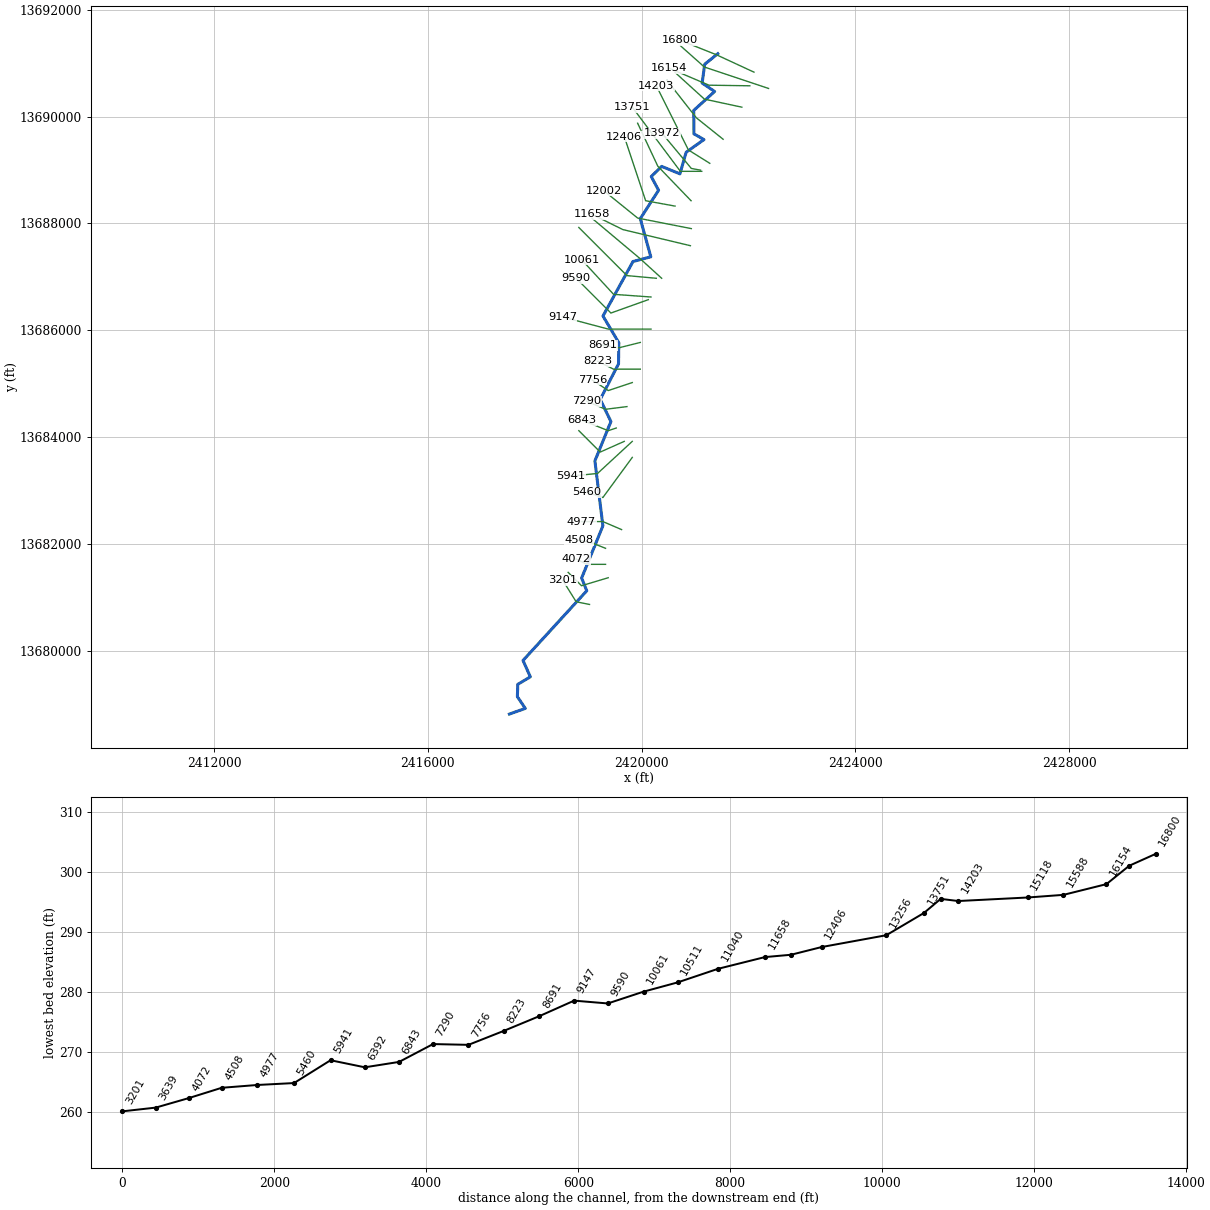
--- ALLIGATOR CREEK 2.prj (project) ---

Proj Title=ALLIGATOR CREEK 2 Base Level Engineering
Current Plan=p01
Default Exp/Contr=0.3,0.1
English Units
Geom File=g01
Flow File=f01
Plan File=p01
BEGIN DESCRIPTION:
ALLIGATOR CREEK 2
END DESCRIPTION:

--- ALLIGATOR CREEK 2.p01 (plan) ---

Plan Title=Multiple Run
Short Identifier=Multiple
Geom File=g01
Flow File=f01
Subcritical Flow
K Sum by GR= 0
Std Step Tol= 0.01
Critical Tol= 0.01
Num of Std Step Trials= 20
Max Error Tol= 0.3
Flow Tol Ratio= 0.001
Split Flow NTrial= 30
Split Flow Tol= 0.02
Split Flow Ratio= 0.02
Log Output Level= 0
Friction Slope Method= 1
Unsteady Friction Slope Method= 2
Unsteady Bridges Friction Slope Method= 1
Parabolic Critical Depth
Global Vel Dist=  1 , 1 , 1
Global Log Level= 0
CheckData=True
Encroach Param= -1, 0, 0, 0
BEGIN DESCRIPTION:
Multiple Run
END DESCRIPTION:

--- ALLIGATOR CREEK 2.f01 (steady flow) ---

Flow Title=Multiple
Number of Profiles=7
Profile Names=10-year,25-year,50-year,1pct_min,100-year,1pct_plu,500-year
River Rch & RM= ALLIGATOR CREEK ,Reach-1,16800
     678    1084    1446     933    1861    3713    3054
River Rch & RM= ALLIGATOR CREEK ,Reach-1,10511
     785    1263    1692    1095    2185    4360    3614
River Rch & RM= ALLIGATOR CREEK ,Reach-1,4977
     982    1596    2153    1402    2797    5580    4680
Boundary for River Rch & Prof#=ALLIGATOR CREEK ,Reach-1,1
Up Type=0
Dn Type=3
Dn Slope=0.005
Boundary for River Rch & Prof#=ALLIGATOR CREEK ,Reach-1,2
Up Type=0
Dn Type=3
Dn Slope=0.005
Boundary for River Rch & Prof#=ALLIGATOR CREEK ,Reach-1,3
Up Type=0
Dn Type=3
Dn Slope=0.005
Boundary for River Rch & Prof#=ALLIGATOR CREEK ,Reach-1,4
Up Type=0
Dn Type=3
Dn Slope=0.005
Boundary for River Rch & Prof#=ALLIGATOR CREEK ,Reach-1,5
Up Type=0
Dn Type=3
Dn Slope=0.005
Boundary for River Rch & Prof#=ALLIGATOR CREEK ,Reach-1,6
Up Type=0
Dn Type=3
Dn Slope=0.005
Boundary for River Rch & Prof#=ALLIGATOR CREEK ,Reach-1,7
Up Type=0
Dn Type=3
Dn Slope=0.005

--- ALLIGATOR CREEK 2.g01 (geometry) ---

Geom Title=Existing Conditions

River Reach=ALLIGATOR CREEK ,Reach-1
Reach XY= 30
      2421425.00     13691175.00      2421180.36     13690977.70
      2421132.31     13690624.89      2421366.12     13690468.49
      2420975.53     13690114.53      2420978.36     13689676.25
      2421166.12     13689568.51      2420832.70     13689331.48
      2420716.54     13688927.62      2420374.99     13689067.92
      2420180.06     13688877.29      2420317.33     13688621.34
      2419974.47     13688090.19      2420171.63     13687376.28
      2419838.47     13687288.71      2419276.88     13686269.31
      2419573.11     13685769.29      2419567.68     13685374.90
      2419225.17     13684708.96      2419425.29     13684295.18
      2419125.51     13683559.79      2419275.01     13682345.00
      2418877.22     13681369.06      2418973.43     13681131.08
      2417780.39     13679827.44      2417917.41     13679521.65
      2417682.68     13679381.52      2417674.70     13679149.87
      2417823.15     13678930.75      2417525.00     13678825.00

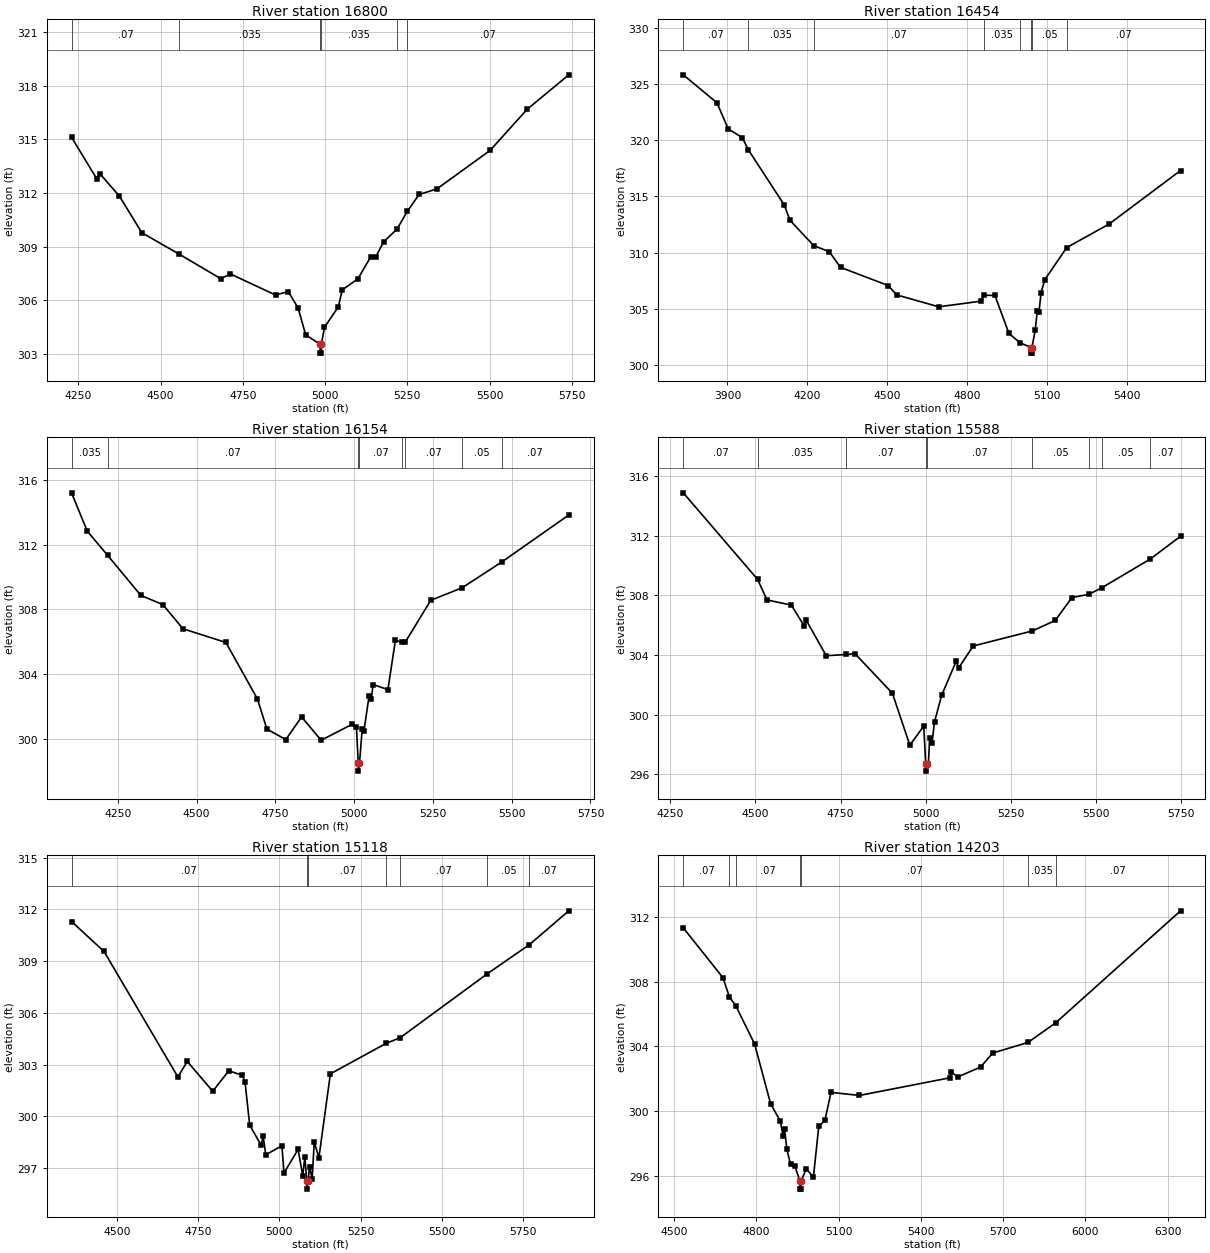
Type RM Length L Ch R = 1,16800,346,346,346
BEGIN DESCRIPTION:
X18028
END DESCRIPTION:
XS GIS Cut Line= 3
      2422102.81     13690829.66      2421400.31     13691154.79
      2420715.24     13691427.65
#Sta/Elev= 30
  4229.3  315.11  4305.5  312.80  4315.0  313.08  4374.3  311.83  4443.1  309.77
  4556.8  308.57  4683.3  307.20  4711.8  307.47  4849.3  306.29  4888.0  306.48
  4918.1  305.56  4941.0  304.06  4984.8  303.54  4985.1  303.04  4988.6  303.04
  4988.8  303.54  4998.1  304.48  5040.3  305.63  5052.2  306.58  5099.6  307.19
  5138.3  308.41  5153.5  308.40  5177.8  309.26  5218.5  309.97  5250.4  310.98
  5285.7  311.91  5339.6  312.22  5501.4  314.37  5614.6  316.68  5740.8  318.60
#Mann=6,-1,0
  4229.3    0.07       0  4556.8   0.035       0  4984.8   0.035       0
  4988.8   0.035       0  5218.5    0.05       0  5250.4    0.07       0
Bank Sta=4984.8,4988.8
Exp/Cntr=0.3,0.1

Type RM Length L Ch R = 1,16454,300,300,300
BEGIN DESCRIPTION:
ALLIGATOR CREEK 2 28.0
END DESCRIPTION:
XS GIS Cut Line= 3
      2422374.99     13690525.00      2421175.00     13690925.00
      2420724.98     13691325.01
#Sta/Elev= 30
  3734.5  325.82  3861.0  323.33  3903.1  321.01  3955.8  320.24  3978.3  319.17
  4114.0  314.23  4135.0  312.89  4224.2  310.63  4282.6  310.09  4324.8  308.70
  4504.0  307.08  4535.6  306.25  4693.7  305.19  4851.8  305.69  4863.8  306.22
  4904.5  306.20  4957.2  302.82  4997.9  302.01  5039.6  301.57  5039.9  301.07
  5043.4  301.07  5043.6  301.57  5055.8  303.10  5063.4  304.80  5070.1  304.74
  5077.6  306.42  5091.8  307.60  5174.2  310.46  5332.6  312.54  5601.5  317.31
#Mann=8,-1,0
  3734.5    0.07       0  3978.3   0.035       0  4224.2    0.07       0
  4863.8   0.035       0  4997.9    0.05       0  5039.6    0.05       0
  5043.6    0.05       0  5174.2    0.07       0
Bank Sta=5039.6,5043.6
Exp/Cntr=0.3,0.1

Type RM Length L Ch R = 1,16154,566,566,566
BEGIN DESCRIPTION:
ALLIGATOR CREEK 2 27.0
END DESCRIPTION:
XS GIS Cut Line= 3
      2422024.97     13690575.00      2421260.98     13690585.85
      2420512.08     13690905.15
#Sta/Elev= 30
  4103.0  315.20  4153.0  312.83  4217.4  311.34  4323.0  308.86  4393.0  308.29
  4456.6  306.80  4593.0  305.95  4693.0  302.46  4723.0  300.60  4783.0  299.95
  4833.0  301.35  4895.3  299.91  4993.2  300.89  5007.3  300.70  5012.8  298.50
  5013.1  298.00  5016.9  298.50  5025.5  300.58  5030.9  300.46  5047.5  302.67
  5054.5  302.47  5060.0  303.35  5107.2  303.04  5130.8  306.09  5153.2  305.95
  5162.4  305.98  5243.2  308.56  5342.5  309.33  5468.1  310.92  5681.2  313.83
#Mann=8,-1,0
  4103.0   0.035       0  4217.4    0.07       0  5012.8    0.05       0
  5016.9    0.07       0  5153.2    0.05       0  5162.4    0.07       0
  5342.5    0.05       0  5468.1    0.07       0
Bank Sta=5012.8,5016.9
Exp/Cntr=0.3,0.1

Type RM Length L Ch R = 1,15588,470,470,470
BEGIN DESCRIPTION:
ALLIGATOR CREEK 2 26.0
END DESCRIPTION:
XS GIS Cut Line= 3
      2421875.05     13690174.99      2421175.00     13690325.00
      2420625.03     13690824.97
#Sta/Elev= 30
  4288.3  314.87  4506.6  309.06  4533.8  307.69  4605.4  307.34  4643.7  305.92
  4648.8  306.34  4707.7  303.95  4766.7  304.03  4792.0  304.09  4902.0  301.43
  4953.1  297.95  4994.0  299.23  4999.6  296.71  4999.9  296.21  5003.7  296.71
  5007.6  296.71  5011.3  298.45  5018.1  298.08  5025.5  299.51  5046.5  301.30
  5089.0  303.57  5096.5  303.14  5139.0  304.60  5312.8  305.61  5379.6  306.31
  5428.9  307.85  5479.4  308.07  5517.6  308.52  5658.7  310.43  5747.5  311.96
#Mann=9,-1,0
  4288.3    0.07       0  4506.6   0.035       0  4766.7    0.07       0
  4999.6    0.05       0  5003.7    0.07       0  5312.8    0.05       0
  5479.4    0.07       0  5517.6    0.05       0  5658.7    0.07       0
Bank Sta=4999.6,5003.7
Exp/Cntr=0.3,0.1

Type RM Length L Ch R = 1,15118,915,915,915
BEGIN DESCRIPTION:
ALLIGATOR CREEK 2 25.0
END DESCRIPTION:
XS GIS Cut Line= 3
      2421525.00     13689575.00      2421025.00     13689975.00
      2420475.03     13690674.97
#Sta/Elev= 30
  4360.2  311.30  4460.3  309.56  4687.6  302.28  4716.4  303.18  4794.8  301.45
  4844.4  302.64  4886.1  302.37  4894.1  302.00  4908.5  299.49  4943.7  298.32
  4950.1  298.83  4958.1  297.76  5007.7  298.29  5014.1  296.71  5057.5  298.07
  5071.9  296.55  5078.3  297.65  5084.2  296.27  5084.5  295.77  5088.5  296.27
  5092.7  297.07  5100.8  296.38  5107.2  298.50  5121.6  297.60  5156.9  302.46
  5329.6  304.24  5371.3  304.55  5640.1  308.27  5769.6  309.96  5890.7  311.92
#Mann=7,-1,0
  4360.2    0.07       0  5084.2    0.05       0  5088.5    0.07       0
  5329.6    0.05       0  5371.3    0.07       0  5640.1    0.05       0
  5769.6    0.07       0
Bank Sta=5084.2,5088.5
Exp/Cntr=0.3,0.1

Type RM Length L Ch R = 1,14203,231,231,231
BEGIN DESCRIPTION:
ALLIGATOR CREEK 2 24.0
END DESCRIPTION:
XS GIS Cut Line= 3
      2421275.04     13689124.98      2420875.00     13689375.00
      2420274.99     13690575.01
#Sta/Elev= 30
  4533.6  311.33  4678.1  308.25  4702.0  307.05  4725.1  306.51  4793.7  304.15
  4852.0  300.46  4888.0  299.36  4897.4  298.45  4903.3  298.88  4911.0  297.66
  4924.6  296.72  4939.9  296.63  4958.9  295.68  4959.2  295.18  4963.0  295.18
  4963.3  295.68  4982.3  296.44  5008.1  295.91  5027.7  299.06  5050.1  299.44
  5072.4  301.16  5175.8  300.97  5505.7  302.06  5511.3  302.43  5533.6  302.11
  5617.5  302.72  5662.2  303.59  5791.1  304.25  5892.4  305.47  6347.0  312.38
#Mann=7,-1,0
  4533.6    0.07       0  4702.0    0.12       0  4725.1    0.07       0
  4958.9    0.05       0  4963.3    0.07       0  5791.1   0.035       0
  5892.4    0.07       0
Bank Sta=4958.9,4963.3
Exp/Cntr=0.3,0.1

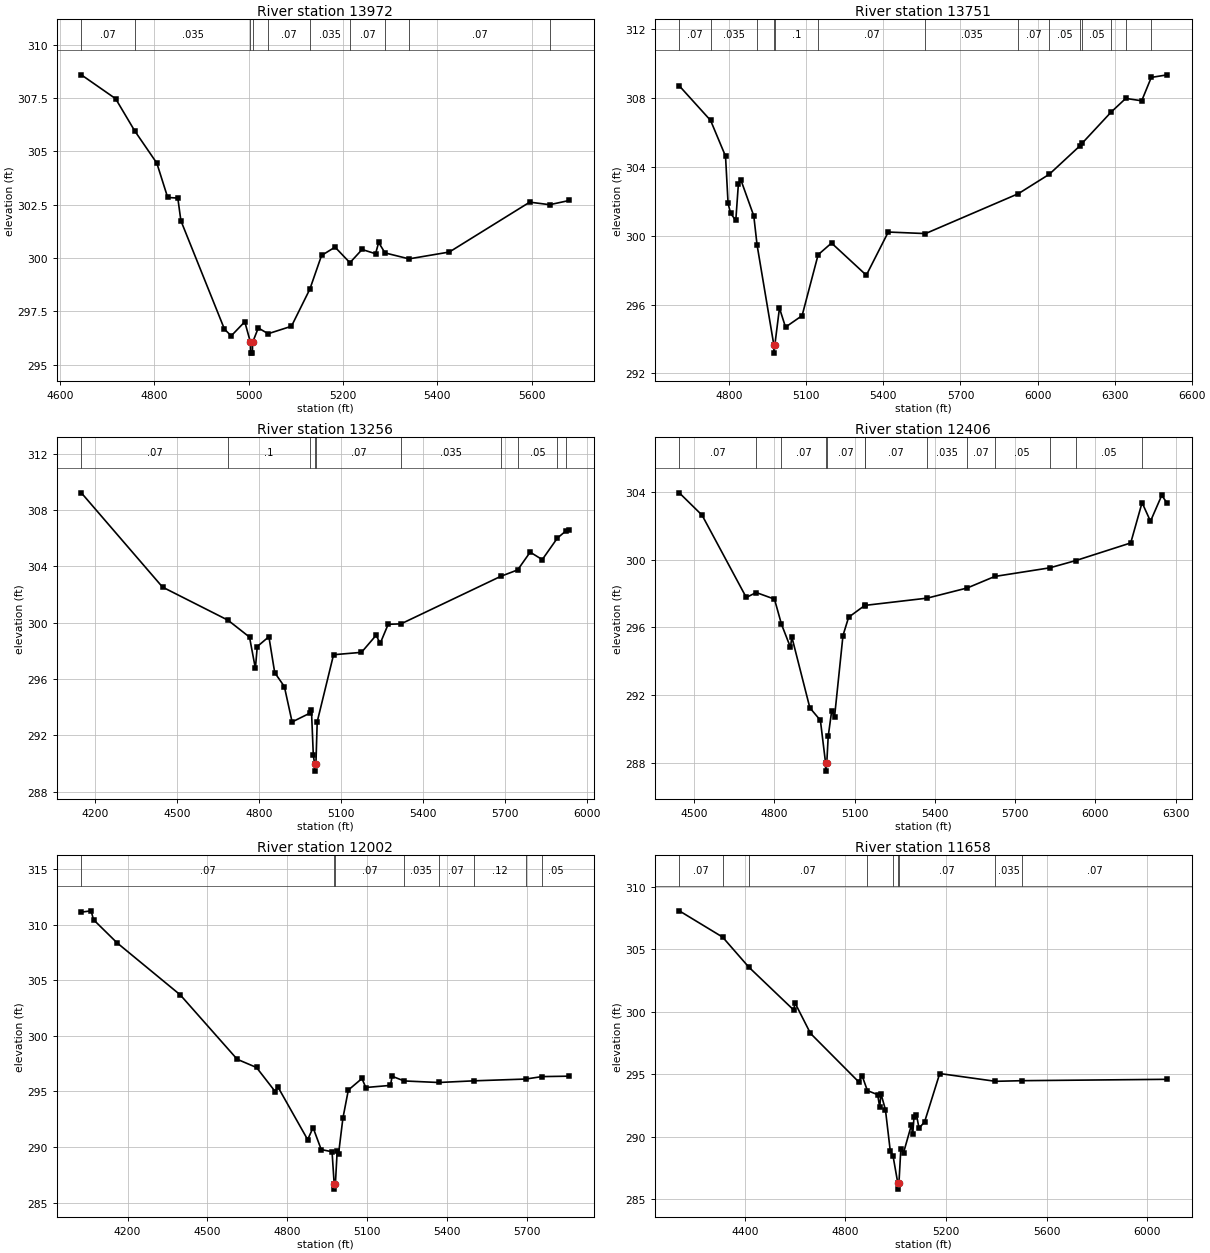
Type RM Length L Ch R = 1,13972,221,221,221
BEGIN DESCRIPTION:
ALLIGATOR CREEK 2 23.5
END DESCRIPTION:
XS GIS Cut Line= 3
      2421102.22     13688996.74      2420930.00     13689029.03
      2420379.62     13689688.77
#Sta/Elev= 30
  4645.5  308.59  4718.2  307.47  4758.7  305.96  4805.5  304.45  4828.5  302.84
  4850.0  302.81  4856.5  301.75  4948.9  296.66  4963.2  296.35  4991.9  297.01
  5004.0  296.04  5004.3  295.54  5008.1  295.54  5008.4  296.04  5020.5  296.72
  5041.4  296.45  5090.8  296.80  5129.8  298.54  5154.6  300.12  5183.2  300.51
  5214.7  299.78  5240.5  300.40  5269.1  300.20  5275.6  300.73  5289.0  300.24
  5339.9  299.96  5425.3  300.28  5595.8  302.62  5638.1  302.50  5679.9  302.70
#Mann=10,-1,0
  4645.5    0.07       0  4758.7   0.035       0  5004.0   0.035       0
  5008.4   0.035       0  5041.4    0.07       0  5129.8   0.035       0
  5214.7    0.07       0  5289.0   0.035       0  5339.9    0.07       0
  5638.1   0.035       0
Bank Sta=5004,5008.4
Exp/Cntr=0.3,0.1

Type RM Length L Ch R = 1,13751,495,495,495
BEGIN DESCRIPTION:
ALLIGATOR CREEK 2 23.0
END DESCRIPTION:
XS GIS Cut Line= 3
      2421124.96     13688975.00      2420725.00     13688975.00
      2419824.97     13690175.04
#Sta/Elev= 30
  4605.5  308.72  4727.3  306.71  4785.5  304.63  4795.5  301.88  4805.5  301.30
  4825.5  300.90  4835.5  303.00  4845.5  303.24  4895.5  301.16  4908.3  299.47
  4973.3  293.68  4973.6  293.18  4977.7  293.68  4995.5  295.80  5019.0  294.69
  5083.6  295.36  5146.0  298.90  5198.2  299.58  5333.6  297.71  5419.0  300.22
  5563.9  300.13  5925.4  302.45  6045.9  303.58  6166.4  305.25  6172.9  305.37
  6286.9  307.20  6343.5  307.99  6405.5  307.85  6442.8  309.21  6505.5  309.36
#Mann=14,-1,0
  4605.5    0.07       0  4727.3   0.035       0  4908.3     0.1       0
  4973.3    0.05       0  4977.7     0.1       0  5146.0    0.07       0
  5563.9   0.035       0  5925.4    0.07       0  6045.9    0.05       0
  6166.4   0.035       0  6172.9    0.05       0  6286.9   0.035       0
  6343.5    0.05       0  6442.8   0.035       0
Bank Sta=4973.3,4977.7
Exp/Cntr=0.3,0.1

Type RM Length L Ch R = 1,13256,850,850,850
BEGIN DESCRIPTION:
ALLIGATOR CREEK 2 22.0
END DESCRIPTION:
XS GIS Cut Line= 3
      2420924.98     13688425.02      2420303.07     13689070.61
      2419925.01     13689874.98
#Sta/Elev= 30
  4150.8  309.22  4447.8  302.53  4687.3  300.18  4766.0  298.98  4787.4  296.76
  4794.3  298.31  4836.8  299.01  4858.1  296.46  4893.4  295.47  4921.7  292.96
  4986.3  293.58  4992.4  293.83  4999.3  290.59  5004.2  289.97  5004.5  289.47
  5008.8  289.97  5013.5  292.97  5073.3  297.73  5175.5  297.90  5228.9  299.11
  5244.0  298.54  5273.1  299.89  5319.9  299.92  5684.4  303.29  5746.7  303.75
  5792.4  305.01  5836.6  304.48  5892.0  306.01  5923.4  306.52  5936.0  306.61
#Mann=10,-1,0
  4150.8    0.07       0  4687.3     0.1       0  4986.3    0.07       0
  5004.2    0.05       0  5008.8    0.07       0  5319.9   0.035       0
  5684.4    0.07       0  5746.7    0.05       0  5892.0    0.07       0
  5923.4    0.05       0
Bank Sta=5004.2,5008.8
Exp/Cntr=0.3,0.1

Type RM Length L Ch R = 1,12406,404,404,404
BEGIN DESCRIPTION:
ALLIGATOR CREEK 2 21.0
END DESCRIPTION:
XS GIS Cut Line= 3
      2420625.00     13688325.00      2420075.00     13688425.00
      2419675.01     13689624.97
#Sta/Elev= 30
  4444.9  303.94  4530.0  302.62  4695.2  297.76  4732.5  298.05  4800.6  297.66
  4826.7  296.18  4860.4  294.81  4865.4  295.43  4932.8  291.24  4972.2  290.50
  4991.4  288.00  4991.8  287.50  4996.1  288.00  5001.4  289.55  5014.5  291.07
  5025.0  290.69  5056.6  295.51  5077.7  296.59  5137.3  297.28  5138.4  297.29
  5371.5  297.72  5521.0  298.32  5623.8  299.00  5829.5  299.51  5926.9  299.94
  6131.8  300.98  6174.2  303.36  6205.6  302.26  6247.7  303.79  6268.8  303.31
#Mann=13,-1,0
  4444.9    0.07       0  4732.5     0.1       0  4826.7    0.07       0
  4991.4    0.05       0  4996.1    0.07       0  5137.3     0.1       0
  5138.4    0.07       0  5371.5   0.035       0  5521.0    0.07       0
  5623.8    0.05       0  5829.5    0.07       0  5926.9    0.05       0
  6174.2    0.07       0
Bank Sta=4991.4,4996.1
Exp/Cntr=0.3,0.1

Type RM Length L Ch R = 1,12002,344,344,344
BEGIN DESCRIPTION:
X18027
END DESCRIPTION:
XS GIS Cut Line= 3
      2420930.02     13687903.71      2419925.71     13688101.08
      2419294.16     13688610.96
#Sta/Elev= 30
  4026.2  311.12  4062.9  311.24  4072.1  310.44  4160.6  308.36  4398.2  303.68
  4612.2  297.89  4684.9  297.15  4754.9  294.99  4765.1  295.41  4877.2  290.66
  4897.6  291.74  4928.1  289.77  4968.9  289.57  4976.8  286.71  4977.1  286.21
  4981.5  286.71  4988.2  289.64  4993.3  289.37  5009.7  292.59  5030.1  295.12
  5081.3  296.16  5095.7  295.35  5188.4  295.54  5194.8  296.36  5239.8  295.94
  5369.3  295.80  5502.2  295.95  5696.8  296.11  5757.8  296.33  5861.4  296.37
#Mann=8,-1,0
  4026.2    0.07       0  4976.8    0.05       0  4981.5    0.07       0
  5239.8   0.035       0  5369.3    0.07       0  5502.2    0.12       0
  5696.8    0.07       0  5757.8    0.05       0
Bank Sta=4976.8,4981.5
Exp/Cntr=0.3,0.1

Type RM Length L Ch R = 1,11658,618,618,618
BEGIN DESCRIPTION:
X18026
END DESCRIPTION:
XS GIS Cut Line= 3
      2420912.63     13687584.40      2419647.04     13687886.28
      2419073.09     13688170.36
#Sta/Elev= 30
  4139.0  308.07  4311.3  305.97  4415.1  303.58  4594.1  300.14  4599.2  300.71
  4660.9  298.27  4851.9  294.41  4866.5  294.87  4887.2  293.70  4928.2  293.37
  4936.1  292.36  4941.3  293.44  4959.0  292.17  4978.2  288.88  4989.1  288.49
  5008.0  286.32  5008.4  285.82  5012.8  286.32  5020.3  289.06  5031.0  288.73
  5061.8  290.91  5067.6  290.23  5072.7  291.60  5082.4  291.76  5092.7  290.69
  5114.8  291.20  5174.9  295.06  5396.7  294.44  5504.0  294.49  6080.5  294.60
#Mann=9,-1,0
  4139.0    0.07       0  4311.3    0.12       0  4415.1    0.07       0
  4887.2    0.12       0  4989.1    0.07       0  5008.0    0.05       0
  5012.8    0.07       0  5396.7   0.035       0  5504.0    0.07       0
Bank Sta=5008,5012.8
Exp/Cntr=0.3,0.1

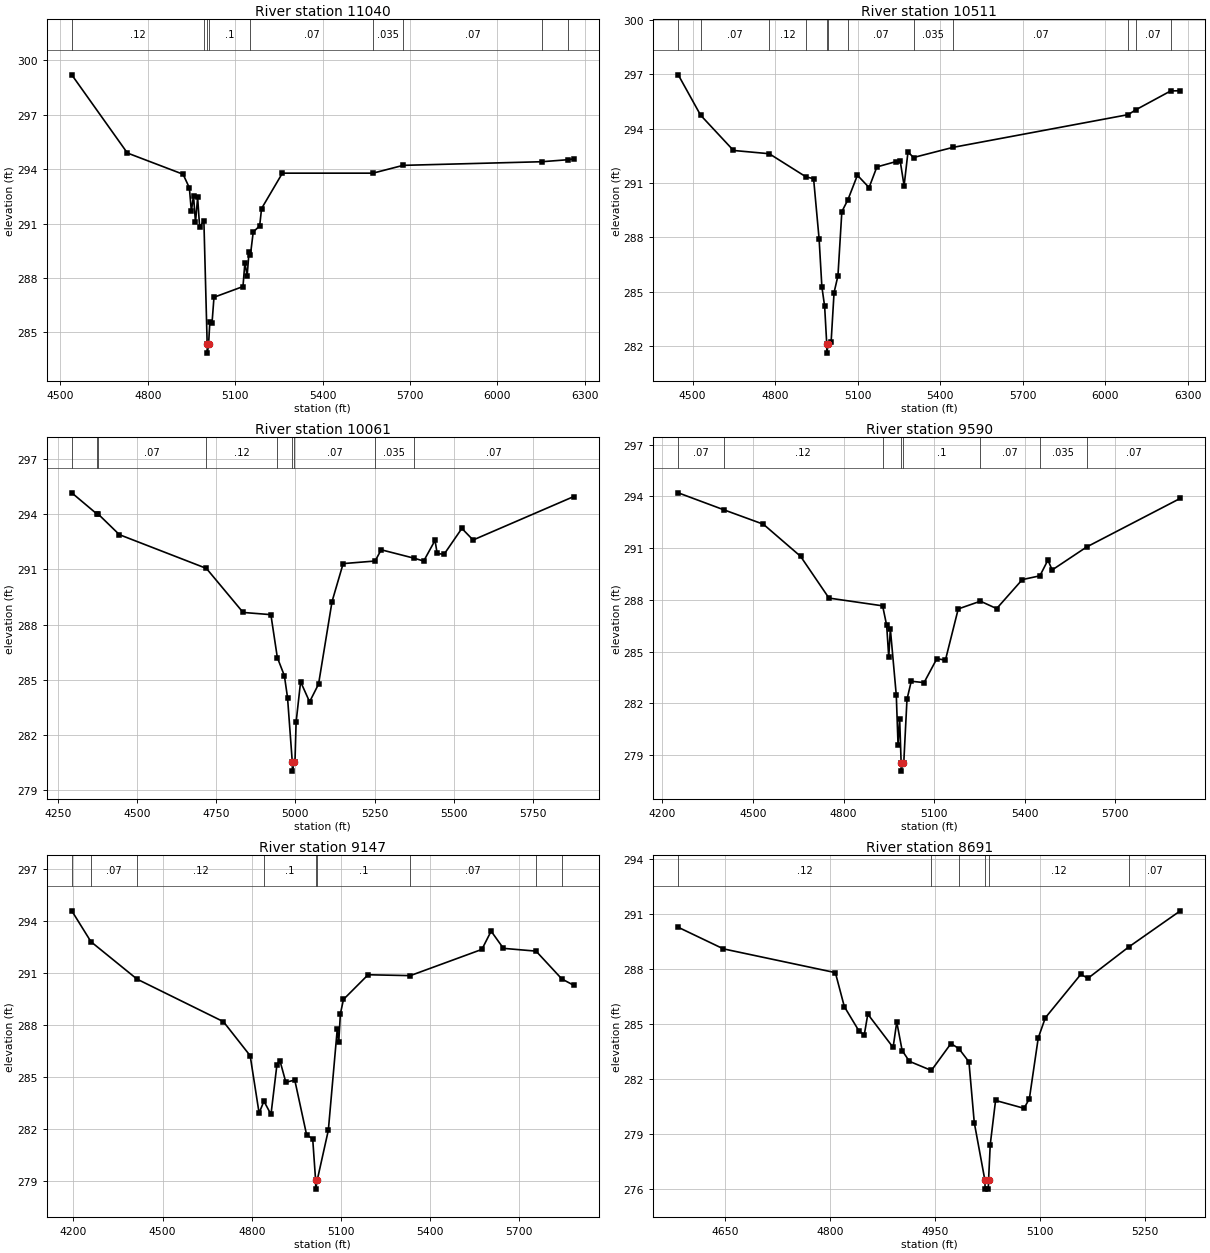
Type RM Length L Ch R = 1,11040,529,529,529
BEGIN DESCRIPTION:
ALLIGATOR CREEK 2 20.0
END DESCRIPTION:
XS GIS Cut Line= 3
      2420374.97     13686975.02      2419966.35     13687346.37
      2419068.87     13688099.09
#Sta/Elev= 30
  4539.1  299.20  4730.0  294.89  4921.2  293.72  4942.8  292.97  4949.6  291.68
  4957.0  292.54  4963.8  291.07  4971.2  292.44  4978.0  290.80  4992.6  291.16
  5003.9  284.36  5004.2  283.86  5008.8  284.36  5013.1  285.59  5020.5  285.51
  5027.3  286.94  5126.8  287.53  5133.4  288.85  5141.1  288.12  5147.7  289.45
  5152.4  289.27  5162.0  290.54  5184.1  290.87  5190.6  291.83  5262.1  293.78
  5573.0  293.78  5676.6  294.21  6152.1  294.41  6241.7  294.52  6262.6  294.57
#Mann=9,-1,0
  4539.1    0.12       0  4992.6     0.1       0  5003.9    0.05       0
  5008.8     0.1       0  5152.4    0.07       0  5573.0   0.035       0
  5676.6    0.07       0  6152.1    0.12       0  6241.7    0.07       0
Bank Sta=5003.9,5008.8
Exp/Cntr=0.3,0.1

Type RM Length L Ch R = 1,10511,450,450,450
BEGIN DESCRIPTION:
ALLIGATOR CREEK 2 19.0
END DESCRIPTION:
XS GIS Cut Line= 3
      2420274.99     13686975.00      2419725.00     13687025.00
      2418825.03     13687924.97
#Sta/Elev= 30
  4448.1  296.98  4529.4  294.75  4648.9  292.80  4778.9  292.62  4912.6  291.34
  4940.1  291.24  4960.2  287.90  4970.2  285.27  4980.3  284.18  4987.9  282.10
  4988.2  281.60  4992.8  282.10  5003.9  282.24  5014.5  284.95  5028.6  285.87
  5042.8  289.42  5064.7  290.07  5099.4  291.43  5141.8  290.75  5170.1  291.89
  5240.8  292.19  5254.9  292.22  5269.1  290.85  5283.2  292.72  5303.3  292.41
  5446.6  292.97  6083.7  294.78  6110.5  295.04  6238.1  296.09  6273.1  296.10
#Mann=12,-1,0
  4448.1    0.12       0  4529.4    0.07       0  4778.9    0.12       0
  4912.6     0.1       0  4987.9    0.05       0  4992.8     0.1       0
  5064.7    0.07       0  5303.3   0.035       0  5446.6    0.07       0
  6083.7    0.12       0  6110.5    0.07       0  6238.1    0.12       0
Bank Sta=4987.9,4992.8
Exp/Cntr=0.3,0.1

Type RM Length L Ch R = 1,10061,471,471,471
BEGIN DESCRIPTION:
ALLIGATOR CREEK 2 18.0
END DESCRIPTION:
XS GIS Cut Line= 3
      2420174.97     13686625.00      2419475.00     13686675.00
      2418875.03     13687324.97
#Sta/Elev= 30
  4293.5  295.15  4373.8  293.99  4376.8  294.00  4443.9  292.88  4718.8  291.05
  4834.8  288.66  4922.6  288.54  4943.0  286.21  4965.2  285.23  4975.2  284.04
  4990.2  280.55  4990.6  280.05  4995.3  280.55  4998.7  280.55  5002.3  282.71
  5016.5  284.90  5044.9  283.81  5073.2  284.77  5115.8  289.25  5150.9  291.31
  5251.9  291.45  5271.1  292.06  5373.4  291.61  5405.5  291.45  5441.2  292.57
  5448.0  291.86  5469.6  291.81  5526.0  293.22  5561.4  292.59  5879.8  294.95
#Mann=9,-1,0
  4293.5    0.07       0  4373.8    0.12       0  4376.8    0.07       0
  4718.8    0.12       0  4943.0    0.07       0  4990.2    0.05       0
  4995.3    0.07       0  5251.9   0.035       0  5373.4    0.07       0
Bank Sta=4990.2,4995.3
Exp/Cntr=0.3,0.1

Type RM Length L Ch R = 1,9590,443,443,443
BEGIN DESCRIPTION:
ALLIGATOR CREEK 2 17.0
END DESCRIPTION:
XS GIS Cut Line= 3
      2420125.01     13686575.00      2419425.00     13686325.00
      2418774.97     13686975.03
#Sta/Elev= 30
  4252.5  294.21  4402.9  293.23  4534.4  292.39  4657.6  290.53  4751.6  288.11
  4929.3  287.66  4942.7  286.53  4949.6  284.68  4954.9  286.32  4974.6  282.47
  4980.4  279.60  4985.7  281.12  4990.6  278.58  4991.0  278.08  4995.7  278.58
  4999.4  278.58  5010.0  282.24  5024.1  283.29  5066.5  283.21  5109.0  284.60
  5137.2  284.51  5179.7  287.48  5253.2  287.93  5306.9  287.50  5391.8  289.18
  5450.2  289.40  5476.6  290.31  5490.8  289.74  5604.8  291.07  5915.1  293.89
#Mann=8,-1,0
  4252.5    0.07       0  4402.9    0.12       0  4929.3     0.1       0
  4990.6    0.05       0  4995.7     0.1       0  5253.2    0.07       0
  5450.2   0.035       0  5604.8    0.07       0
Bank Sta=4990.6,4995.7
Exp/Cntr=0.3,0.1

Type RM Length L Ch R = 1,9147,456,456,456
BEGIN DESCRIPTION:
ALLIGATOR CREEK 2 16.0
END DESCRIPTION:
XS GIS Cut Line= 3
      2420175.00     13686025.00      2419375.00     13686025.00
      2418516.03     13686252.56
#Sta/Elev= 30
  4194.5  294.57  4259.1  292.79  4413.9  290.64  4704.5  288.19  4794.5  286.23
  4824.5  282.93  4840.8  283.61  4864.5  282.85  4884.5  285.71  4894.5  285.95
  4914.5  284.70  4944.5  284.83  4984.5  281.66  5004.8  281.45  5014.6  279.05
  5015.0  278.55  5019.8  279.05  5057.4  281.94  5087.3  287.74  5092.4  287.01
  5097.9  288.64  5108.3  289.47  5191.1  290.89  5333.1  290.84  5573.8  292.35
  5604.9  293.40  5646.2  292.41  5756.0  292.25  5842.6  290.65  5883.1  290.28
#Mann=9,-1,0
  4194.5    0.12       0  4259.1    0.07       0  4413.9    0.12       0
  4840.8     0.1       0  5014.6    0.05       0  5019.8     0.1       0
  5333.1    0.07       0  5756.0   0.035       0  5842.6    0.07       0
Bank Sta=5014.6,5019.8
Exp/Cntr=0.3,0.1

Type RM Length L Ch R = 1,8691,468,468,468
BEGIN DESCRIPTION:
ALLIGATOR CREEK 2 15.0
END DESCRIPTION:
XS GIS Cut Line= 3
      2419974.97     13685774.99      2419575.00     13685675.00
      2419275.02     13685725.00
#Sta/Elev= 30
  4583.5  290.29  4647.9  289.11  4807.7  287.81  4820.5  285.95  4841.2  284.63
  4848.9  284.40  4854.0  285.54  4890.1  283.72  4895.3  285.11  4903.0  283.55
  4913.3  282.96  4944.7  282.46  4972.6  283.93  4983.8  283.66  4998.3  282.93
  5005.9  279.61  5021.0  276.47  5021.4  275.97  5025.9  275.97  5026.3  276.47
  5028.7  278.41  5036.3  280.82  5076.9  280.39  5084.5  280.91  5097.2  284.24
  5107.3  285.34  5158.0  287.72  5168.1  287.50  5226.2  289.21  5299.9  291.19
#Mann=6,-1,0
  4583.5    0.12       0  4944.7     0.1       0  4983.8    0.12       0
  5021.0    0.05       0  5026.3    0.12       0  5226.2    0.07       0
Bank Sta=5021,5026.3
Exp/Cntr=0.3,0.1

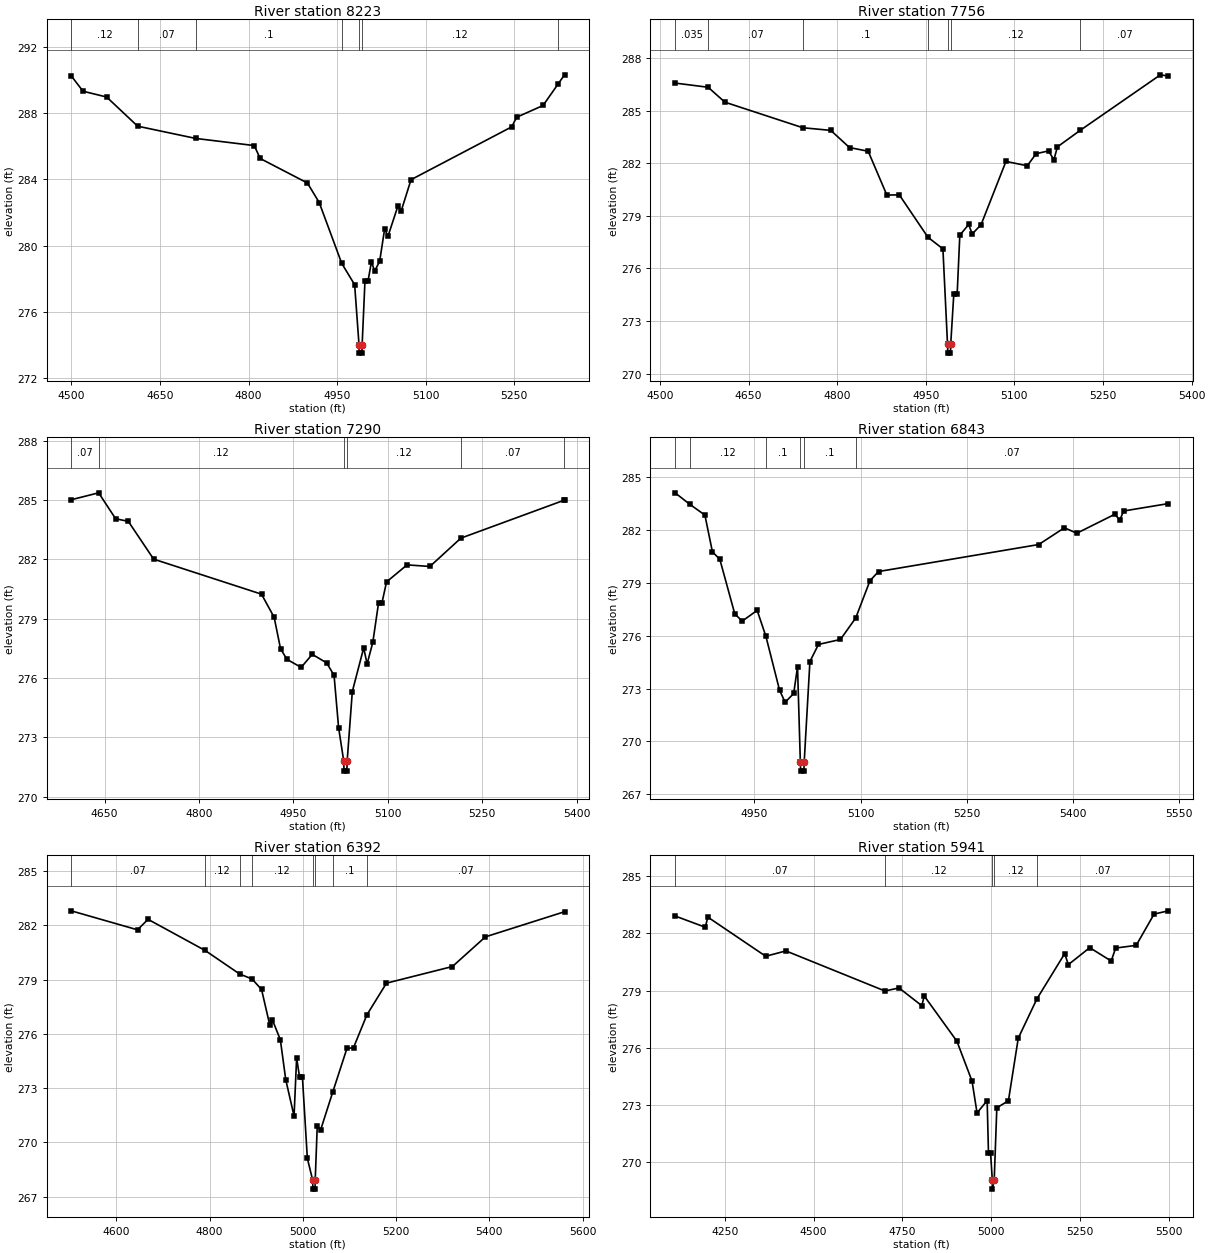
Type RM Length L Ch R = 1,8223,467,467,467
BEGIN DESCRIPTION:
ALLIGATOR CREEK 2 14.0
END DESCRIPTION:
XS GIS Cut Line= 3
      2419975.04     13685275.00      2419475.00     13685275.00
      2419175.04     13685424.98
#Sta/Elev= 30
  4499.7  290.25  4519.7  289.32  4559.7  288.97  4612.2  287.21  4710.6  286.47
  4809.7  286.04  4819.7  285.26  4899.7  283.78  4919.7  282.60  4957.8  278.93
  4979.7  277.64  4987.1  274.01  4987.5  273.51  4992.0  273.51  4992.4  274.01
  4997.2  277.89  5002.5  277.89  5008.1  279.01  5013.7  278.47  5022.1  279.06
  5030.5  281.01  5036.1  280.56  5052.8  282.37  5058.4  282.08  5075.2  283.98
  5245.7  287.17  5254.1  287.75  5298.8  288.46  5323.7  289.73  5335.1  290.31
#Mann=7,-1,0
  4499.7    0.12       0  4612.2    0.07       0  4710.6     0.1       0
  4957.8    0.12       0  4987.1    0.05       0  4992.4    0.12       0
  5323.7    0.07       0
Bank Sta=4987.1,4992.4
Exp/Cntr=0.3,0.1

Type RM Length L Ch R = 1,7756,466,466,466
BEGIN DESCRIPTION:
ALLIGATOR CREEK 2 13.0
END DESCRIPTION:
XS GIS Cut Line= 3
      2419825.01     13685025.00      2419375.00     13684875.00
      2419075.01     13685075.00
#Sta/Elev= 30
  4525.7  286.58  4581.7  286.34  4610.0  285.49  4742.0  284.03  4789.2  283.88
  4820.9  282.90  4852.5  282.69  4884.1  280.19  4905.2  280.20  4953.7  277.78
  4979.0  277.12  4986.8  271.67  4987.3  271.17  4991.8  271.17  4992.2  271.67
  4997.4  274.53  5003.1  274.53  5007.6  277.90  5022.6  278.51  5028.6  277.97
  5043.6  278.50  5085.7  282.11  5121.7  281.86  5136.8  282.55  5157.8  282.71
  5166.8  282.20  5172.8  282.94  5211.7  283.89  5347.1  287.05  5360.6  286.98
#Mann=7,-1,0
  4525.7   0.035       0  4581.7    0.07       0  4742.0     0.1       0
  4953.7    0.12       0  4986.8    0.05       0  4992.2    0.12       0
  5211.7    0.07       0
Bank Sta=4986.8,4992.2
Exp/Cntr=0.3,0.1

Type RM Length L Ch R = 1,7290,447,447,447
BEGIN DESCRIPTION:
ALLIGATOR CREEK 2 12.0
END DESCRIPTION:
XS GIS Cut Line= 3
      2419725.03     13684575.00      2419325.00     13684525.00
      2418975.03     13684674.99
#Sta/Elev= 30
  4596.9  285.01  4640.5  285.36  4667.5  284.05  4687.6  283.92  4727.9  282.01
  4899.3  280.24  4919.4  279.07  4929.5  277.49  4939.6  276.95  4962.3  276.54
  4979.9  277.20  5002.8  276.77  5014.6  276.14  5021.8  273.50  5030.0  271.80
  5030.4  271.30  5035.0  271.30  5035.4  271.80  5043.6  275.32  5061.7  277.53
  5067.1  276.71  5076.2  277.81  5085.3  279.80  5090.7  279.80  5098.0  280.86
  5130.6  281.72  5166.9  281.64  5216.1  283.07  5379.7  284.98  5380.8  284.98
#Mann=6,-1,0
  4596.9    0.07       0  4640.5    0.12       0  5030.0    0.05       0
  5035.4    0.12       0  5216.1    0.07       0  5379.7    0.12       0
Bank Sta=5030,5035.4
Exp/Cntr=0.3,0.1

Type RM Length L Ch R = 1,6843,451,451,451
BEGIN DESCRIPTION:
ALLIGATOR CREEK 2 11.0
END DESCRIPTION:
XS GIS Cut Line= 3
      2419524.96     13684174.99      2419375.00     13684125.00
      2418874.99     13684325.00
#Sta/Elev= 30
  4838.0  284.09  4859.1  283.43  4880.1  282.83  4890.7  280.75  4901.2  280.32
  4922.3  277.23  4932.8  276.82  4953.9  277.43  4966.3  275.95  4985.5  272.91
  4993.4  272.22  5005.5  272.72  5010.9  274.23  5014.9  268.82  5015.3  268.32
  5019.9  268.32  5020.3  268.82  5028.4  274.53  5040.5  275.50  5071.5  275.78
  5093.1  277.00  5113.2  279.11  5125.3  279.63  5351.5  281.16  5387.8  282.11
  5405.3  281.80  5459.2  282.88  5465.9  282.53  5471.3  283.06  5534.6  283.48
#Mann=6,-1,0
  4838.0    0.07       0  4859.1    0.12       0  4966.3     0.1       0
  5014.9    0.05       0  5020.3     0.1       0  5093.1    0.07       0
Bank Sta=5014.9,5020.3
Exp/Cntr=0.3,0.1

Type RM Length L Ch R = 1,6392,451,451,451
BEGIN DESCRIPTION:
ALLIGATOR CREEK 2 10.0
END DESCRIPTION:
XS GIS Cut Line= 3
      2419674.96     13683924.98      2419225.00     13683725.00
      2418824.99     13684125.01
#Sta/Elev= 30
  4503.1  282.81  4645.3  281.76  4667.9  282.34  4790.2  280.62  4864.2  279.32
  4891.0  279.04  4911.4  278.46  4929.2  276.47  4934.6  276.78  4951.7  275.68
  4963.3  273.47  4981.1  271.46  4986.6  274.67  4992.8  273.63  4999.0  273.63
  5009.6  269.12  5021.0  267.92  5021.5  267.42  5026.1  267.42  5026.5  267.92
  5030.8  270.89  5037.9  270.68  5064.0  272.78  5094.5  275.20  5108.6  275.24
  5137.4  277.06  5179.3  278.81  5320.8  279.73  5391.5  281.37  5561.2  282.76
#Mann=8,-1,0
  4503.1    0.07       0  4790.2    0.12       0  4864.2    0.07       0
  4891.0    0.12       0  5021.0    0.05       0  5026.5    0.12       0
  5064.0     0.1       0  5137.4    0.07       0
Bank Sta=5021,5026.5
Exp/Cntr=0.3,0.1

Type RM Length L Ch R = 1,5941,481,481,481
BEGIN DESCRIPTION:
ALLIGATOR CREEK 2 9.0
END DESCRIPTION:
XS GIS Cut Line= 3
      2419824.98     13683924.99      2419175.00     13683325.00
      2418674.96     13683275.00
#Sta/Elev= 30
  4110.6  282.91  4195.4  282.32  4202.7  282.85  4365.5  280.80  4422.2  281.08
  4700.7  278.98  4740.3  279.14  4804.4  278.21  4811.2  278.72  4903.0  276.35
  4945.6  274.26  4959.7  272.59  4988.1  273.24  4991.8  270.50  4997.7  270.50
  5002.5  269.10  5002.9  268.60  5008.0  269.10  5015.3  272.86  5047.9  273.23
  5075.6  276.51  5128.1  278.57  5206.2  280.94  5216.3  280.36  5276.6  281.25
  5336.9  280.55  5349.4  281.23  5407.2  281.37  5457.5  283.01  5497.7  283.18
#Mann=5,-1,0
  4110.6    0.07       0  4700.7    0.12       0  5002.5    0.05       0
  5008.0    0.12       0  5128.1    0.07       0
Bank Sta=5002.5,5008
Exp/Cntr=0.3,0.1

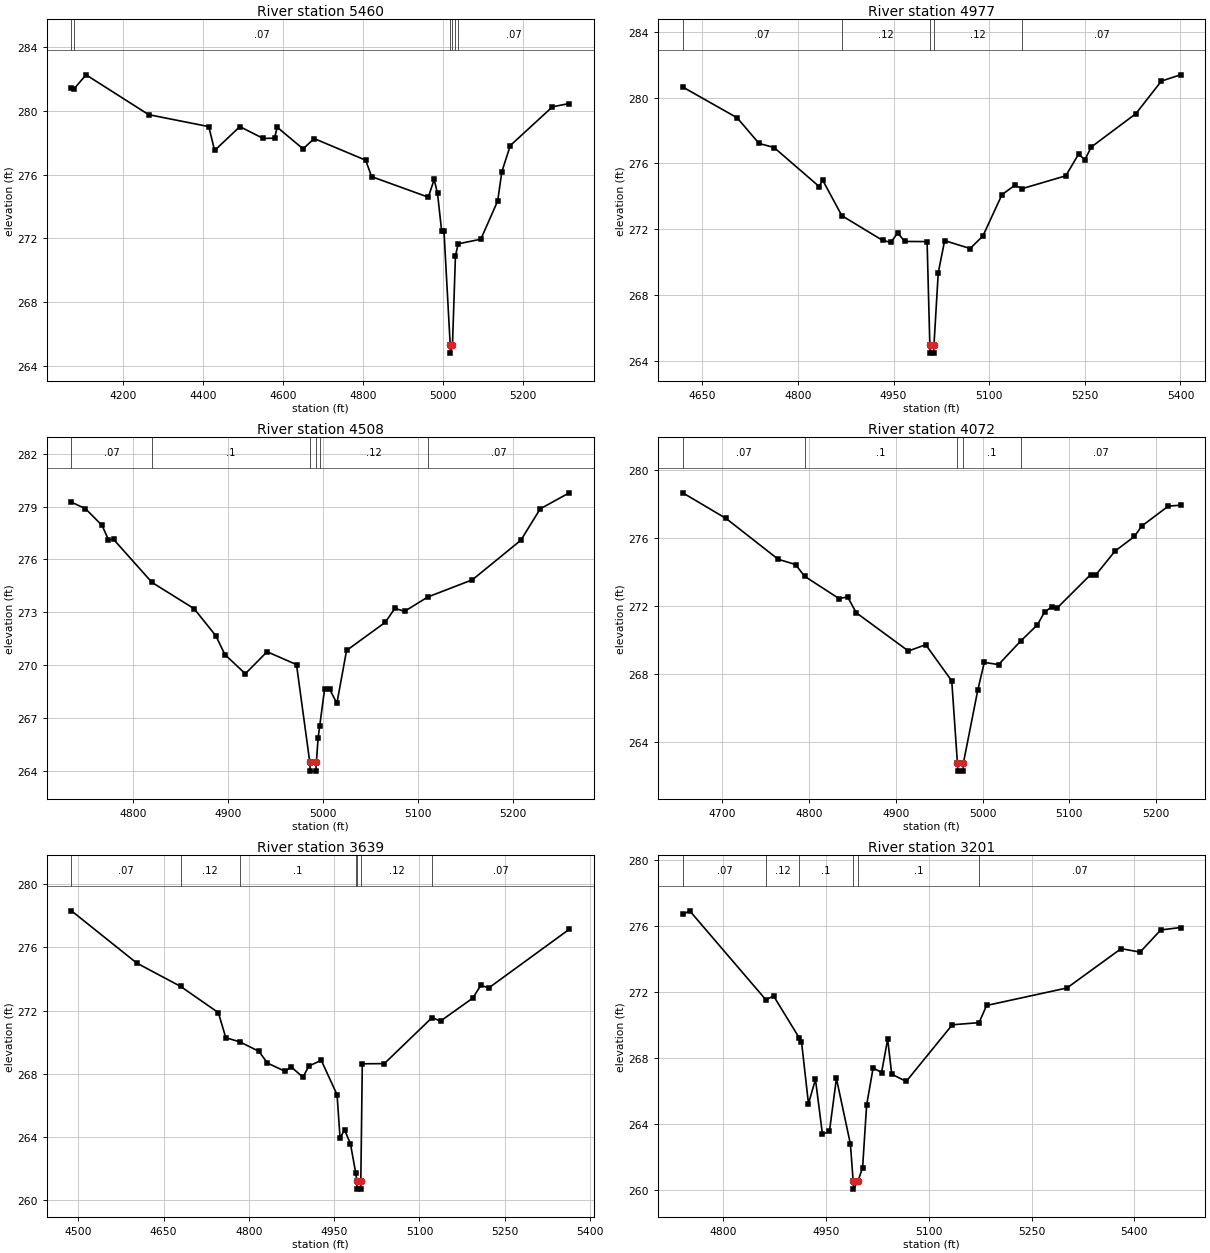
Type RM Length L Ch R = 1,5460,483,483,483
BEGIN DESCRIPTION:
ALLIGATOR CREEK 2 8.0
END DESCRIPTION:
XS GIS Cut Line= 3
      2419825.00     13683624.99      2419275.00     13682875.00
      2418974.98     13682975.01
#Sta/Elev= 30
  4070.1  281.45  4076.3  281.37  4106.7  282.26  4263.4  279.76  4413.9  279.01
  4428.6  277.51  4491.7  279.01  4549.8  278.27  4578.5  278.28  4585.3  278.97
  4650.1  277.61  4677.7  278.26  4806.8  276.90  4821.5  275.87  4963.5  274.58
  4978.2  275.69  4986.6  274.82  4997.0  272.44  5002.8  272.44  5018.4  265.29
  5018.9  264.79  5024.0  265.29  5031.5  270.90  5038.4  271.65  5095.0  271.94
  5137.2  274.34  5147.7  276.18  5168.8  277.82  5274.2  280.25  5316.4  280.46
#Mann=6,-1,0
  4070.1    0.12       0  4076.3    0.07       0  5018.4    0.05       0
  5024.0    0.07       0  5031.5    0.12       0  5038.4    0.07       0
Bank Sta=5018.4,5024
Exp/Cntr=0.3,0.1

Type RM Length L Ch R = 1,4977,469,469,469
BEGIN DESCRIPTION:
ALLIGATOR CREEK 2 7.0
END DESCRIPTION:
XS GIS Cut Line= 3
      2419625.04     13682274.98      2419275.00     13682425.00
      2418875.04     13682425.00
#Sta/Elev= 30
  4619.3  280.65  4704.6  278.78  4739.0  277.22  4762.6  276.97  4833.3  274.60
  4838.8  274.99  4868.8  272.83  4933.0  271.32  4945.7  271.21  4956.6  271.78
  4967.5  271.26  5002.6  271.25  5006.9  264.97  5007.4  264.47  5012.9  264.47
  5013.4  264.97  5020.1  269.35  5030.1  271.31  5070.1  270.83  5090.1  271.59
  5120.1  274.11  5140.1  274.67  5151.7  274.47  5220.1  275.25  5240.1  276.56
  5250.1  276.23  5260.1  277.00  5330.1  279.03  5370.1  281.01  5400.1  281.39
#Mann=5,-1,0
  4619.3    0.07       0  4868.8    0.12       0  5006.9    0.05       0
  5013.4    0.12       0  5151.7    0.07       0
Bank Sta=5006.9,5013.4
Exp/Cntr=0.3,0.1

Type RM Length L Ch R = 1,4508,436,436,436
BEGIN DESCRIPTION:
ALLIGATOR CREEK 2 6.0
END DESCRIPTION:
XS GIS Cut Line= 3
      2419325.00     13681925.00      2419075.00     13682025.00
      2418825.01     13682075.00
#Sta/Elev= 30
  4734.8  279.25  4749.6  278.88  4767.1  277.93  4773.8  277.12  4779.2  277.14
  4819.6  274.70  4864.0  273.21  4886.9  271.67  4896.4  270.61  4917.9  269.52
  4940.8  270.77  4971.8  270.04  4985.8  264.50  4986.3  264.00  4992.2  264.00
  4992.7  264.50  4994.6  265.90  4996.2  266.55  5001.4  268.66  5006.6  268.66
  5014.3  267.84  5024.5  270.84  5065.3  272.44  5075.4  273.23  5085.6  273.06
  5109.9  273.87  5157.0  274.85  5208.0  277.09  5228.4  278.87  5259.0  279.78
#Mann=6,-1,0
  4734.8    0.07       0  4819.6     0.1       0  4985.8    0.05       0
  4992.7     0.1       0  4996.2    0.12       0  5109.9    0.07       0
Bank Sta=4985.8,4992.7
Exp/Cntr=0.3,0.1

Type RM Length L Ch R = 1,4072,433,433,433
BEGIN DESCRIPTION:
ALLIGATOR CREEK 2 5.0
END DESCRIPTION:
XS GIS Cut Line= 3
      2419324.96     13681625.00      2418975.00     13681625.00
      2418774.97     13681725.02
#Sta/Elev= 30
  4654.4  278.65  4704.4  277.14  4764.4  274.74  4784.4  274.43  4794.8  273.74
  4834.4  272.43  4844.4  272.52  4854.4  271.59  4914.4  269.34  4934.4  269.71
  4964.4  267.58  4970.9  262.77  4971.4  262.27  4977.4  262.27  4977.9  262.77
  4994.4  267.04  5001.9  268.67  5018.3  268.54  5043.9  269.93  5063.1  270.88
  5071.4  271.64  5079.8  271.94  5085.4  271.85  5124.5  273.84  5130.1  273.80
  5152.5  275.22  5174.9  276.08  5183.2  276.69  5214.0  277.87  5228.0  277.92
#Mann=5,-1,0
  4654.4    0.07       0  4794.8     0.1       0  4970.9    0.05       0
  4977.9     0.1       0  5043.9    0.07       0
Bank Sta=4970.9,4977.9
Exp/Cntr=0.3,0.1

Type RM Length L Ch R = 1,3639,438,438,438
BEGIN DESCRIPTION:
ALLIGATOR CREEK 2 4.0
END DESCRIPTION:
XS GIS Cut Line= 3
      2419375.04     13681375.01      2418875.00     13681225.00
      2418625.01     13681474.99
#Sta/Elev= 30
  4487.9  278.32  4602.8  275.01  4680.0  273.53  4746.3  271.87  4759.4  270.28
  4784.0  270.02  4817.7  269.42  4832.5  268.68  4863.8  268.15  4874.2  268.44
  4895.1  267.78  4905.6  268.49  4927.3  268.85  4955.1  266.67  4960.4  263.92
  4968.2  264.45  4978.6  263.57  4987.8  261.74  4989.9  261.19  4990.4  260.69
  4996.4  260.69  4996.9  261.19  4999.5  268.63  5038.2  268.64  5122.0  271.55
  5137.2  271.34  5193.8  272.79  5207.9  273.60  5222.1  273.44  5363.5  277.15
#Mann=7,-1,0
  4487.9    0.07       0  4680.0    0.12       0  4784.0     0.1       0
  4987.8    0.12       0  4989.9    0.05       0  4996.9    0.12       0
  5122.0    0.07       0
Bank Sta=4989.9,4996.9
Exp/Cntr=0.3,0.1

Type RM Length L Ch R = 1,3201,449,449,449
BEGIN DESCRIPTION:
ALLIGATOR CREEK 2 3.0
END DESCRIPTION:
XS GIS Cut Line= 3
      2419025.01     13680875.00      2418775.00     13680925.00
      2418524.98     13681325.04
#Sta/Elev= 30
  4740.6  276.70  4750.8  276.92  4862.1  271.53  4873.2  271.77  4910.5  269.24
  4914.0  269.00  4924.2  265.24  4934.4  266.72  4944.6  263.39  4954.8  263.57
  4965.0  266.77  4985.4  262.80  4989.4  260.57  4989.9  260.07  4996.6  260.57
  5003.2  261.37  5009.1  265.17  5018.6  267.41  5030.9  267.13  5039.8  269.15
  5045.7  267.03  5066.9  266.59  5134.1  270.02  5173.2  270.15  5184.2  271.19
  5301.6  272.25  5380.6  274.63  5408.3  274.42  5438.4  275.76  5467.3  275.91
#Mann=6,-1,0
  4740.6    0.07       0  4862.1    0.12       0  4910.5     0.1       0
  4989.4    0.05       0  4996.6     0.1       0  5173.2    0.07       0
Bank Sta=4989.4,4996.6
Exp/Cntr=0.3,0.1