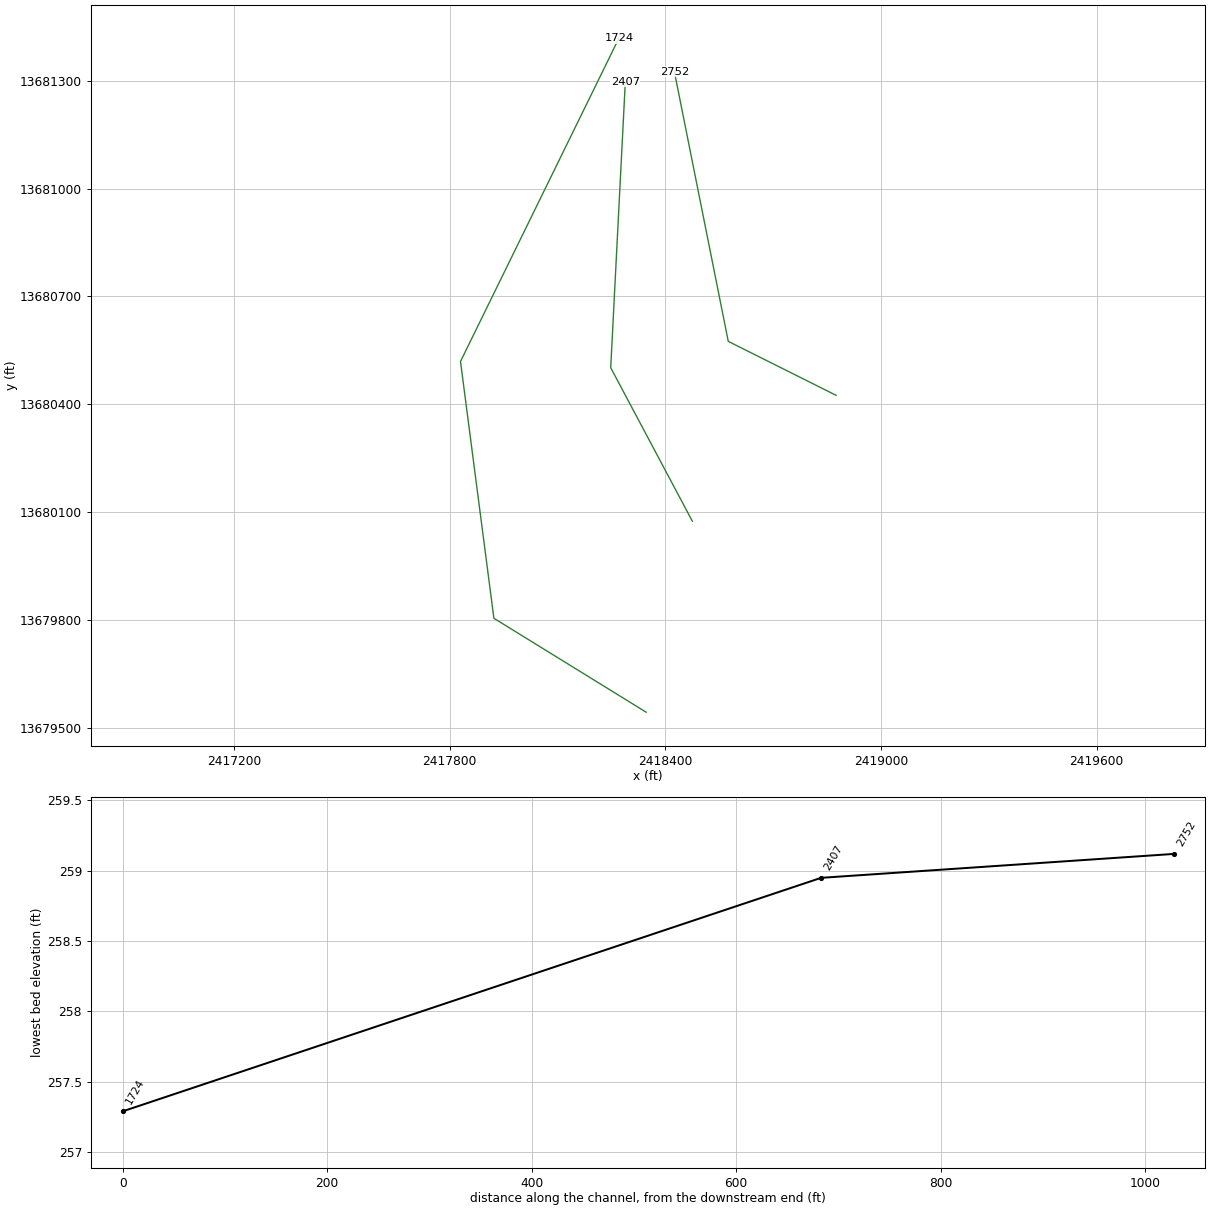
HEC-RAS study ALLIGATOR CREEK 2.prj: ALLIGATOR CREEK 2 Base Level Engineering

--- ALLIGATOR CREEK 2.g01 (geometry) --- (continued)

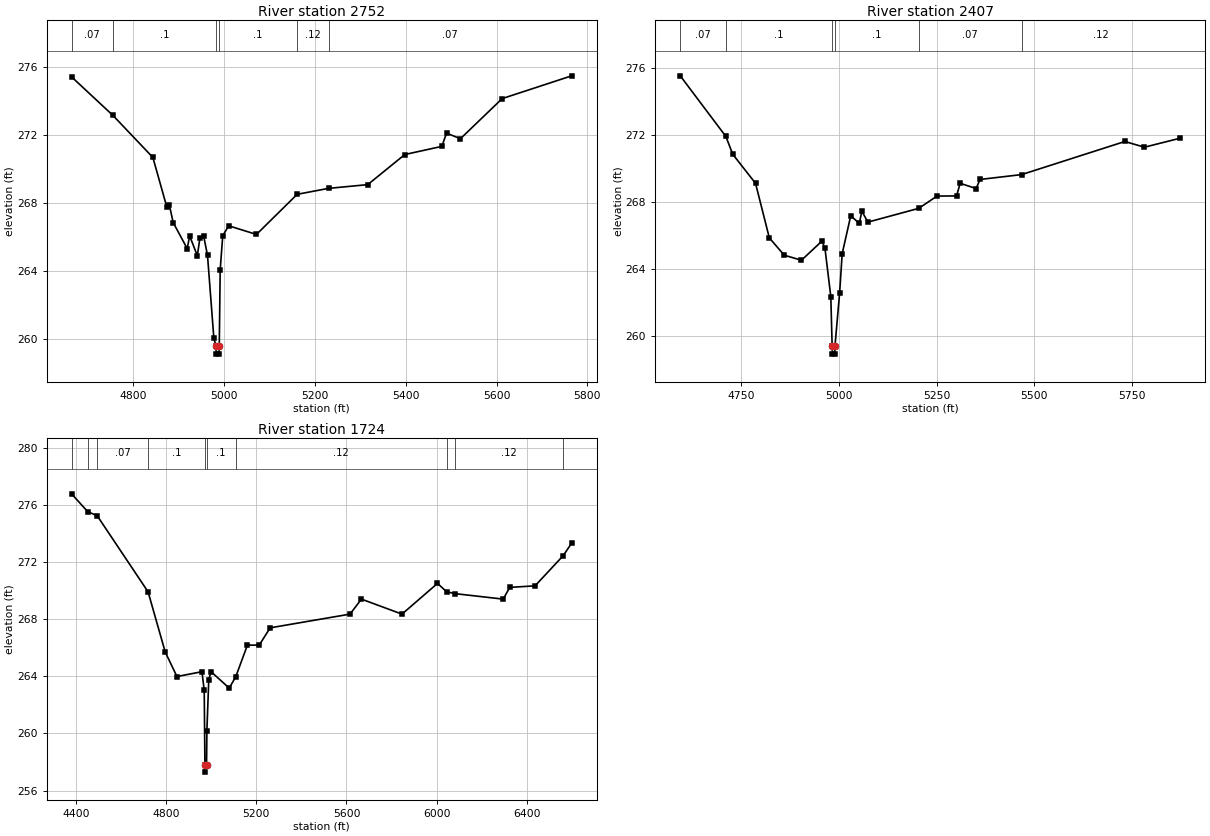
Type RM Length L Ch R = 1,2752,345,345,345
BEGIN DESCRIPTION:
ALLIGATOR CREEK 2 2.0
END DESCRIPTION:
XS GIS Cut Line= 3
      2418875.01     13680425.00      2418575.00     13680575.00
      2418424.99     13681325.03
#Sta/Elev= 30
  4665.1  275.43  4756.2  273.16  4844.0  270.69  4874.7  267.77  4880.3  267.89
  4888.7  266.86  4919.5  265.33  4925.0  266.07  4941.8  264.91  4947.4  265.93
  4955.8  266.06  4964.2  264.93  4978.2  260.04  4982.9  259.62  4983.4  259.12
  4989.6  259.12  4990.1  259.62  4992.1  264.08  4997.7  266.08  5010.7  266.67
  5071.9  266.16  5161.4  268.52  5230.4  268.87  5316.7  269.09  5398.2  270.86
  5479.8  271.34  5490.0  272.12  5520.6  271.79  5612.4  274.15  5765.4  275.49
#Mann=6,-1,0
  4665.1    0.07       0  4756.2     0.1       0  4982.9    0.05       0
  4990.1     0.1       0  5161.4    0.12       0  5230.4    0.07       0
Bank Sta=4982.9,4990.1
Exp/Cntr=0.3,0.1

Type RM Length L Ch R = 1,2407,683,683,683
BEGIN DESCRIPTION:
ALLIGATOR CREEK 2 1.0
END DESCRIPTION:
XS GIS Cut Line= 3
      2418475.00     13680075.00      2418247.91     13680501.66
      2418288.55     13681296.99
#Sta/Elev= 30
  4594.2  275.52  4710.9  271.91  4728.5  270.85  4786.8  269.12  4822.1  265.87
  4860.3  264.84  4904.3  264.54  4956.7  265.68  4964.5  265.24  4979.4  262.38
  4982.8  259.45  4983.3  258.95  4989.6  258.95  4990.1  259.45  5002.0  262.60
  5008.5  264.93  5030.4  267.19  5052.4  266.73  5058.7  267.46  5074.4  266.81
  5204.4  267.63  5251.1  268.36  5301.2  268.37  5310.3  269.12  5351.2  268.81
  5361.2  269.35  5467.7  269.64  5731.7  271.61  5781.8  271.27  5873.9  271.81
#Mann=6,-1,0
  4594.2    0.07       0  4710.9     0.1       0  4982.8    0.05       0
  4990.1     0.1       0  5204.4    0.07       0  5467.7    0.12       0
Bank Sta=4982.8,4990.1
Exp/Cntr=0.3,0.1

Type RM Length L Ch R = 1,1724,0,0,0
BEGIN DESCRIPTION:
X18025
END DESCRIPTION:
XS GIS Cut Line= 4
      2418346.60     13679543.75      2417922.80     13679805.00
      2417829.92     13680519.07      2418270.59     13681417.82
#Sta/Elev= 30
  4380.4  276.77  4452.2  275.52  4494.0  275.24  4719.9  269.91  4795.9  265.70
  4848.0  263.98  4958.9  264.32  4969.0  263.01  4972.1  257.79  4972.6  257.29
  4979.4  257.79  4980.8  260.19  4989.2  263.76  4999.3  264.32  5079.9  263.17
  5109.0  263.97  5160.6  266.18  5213.1  266.18  5261.4  267.39  5615.9  268.35
  5666.4  269.40  5846.4  268.35  6003.9  270.50  6044.9  269.91  6083.5  269.78
  6295.5  269.40  6324.3  270.22  6436.8  270.33  6560.9  272.43  6599.3  273.32
#Mann=10,-1,0
  4380.4    0.07       0  4452.2    0.12       0  4494.0    0.07       0
  4719.9     0.1       0  4972.1    0.05       0  4979.4     0.1       0
  5109.0    0.12       0  6044.9    0.07       0  6083.5    0.12       0
  6560.9    0.07       0
Bank Sta=4972.1,4979.4
Exp/Cntr=0.3,0.1

Chan Stop Cuts=-1