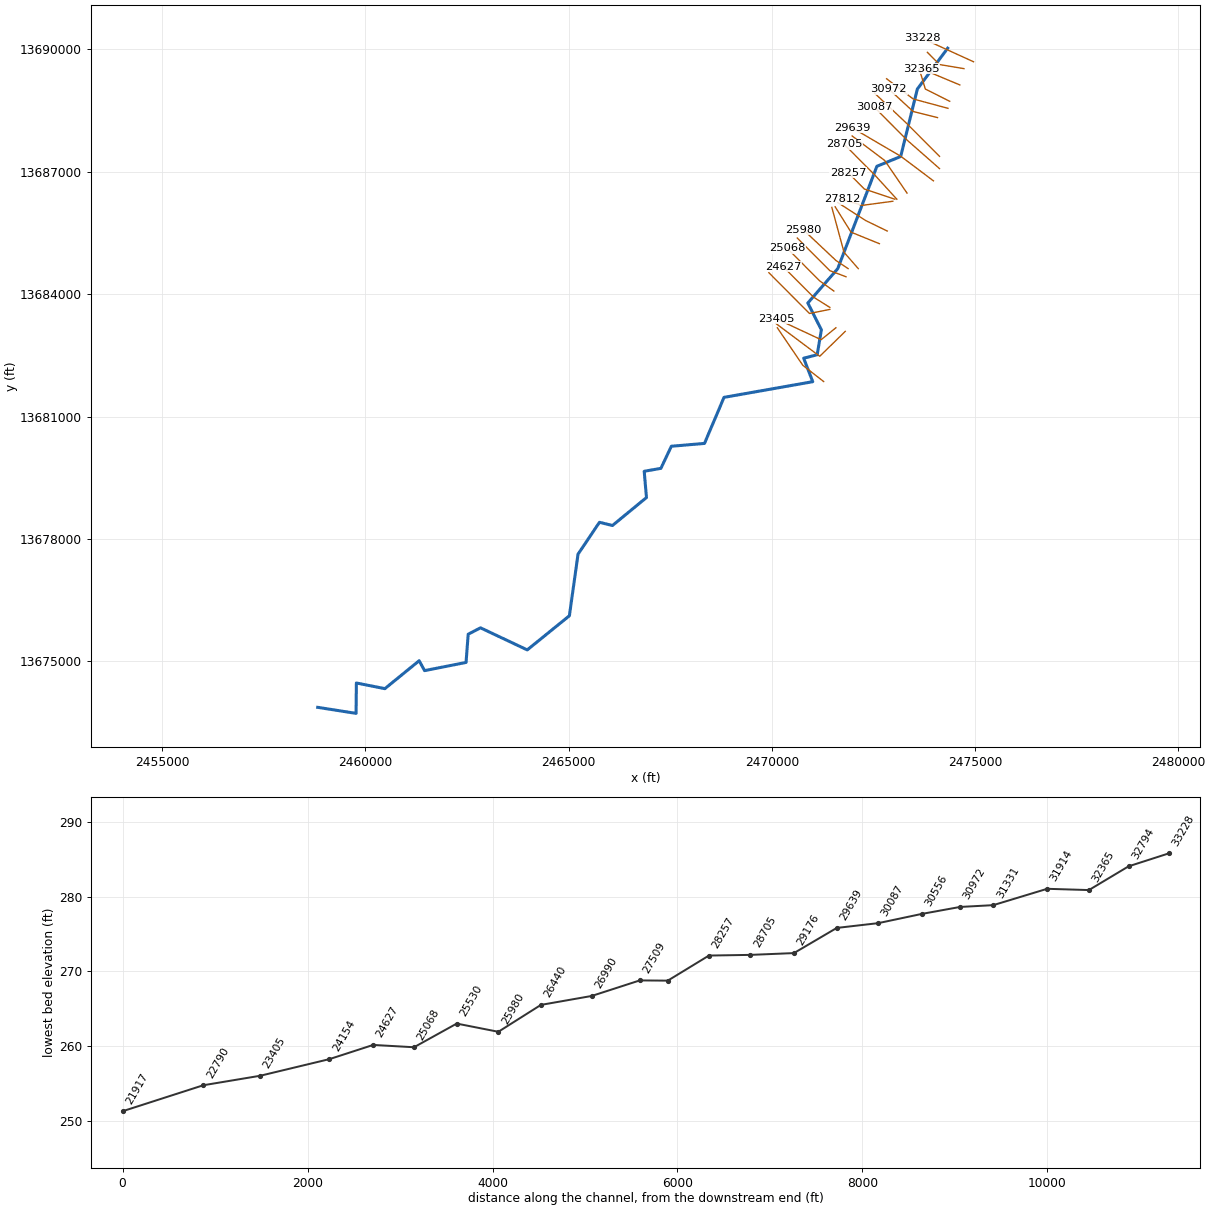
--- BRUSHY CREEK 2.prj (project) ---

Proj Title=BRUSHY CREEK 2 Base Level Engineering
Current Plan=p01
Default Exp/Contr=0.3,0.1
English Units
Geom File=g01
Flow File=f01
Plan File=p01
Y Axis Title=Elevation
X Axis Title(PF)=Main Channel Distance
X Axis Title(XS)=Station
BEGIN DESCRIPTION:
BRUSHY CREEK 2
END DESCRIPTION:
DSS Export Rating Curves= 0
DSS Export Rating Curve Sorted= 0
DSS Export Volume Flow Curves= 0
DXF OffsetX= 0
DXF OffsetY= 0
DXF ScaleX= 1
DXF ScaleY= 10

--- BRUSHY CREEK 2.p01 (plan) ---

Plan Title=Multiple Run
Program Version=4.10
Short Identifier=Multiple
Geom File=g01
Flow File=f01
Subcritical Flow
K Sum by GR= 0
Std Step Tol= 0.01
Critical Tol= 0.01
Num of Std Step Trials= 20
Max Error Tol= 0.3
Flow Tol Ratio= 0.001
Split Flow NTrial= 30
Split Flow Tol= 0.02
Split Flow Ratio= 0.02
Log Output Level= 0
Friction Slope Method= 1
Unsteady Friction Slope Method= 2
Unsteady Bridges Friction Slope Method= 1
Parabolic Critical Depth
Global Vel Dist= 1 , 1 , 1
Global Log Level= 0
CheckData=True
Encroach Param=-1 ,0,0, 0
BEGIN DESCRIPTION:
Multiple Run
END DESCRIPTION:
Computation Interval=1HOUR
Output Interval=1HOUR
Run HTab= 0
Run UNet= 0
Run PostProcess= 0
Run WQNet= 0
UNET Theta= 1
UNET Theta Warmup= 1
UNET ZTol= 0.02
UNET ZSATol= 0.05
UNET MxIter= 20
UNET MaxInSteps= 0
UNET DtIC= 0
UNET DtMin= 0
UNET MaxCRTS= 20
UNET WFStab= 2
UNET SFStab= 1
UNET WFX= 1
UNET SFX= 1
UNET DSS MLevel= 4
UNET DZMax Abort= 100
UNET Convert EG Bridges= 0
UNET Use Existing IB Tables=-1
UNET Froude Reduction=False
UNET Froude Limit= 1
UNET Froude Power= 10
UNET Time Slicing=0,0, 5
UNET Junction Losses=0
Instantaneous Interval=1HOUR
Write IC File= 0
Write IC File at Sim End=0
Echo Input=False
Echo Parameters=False
Echo Output=False
Write Detailed= 0
WQ AD Non Conservative
WQ ULTIMATE=-1
WQ Max Comp Step=1HOUR
WQ Output Interval=15MIN
WQ Output Selected Increments= 0
WQ Output face flow=0
WQ Output face velocity=0
WQ Output face area=0
WQ Output face dispersion=0
WQ Output cell volume=0
WQ Output cell surface area=0
WQ Output cell continuity=0
WQ Output cumulative cell continuity=0
WQ Output face conc=0
WQ Output face dconc_dx=0
WQ Output face courant=0
WQ Output face peclet=0
WQ Output face adv mass=0
WQ Output face disp mass=0
WQ Output cell mass=0
WQ Output cell source sink temp=0
WQ Output cell source sink nsm=0
WQ Output MaxMinRange=-1
WQ Daily Max Min Mean=-1
WQ Daily Range=0
WQ Daily Time=0
WQ Create Restart=0
WQ Fixed Restart=0
WQ System Summary=0
WQ Use Fixed Temperature=0
Sorting and Armoring Iterations= 10
XS Update Threshold= 0.02
Hydraulics Update Threshold= 0.02
Energy Slope Method= 1
Volume Change Method= 0
XS Weighting Method= 0
Number of US Weighted Cross Sections= 1
Number of DS Weighted Cross Sections= 1
Upstream XS Weight=0.25
Main XS Weight=0.5
Downstream XS Weight=0.25
Number of DS XS's Weighted with US Boundary= 1
Upstream Boundary Weight= 1
Weight of XSs Associated with US Boundary= 0
Number of US XS's Weighted with DS Boundary= 1
Downstream Boundary Weight= 0.5
Weight of XSs Associated with DS Boundary= 0.5
Sediment Output Level= 4
Mass or Volume Output= 0
Output Increment Type= 1
Profile and TS Output Increment= 10
XS Output Flag= 0
XS Output Increment= 10
Disregard all LS=0
Disregard all Conn=0
Disregard all Breaches=0
Disregard all Pumps=0

--- BRUSHY CREEK 2.f01 (steady flow) ---

Flow Title=Multiple
Number of Profiles=7
Profile Names=10-year,25-year,50-year,1pct_min,100-year,1pct_plu,500-year
River Rch & RM= BRUSHY CREEK 2,Reach-1,33228
     685    1096    1463     945    1885    3762    3101
River Rch & RM= BRUSHY CREEK 2,Reach-1,30556
     849    1367    1832    1186    2367    4722    3914
River Rch & RM= BRUSHY CREEK 2,Reach-1,21917
    1409    2326    3170    2084    4159    8298    7096
River Rch & RM= BRUSHY CREEK 2,Reach-1,18684
    1617    2683    3671    2422    4833    9643    8302
River Rch & RM= BRUSHY CREEK 2,Reach-1,17775
    1561    2580    3520    2315    4619    9216    7884
River Rch & RM= BRUSHY CREEK 2,Reach-1,15909
    1651    2733    3732    2457    4902    9781    8383
River Rch & RM= BRUSHY CREEK 2,Reach-1,14149
    1824    3020    4123    2712    5410   10795    9237
River Rch & RM= BRUSHY CREEK 2,Reach-1,9176
    1937    3214    4395    2895    5777   11526    9893
River Rch & RM= BRUSHY CREEK 2,Reach-1,5317
    2461    4111    5649    3735    7452   14869   12857
Boundary for River Rch & Prof#=BRUSHY CREEK 2,Reach-1,1
Up Type=0
Dn Type=3
Dn Slope=0.0009
Boundary for River Rch & Prof#=BRUSHY CREEK 2,Reach-1,2
Up Type=0
Dn Type=3
Dn Slope=0.0009
Boundary for River Rch & Prof#=BRUSHY CREEK 2,Reach-1,3
Up Type=0
Dn Type=3
Dn Slope=0.0009
Boundary for River Rch & Prof#=BRUSHY CREEK 2,Reach-1,4
Up Type=0
Dn Type=3
Dn Slope=0.0009
Boundary for River Rch & Prof#=BRUSHY CREEK 2,Reach-1,5
Up Type=0
Dn Type=3
Dn Slope=0.0009
Boundary for River Rch & Prof#=BRUSHY CREEK 2,Reach-1,6
Up Type=0
Dn Type=3
Dn Slope=0.0009
Boundary for River Rch & Prof#=BRUSHY CREEK 2,Reach-1,7
Up Type=0
Dn Type=3
Dn Slope=0.0009

--- BRUSHY CREEK 2.g01 (geometry) ---

Geom Title=Existing Conditions
Program Version=4.10

River Reach=BRUSHY CREEK 2  ,Reach-1
Reach XY= 30
        2474325.       13690025.      2473578.43     13689023.78
      2473169.28     13687372.42      2472583.14     13687131.06
       2471619.6     13684622.03      2470884.13     13683781.74
      2471217.93       13683125.      2471114.04     13682514.57
      2470782.47     13682428.62       2471005.4     13681853.94
      2468822.35     13681470.06      2468341.83     13680341.46
      2467526.67     13680271.99      2467269.39     13679730.59
      2466858.25     13679658.78      2466914.23     13679015.32
       2466077.3     13678330.09      2465757.83      13678408.9
      2465230.46     13677628.01      2465017.56     13676118.65
      2463981.34     13675282.36      2462830.93     13675822.76
      2462528.06     13675666.72        2462475.       13674975.
      2461454.37      13674774.4       2461321.6     13675017.22
      2460478.41     13674332.82      2459776.46     13674471.47
      2459769.31     13673726.87        2458825.       13673875.

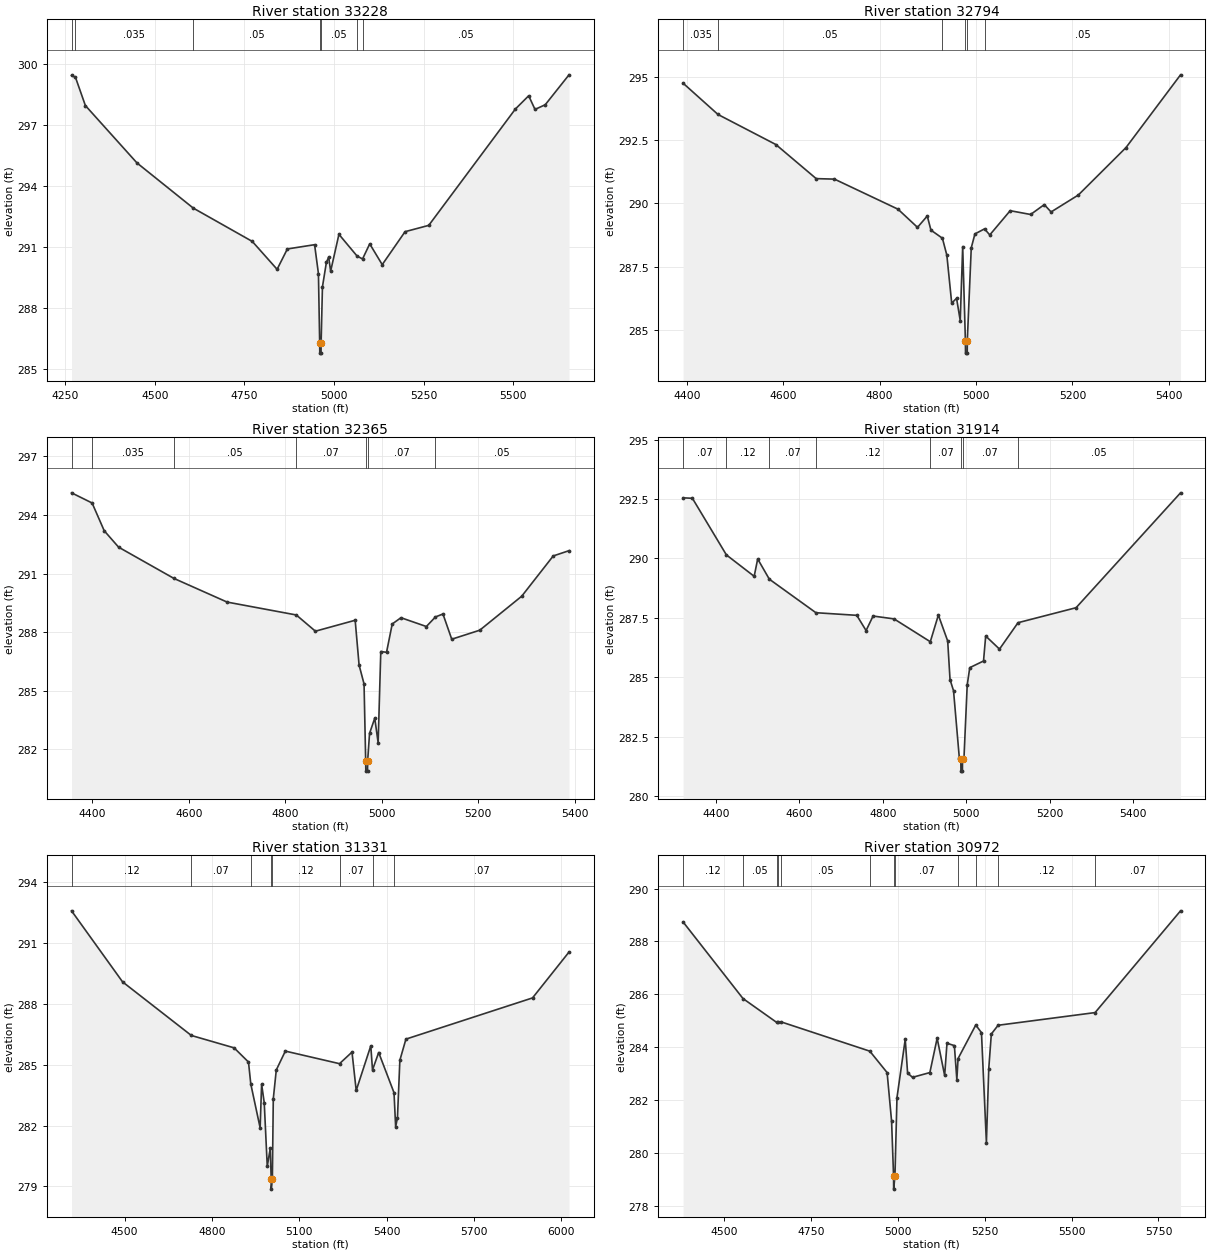
Type RM Length L Ch R = 1 ,33228   ,434,434,434
BEGIN DESCRIPTION:
X18350
END DESCRIPTION:
XS GIS Cut Line= 2
      2474962.29     13689692.77      2473698.79     13690267.09
#Sta/Elev= 30
  4267.8  299.45  4278.7  299.36  4306.4  297.97  4450.3  295.15  4607.3  292.93
  4772.1  291.29  4841.3  289.92  4869.9  290.92  4945.9  291.13  4956.6  289.71
  4960.1   286.3  4960.4   285.8  4963.9   285.8  4964.1   286.3  4967.8  289.06
  4978.8  290.26  4985.2  290.52  4990.7  289.83  5013.8  291.64  5064.5  290.57
  5079.7  290.43  5099.7  291.17  5134.6  290.15  5198.3  291.77  5264.4  292.08
  5506.1   297.8  5543.2  298.45  5560.8  297.78  5589.4  298.01  5655.7  299.48
#Mann= 7 ,-1 , 0
  4267.8     .07       0  4278.7    .035       0  4607.3     .05       0
  4960.1     .05       0  4964.1     .05       0  5064.5     .07       0
  5079.7     .05       0
Bank Sta=4960.1,4964.1
XS Rating Curve= 0 ,0
Exp/Cntr=0.3,0.1

Type RM Length L Ch R = 1 ,32794   ,429,429,429
BEGIN DESCRIPTION:
BRUSHY CREEK 2 45.0
END DESCRIPTION:
XS GIS Cut Line= 3
      2474725.02       13689525.        2474125.       13689625.
      2473824.97     13689925.03
#Sta/Elev= 30
  4391.9  294.76  4464.4  293.52  4584.5  292.33  4668.2  290.98  4706.2  290.96
    4838  289.77  4878.5  289.05  4898.8   289.5  4906.4  288.94  4930.2  288.62
  4939.4  287.95  4949.5  286.05  4959.6  286.24  4967.2  285.36  4972.3  288.29
  4977.9  284.57  4978.2  284.07  4981.7  284.07  4981.9  284.57  4990.1  288.24
  4997.7  288.79  5017.6  288.99  5028.5  288.75  5070.9  289.71  5113.3  289.56
  5141.6  289.95  5155.8  289.66  5212.3  290.33  5311.3  292.21  5424.5  295.09
#Mann= 6 ,-1 , 0
  4391.9    .035       0  4464.4     .05       0  4930.2     .07       0
  4977.9     .05       0  4981.9     .07       0  5017.6     .05       0
Bank Sta=4977.9,4981.9
XS Rating Curve= 0 ,0
Exp/Cntr=0.3,0.1

Type RM Length L Ch R = 1 ,32365   ,451,451,451
BEGIN DESCRIPTION:
BRUSHY CREEK 2 44.0
END DESCRIPTION:
XS GIS Cut Line= 3
      2474624.97     13689125.01        2474025.       13689375.
      2473674.96     13689525.02
#Sta/Elev= 30
  4357.1  295.13  4399.7  294.61  4424.8  293.19  4454.6  292.35  4569.3  290.75
  4679.4  289.54  4822.8  288.88  4862.4  288.05  4944.8  288.61  4952.9  286.32
  4963.2  285.35  4966.6  281.39  4966.9  280.89  4970.4  280.89  4970.6  281.39
  4974.6  282.82  4985.4   283.6  4992.4  282.34  4997.9  287.01  5009.8  286.97
  5021.6  288.42  5039.7  288.74  5092.3  288.29  5111.2  288.78  5126.7  288.93
  5144.9  287.64  5202.9   288.1  5289.9  289.84  5355.2   291.9  5387.9  292.17
#Mann= 7 ,-1 , 0
  4357.1     .07       0  4399.7    .035       0  4569.3     .05       0
  4822.8     .07       0  4966.6     .05       0  4970.6     .07       0
  5111.2     .05       0
Bank Sta=4966.6,4970.6
XS Rating Curve= 0 ,0
Exp/Cntr=0.3,0.1

Type RM Length L Ch R = 1 ,31914   ,583,583,583
BEGIN DESCRIPTION:
BRUSHY CREEK 2 43.0
END DESCRIPTION:
XS GIS Cut Line= 3
      2474375.01     13688724.99        2473775.       13689025.
      2473625.01     13689524.95
#Sta/Elev= 30
  4321.1  292.55  4343.5  292.53    4425  290.15  4491.6  289.25    4500  289.98
  4527.9  289.13  4639.6  287.72  4737.6  287.61  4759.9  286.97  4776.7  287.58
    4827  287.46  4913.9   286.5  4933.2  287.62  4955.6  286.53  4961.2  284.91
  4969.6  284.44  4983.5  281.61  4987.1  281.56  4987.4  281.06  4990.9  281.06
  4991.1  281.56  4994.5  281.56  5002.4  284.68  5008.5  285.41  5041.5  285.69
  5046.7  286.74  5079.8  286.19  5124.2   287.3  5263.4  287.93  5513.9  292.76
#Mann= 8 ,-1 , 0
  4321.1     .07       0    4425     .12       0  4527.9     .07       0
  4639.6     .12       0  4913.9     .07       0  4987.1     .05       0
  4991.1     .07       0  5124.2     .05       0
Bank Sta=4987.1,4991.1
XS Rating Curve= 0 ,0
Exp/Cntr=0.3,0.1

Type RM Length L Ch R = 1 ,31331   ,359,359,359
BEGIN DESCRIPTION:
X18349
END DESCRIPTION:
XS GIS Cut Line= 3
      2474334.36     13688551.93      2473476.54     13688781.87
      2472822.11     13689277.11
#Sta/Elev= 30
  4317.9  292.58  4493.2  289.08  4729.4  286.44  4876.3  285.83  4925.7  285.13
  4933.6  284.05  4965.7  281.89  4970.8  284.04  4979.8  283.13  4990.2  279.99
  5000.5  280.88  5003.7  279.37  5003.9  278.87  5007.7  279.37  5010.9  283.32
  5021.2  284.74  5052.3  285.67  5238.4  285.05  5281.3  285.62  5295.7  283.73
  5345.8  285.93  5351.7  284.74  5372.9   285.6  5425.6  283.62  5431.2  281.94
  5437.4  282.38  5445.7  285.22  5466.5  286.26  5901.4  288.29  6026.7  290.55
#Mann= 8 ,-1 , 0
  4317.9     .12       0  4729.4     .07       0  4933.6     .12       0
  5003.7     .05       0  5007.7     .12       0  5238.4     .07       0
  5351.7     .12       0  5425.6     .07       0
Bank Sta=5003.7,5007.7
XS Rating Curve= 0 ,0
Exp/Cntr=0.3,0.1

Type RM Length L Ch R = 1 ,30972   ,416,416,416
BEGIN DESCRIPTION:
BRUSHY CREEK 2 42.0
END DESCRIPTION:
XS GIS Cut Line= 3
      2474074.97     13688325.01        2473475.       13688475.
      2472874.98     13689025.02
#Sta/Elev= 30
  4381.2  288.74  4553.8  285.84  4650.5  284.94  4655.6  284.95    4663  284.96
  4918.9  283.85  4968.7  283.04  4981.6   281.2  4987.3  279.13  4987.6  278.63
  4991.3  279.13  4997.1  282.09  5020.9   284.3  5027.7  283.02  5041.9  282.86
  5091.8  283.04  5112.8  284.34  5134.4  282.93  5141.1  284.15  5162.4  284.06
  5169.5  282.77    5173  283.57    5224  284.84  5240.4  284.55  5254.6  280.39
  5261.4  283.19  5268.8   284.5  5288.3  284.83  5567.6  285.31  5813.6  289.16
#Mann= 12 ,-1 , 0
  4381.2     .12       0  4553.8     .05       0  4650.5     .12       0
  4655.6     .07       0    4663     .05       0  4918.9     .07       0
  4987.3     .05       0  4991.3     .07       0    5173     .12       0
    5224     .05       0  5288.3     .12       0  5567.6     .07       0
Bank Sta=4987.3,4991.3
XS Rating Curve= 0 ,0
Exp/Cntr=0.3,0.1

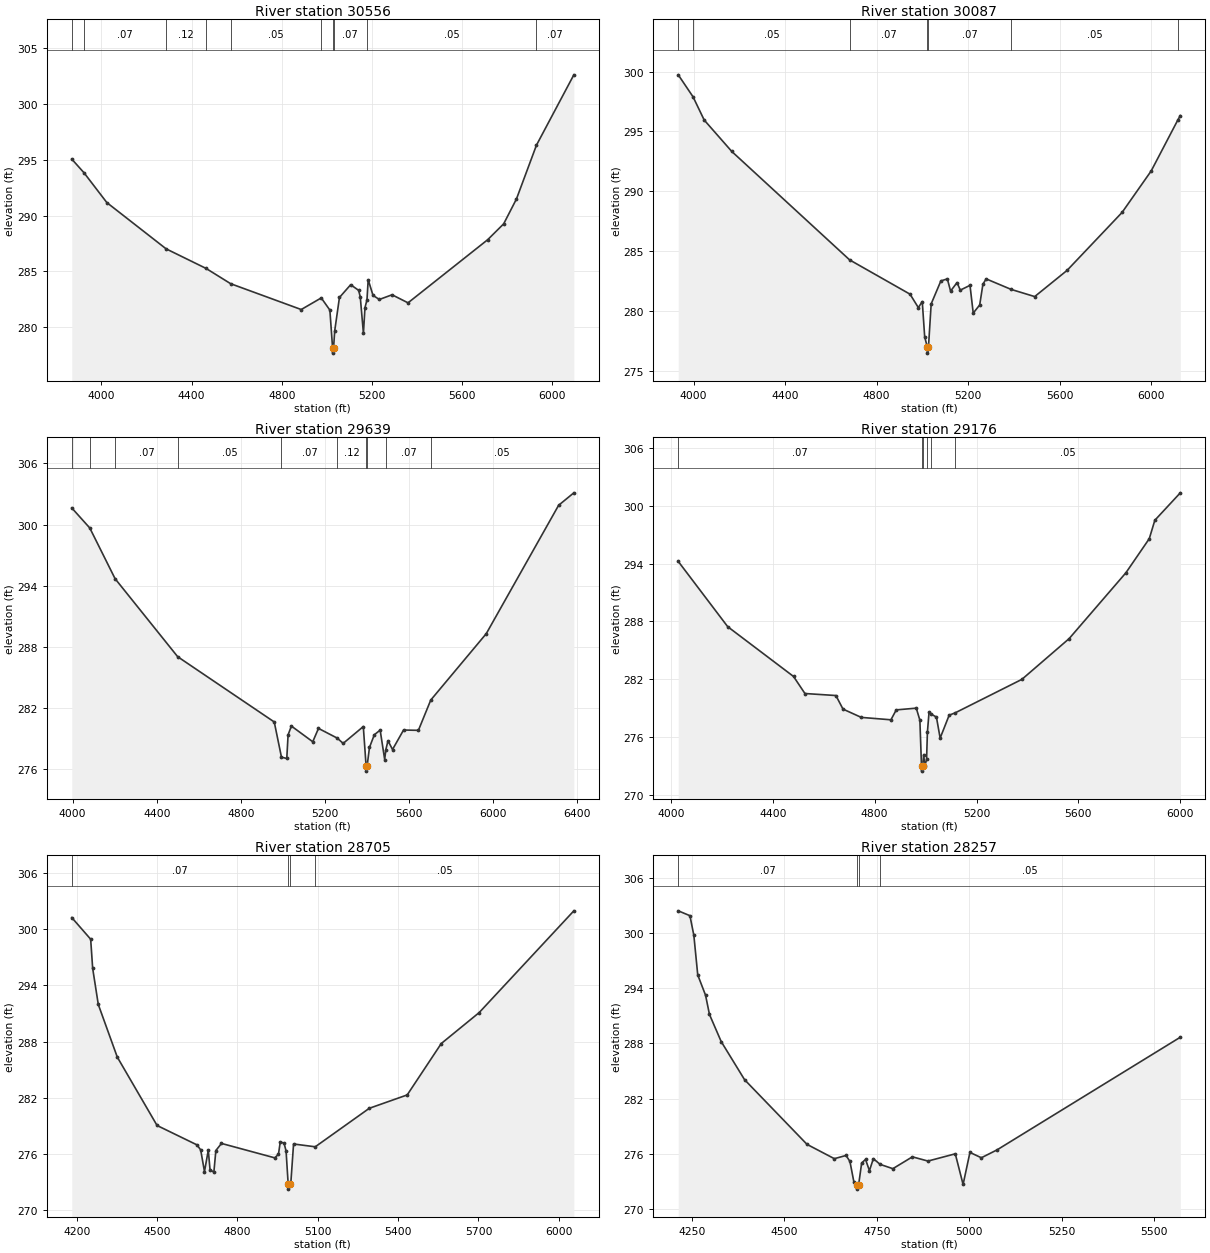
Type RM Length L Ch R = 1 ,30556   ,469,469,469
BEGIN DESCRIPTION:
BRUSHY CREEK 2 41.0
END DESCRIPTION:
XS GIS Cut Line= 3
      2474124.99     13687375.01        2473325.       13688175.
      2472525.03     13688924.97
#Sta/Elev= 30
  3868.4  295.05  3922.6  293.83    4024  291.16  4287.1  287.02  4464.2  285.27
  4573.6   283.9  4886.6  281.59  4975.5  282.63  5013.7  281.54  5025.6  278.19
  5025.9  277.69  5030.2  278.19  5035.2  279.69  5056.2  282.67    5106  283.81
  5141.2  283.31  5148.5  282.73  5162.6  279.46  5169.5  281.76  5178.4  282.46
  5183.7  284.26  5205.1  282.86    5233  282.49  5289.7  282.91  5360.5  282.19
  5714.1  287.84    5785  289.26  5841.6  291.48  5930.5   296.3  6096.3  302.59
#Mann= 10 ,-1 , 0
  3868.4    .035       0  3922.6     .07       0  4287.1     .12       0
  4464.2     .07       0  4573.6     .05       0  4975.5     .07       0
  5025.6     .05       0  5030.2     .07       0  5178.4     .05       0
  5930.5     .07       0
Bank Sta=5025.6,5030.2
XS Rating Curve= 0 ,0
Exp/Cntr=0.3,0.1

Type RM Length L Ch R = 1 ,30087   ,448,448,448
BEGIN DESCRIPTION:
BRUSHY CREEK 2 40.0
END DESCRIPTION:
XS GIS Cut Line= 3
      2474125.02     13687074.98        2473325.       13687775.
      2472525.01     13688574.99
#Sta/Elev= 30
  3932.8  299.74  3997.5   297.9  4046.2  295.96  4166.8  293.33  4681.8  284.26
    4946  281.39  4982.1  280.27  4999.4  280.77    5010  277.81  5021.7  276.96
  5022.1  276.46  5026.5  276.96  5038.3  280.58  5080.7   282.5    5109  282.67
  5123.1  281.65  5151.4  282.36  5165.5  281.73    5208  282.13  5222.1  279.81
  5250.4  280.49  5264.5  282.23  5278.7  282.67  5387.9  281.79  5490.8  281.19
  5632.2  283.38  5872.7  288.23  5999.9   291.7  6117.1  295.99  6127.2  296.33
#Mann= 7 ,-1 , 0
  3932.8    .035       0  3997.5     .05       0  4681.8     .07       0
  5021.7     .05       0  5026.5     .07       0  5387.9     .05       0
  6117.1    .035       0
Bank Sta=5021.7,5026.5
XS Rating Curve= 0 ,0
Exp/Cntr=0.3,0.1

Type RM Length L Ch R = 1 ,29639   ,463,463,463
BEGIN DESCRIPTION:
BRUSHY CREEK 2 39.0
END DESCRIPTION:
XS GIS Cut Line= 3
      2473975.01     13686774.99        2473175.       13687375.
      2471974.96     13688075.02
#Sta/Elev= 30
  3995.8  301.63  4081.6  299.66  4201.9  294.69  4499.8  287.04  4959.4  280.64
  4993.7  277.19    5019  277.06  5025.2  279.37  5040.9  280.24  5142.6   278.7
  5169.9  280.01  5258.9  279.06  5287.3  278.54  5383.2  280.19  5396.5  276.32
  5396.9  275.82  5401.3  276.32  5412.6  278.15  5435.7  279.39  5463.4  279.84
  5484.9  276.96  5490.6  277.94  5500.7   278.8  5522.2  277.94  5574.7  279.85
  5645.4  279.82  5704.2  282.79  5968.3   289.3  6312.7  301.89  6385.1  303.11
#Mann= 10 ,-1 , 0
  3995.8     .07       0  4081.6     .12       0  4201.9     .07       0
  4499.8     .05       0  4993.7     .07       0  5258.9     .12       0
  5396.5     .05       0  5401.3     .12       0  5490.6     .07       0
  5704.2     .05       0
Bank Sta=5396.5,5401.3
XS Rating Curve= 0 ,0
Exp/Cntr=0.3,0.1

Type RM Length L Ch R = 1 ,29176   ,471,471,471
BEGIN DESCRIPTION:
BRUSHY CREEK 2 38.0
END DESCRIPTION:
XS GIS Cut Line= 3
        2473325.       13686475.        2472775.       13687275.
      2471975.02     13687874.98
#Sta/Elev= 30
  4029.1  294.23  4223.3  287.45  4481.7  282.28  4526.4  280.51    4648   280.3
  4675.9  278.89  4747.6  278.03    4864  277.78  4884.9  278.81  4963.5  278.99
  4977.6  277.74    4984  272.95  4984.3  272.45  4988.9  272.95  4992.5  274.17
  4996.9  272.97  5003.9  273.66  5007.2   276.5  5013.5  278.54  5022.2  278.37
  5042.6  278.06  5057.2  275.88  5092.6  278.26    5116   278.5  5378.1  281.98
  5563.5  286.21  5786.4  293.05  5878.1  296.59  5899.9   298.5  5999.9  301.35
#Mann= 6 ,-1 , 0
  4029.1     .07       0    4984     .05       0  4988.9     .07       0
  5003.9     .05       0  5022.2     .07       0    5116     .05       0
Bank Sta=4984,4988.9
XS Rating Curve= 0 ,0
Exp/Cntr=0.3,0.1

Type RM Length L Ch R = 1 ,28705   ,448,448,448
BEGIN DESCRIPTION:
BRUSHY CREEK 2 37.0
END DESCRIPTION:
XS GIS Cut Line= 3
      2473075.02     13686324.98        2472525.       13686925.
      2471775.02     13687674.98
#Sta/Elev= 30
  4181.4  301.27    4252  298.95  4259.4  295.84  4280.4  291.97  4351.3  286.34
  4499.9  279.02  4648.5  276.95  4662.7  276.41  4676.9  274.09  4691.1  276.37
  4697.8  274.25    4712  274.04  4719.4  276.34  4740.4   277.1  4938.9  275.56
  4953.1  275.93  4959.9  277.27  4974.1  277.12  4981.5   276.3  4989.5  272.71
  4989.9  272.21  4994.5  272.71  4998.9  272.71  5009.5  277.04  5090.5  276.74
  5292.3  280.86  5433.8  282.29    5561  287.79  5702.5   291.1    6056  301.99
#Mann= 4 ,-1 , 0
  4181.4     .07       0  4989.5     .05       0  4994.5     .07       0
  5090.5     .05       0
Bank Sta=4989.5,4994.5
XS Rating Curve= 0 ,0
Exp/Cntr=0.3,0.1

Type RM Length L Ch R = 1 ,28257   ,445,445,445
BEGIN DESCRIPTION:
BRUSHY CREEK 2 36.0
END DESCRIPTION:
XS GIS Cut Line= 3
      2473025.03     13686324.99        2472275.       13686575.
      2471874.99     13686975.01
#Sta/Elev= 30
  4213.7  302.46  4245.3  301.93  4255.9  299.78  4266.4  295.47  4287.5  293.26
  4298.1  291.16  4329.7  288.21  4392.9  284.05  4561.6     277  4635.4  275.44
    4667  275.79  4677.5  275.14  4688.1  272.92  4696.1  272.62  4696.5  272.12
  4701.1  272.62  4709.2  274.97  4719.7  275.36  4730.2  274.13  4740.8  275.44
    4759  274.82  4793.5  274.35  4846.2  275.64  4888.3  275.18  4962.1  275.97
  4983.2  272.63  5001.7  276.12  5032.6  275.54    5075   276.4    5570  288.68
#Mann= 4 ,-1 , 0
  4213.7     .07       0  4696.1     .05       0  4701.1     .07       0
    4759     .05       0
Bank Sta=4696.1,4701.1
XS Rating Curve= 0 ,0
Exp/Cntr=0.3,0.1

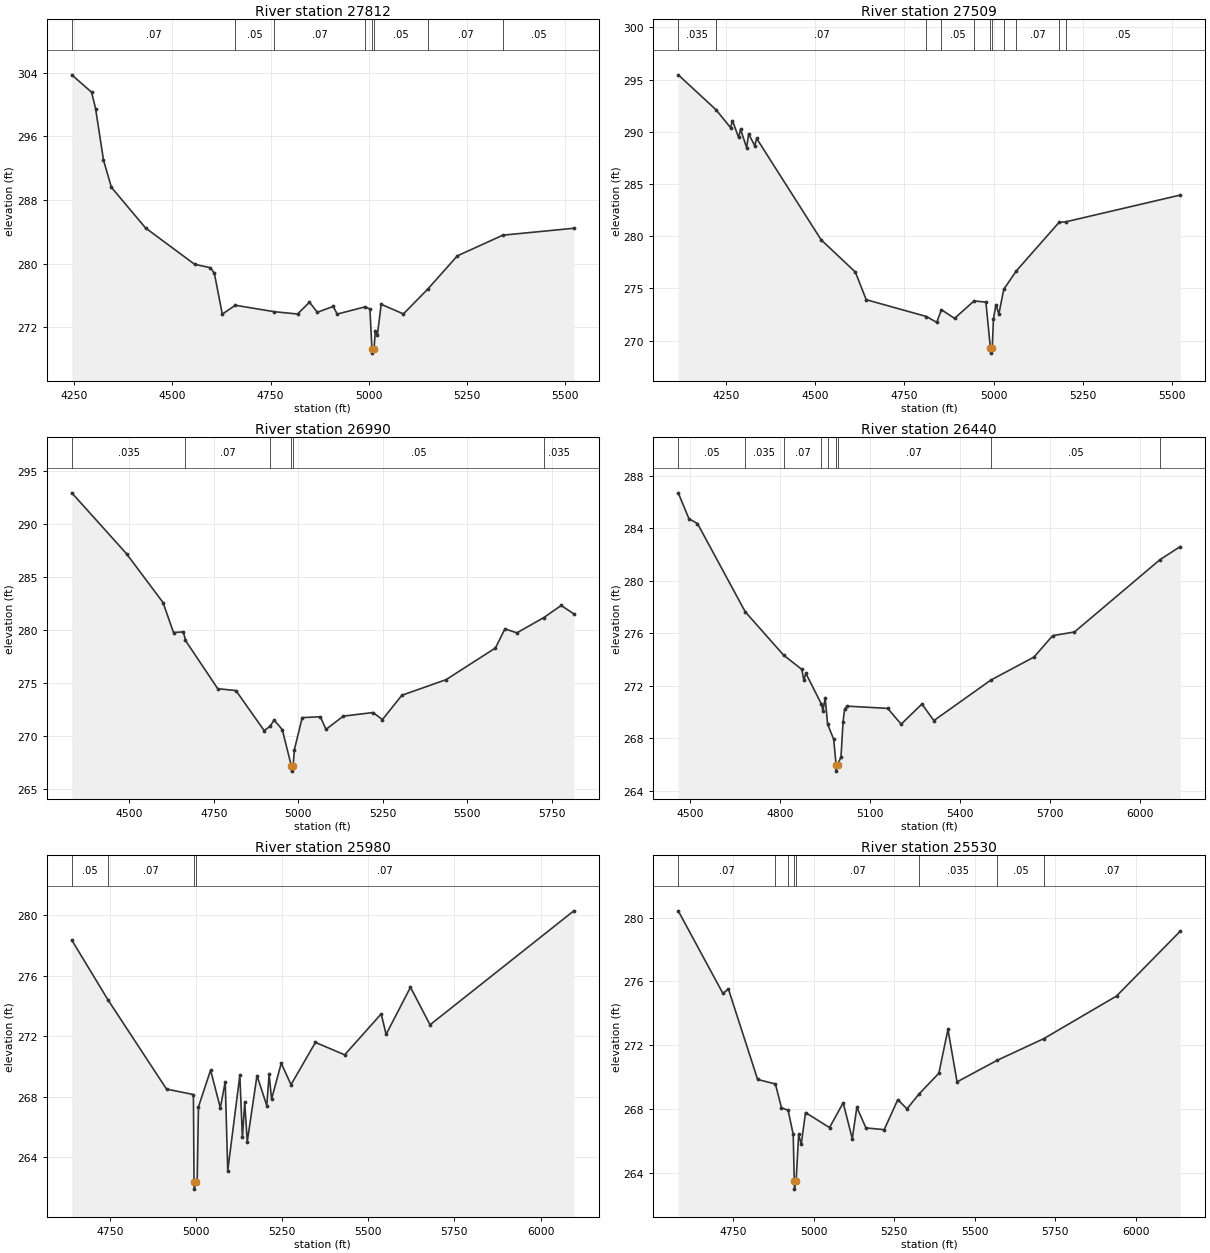
Type RM Length L Ch R = 1 ,27812   ,303,303,303
BEGIN DESCRIPTION:
BRUSHY CREEK 2 35.0
END DESCRIPTION:
XS GIS Cut Line= 3
      2472975.05     13686275.01        2472225.       13686175.
        2471725.       13686325.
#Sta/Elev= 30
  4243.5  303.75    4294  301.56  4304.1  299.51  4324.3  293.04  4344.4  289.61
  4431.4   284.5  4556.3  279.93  4596.6   279.5  4606.7  278.79  4626.9  273.66
    4660  274.78  4758.8  273.97  4818.6  273.68  4848.9  275.16    4869   273.9
  4909.4  274.63  4919.5  273.67  4990.7  274.58  5002.8   274.3    5008  269.26
  5008.4  268.76  5013.2  269.26  5016.7   271.6  5021.9  271.06  5031.5   274.9
  5088.1  273.69  5150.9  276.85  5225.5  280.99  5341.4  283.59  5522.2  284.46
#Mann= 8 ,-1 , 0
  4243.5     .07       0    4660     .05       0  4758.8     .07       0
  4990.7     .05       0    5008     .05       0  5013.2     .05       0
  5150.9     .07       0  5341.4     .05       0
Bank Sta=5008,5013.2
XS Rating Curve= 0 ,0
Exp/Cntr=0.3,0.1

Type RM Length L Ch R = 1 ,27509   ,519,519,519
BEGIN DESCRIPTION:
X18348
END DESCRIPTION:
XS GIS Cut Line= 3
      2472839.78     13685545.05      2472309.16     13685801.52
       2471619.7     13686243.48
#Sta/Elev= 30
  4115.4  295.46  4222.1  292.09  4262.1   290.4  4267.6  291.06  4284.7  289.46
  4290.2  290.24  4307.3  288.48  4312.8  289.81  4329.9  288.67  4335.4  289.36
  4516.2  279.65  4612.2  276.56  4642.7  273.91  4811.7   272.3  4840.4  271.74
  4853.8  272.95  4890.5  272.12  4945.1  273.79  4978.4  273.68    4991  269.29
  4991.4  268.79  4996.2  269.29  4999.6  272.08  5006.6  273.42  5014.8  272.54
  5028.5  274.91  5064.2  276.69  5183.3  281.31  5203.2  281.38  5523.7  283.94
#Mann= 11 ,-1 , 0
  4115.4    .035       0  4222.1     .07       0  4811.7    .035       0
  4853.8     .05       0  4945.1     .07       0    4991     .05       0
  4996.2     .07       0  5028.5     .05       0  5064.2     .07       0
  5183.3    .035       0  5203.2     .05       0
Bank Sta=4991,4996.2
XS Rating Curve= 0 ,0
Exp/Cntr=0.3,0.1

Type RM Length L Ch R = 1 ,26990   ,550,550,550
BEGIN DESCRIPTION:
BRUSHY CREEK 2 34.0
END DESCRIPTION:
XS GIS Cut Line= 3
      2472645.19     13685235.53      2471946.57     13685518.52
      2471557.42     13686137.61
#Sta/Elev= 30
  4330.1  292.97  4492.1  287.22    4600  282.62    4631  279.79  4660.5  279.85
  4666.4  279.04  4761.9  274.49  4815.8  274.31    4899  270.54  4916.4  270.93
  4928.6  271.53  4952.7  270.63  4979.5  267.21    4980  266.71  4984.8  267.21
  4988.4  268.72  5011.7  271.76  5065.3  271.84    5082  270.65  5133.3   271.9
  5221.4  272.24  5248.8  271.57  5306.5  273.87  5437.2  275.34  5583.2  278.33
  5611.2  280.13  5646.8  279.76  5726.3   281.2  5777.6  282.34  5815.1  281.55
#Mann= 6 ,-1 , 0
  4330.1    .035       0  4666.4     .07       0  4916.4     .05       0
  4979.5     .05       0  4984.8     .05       0  5726.3    .035       0
Bank Sta=4979.5,4984.8
XS Rating Curve= 0 ,0
Exp/Cntr=0.3,0.1

Type RM Length L Ch R = 1 ,26440   ,460,460,460
BEGIN DESCRIPTION:
BRUSHY CREEK 2 33.0
END DESCRIPTION:
XS GIS Cut Line= 3
      2472124.99     13684625.01        2471775.       13685025.
      2471474.99     13686125.03
#Sta/Elev= 30
  4461.7  286.71  4497.3  284.74  4525.8  284.37  4684.7  277.65  4812.4  274.35
  4873.1  273.26  4879.8  272.45  4886.9  272.95  4938.1  270.63  4943.4  270.12
    4951  271.07  4959.1  269.08  4979.4  267.93  4987.2  266.01  4987.6  265.51
  4992.5  266.01  5003.6  266.59  5010.5  269.29  5015.7  270.24  5024.3  270.46
    5159  270.29    5204  269.09  5273.1  270.62  5312.8  269.36  5502.9  272.45
  5646.2   274.2  5708.4  275.83    5781  276.11  6065.2  281.61  6133.4  282.62
#Mann= 9 ,-1 , 0
  4461.7     .05       0  4684.7    .035       0  4812.4     .07       0
  4938.1    .035       0  4959.1     .07       0  4987.2     .05       0
  4992.5     .07       0  5502.9     .05       0  6065.2     .07       0
Bank Sta=4987.2,4992.5
XS Rating Curve= 0 ,0
Exp/Cntr=0.3,0.1

Type RM Length L Ch R = 1 ,25980   ,450,450,450
BEGIN DESCRIPTION:
BRUSHY CREEK 2 32.0
END DESCRIPTION:
XS GIS Cut Line= 3
      2471875.03     13684624.98        2471575.       13684825.
      2470774.98     13685575.01
#Sta/Elev= 30
  4639.4  278.34  4744.4   274.4  4914.4  268.51  4992.5  268.15  4994.2  262.41
  4994.6  261.91  4999.8  262.41  5003.4  262.41  5007.1  267.34  5042.3  269.76
  5070.6  267.27  5084.8     269  5092.1  263.13  5127.2  269.42  5134.6  265.32
  5141.4  267.65  5148.7  265.04    5177   269.4  5205.4  267.42  5212.2  269.49
  5219.3  267.85  5247.4  270.22  5275.7   268.8  5346.6  271.59  5431.5  270.77
  5537.5  273.47  5551.7  272.12  5622.5  275.23  5679.2  272.75  6096.6  280.27
#Mann= 4 ,-1 , 0
  4639.4     .05       0  4744.4     .07       0  4994.2     .05       0
  4999.8     .07       0
Bank Sta=4994.2,4999.8
XS Rating Curve= 0 ,0
Exp/Cntr=0.3,0.1

Type RM Length L Ch R = 1 ,25530   ,462,462,462
BEGIN DESCRIPTION:
BRUSHY CREEK 2 31.0
END DESCRIPTION:
XS GIS Cut Line= 3
      2471824.98     13684425.01        2471425.       13684575.
      2470624.96     13685375.04
#Sta/Elev= 30
  4579.4  280.42  4718.2  275.25  4735.1  275.53  4825.9  269.87    4881  269.59
  4899.8  268.11  4920.5  267.94  4936.3  266.44  4939.6  263.51  4940.1  263.01
  4945.3  263.51  4953.2  266.43  4961.2  265.81  4974.5   267.8    5049  266.86
  5091.4  268.41  5119.7  266.16  5133.9  268.13  5162.1  266.84  5218.7  266.73
  5261.1  268.61  5289.4  268.03  5327.3  268.97  5388.4  270.26  5416.7     273
    5445  269.72  5569.6  271.07  5713.8  272.42    5940  275.09    6138  279.15
#Mann= 8 ,-1 , 0
  4579.4     .07       0    4881     .12       0  4920.5     .07       0
  4939.6     .05       0  4945.3     .07       0  5327.3    .035       0
  5569.6     .05       0  5713.8     .07       0
Bank Sta=4939.6,4945.3
XS Rating Curve= 0 ,0
Exp/Cntr=0.3,0.1

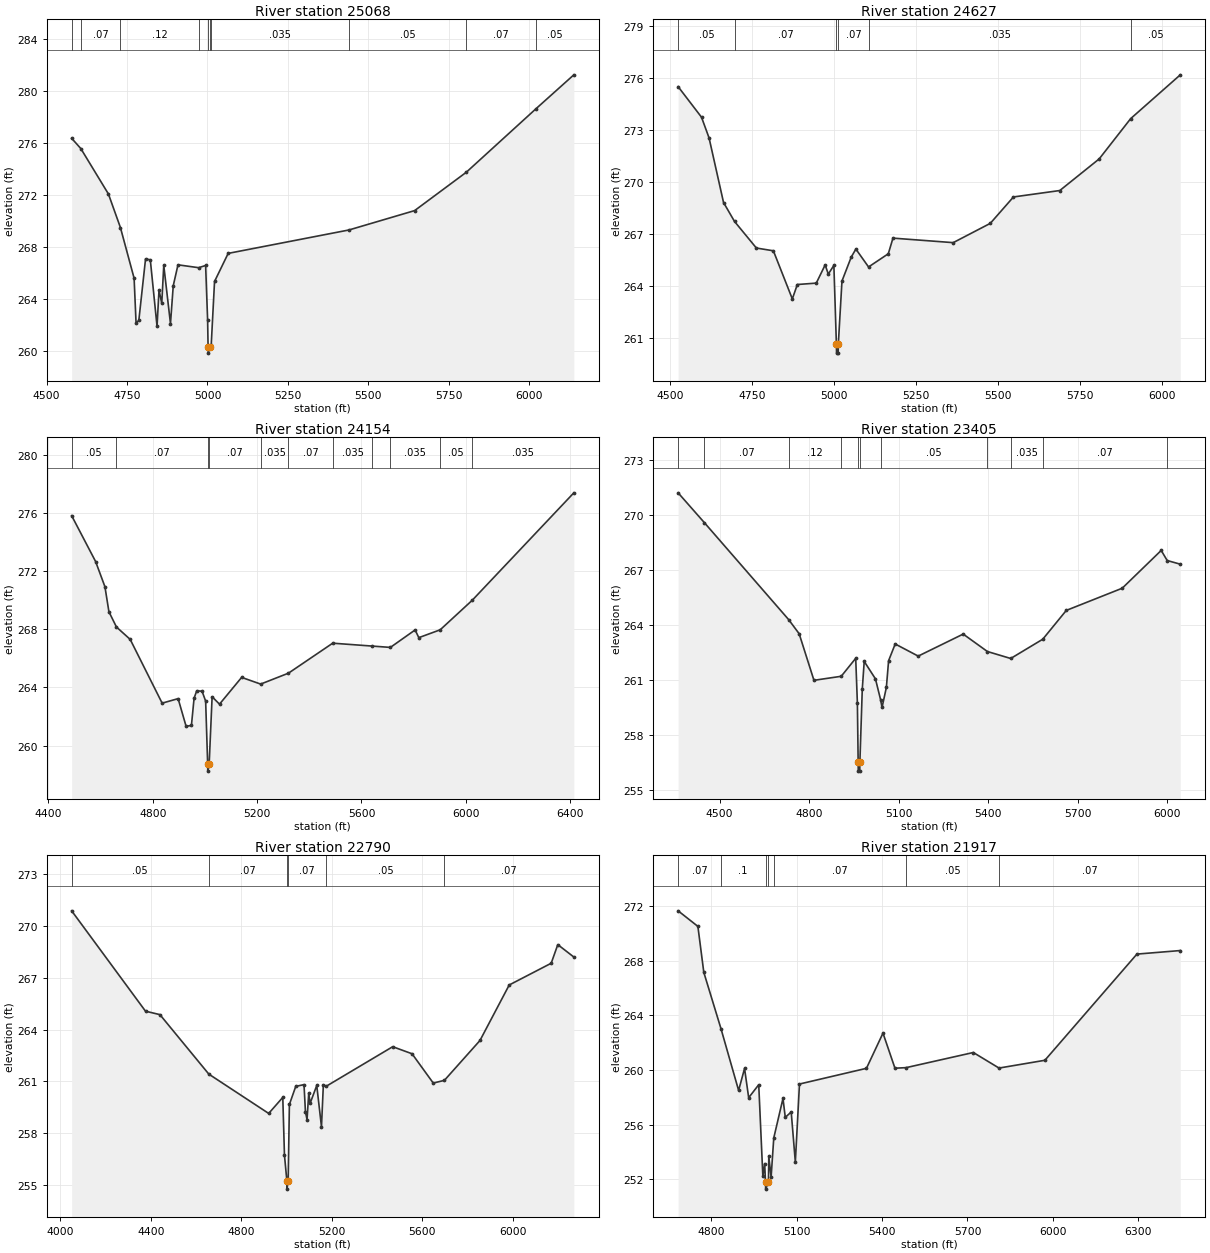
Type RM Length L Ch R = 1 ,25068   ,441,441,441
BEGIN DESCRIPTION:
BRUSHY CREEK 2 30.0
END DESCRIPTION:
XS GIS Cut Line= 3
      2471525.02     13684074.98        2471175.       13684325.
      2470375.01     13685124.99
#Sta/Elev= 30
  4577.7  276.36  4606.2  275.57    4692  272.08  4729.3   269.5  4771.9   265.6
    4778  262.14  4786.6  262.36  4807.5  267.09  4822.3  267.01  4843.2   261.9
  4849.3  264.68  4857.9  263.68  4864.1  266.59    4885  262.11  4893.6  265.02
  4908.3  266.63  4972.6  266.41  4994.3  266.58  5000.5  262.37  5001.9  260.34
  5002.4  259.84  5007.6  260.34  5011.6  260.43    5022  265.35  5064.4  267.51
  5439.9  269.31  5644.2   270.8  5804.9  273.75  6020.5  278.61  6139.2  281.24
#Mann= 10 ,-1 , 0
  4577.7     .05       0  4606.2     .07       0  4729.3     .12       0
  4972.6     .07       0  5001.9     .05       0  5007.6     .07       0
  5011.6    .035       0  5439.9     .05       0  5804.9     .07       0
  6020.5     .05       0
Bank Sta=5001.9,5007.6
XS Rating Curve= 0 ,0
Exp/Cntr=0.3,0.1

Type RM Length L Ch R = 1 ,24627   ,473,473,473
BEGIN DESCRIPTION:
BRUSHY CREEK 2 29.0
END DESCRIPTION:
XS GIS Cut Line= 3
      2471425.03     13683674.98        2471025.       13683925.
        2470275.       13684675.
#Sta/Elev= 30
  4523.9  275.49  4595.3  273.73  4618.3  272.54  4662.5  268.82    4696  267.73
  4762.7   266.2  4814.6  266.04  4872.4  263.27  4887.7   264.1  4945.5  264.18
  4972.6  265.23  4982.1   264.7  4999.2   265.2  5006.9  260.65  5007.4  260.15
  5012.2  260.15  5012.7  260.65  5023.9   264.3  5052.2  265.68  5066.3  266.14
    5105  265.11  5165.3  265.87  5179.5  266.77  5363.3  266.51  5476.5  267.62
  5547.2  269.14  5688.6  269.51  5808.8  271.33  5904.9  273.65  6056.3  276.17
#Mann= 6 ,-1 , 0
  4523.9     .05       0    4696     .07       0  5006.9     .05       0
  5012.7     .07       0    5105    .035       0  5904.9     .05       0
Bank Sta=5006.9,5012.7
XS Rating Curve= 0 ,0
Exp/Cntr=0.3,0.1

Type RM Length L Ch R = 1 ,24154   ,749,749,749
BEGIN DESCRIPTION:
BRUSHY CREEK 2 28.0
END DESCRIPTION:
XS GIS Cut Line= 3
      2471424.99       13683625.        2470925.       13683525.
        2469925.       13684525.
#Sta/Elev= 30
  4489.5   275.8  4581.3  272.65    4617  270.92  4632.3   269.2  4661.2  268.15
  4713.8   267.3  4836.2  262.92  4897.4  263.23    4928  261.33  4948.4  261.39
  4958.6  263.26  4968.8  263.77  4989.2  263.74  5002.9  263.06  5010.6  258.75
  5011.1  258.25  5016.4  258.75  5027.7  263.36    5056  262.85  5140.8  264.69
  5213.7  264.23  5320.2  264.98  5489.7  267.04    5642  266.84  5710.7  266.75
  5805.5  267.95  5819.6  267.42  5901.6  267.96  6024.4  269.99  6413.6  277.37
#Mann= 11 ,-1 , 0
  4489.5     .05       0  4661.2     .07       0  5010.6     .05       0
  5016.4     .07       0  5213.7    .035       0  5320.2     .07       0
  5489.7    .035       0    5642     .07       0  5710.7    .035       0
  5901.6     .05       0  6024.4    .035       0
Bank Sta=5010.6,5016.4
XS Rating Curve= 0 ,0
Exp/Cntr=0.3,0.1

Type RM Length L Ch R = 1 ,23405   ,615,615,615
BEGIN DESCRIPTION:
BRUSHY CREEK 2 27.0
END DESCRIPTION:
XS GIS Cut Line= 3
      2471574.99       13683175.      2471212.54     13682883.08
      2470108.49     13683395.35
#Sta/Elev= 30
  4361.1  271.19  4449.3  269.56  4731.4  264.28  4766.6  263.51  4816.2  260.97
  4907.6  261.19  4956.1  262.17  4961.7  259.73  4964.3  256.52  4964.7  256.02
  4969.6  256.02  4970.1  256.52  4978.1  260.49  4984.6     262  5022.2  261.05
  5039.5  259.91  5044.3  259.49  5058.8  260.58  5066.3  262.04  5088.4  262.95
  5165.5  262.29  5316.2  263.49  5397.3  262.54  5475.4  262.16  5582.8  263.21
  5661.6  264.78    5849  265.99  5979.6  268.05  5999.7   267.5  6043.6   267.3
#Mann= 11 ,-1 , 0
  4361.1     .05       0  4449.3     .07       0  4731.4     .12       0
  4907.6     .07       0  4964.3     .05       0  4970.1     .07       0
  5039.5     .05       0  5397.3     .07       0  5475.4    .035       0
  5582.8     .07       0  5999.7     .12       0
Bank Sta=4964.3,4970.1
XS Rating Curve= 0 ,0
Exp/Cntr=0.3,0.1

Type RM Length L Ch R = 1 ,22790   ,873,873,873
BEGIN DESCRIPTION:
BRUSHY CREEK 2 26.0
END DESCRIPTION:
XS GIS Cut Line= 3
      2471805.06     13683086.48      2471177.16     13682476.26
      2470099.82     13683279.85
#Sta/Elev= 30
  4049.6  270.89    4376  265.07  4439.7  264.87  4655.9  261.42  4920.5  259.14
  4982.8  260.07  4990.2  256.72  5000.7  255.25  5001.2  254.75  5006.6  255.25
    5012  259.66  5040.1  260.71  5076.6  260.81  5082.9  259.24    5090  258.78
  5097.5  260.33  5103.7  259.73  5132.9  260.76  5153.8  258.37  5162.1   260.8
  5175.3  260.72  5468.6  263.01  5554.1   262.6  5647.9   260.9  5697.2  261.06
  5854.3  263.37  5983.6  266.59  6169.1  267.85  6198.3  268.93  6269.2  268.21
#Mann= 6 ,-1 , 0
  4049.6     .05       0  4655.9     .07       0  5000.7     .05       0
  5006.6     .07       0  5175.3     .05       0  5697.2     .07       0
Bank Sta=5000.7,5006.6
XS Rating Curve= 0 ,0
Exp/Cntr=0.3,0.1

Type RM Length L Ch R = 1 ,21917   ,484,484,484
BEGIN DESCRIPTION:
X18347
END DESCRIPTION:
XS GIS Cut Line= 3
      2471274.45     13681857.19       2470761.5     13682255.17
      2470133.58     13683174.94
#Sta/Elev= 30
  4684.3  271.66  4753.7  270.52  4774.5  267.15  4834.7  263.03  4896.7   258.5
  4917.5  260.11    4932  257.97  4967.3  258.92  4981.8   252.2  4988.1  253.14
  4991.1  251.77  4991.6  251.27  5001.4  251.77  5002.6  253.68  5010.7  252.14
  5020.1  255.02  5052.4  257.91  5060.5  256.53  5081.3  256.92  5095.8  253.25
  5110.3  258.97  5345.4  260.12  5403.5   262.7  5445.5  260.13  5484.4  260.17
  5720.6  261.28  5810.8  260.14  5971.8  260.71  6294.9  268.49  6447.2  268.75
#Mann= 7 ,-1 , 0
  4684.3     .07       0  4834.7      .1       0  4991.1     .05       0
  5001.4      .1       0  5020.1     .07       0  5484.4     .05       0
  5810.8     .07       0
Bank Sta=4991.1,5001.4
XS Rating Curve= 0 ,0
Exp/Cntr=0.3,0.1