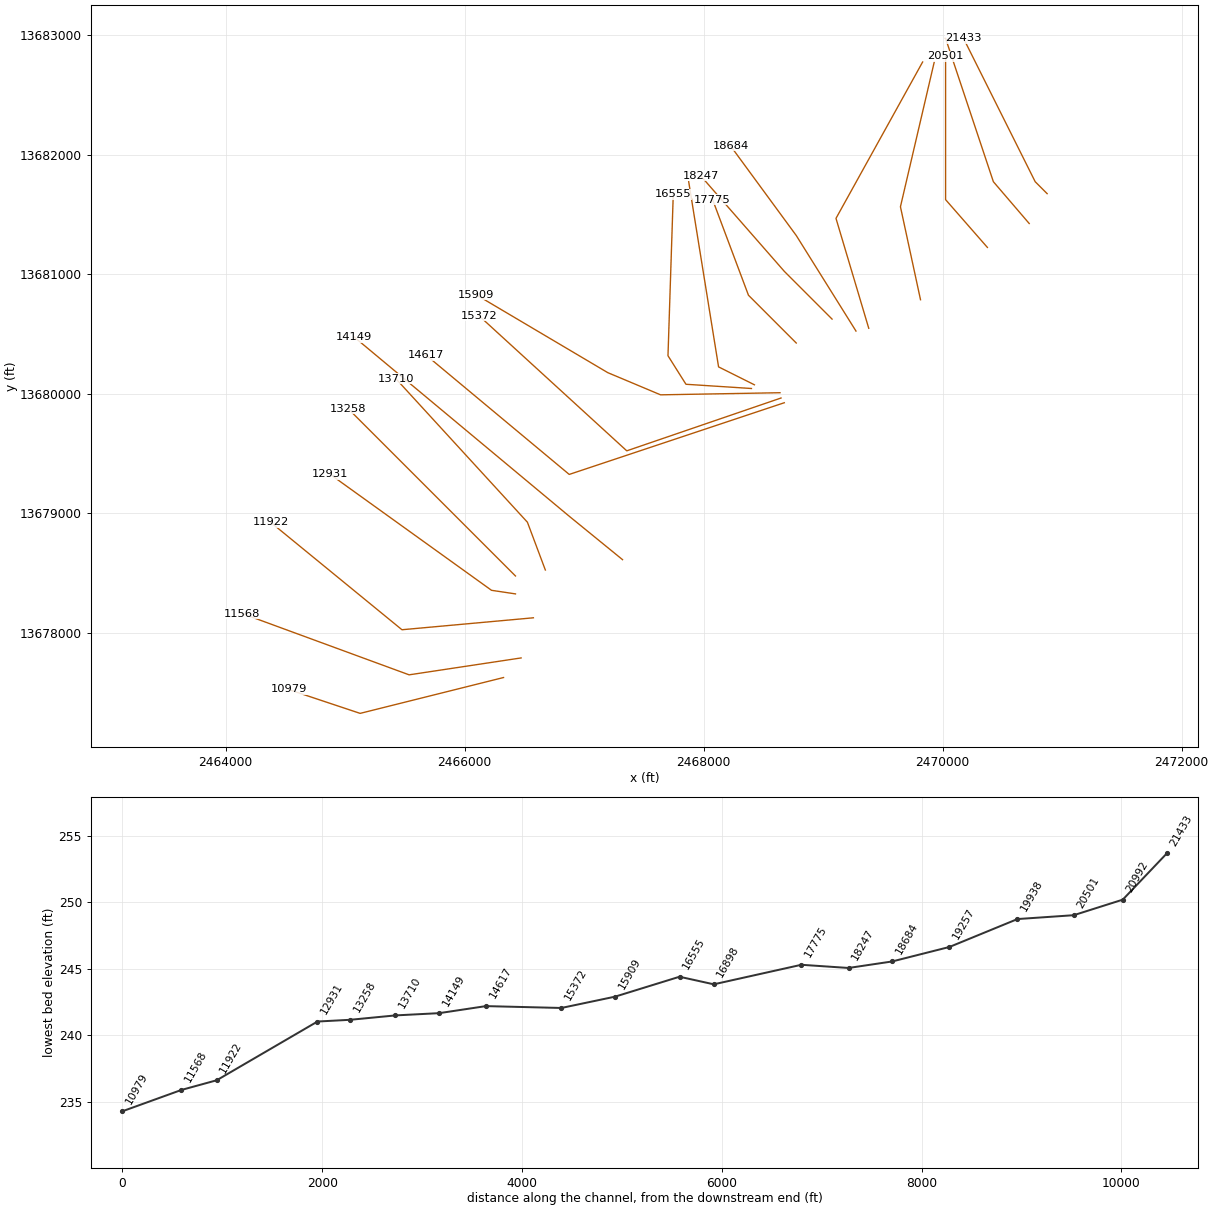
HEC-RAS study BRUSHY CREEK 2.prj: BRUSHY CREEK 2 Base Level Engineering

--- BRUSHY CREEK 2.g01 (geometry) --- (continued)

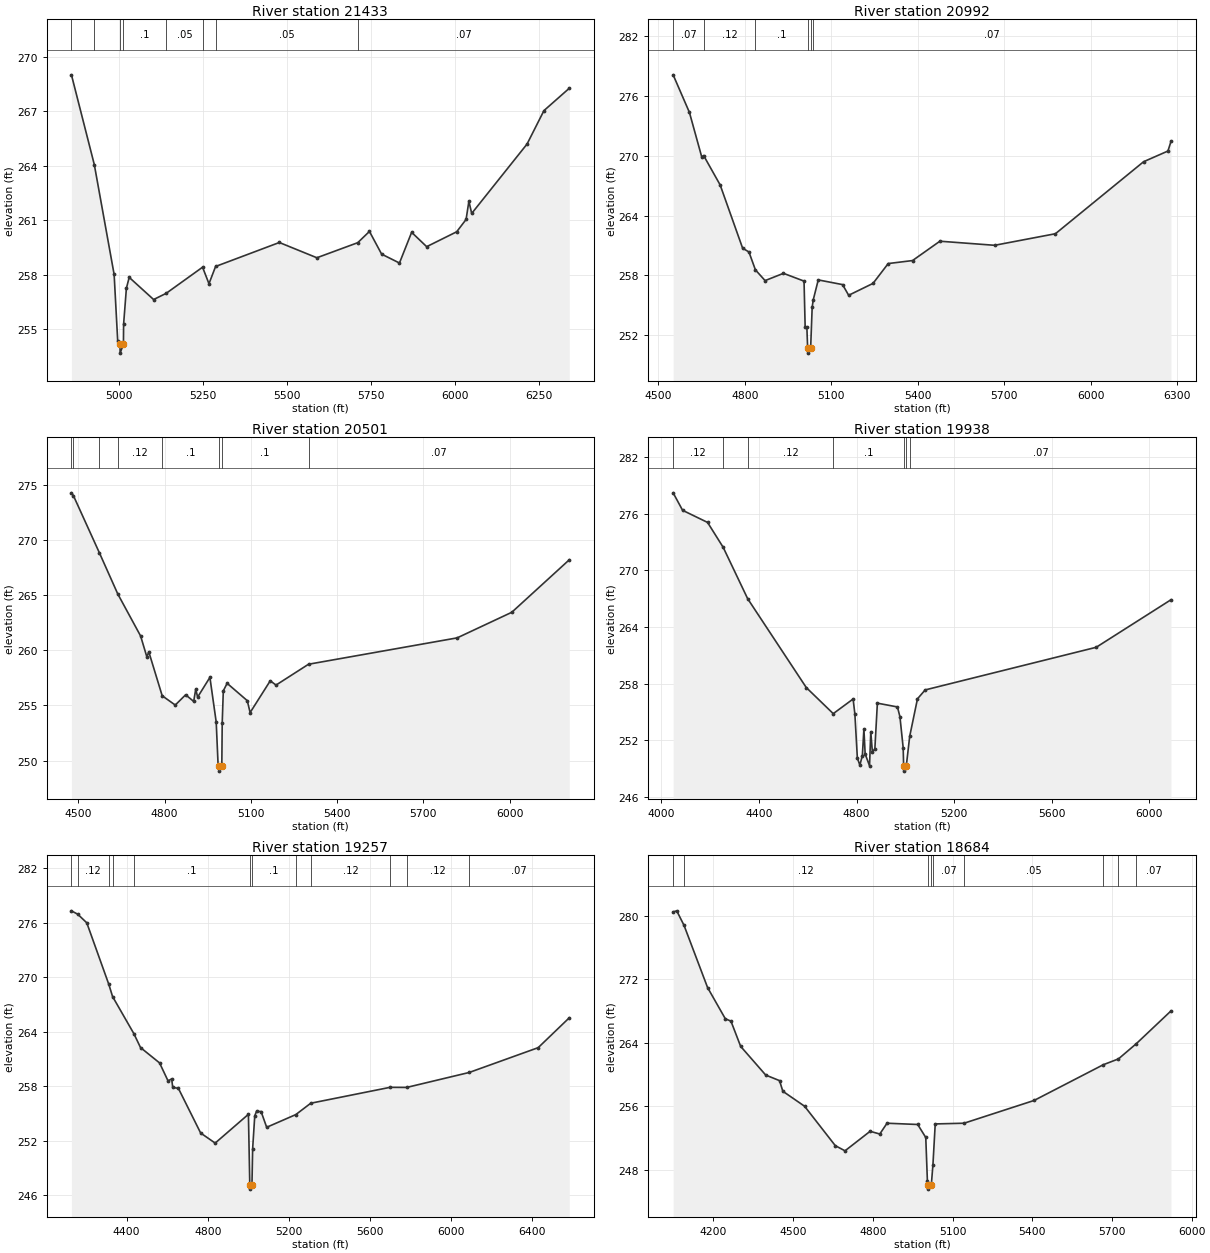
Type RM Length L Ch R = 1 ,21433   ,441,441,441
BEGIN DESCRIPTION:
BRUSHY CREEK 2 25.0
END DESCRIPTION:
XS GIS Cut Line= 3
      2470874.97     13681675.03        2470775.       13681775.
      2470175.01     13682974.99
#Sta/Elev= 30
  4858.4  269.01  4926.5  264.07  4985.6  258.02  4996.2  254.37    5003  254.19
  5003.5  253.69  5013.3  254.19  5013.8  255.28  5022.1  257.26  5030.5  257.86
  5103.2  256.64  5140.5  256.98    5249  258.42  5268.1  257.51  5287.8  258.46
  5477.7  259.78  5589.5  258.94  5711.3  259.77  5746.1  260.39  5782.4  259.14
  5835.5  258.65  5871.8  260.34  5916.6  259.55    6006  260.37    6034  261.05
  6042.3  262.05  6050.7  261.38  6215.6   265.2  6265.9  267.04  6341.4  268.27
#Mann= 8 ,-1 , 0
  4858.4     .07       0  4926.5      .1       0    5003     .05       0
  5013.3      .1       0  5140.5     .05       0    5249     .07       0
  5287.8     .05       0  5711.3     .07       0
Bank Sta=5003,5013.3
XS Rating Curve= 0 ,0
Exp/Cntr=0.3,0.1

Type RM Length L Ch R = 1 ,20992   ,491,491,491
BEGIN DESCRIPTION:
BRUSHY CREEK 2 24.0
END DESCRIPTION:
XS GIS Cut Line= 3
      2470724.98     13681425.02        2470425.       13681775.
      2470024.99     13682975.03
#Sta/Elev= 30
  4551.7  278.11  4608.2  274.34    4651  269.86  4657.4  270.02  4714.7  267.07
  4792.6  260.73  4814.5  260.35  4836.9  258.56  4870.5  257.48  4934.2  258.21
  5005.5  257.43  5009.4  252.81  5015.3  252.81    5018  250.71  5018.5  250.21
  5028.4  250.71  5033.7   254.8  5037.4  255.55  5054.8  257.55  5139.1  257.08
  5160.2  256.01  5244.6   257.2  5297.3  259.19  5381.6  259.49  5476.5  261.43
  5666.2  261.02    5877  262.18  6182.7   269.4    6267  270.47  6277.6  271.43
#Mann= 6 ,-1 , 0
  4551.7     .07       0  4657.4     .12       0  4836.9      .1       0
    5018     .05       0  5028.4      .1       0  5037.4     .07       0
Bank Sta=5018,5028.4
XS Rating Curve= 0 ,0
Exp/Cntr=0.3,0.1

Type RM Length L Ch R = 1 ,20501   ,563,563,563
BEGIN DESCRIPTION:
BRUSHY CREEK 2 23.0
END DESCRIPTION:
XS GIS Cut Line= 3
      2470374.98     13681225.02        2470025.       13681625.
        2470025.     13682825.02
#Sta/Elev= 30
  4476.2  274.27    4483  274.02  4573.8  268.81  4637.4   265.1  4716.8  261.29
  4738.6  259.39  4745.2  259.86  4791.9  255.87  4837.3  255.03  4873.4  255.96
  4901.4  255.36  4908.5  256.47  4915.1  255.75  4957.8  257.54  4979.7  253.49
  4986.3  249.61  4988.7  249.54  4989.2  249.04  4999.2  249.54  5000.6  253.41
  5004.4  256.32  5017.7     257  5087.7  255.43  5097.7  254.35  5167.7  257.23
  5187.7  256.84  5300.8  258.73  5817.7  261.12  6007.7  263.44  6207.7   268.2
#Mann= 8 ,-1 , 0
  4476.2     .07       0    4483     .12       0  4573.8     .07       0
  4637.4     .12       0  4791.9      .1       0  4988.7     .05       0
  4999.2      .1       0  5300.8     .07       0
Bank Sta=4988.7,4999.2
XS Rating Curve= 0 ,0
Exp/Cntr=0.3,0.1

Type RM Length L Ch R = 1 ,19938   ,681,681,681
BEGIN DESCRIPTION:
X18346
END DESCRIPTION:
XS GIS Cut Line= 3
      2469815.22      13680787.1      2469647.19     13681565.36
       2469930.1     13682776.57
#Sta/Elev= 30
  4048.3  278.19  4087.1  276.34  4189.4  275.06  4253.5  272.42  4353.7  266.99
  4593.9  257.59  4704.4  254.83  4785.8  256.38    4793  254.79  4803.2  250.13
  4813.4  249.38  4823.7   250.4    4830  253.21  4835.1  250.57  4853.1  249.31
  4858.2  252.92  4864.7  250.77  4874.9  251.11  4885.2  255.94  4967.4  255.54
  4977.6  254.51  4990.9  251.23  4992.9  249.25  4993.4  248.75  5003.5  249.25
  5017.7  252.44  5049.5   256.4  5081.1  257.34  5781.9  261.85  6088.3  266.88
#Mann= 7 ,-1 , 0
  4048.3     .12       0  4253.5     .07       0  4353.7     .12       0
  4704.4      .1       0  4992.9     .05       0  5003.5      .1       0
  5017.7     .07       0
Bank Sta=4992.9,5003.5
XS Rating Curve= 0 ,0
Exp/Cntr=0.3,0.1

Type RM Length L Ch R = 1 ,19257   ,573,573,573
BEGIN DESCRIPTION:
BRUSHY CREEK 2 22.0
END DESCRIPTION:
XS GIS Cut Line= 3
      2469381.89     13680548.29      2469107.72     13681468.08
       2469832.9     13682776.93
#Sta/Elev= 30
  4127.6   277.3    4159  276.92  4203.3  275.98  4312.2  269.19  4330.5  267.86
  4435.4  263.78  4468.5  262.24  4562.4  260.55  4604.2  258.57  4622.1  258.79
  4627.3  257.85  4655.2  257.75  4765.1  252.83  4836.7  251.72  5000.7  254.89
  5007.5  247.15    5008  246.65  5018.2  247.15  5021.6   251.1    5032  254.72
  5040.8  255.22  5063.3  255.19  5090.8  253.46  5234.6  254.86  5308.2  256.11
  5699.3  257.86  5781.4  257.85  6090.3   259.5  6430.2  262.23  6583.7  265.52
#Mann= 12 ,-1 , 0
  4127.6     .07       0    4159     .12       0  4312.2    .035       0
  4330.5     .12       0  4435.4      .1       0  5007.5     .05       0
  5018.2      .1       0  5234.6     .07       0  5308.2     .12       0
  5699.3     .07       0  5781.4     .12       0  6090.3     .07       0
Bank Sta=5007.5,5018.2
XS Rating Curve= 0 ,0
Exp/Cntr=0.3,0.1

Type RM Length L Ch R = 1 ,18684   ,437,437,437
BEGIN DESCRIPTION:
BRUSHY CREEK 2 21.0
END DESCRIPTION:
XS GIS Cut Line= 3
      2469275.01     13680524.98        2468775.       13681325.
      2468224.98     13682075.02
#Sta/Elev= 30
  4048.7  280.51  4062.3  280.65  4089.8  278.81  4178.4  270.97  4245.1  267.04
  4266.3  266.74  4302.8  263.56  4397.2  259.94  4449.1  259.24  4461.5   257.9
  4543.4  256.01    4659  251.04  4695.5  250.39  4789.9  252.85  4826.4  252.51
  4853.6  253.87  4969.1  253.71  4999.4  252.07  5005.6  246.54    5008  246.06
  5008.5  245.56  5020.2  246.06  5026.4  248.65    5035  253.78  5143.4  253.87
    5407  256.74  5667.1  261.24  5724.5  261.98  5791.4  263.89  5922.2  268.03
#Mann= 9 ,-1 , 0
  4048.7     .07       0  4089.8     .12       0    5008     .05       0
  5020.2     .12       0  5026.4     .07       0  5143.4     .05       0
  5667.1     .07       0  5724.5     .05       0  5791.4     .07       0
Bank Sta=5008,5020.2
XS Rating Curve= 0 ,0
Exp/Cntr=0.3,0.1

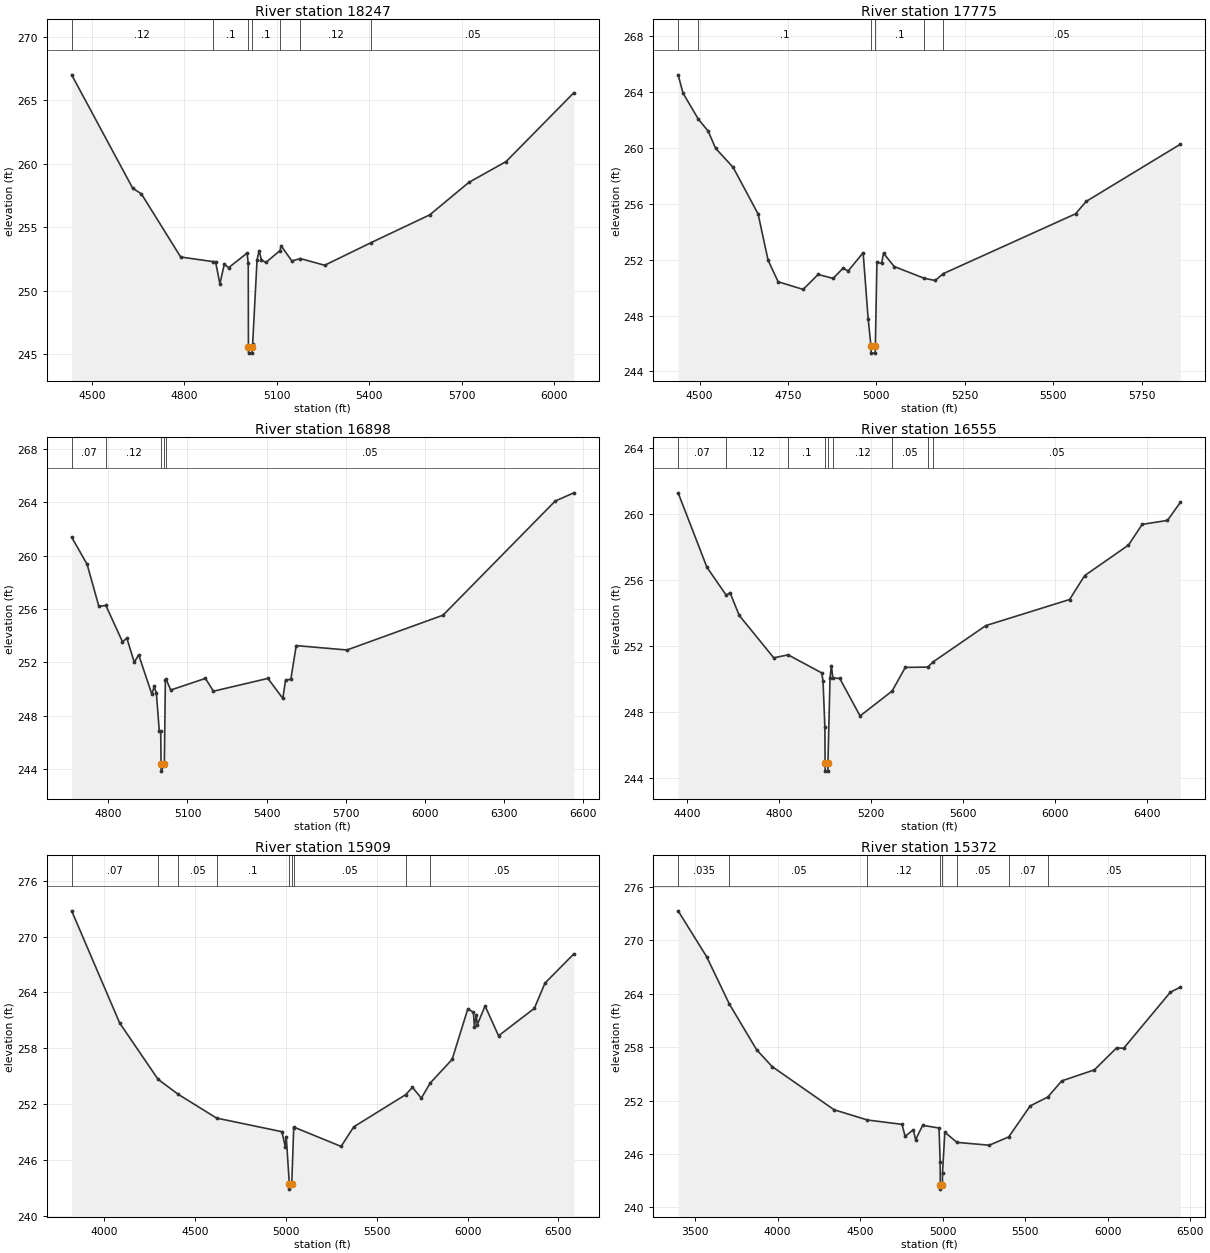
Type RM Length L Ch R = 1 ,18247   ,472,472,472
BEGIN DESCRIPTION:
BRUSHY CREEK 2 20.0
END DESCRIPTION:
XS GIS Cut Line= 3
        2469075.       13680625.        2468675.       13681025.
        2467975.       13681825.
#Sta/Elev= 30
  4434.6  266.99  4632.6  258.06  4660.9  257.61  4788.2  252.64  4892.8  252.28
  4901.3  252.27  4915.4  250.52  4929.6  252.07  4943.7   251.8  5003.6  252.95
  5007.4  252.14  5007.9  245.57  5008.4  245.07  5019.6  245.07  5020.1  245.57
  5021.6  245.79  5035.9  252.42  5042.5  253.13  5050.1  252.42  5064.4  252.21
  5110.5  253.15  5113.7  253.53  5148.8  252.33  5176.4  252.52  5255.1  251.99
  5406.4  253.78  5595.9  255.96    5723  258.52  5843.6  260.16  6063.3  265.58
#Mann= 7 ,-1 , 0
  4434.6     .12       0  4892.8      .1       0  5007.9     .05       0
  5020.1      .1       0  5110.5     .05       0  5176.4     .12       0
  5406.4     .05       0
Bank Sta=5007.9,5020.1
XS Rating Curve= 0 ,0
Exp/Cntr=0.3,0.1

Type RM Length L Ch R = 1 ,17775   ,877,877,877
BEGIN DESCRIPTION:
BRUSHY CREEK 2 19.0
END DESCRIPTION:
XS GIS Cut Line= 3
      2468774.97     13680425.03        2468375.       13680825.
      2468075.02     13681624.96
#Sta/Elev= 30
  4439.4  265.23  4453.5  263.91    4497  262.04  4524.2  261.21  4545.4  259.97
  4594.9  258.61  4665.6  255.27  4693.9  251.95  4722.2  250.42  4792.9  249.87
  4835.3  250.94  4877.8  250.66  4906.1   251.4  4920.2  251.19  4962.6   252.5
  4976.8  247.75  4984.8  245.81  4985.3  245.31  4996.6  245.31  4997.1  245.81
  5001.5  251.84  5014.8  251.73  5020.2  252.46  5050.4  251.51  5134.9  250.67
  5166.1  250.51  5189.2     251  5563.1  255.28  5593.3  256.17  5859.4  260.26
#Mann= 6 ,-1 , 0
  4439.4     .07       0    4497      .1       0  4984.8     .05       0
  4997.1      .1       0  5134.9     .07       0  5189.2     .05       0
Bank Sta=4984.8,4997.1
XS Rating Curve= 0 ,0
Exp/Cntr=0.3,0.1

Type RM Length L Ch R = 1 ,16898   ,343,343,343
BEGIN DESCRIPTION:
BRUSHY CREEK 2 18.0
END DESCRIPTION:
XS GIS Cut Line= 3
      2468424.98     13680075.01        2468125.       13680225.
        2467875.     13681774.98
#Sta/Elev= 30
  4660.6  261.38  4719.3  259.34    4764  256.18  4790.3  256.26  4853.4  253.54
  4870.2   253.8  4898.2     252  4914.9  252.56  4965.2  249.59  4973.6   250.2
    4982   249.7  4993.2  246.82  4998.5  246.82  4999.9  244.34  5000.4  243.84
  5012.3  244.34  5016.2  250.69    5018  250.77  5036.5  249.92  5168.2  250.79
  5198.6  249.83  5405.2  250.79  5461.9  249.29  5472.1  250.66  5492.3  250.73
  5512.6  253.25    5705  252.92  6069.7  255.53  6495.1  264.08    6566   264.7
#Mann= 5 ,-1 , 0
  4660.6     .07       0  4790.3     .12       0  4999.9     .05       0
  5012.3     .12       0    5018     .05       0
Bank Sta=4999.9,5012.3
XS Rating Curve= 0 ,0
Exp/Cntr=0.3,0.1

Type RM Length L Ch R = 1 ,16555   ,646,646,646
BEGIN DESCRIPTION:
X18345
END DESCRIPTION:
XS GIS Cut Line= 4
       2468400.2     13680044.23      2467851.91     13680079.61
      2467701.56     13680318.39      2467745.76     13681670.76
#Sta/Elev= 30
    4362  261.26  4487.5  256.75  4571.9  255.05  4587.7  255.22  4627.8  253.84
  4778.1  251.27  4840.6  251.45  4986.4  250.36  4992.4  249.89  5000.5  247.06
  5001.4  244.91  5001.9  244.41  5013.3  244.41  5013.8  244.91  5022.9  250.06
  5028.8   250.8  5035.1  250.05  5065.3  250.02  5153.6  247.75    5293  249.26
  5350.3  250.69    5448  250.71    5471  251.02  5700.5  253.22    6065   254.8
  6130.7  256.25  6320.8  258.09  6380.9  259.35  6490.9  259.59  6546.7  260.68
#Mann= 9 ,-1 , 0
    4362     .07       0  4571.9     .12       0  4840.6      .1       0
  5001.4     .05       0  5013.8      .1       0  5035.1     .12       0
    5293     .05       0    5448     .07       0    5471     .05       0
Bank Sta=5001.4,5013.8
XS Rating Curve= 0 ,0
Exp/Cntr=0.3,0.1

Type RM Length L Ch R = 1 ,15909   ,537,537,537
BEGIN DESCRIPTION:
X18344
END DESCRIPTION:
XS GIS Cut Line= 4
      2468639.03     13680008.86      2467639.66     13679991.17
      2467197.47     13680176.89      2466093.11     13680830.67
#Sta/Elev= 30
  3822.2  272.76  4086.3  260.73  4297.5  254.69  4408.5  253.08  4619.4  250.53
  4978.9  249.07  4997.2  247.47  5002.6  248.54  5019.9  243.41  5020.4  242.91
  5032.9  243.41  5043.7  249.49  5047.6  249.54  5304.4  247.49  5373.9  249.59
  5659.4  253.04  5696.8  253.83  5745.8  252.67  5794.7  254.29  5915.1  256.82
  6001.5  262.25  6032.1  261.88  6037.9  260.32  6047.8  261.64  6053.6  260.55
  6096.4  262.56  6170.6  259.36  6367.5   262.3    6426  265.01  6584.7  268.14
#Mann= 9 ,-1 , 0
  3822.2     .07       0  4297.5     .12       0  4408.5     .05       0
  4619.4      .1       0  5019.9     .05       0  5032.9      .1       0
  5047.6     .05       0  5659.4     .07       0  5794.7     .05       0
Bank Sta=5019.9,5032.9
XS Rating Curve= 0 ,0
Exp/Cntr=0.3,0.1

Type RM Length L Ch R = 1 ,15372   ,755,755,755
BEGIN DESCRIPTION:
X18343
END DESCRIPTION:
XS GIS Cut Line= 3
      2468647.82     13679964.63      2467356.66     13679522.45
      2466119.26     13680653.78
#Sta/Elev= 30
  3397.2   273.3  3570.2  268.14  3707.8  262.83  3872.5  257.71  3966.4  255.82
  4341.8  250.97  4543.9  249.82  4753.2  249.33  4772.1  247.98  4821.4  248.73
  4835.6  247.61  4878.2  249.22  4977.4  248.92  4984.2  245.16  4985.1  242.56
  4985.6  242.06  4998.2  242.56  4998.4  243.86  5012.6  248.45  5085.4  247.31
  5281.5  246.99  5399.5  247.92  5529.4   251.4  5636.1   252.4  5720.6  254.21
  5918.5  255.45  6052.9  257.92  6095.5  257.87  6378.6  264.17  6438.6  264.73
#Mann= 8 ,-1 , 0
  3397.2    .035       0  3707.8     .05       0  4543.9     .12       0
  4985.1     .05       0  4998.2     .12       0  5085.4     .05       0
  5399.5     .07       0  5636.1     .05       0
Bank Sta=4985.1,4998.2
XS Rating Curve= 0 ,0
Exp/Cntr=0.3,0.1

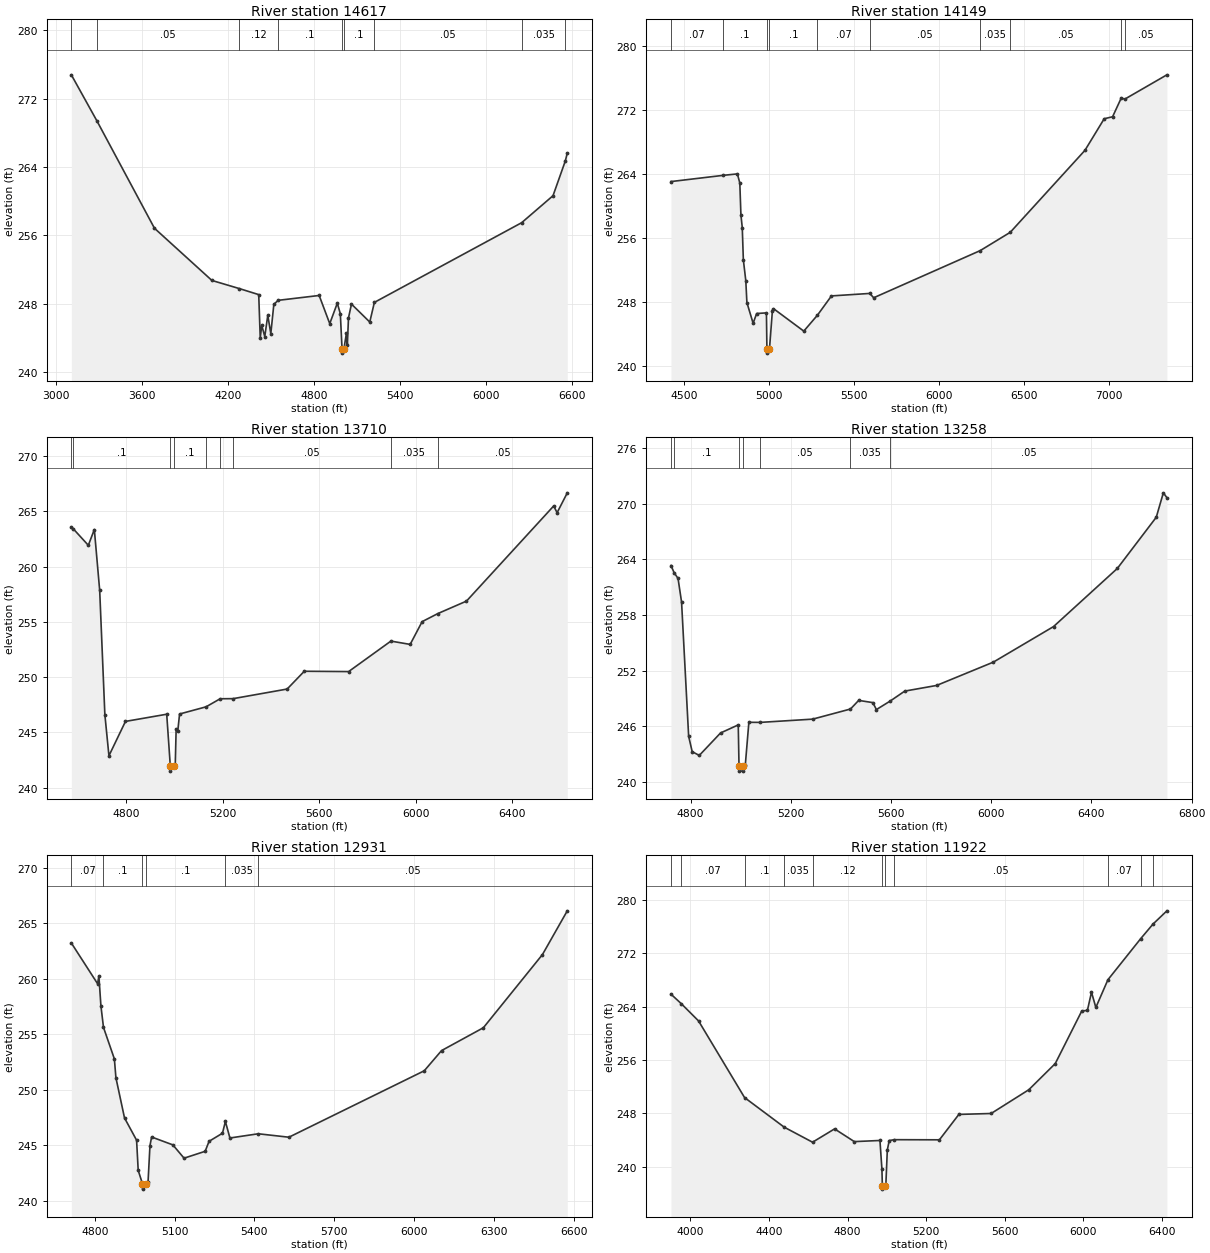
Type RM Length L Ch R = 1 ,14617   ,468,468,468
BEGIN DESCRIPTION:
BRUSHY CREEK 2 17.0
END DESCRIPTION:
XS GIS Cut Line= 3
      2468675.03     13679925.01        2466875.       13679325.
      2465675.03     13680324.97
#Sta/Elev= 30
  3106.9  274.78  3286.2  269.36  3686.7  256.82  4087.2  250.71    4278  249.76
    4414  249.05  4424.5     244  4435.1  245.45  4456.2  244.14  4477.2  246.63
  4498.3  244.48  4519.4  247.91  4549.4  248.38  4835.6  248.95  4909.4  245.65
  4962.1  248.05  4983.2  246.81  4995.1   242.7  4995.6   242.2  5008.3   242.7
  5025.8  244.54  5032.3   243.2  5040.1  246.32  5060.9  247.94  5188.5  245.84
  5220.7  248.14  6248.1  257.47  6466.8  260.63  6552.4  264.69  6566.3  265.62
#Mann= 9 ,-1 , 0
  3106.9    .035       0  3286.2     .05       0    4278     .12       0
  4549.4      .1       0  4995.1     .05       0  5008.3      .1       0
  5220.7     .05       0  6248.1    .035       0  6552.4     .05       0
Bank Sta=4995.1,5008.3
XS Rating Curve= 0 ,0
Exp/Cntr=0.3,0.1

Type RM Length L Ch R = 1 ,14149   ,439,439,439
BEGIN DESCRIPTION:
BRUSHY CREEK 2 16.0
END DESCRIPTION:
XS GIS Cut Line= 3
      2467321.25     13678611.57        2466875.       13678975.
      2465074.99       13680475.
#Sta/Elev= 30
  4424.7  263.11  4733.3  263.89  4815.7  264.07    4830  262.93  4836.5  258.94
  4844.4  257.37  4850.8  253.34  4865.2  250.73  4871.7  247.99  4908.3   245.4
  4929.1  246.62  4986.6   246.7  4989.5  242.17    4990  241.67  5004.5  242.17
  5021.7  246.95  5028.2  247.23  5206.5  244.42  5286.8  246.41  5369.3  248.82
  5594.5  249.13  5617.9  248.59  6244.5  254.48  6421.6  256.77    6861  267.01
  6974.3  270.96  7023.7  271.21  7074.9  273.56  7095.4  273.41  7343.3  276.45
#Mann= 10 ,-1 , 0
  4424.7     .07       0  4733.3      .1       0  4989.5     .05       0
  5004.5      .1       0  5286.8     .07       0  5594.5     .05       0
  6244.5    .035       0  6421.6     .05       0  7074.9    .035       0
  7095.4     .05       0
Bank Sta=4989.5,5004.5
XS Rating Curve= 0 ,0
Exp/Cntr=0.3,0.1

Type RM Length L Ch R = 1 ,13710   ,452,452,452
BEGIN DESCRIPTION:
BRUSHY CREEK 2 15.0
END DESCRIPTION:
XS GIS Cut Line= 3
      2466675.02     13678524.95        2466525.       13678925.
      2465425.02     13680124.98
#Sta/Elev= 30
  4572.1  263.56    4579  263.46  4642.5  261.94  4667.4  263.37  4689.6  257.85
    4711  246.62  4727.9  242.89  4796.4     246  4967.3  246.65  4982.1     242
  4982.6   241.5  4997.1     242  5002.7  242.05  5006.4  245.31  5013.2  245.14
  5020.6  246.67  5130.3  247.32  5188.8  248.05  5242.4  248.06  5466.4  248.93
  5537.4  250.54  5721.1  250.51  5896.3  253.27  5976.1  252.97  6025.7  255.03
  6090.7  255.76  6209.5  256.89  6570.8   265.5    6585  264.89  6627.2  266.69
#Mann= 9 ,-1 , 0
  4572.1     .07       0    4579      .1       0  4982.1     .05       0
  4997.1      .1       0  5130.3     .05       0  5188.8      .1       0
  5242.4     .05       0  5896.3    .035       0  6090.7     .05       0
Bank Sta=4982.1,4997.1
XS Rating Curve= 0 ,0
Exp/Cntr=0.3,0.1

Type RM Length L Ch R = 1 ,13258   ,327,327,327
BEGIN DESCRIPTION:
BRUSHY CREEK 2 14.0
END DESCRIPTION:
XS GIS Cut Line= 3
      2466424.99     13678475.01        2466225.       13678675.
      2465024.99     13679875.01
#Sta/Elev= 30
  4721.2  263.32  4734.5  262.52  4749.5  261.93  4763.6  259.39  4791.9  244.92
    4806  243.27  4834.3  242.86  4919.2  245.28  4989.9  246.15    4993  241.67
  4993.5  241.17  5007.5  241.17    5008  241.67  5018.2  241.88  5032.3  246.43
  5077.3  246.42  5286.9  246.77  5437.9  247.86  5470.7  248.79  5527.3  248.55
  5541.4   247.8  5597.1  248.73  5654.6  249.79  5781.8   250.4  6008.1  252.91
  6248.5  256.74  6503.1     263  6658.7  268.52  6686.9  271.15  6701.1  270.63
#Mann= 7 ,-1 , 0
  4721.2     .07       0  4734.5      .1       0    4993     .05       0
    5008      .1       0  5077.3     .05       0  5437.9    .035       0
  5597.1     .05       0
Bank Sta=4993,5008
XS Rating Curve= 0 ,0
Exp/Cntr=0.3,0.1

Type RM Length L Ch R = 1 ,12931   ,1009,1009,1009
BEGIN DESCRIPTION:
BRUSHY CREEK 2 13.0
END DESCRIPTION:
XS GIS Cut Line= 3
        2466425.       13678325.      2466224.66     13678355.07
      2464875.01     13679324.99
#Sta/Elev= 30
  4711.8  263.23  4810.4  259.56  4815.4  260.25    4823  257.56  4832.7  255.62
  4873.6  252.78  4879.4  251.08  4911.7  247.46  4957.1  245.45  4963.2  242.73
    4979  241.54  4979.5  241.04    4994  241.54  5000.2  241.68  5007.4  244.96
  5013.6  245.74  5093.4  245.03  5135.6  243.83  5214.9  244.45  5229.6  245.35
    5280  246.08    5291  247.14    5308  245.65  5414.7  246.03  5529.7  245.72
  6038.7  251.71  6103.7  253.53  6260.9  255.59  6483.1  262.19  6576.4  266.13
#Mann= 6 ,-1 , 0
  4711.8     .07       0  4832.7      .1       0    4979     .05       0
    4994      .1       0    5291    .035       0  5414.7     .05       0
Bank Sta=4979,4994
XS Rating Curve= 0 ,0
Exp/Cntr=0.3,0.1

Type RM Length L Ch R = 1 ,11922   ,354,354,354
BEGIN DESCRIPTION:
BRUSHY CREEK 2 12.0
END DESCRIPTION:
XS GIS Cut Line= 3
      2466575.01       13678125.        2465475.       13678025.
      2464375.01     13678924.99
#Sta/Elev= 30
  3900.4  265.88  3953.3  264.44    4041  261.86  4275.3  250.36  4477.1  245.92
  4621.6  243.66  4733.8  245.66  4834.2  243.75  4964.8  243.92  4974.8  239.65
  4977.2  237.12  4977.7  236.62  4992.5  237.12  4994.9  237.28  5002.4   242.5
  5012.1  243.91  5038.1  244.04  5267.7  244.02  5366.7  247.83  5531.1  247.97
  5722.8  251.53  5857.7  255.46  5992.7  263.35  6021.4  263.44  6042.2  266.17
  6064.4  263.88  6125.9  268.04  6292.7   274.2  6355.4  276.39  6426.2  278.38
#Mann= 11 ,-1 , 0
  3900.4     .05       0  3953.3     .07       0  4275.3      .1       0
  4477.1    .035       0  4621.6     .12       0  4977.2     .05       0
  4992.5     .12       0  5038.1     .05       0  6125.9     .07       0
  6292.7     .05       0  6355.4     .07       0
Bank Sta=4977.2,4992.5
XS Rating Curve= 0 ,0
Exp/Cntr=0.3,0.1

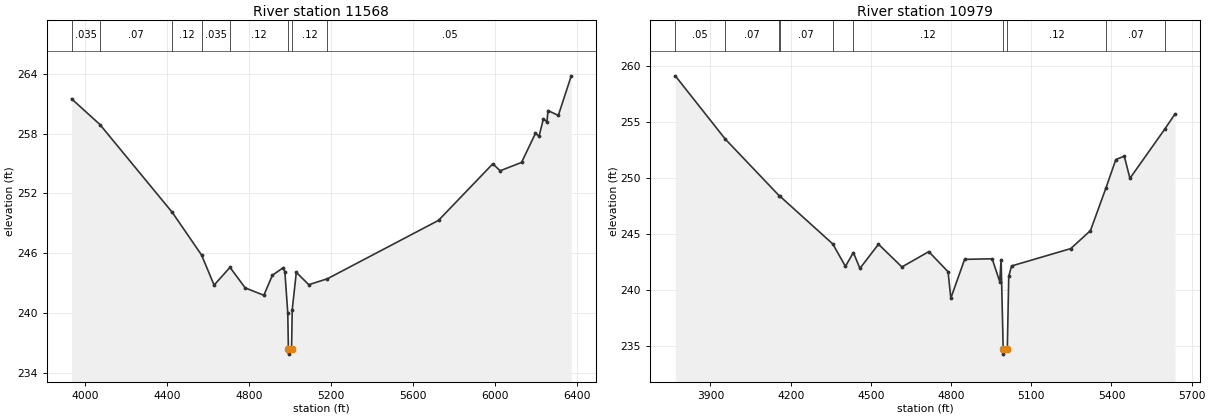
Type RM Length L Ch R = 1 ,11568   ,589,589,589
BEGIN DESCRIPTION:
X18342
END DESCRIPTION:
XS GIS Cut Line= 3
      2466472.29     13677789.07      2465534.84     13677647.57
      2464137.57     13678160.49
#Sta/Elev= 30
  3934.3  261.49  4072.7  258.91  4425.9  250.09  4568.2  245.83  4629.4  242.81
    4707  244.59  4781.1  242.53  4872.1  241.79  4913.6   243.8  4967.4  244.57
  4974.6  244.13  4988.7     240  4991.7  236.39  4992.2  235.89    5007  236.39
  5010.4  240.36  5030.3  244.09  5091.2  242.85  5182.2  243.45  5723.7   249.3
  5988.4  254.97  6024.2  254.27  6128.5  255.11  6196.5  258.03  6213.8  257.73
  6235.1  259.49  6252.2  259.16  6257.5  260.31  6307.8  259.82  6370.8  263.79
#Mann= 8 ,-1 , 0
  3934.3    .035       0  4072.7     .07       0  4425.9     .12       0
  4568.2    .035       0    4707     .12       0  4991.7     .05       0
    5007     .12       0  5182.2     .05       0
Bank Sta=4991.7,5007
XS Rating Curve= 0 ,0
Exp/Cntr=0.3,0.1

Type RM Length L Ch R = 1 ,10979   ,463,463,463
BEGIN DESCRIPTION:
BRUSHY CREEK 2 11.0
END DESCRIPTION:
XS GIS Cut Line= 3
      2466325.04     13677625.01        2465125.       13677325.
      2464525.03     13677524.99
#Sta/Elev= 30
  3768.3  259.16  3954.9  253.52  4156.4  248.46    4159  248.42  4357.8  244.13
  4404.8  242.13  4434.6  243.37    4459  241.95  4528.5  244.11  4616.2  242.08
  4716.7  243.45  4788.8  241.65  4799.1  239.29  4850.7  242.76  4953.7  242.81
  4982.1  240.77  4987.2  242.74    4995  234.79  4995.5  234.29  5010.4  234.79
  5015.8  241.25  5026.4  242.17  5247.7  243.72  5321.5  245.33  5379.4  249.14
  5416.4  251.68    5448  251.98  5469.1     250  5599.2  254.39  5637.7  255.75
#Mann= 10 ,-1 , 0
  3768.3     .05       0  3954.9     .07       0  4156.4     .05       0
    4159     .07       0  4357.8    .035       0  4434.6     .12       0
    4995     .05       0  5010.4     .12       0  5379.4     .07       0
  5599.2    .035       0
Bank Sta=4995,5010.4
XS Rating Curve= 0 ,0
Exp/Cntr=0.3,0.1