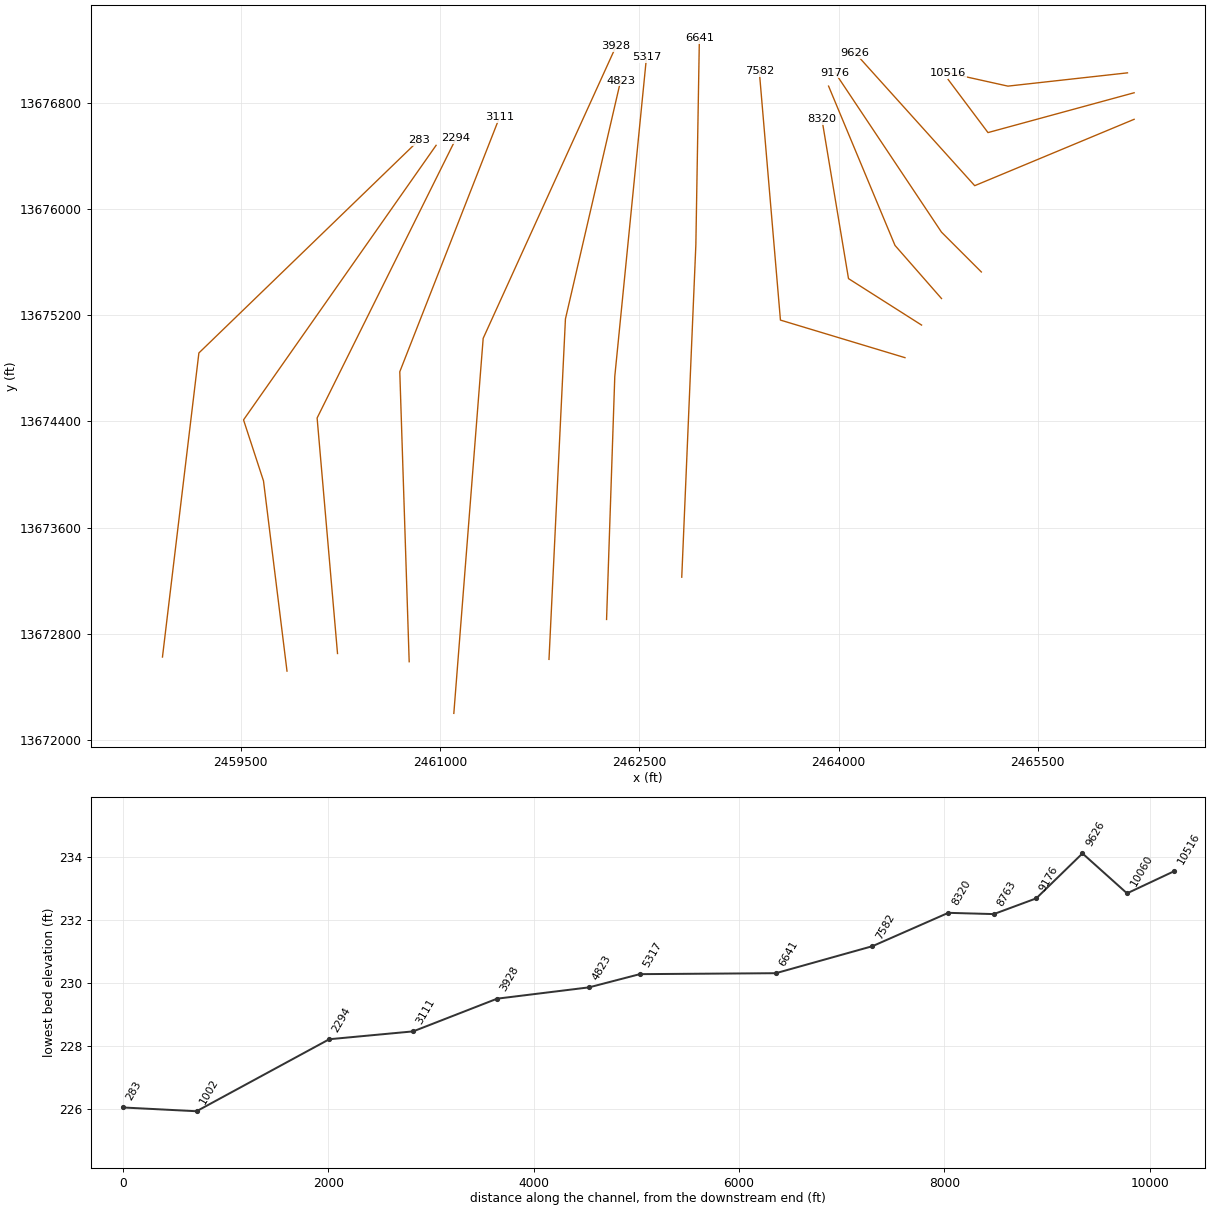
HEC-RAS study BRUSHY CREEK 2.prj: BRUSHY CREEK 2 Base Level Engineering

--- BRUSHY CREEK 2.g01 (geometry) --- (continued)

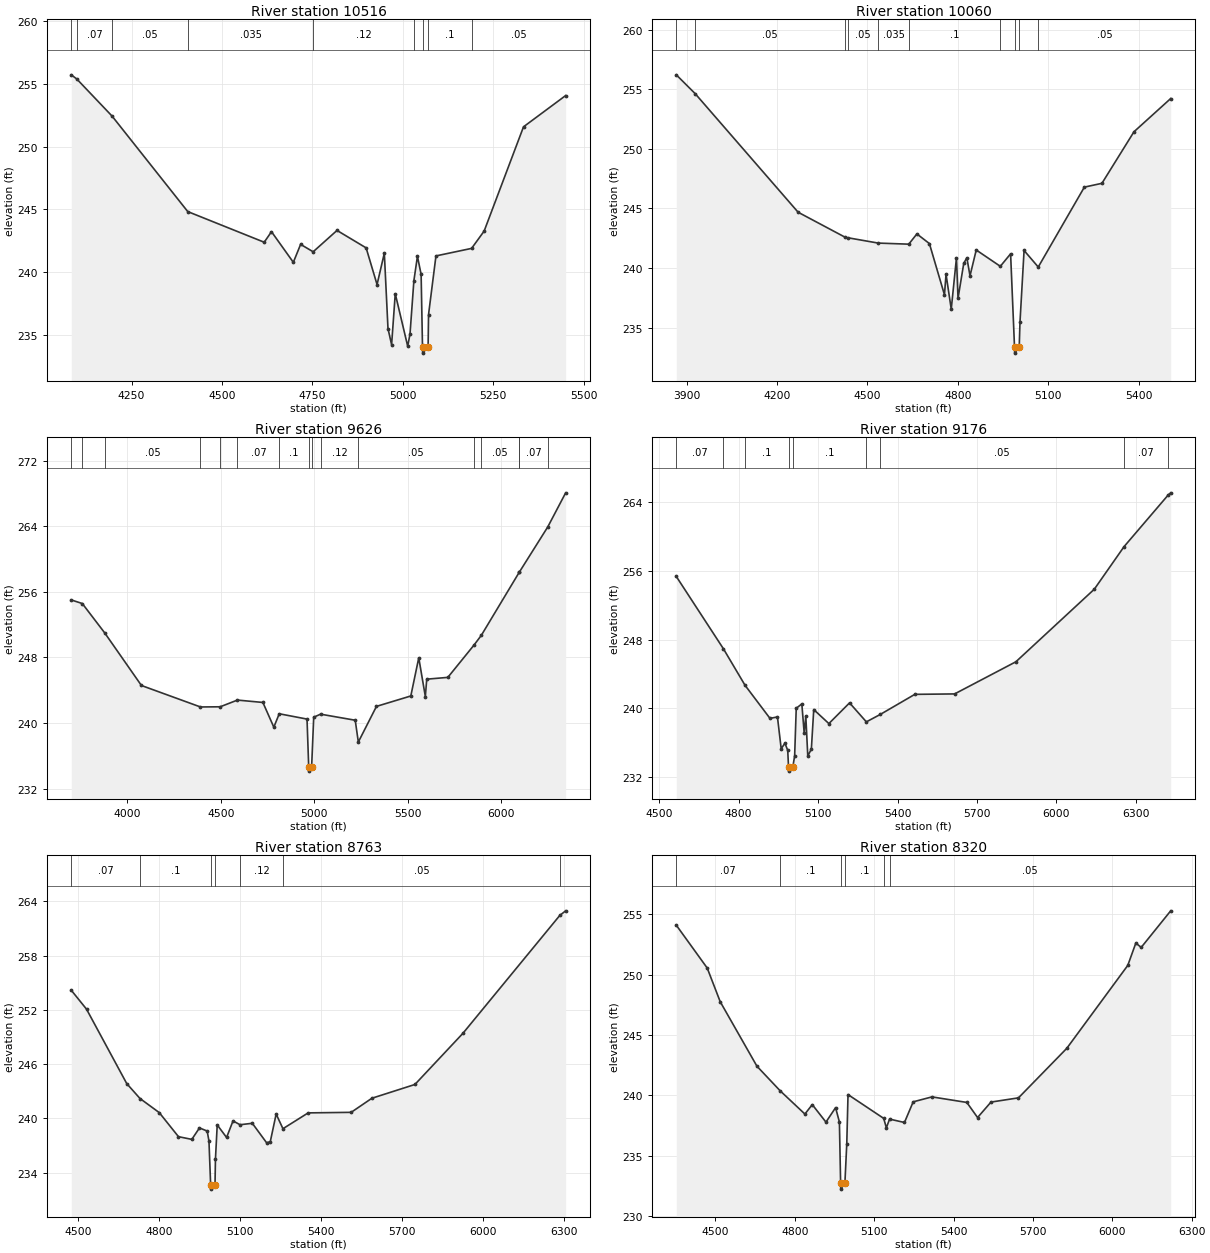
Type RM Length L Ch R = 1 ,10516   ,456,456,456
BEGIN DESCRIPTION:
BRUSHY CREEK 2 10.0
END DESCRIPTION:
XS GIS Cut Line= 3
      2466175.01       13677025.        2465275.       13676925.
      2464825.03     13677024.99
#Sta/Elev= 30
  4083.5  255.71  4098.7  255.38  4196.4  252.42  4405.5  244.82  4616.8  242.38
  4636.9  243.22  4697.3  240.78  4717.4  242.21  4752.1  241.62    4818  243.32
  4898.5  241.93  4928.7  239.01  4948.8  241.51  4958.9  235.51  4968.9  234.22
    4979  238.28  5013.4   234.1  5019.8  235.08  5030.5  239.32  5040.3  241.26
  5050.5  239.82  5054.3  234.05  5054.8  233.55  5069.8  234.05    5071  236.62
  5091.5  241.29    5190  241.89  5224.7  243.27  5333.5  251.57    5450  254.06
#Mann= 9 ,-1 , 0
  4083.5     .05       0  4098.7     .07       0  4196.4     .05       0
  4405.5    .035       0  4752.1     .12       0  5030.5      .1       0
  5054.3     .05       0  5069.8      .1       0    5190     .05       0
Bank Sta=5054.3,5069.8
XS Rating Curve= 0 ,0
Exp/Cntr=0.3,0.1

Type RM Length L Ch R = 1 ,10060   ,434,434,434
BEGIN DESCRIPTION:
BRUSHY CREEK 2 9.0
END DESCRIPTION:
XS GIS Cut Line= 3
      2466224.97     13676874.99        2465125.       13676575.
      2464825.03     13676974.97
#Sta/Elev= 30
  3865.9  256.22  3928.5  254.64  4270.1  244.68  4425.4  242.59  4434.6  242.54
  4535.9  242.09  4637.1     242    4664  242.86  4705.5  242.05  4755.5  237.75
  4760.7  239.48    4778  236.54  4795.3  240.86  4800.5  237.45  4819.5  240.39
  4829.8  240.86  4840.2  239.34  4860.9  241.51  4940.8  240.14  4974.9  241.19
  4987.9  233.35  4988.4  232.85  5003.5  233.35    5006  235.44  5019.6  241.47
  5066.6  240.08  5219.6  246.79  5277.9  247.11  5384.2  251.44    5506  254.23
#Mann= 10 ,-1 , 0
  3865.9     .07       0  3928.5     .05       0  4425.4    .035       0
  4434.6     .05       0  4535.9    .035       0  4637.1      .1       0
  4940.8     .12       0  4987.9     .05       0  5003.5     .12       0
  5066.6     .05       0
Bank Sta=4987.9,5003.5
XS Rating Curve= 0 ,0
Exp/Cntr=0.3,0.1

Type RM Length L Ch R = 1 ,9626    ,450,450,450
BEGIN DESCRIPTION:
BRUSHY CREEK 2 8.0
END DESCRIPTION:
XS GIS Cut Line= 3
      2466224.99       13676675.        2465025.       13676175.
      2464124.97     13677175.04
#Sta/Elev= 30
  3700.3  255.01  3759.4  254.57  3878.9     251  4075.7  244.57  4391.6  241.95
    4497  241.97  4589.5  242.79  4725.7   242.5  4784.2  239.48  4813.1  241.12
  4961.8  240.47  4970.8  234.62  4971.3  234.12  4986.4  234.62  4997.6   240.7
  5034.2  241.07  5219.7  240.33  5236.3  237.67  5333.3  242.02  5517.1  243.29
  5559.7  247.95  5594.9  243.22  5602.3  245.34  5715.2  245.56  5855.2   249.5
  5894.4  250.69  6097.6   258.4  6097.7   258.4  6249.7  263.91  6345.7  268.08
#Mann= 16 ,-1 , 0
  3700.3     .05       0  3759.4    .035       0  3878.9     .05       0
  4391.6     .07       0    4497    .035       0  4589.5     .07       0
  4813.1      .1       0  4970.8     .05       0  4986.4      .1       0
  5034.2     .12       0  5236.3     .05       0  5855.2    .035       0
  5894.4     .05       0  6097.6    .035       0  6097.7     .07       0
  6249.7     .05       0
Bank Sta=4970.8,4986.4
XS Rating Curve= 0 ,0
Exp/Cntr=0.3,0.1

Type RM Length L Ch R = 1 ,9176    ,413,413,413
BEGIN DESCRIPTION:
BRUSHY CREEK 2 7.0
END DESCRIPTION:
XS GIS Cut Line= 3
      2465075.01     13675524.99        2464775.       13675825.
        2463975.       13677025.
#Sta/Elev= 30
  4564.8  255.33  4742.7  246.92  4824.4  242.67  4918.4  238.83  4946.7  238.99
  4960.8  235.29  4974.9  235.94  4985.5   235.1  4988.5  233.19    4989  232.69
  5004.7  233.19  5011.6  234.45  5017.6     240  5038.7  240.51  5047.7   237.1
  5053.7   239.1  5061.2  234.45  5074.7  235.25  5083.7  239.85  5140.8  238.22
  5218.9  240.63  5282.3  238.42  5334.7  239.28  5465.3  241.62  5615.5  241.67
  5846.9  245.41  6142.9  253.85  6255.4  258.81  6422.2  264.82  6431.3  265.06
#Mann= 9 ,-1 , 0
  4564.8     .07       0  4742.7     .12       0  4824.4      .1       0
  4988.5     .05       0  5004.7      .1       0  5282.3     .07       0
  5334.7     .05       0  6255.4     .07       0  6422.2     .05       0
Bank Sta=4988.5,5004.7
XS Rating Curve= 0 ,0
Exp/Cntr=0.3,0.1

Type RM Length L Ch R = 1 ,8763    ,443,443,443
BEGIN DESCRIPTION:
BRUSHY CREEK 2 6.0
END DESCRIPTION:
XS GIS Cut Line= 3
        2464775.       13675325.        2464425.       13675725.
        2463925.       13676925.
#Sta/Elev= 30
  4473.4  254.18  4529.9  252.09  4678.9  243.86    4728  242.21  4799.4  240.65
  4870.6  237.99    4920  237.69  4948.4  238.96  4976.9  238.61  4983.5  237.51
  4989.7  232.69  4990.2  232.19  5005.9  232.69  5007.6  235.53  5014.1  239.29
  5048.8   237.9  5072.6  239.73  5098.7  239.31  5144.1  239.47  5197.2  237.31
  5210.7  237.44  5232.4  240.49  5257.6  238.87    5351  240.62  5510.3  240.68
  5587.2  242.24  5746.4  243.76  5924.1  249.41  6283.4  262.46  6304.9  262.96
#Mann= 7 ,-1 , 0
  4473.4     .07       0    4728      .1       0  4989.7     .05       0
  5005.9      .1       0  5098.7     .12       0  5257.6     .05       0
  6283.4     .07       0
Bank Sta=4989.7,5005.9
XS Rating Curve= 0 ,0
Exp/Cntr=0.3,0.1

Type RM Length L Ch R = 1 ,8320    ,738,738,738
BEGIN DESCRIPTION:
BRUSHY CREEK 2 5.0
END DESCRIPTION:
XS GIS Cut Line= 3
      2464625.02     13675124.99        2464075.       13675475.
        2463875.       13676675.
#Sta/Elev= 30
  4352.3  254.09  4469.2  250.54  4518.3  247.75  4657.1  242.41    4745  240.37
  4838.3  238.45  4866.2  239.23  4917.9  237.78  4954.3  238.98  4968.7  237.79
  4973.3  232.73  4973.8  232.23  4989.5  232.73  4996.6     236  5001.3  240.06
  5136.1  238.09  5146.2  237.31  5158.3  238.03  5214.6  237.75  5247.6  239.46
  5318.5  239.87  5450.3  239.41  5490.9  238.16  5541.6  239.44  5645.5  239.79
    5828  243.89  6058.6  250.76    6089  252.61  6109.3  252.25  6220.8  255.28
#Mann= 6 ,-1 , 0
  4352.3     .07       0    4745      .1       0  4973.3     .05       0
  4989.5      .1       0  5136.1     .12       0  5158.3     .05       0
Bank Sta=4973.3,4989.5
XS Rating Curve= 0 ,0
Exp/Cntr=0.3,0.1

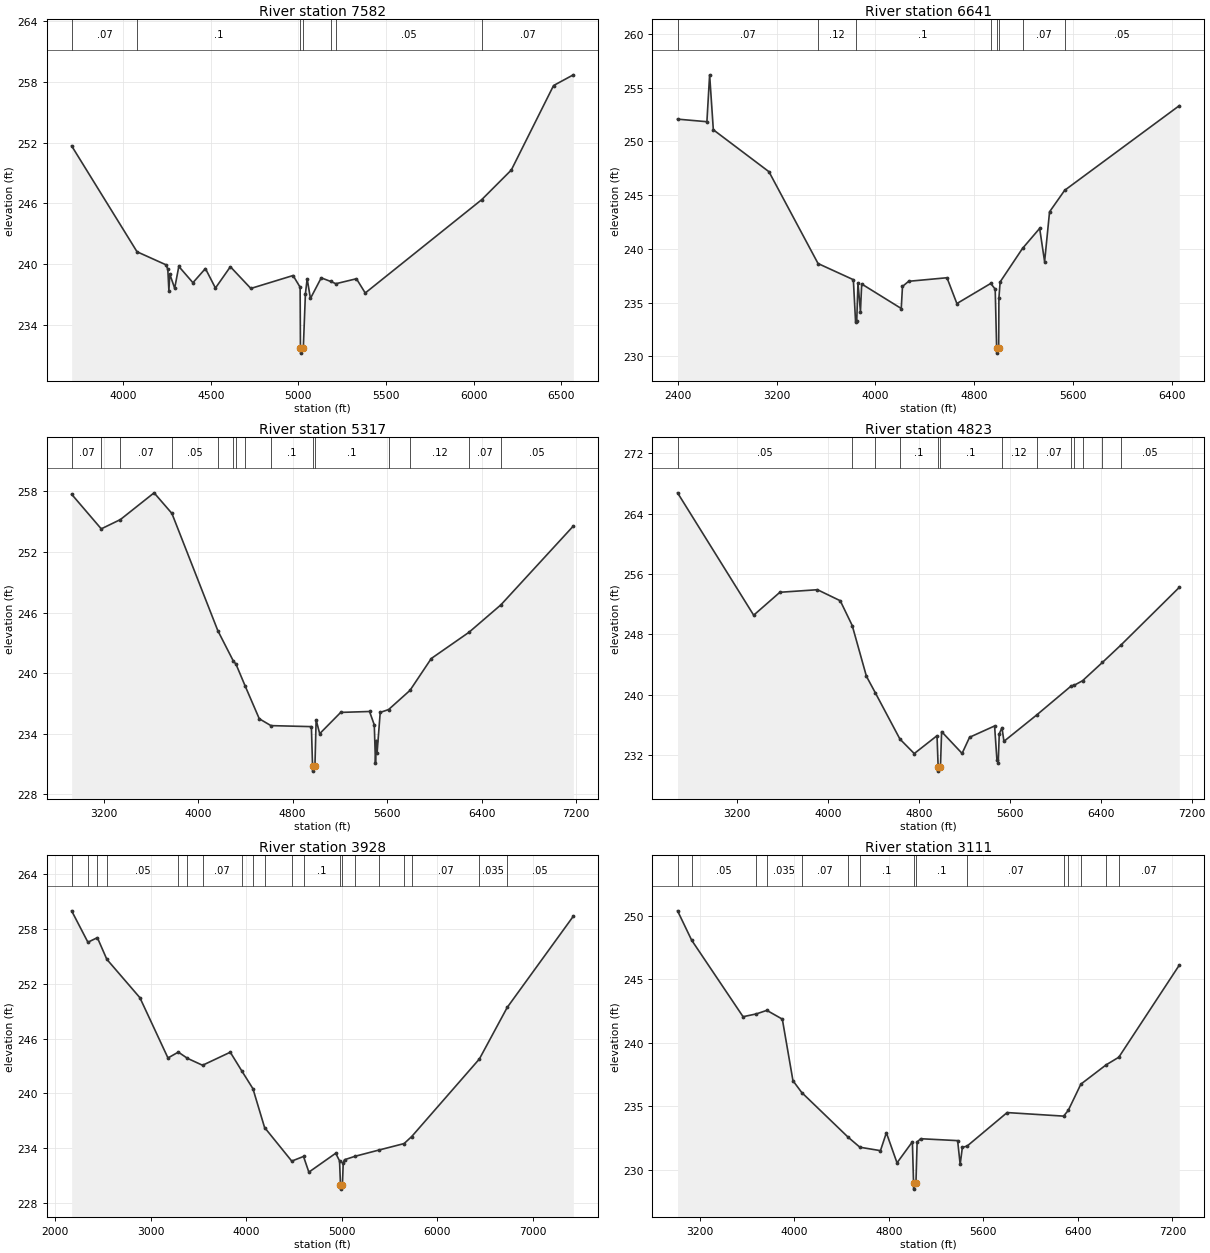
Type RM Length L Ch R = 1 ,7582    ,941,941,941
BEGIN DESCRIPTION:
X18341
END DESCRIPTION:
XS GIS Cut Line= 3
      2464500.11     13674879.48      2463562.68     13675162.48
       2463403.5     13677037.31
#Sta/Elev= 30
    3707  251.68    4080   241.2  4245.1  239.91  4255.5  239.46  4261.6  237.35
  4266.8  238.99  4294.6  237.59  4318.2  239.75  4398.7  238.14  4469.9  239.54
  4527.1  237.61  4612.2  239.72  4728.9  237.57  4969.8  238.85  5009.9  237.69
  5011.8  231.67  5012.3  231.17  5028.1  231.67    5040  237.02    5050  238.53
  5068.8  236.58  5130.3  238.62  5184.6  238.26  5213.9  238.04  5331.1  238.53
  5381.2  237.12    6045  246.35  6214.2  249.29  6455.1  257.65  6567.8  258.71
#Mann= 7 ,-1 , 0
    3707     .07       0    4080      .1       0  5011.8     .05       0
  5028.1      .1       0  5184.6     .12       0  5213.9     .05       0
    6045     .07       0
Bank Sta=5011.8,5028.1
XS Rating Curve= 0 ,0
Exp/Cntr=0.3,0.1

Type RM Length L Ch R = 1 ,6641    ,1324,1324,1324
BEGIN DESCRIPTION:
BRUSHY CREEK 2 4.0
END DESCRIPTION:
XS GIS Cut Line= 3
      2462819.81     13673225.67      2462925.93     13675728.48
      2462952.46       13677285.
#Sta/Elev= 30
  2398.3  252.07  2635.9  251.83  2657.9  256.19  2687.9  251.08  3138.3  247.18
  3535.8  238.64  3821.5  237.14  3839.6   233.2  3848.9  233.28  3858.9  236.85
    3879  234.16    3889  236.74  4209.3  234.46  4219.3  236.51  4269.3  236.99
  4579.6  237.32  4659.7  234.92  4933.8  236.79  4969.9  236.26  4981.6  230.81
  4982.1  230.31  4998.1  230.81  4999.9  235.42  5009.9  236.93  5191.2  240.05
  5329.9  241.91  5369.9  238.82    5410  243.45  5532.2  245.45  6460.1  253.32
#Mann= 8 ,-1 , 0
  2398.3     .07       0  3535.8     .12       0  3839.6      .1       0
  4933.8     .12       0  4981.6     .05       0  4998.1     .12       0
  5191.2     .07       0  5532.2     .05       0
Bank Sta=4981.6,4998.1
XS Rating Curve= 0 ,0
Exp/Cntr=0.3,0.1

Type RM Length L Ch R = 1 ,5317    ,494,494,494
BEGIN DESCRIPTION:
X18340
END DESCRIPTION:
XS GIS Cut Line= 3
      2462253.81     13672907.32      2462315.71     13674737.98
      2462554.32     13677141.76
#Sta/Elev= 30
  2929.8  257.72  3180.6  254.29  3342.6  255.21  3627.9  257.86  3778.7  255.82
  4167.5   244.2    4298  241.21  4321.3  240.88  4400.6  238.67  4518.4  235.47
    4617  234.79  4959.5  234.69  4969.5  230.78    4970  230.28  4989.6  230.78
  4999.7  235.36  5029.8  233.99  5207.8   236.1  5451.9  236.19  5492.1  234.86
  5502.1  231.07  5510.4  233.31  5515.4  232.04  5542.3   236.1    5613  236.38
  5794.2  238.28  5974.5  241.44  6293.8  244.04    6564  246.76  7177.1  254.57
#Mann= 15 ,-1 , 0
  2929.8     .07       0  3180.6    .035       0  3342.6     .07       0
  3778.7     .05       0  4167.5     .07       0    4298     .12       0
  4321.3     .07       0  4400.6     .12       0    4617      .1       0
  4969.5     .05       0  4989.6      .1       0    5613     .07       0
  5794.2     .12       0  6293.8     .07       0    6564     .05       0
Bank Sta=4969.5,4989.6
XS Rating Curve= 0 ,0
Exp/Cntr=0.3,0.1

Type RM Length L Ch R = 1 ,4823    ,895,895,895
BEGIN DESCRIPTION:
X18339
END DESCRIPTION:
XS GIS Cut Line= 3
      2461820.46     13672606.59      2461944.28     13675171.32
      2462359.94     13676966.62
#Sta/Elev= 30
  2680.2  266.77  3349.4  250.54  3579.7  253.58    3910  253.92  4110.3  252.46
  4215.7  249.17  4340.5  242.44    4418  240.27  4635.1  234.11    4761  232.19
  4961.3  234.56  4971.2  230.36  4971.7  229.86  4991.3  230.36  5001.3   235.1
  5181.5  232.21  5247.3  234.35  5467.2  235.85  5487.8  231.36  5499.1  230.95
  5508.3  234.81  5532.2  235.63  5549.4  233.81  5837.5  237.31  6142.7  241.18
  6168.6  241.26  6240.5  241.85  6415.3  244.28  6579.2   246.6  7090.7  254.23
#Mann= 13 ,-1 , 0
  2680.2     .05       0  4215.7     .12       0    4418     .07       0
  4635.1      .1       0  4971.2     .05       0  4991.3      .1       0
  5532.2     .12       0  5837.5     .07       0  6142.7     .12       0
  6168.6     .07       0  6240.5     .12       0  6415.3     .07       0
  6579.2     .05       0
Bank Sta=4971.2,4991.3
XS Rating Curve= 0 ,0
Exp/Cntr=0.3,0.1

Type RM Length L Ch R = 1 ,3928    ,817,817,817
BEGIN DESCRIPTION:
BRUSHY CREEK 2 3.0
END DESCRIPTION:
XS GIS Cut Line= 3
      2461104.12     13672199.83        2461325.       13675025.
        2462325.       13677225.
#Sta/Elev= 30
  2173.6  259.99    2344  256.55    2443  257.05    2542  254.68  2888.2  250.47
  3181.8  243.87    3290  244.51  3385.8  243.83  3544.1  243.07  3833.8   244.5
  3955.1  242.44  4071.1   240.5  4192.9  236.25  4477.3  232.57  4600.4  233.08
  4656.3  231.36  4937.2  233.43  4977.3   232.6  4987.3     230  4987.8   229.5
  5007.4     230  5016.2   232.4  5029.4  232.72  5140.2   233.1  5388.9  233.78
  5652.8  234.49  5732.5  235.26  6440.9  243.76  6731.7   249.4    7424   259.4
#Mann= 20 ,-1 , 0
  2173.6     .07       0    2344     .05       0    2443    .035       0
    2542     .05       0    3290     .07       0  3385.8     .05       0
  3544.1     .07       0  3955.1     .05       0  4071.1     .07       0
  4192.9     .05       0  4477.3     .05       0  4600.4      .1       0
  4987.3     .05       0  5007.4      .1       0  5140.2     .07       0
  5388.9     .07       0  5652.8     .05       0  5732.5     .07       0
  6440.9    .035       0  6731.7     .05       0
Bank Sta=4987.3,5007.4
XS Rating Curve= 0 ,0
Exp/Cntr=0.3,0.1

Type RM Length L Ch R = 1 ,3111    ,817,817,817
BEGIN DESCRIPTION:
X18338
END DESCRIPTION:
XS GIS Cut Line= 3
      2460768.06     13672588.96      2460697.31     13674773.35
      2461448.55     13676691.23
#Sta/Elev= 30
  3012.6  250.38  3131.7  248.07  3567.1  242.04  3678.6  242.26    3768  242.54
  3899.1  241.85  3989.1     237  4063.3  236.07  4457.1  232.54  4555.6  231.76
  4729.5  231.49  4779.6   232.9  4869.6  230.53  4999.7  232.19  5009.5  228.96
    5010  228.46  5029.8  228.96  5039.7  232.17  5069.7  232.43  5382.5  232.28
    5404   230.4  5422.5  231.75  5462.6  231.85  5801.3  234.49  6279.3  234.21
  6318.4  234.66  6425.4  236.73  6639.3  238.25  6746.4  238.85  7257.9   246.1
#Mann= 15 ,-1 , 0
  3012.6    .035       0  3131.7     .05       0  3678.6     .07       0
    3768    .035       0  4063.3     .07       0  4457.1    .035       0
  4555.6      .1       0  5009.5     .05       0  5029.8      .1       0
  5462.6     .07       0  6279.3     .05       0  6318.4     .07       0
  6425.4     .05       0  6639.3     .12       0  6746.4     .07       0
Bank Sta=5009.5,5029.8
XS Rating Curve= 0 ,0
Exp/Cntr=0.3,0.1

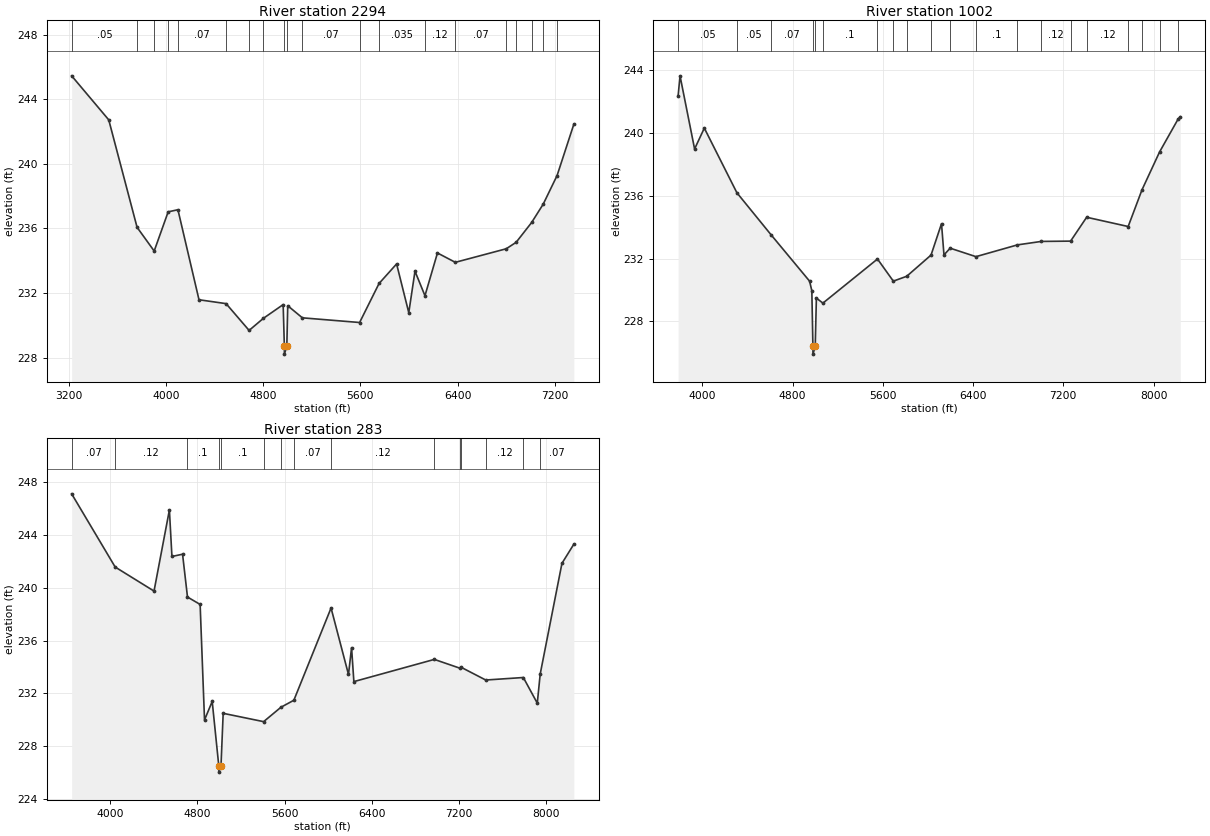
Type RM Length L Ch R = 1 ,2294    ,1292,1292,1292
BEGIN DESCRIPTION:
BRUSHY CREEK 2 2.0
END DESCRIPTION:
XS GIS Cut Line= 3
      2460228.58     13672650.87        2460075.       13674425.
        2461121.     13676531.64
#Sta/Elev= 30
  3224.2  245.46  3529.5  242.73  3762.6  236.07  3903.4   234.6  4018.5  237.03
  4098.8  237.16  4272.2  231.58  4495.1  231.34  4684.5  229.68  4802.3  230.43
  4964.8  231.28  4974.7  228.71  4975.2  228.21    4995  228.71  5002.5  231.21
    5123  230.46    5594  230.17  5754.1  232.59  5898.4   233.8  5998.6  230.78
  6049.7  233.35  6131.8  231.83  6234.6  234.48  6381.7   233.9  6800.5  234.74
  6882.1  235.14  7009.8  236.37  7105.2  237.51  7219.1  239.28    7357  242.46
#Mann= 20 ,-1 , 0
  3224.2     .05       0  3762.6     .07       0  3903.4     .05       0
  4018.5     .05       0  4098.8     .07       0  4495.1     .12       0
  4684.5      .1       0  4802.3    .035       0  4974.7     .05       0
    4995      .1       0    5123     .07       0    5594     .05       0
  5754.1    .035       0  6131.8     .12       0  6381.7     .07       0
  6800.5     .05       0  6882.1     .07       0  7009.8     .07       0
  7105.2     .05       0  7219.1     .07       0
Bank Sta=4974.7,4995
XS Rating Curve= 0 ,0
Exp/Cntr=0.3,0.1

Type RM Length L Ch R = 1 ,1002    ,719,719,719
BEGIN DESCRIPTION:
X18337
END DESCRIPTION:
XS GIS Cut Line= 4
      2459848.31     13672518.19      2459671.43     13673950.88
      2459521.09     13674410.76      2460970.67     13676479.06
#Sta/Elev= 30
  3784.5  242.37  3801.4  243.65  3930.6  238.99  4016.8  240.32  4305.7   236.2
  4610.2  233.51  4950.1  230.57  4970.2  229.96  4979.8  226.42  4980.3  225.92
  5000.4  226.42  5010.6  229.49  5068.4  229.17  5552.4  231.98  5692.8  230.57
  5811.7  230.88  6027.2  232.23  6120.1  234.23    6142  232.24  6196.8  232.67
  6425.4  232.13  6793.5  232.88  7005.3   233.1  7264.9  233.12  7407.1  234.64
  7775.3  234.05    7898  236.39  8053.7   238.8  8218.4   240.9  8237.6  241.04
#Mann= 20 ,-1 , 0
  3784.5     .05       0  4305.7     .05       0  4610.2     .07       0
  4979.8     .05       0  5000.4     .07       0  5068.4      .1       0
  5552.4     .12       0  5692.8    .035       0  5811.7     .07       0
  6027.2     .12       0  6196.8     .05       0  6425.4      .1       0
  6793.5    .035       0  7005.3     .12       0  7264.9    .035       0
  7407.1     .12       0  7775.3     .12       0    7898     .07       0
  8053.7     .05       0  8218.4    .035       0
Bank Sta=4979.8,5000.4
XS Rating Curve= 0 ,0
Exp/Cntr=0.3,0.1

Type RM Length L Ch R = 1 ,283     ,0,0,0
BEGIN DESCRIPTION:
BRUSHY CREEK 2 1.0
END DESCRIPTION:
XS GIS Cut Line= 3
      2458910.87     13672624.37      2459185.02     13674914.85
      2460838.79     13676515.56
#Sta/Elev= 30
  3645.7   247.1  4045.1  241.56  4401.7  239.74  4542.7  245.88  4565.9  242.36
  4663.5  242.53  4708.7  239.29  4824.7  238.73    4865  229.99  4935.5  231.39
  4995.6  226.54  4996.1  226.04  5016.3  226.54  5036.2  230.49  5407.4  229.86
  5566.4  230.95  5684.9  231.48  6026.2  238.46  6186.1  233.43  6214.4  235.46
  6235.5  232.89  6973.9  234.57  7210.3   233.9  7218.3  233.98  7445.7  233.01
  7790.7   233.2  7918.6  231.26  7945.6  233.47    8145  241.84  8254.1  243.29
#Mann= 15 ,-1 , 0
  3645.7     .07       0  4045.1     .12       0  4708.7      .1       0
  4995.6     .05       0  5016.3      .1       0  5407.4     .07       0
  5566.4    .035       0  5684.9     .07       0  6026.2     .12       0
  6973.9    .035       0  7210.3     .12       0  7218.3    .035       0
  7445.7     .12       0  7790.7      .1       0  7945.6     .07       0
Bank Sta=4995.6,5016.3
XS Rating Curve= 0 ,0
Exp/Cntr=0.3,0.1

Chan Stop Cuts=-1
Use User Specified Reach Order=0
Composite Channel Slope=5