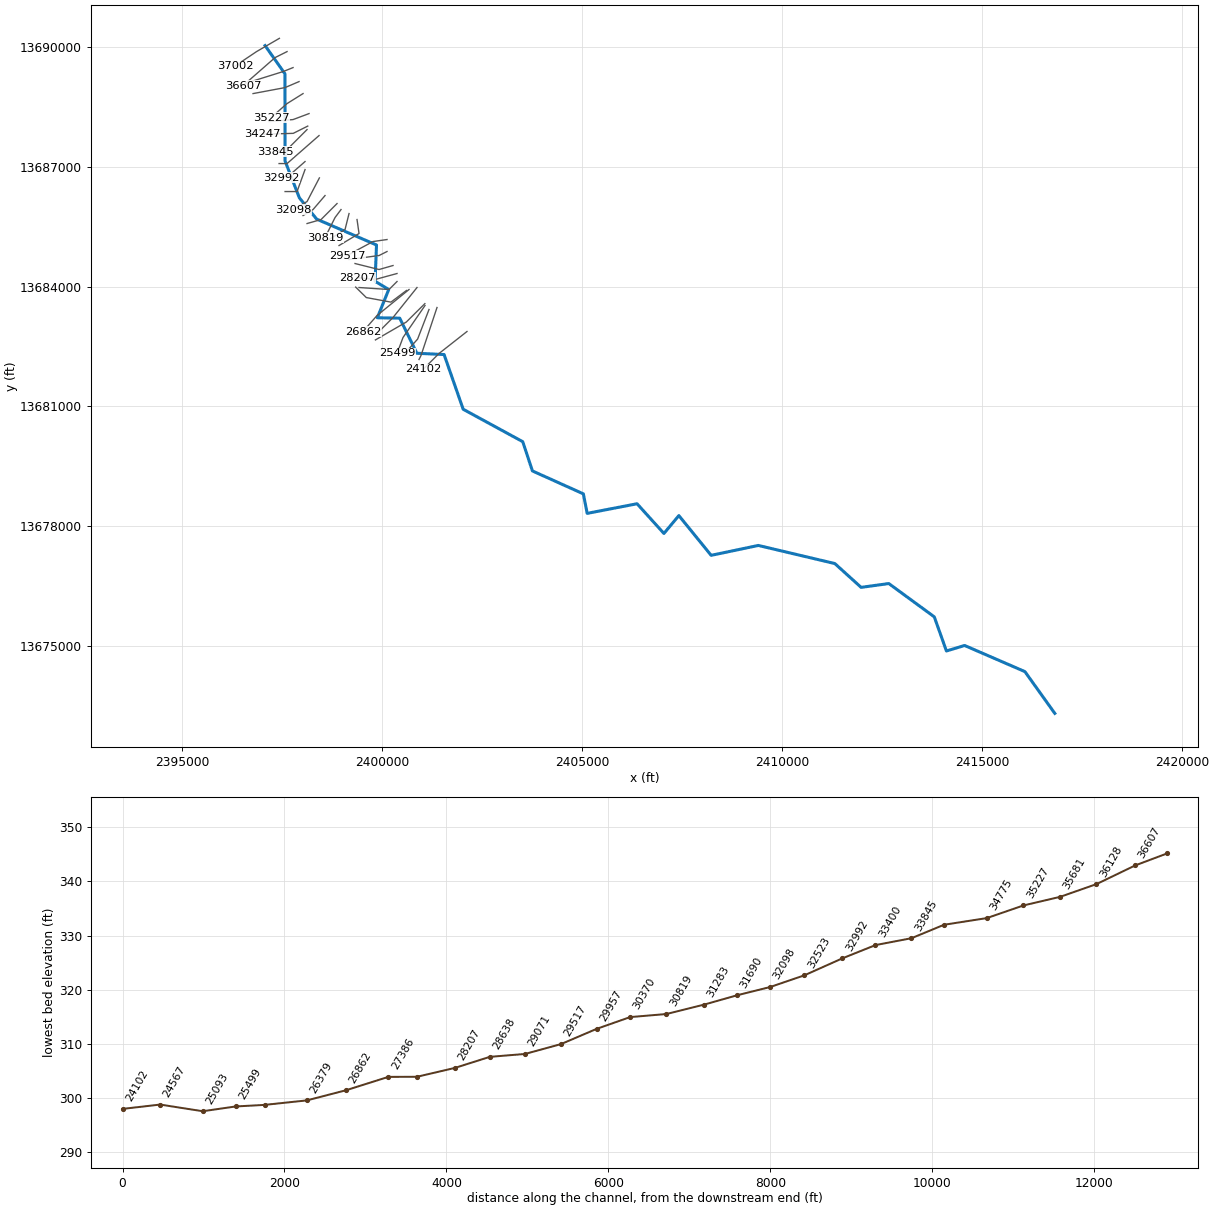
--- BUCKHORN CREEK.prj (project) ---

Proj Title=BUCKHORN CREEK Base Level Engineering
Current Plan=p01
Default Exp/Contr=0.3,0.1
English Units
Geom File=g01
Flow File=f01
Plan File=p01
Y Axis Title=Elevation
X Axis Title(PF)=Main Channel Distance
X Axis Title(XS)=Station
BEGIN DESCRIPTION:
BUCKHORN CREEK
END DESCRIPTION:
DSS Export Rating Curves= 0
DSS Export Rating Curve Sorted= 0
DSS Export Volume Flow Curves= 0
DXF OffsetX= 0
DXF OffsetY= 0
DXF ScaleX= 1
DXF ScaleY= 10

--- BUCKHORN CREEK.p01 (plan) ---

Plan Title=Multiple Run
Short Identifier=Multiple
Geom File=g01
Flow File=f01
Subcritical Flow
K Sum by GR= 0
Std Step Tol= 0.01
Critical Tol= 0.01
Num of Std Step Trials= 20
Max Error Tol= 0.3
Flow Tol Ratio= 0.001
Split Flow NTrial= 30
Split Flow Tol= 0.02
Split Flow Ratio= 0.02
Log Output Level= 0
Friction Slope Method= 1
Unsteady Friction Slope Method= 2
Unsteady Bridges Friction Slope Method= 1
Parabolic Critical Depth
Global Vel Dist=  1 , 1 , 1
Global Log Level= 0
CheckData=True
Encroach Param= -1, 0, 0, 0
BEGIN DESCRIPTION:
Multiple Run
END DESCRIPTION:

--- BUCKHORN CREEK.f01 (steady flow) ---

Flow Title=Multiple
Number of Profiles=7
Profile Names=10-year,25-year,50-year,1pct_min,100-year,1pct_plu,500-year
River Rch & RM= BUCKHORN CREEK,Reach-1,37002
     744    1208    1628    1061    2118    4225    3552
River Rch & RM= BUCKHORN CREEK,Reach-1,29517
    1046    1728    2358    1555    3102    6189    5323
River Rch & RM= BUCKHORN CREEK,Reach-1,26862
    1630    2753    3811    2546    5079   10134    8951
River Rch & RM= BUCKHORN CREEK,Reach-1,23652
    1808    3058    4238    2831    5649   11272    9963
River Rch & RM= BUCKHORN CREEK,Reach-1,20458
    2314    3952    5513    3705    7392   14750   13189
River Rch & RM= BUCKHORN CREEK,Reach-1,15528
    2363    4035    5626    3780    7541   15047   13443
River Rch & RM= BUCKHORN CREEK,Reach-1,11032
    3020    5184    7252    4884    9745   19444   17456
River Rch & RM= BUCKHORN CREEK,Reach-1,244
    3139    5377    7514    5055   10086   20125   18021
Boundary for River Rch & Prof#=BUCKHORN CREEK,Reach-1,1
Up Type=0
Dn Type=3
Dn Slope=0.0024
Boundary for River Rch & Prof#=BUCKHORN CREEK,Reach-1,2
Up Type=0
Dn Type=3
Dn Slope=0.0024
Boundary for River Rch & Prof#=BUCKHORN CREEK,Reach-1,3
Up Type=0
Dn Type=3
Dn Slope=0.0024
Boundary for River Rch & Prof#=BUCKHORN CREEK,Reach-1,4
Up Type=0
Dn Type=3
Dn Slope=0.0024
Boundary for River Rch & Prof#=BUCKHORN CREEK,Reach-1,5
Up Type=0
Dn Type=3
Dn Slope=0.0024
Boundary for River Rch & Prof#=BUCKHORN CREEK,Reach-1,6
Up Type=0
Dn Type=3
Dn Slope=0.0024
Boundary for River Rch & Prof#=BUCKHORN CREEK,Reach-1,7
Up Type=0
Dn Type=3
Dn Slope=0.0024

--- BUCKHORN CREEK.g01 (geometry) ---

Geom Title=Existing Conditions
Program Version=4.10

River Reach=BUCKHORN CREEK  ,Reach-1
Reach XY= 30
        2397075.       13690025.      2397573.03     13689319.11
      2397575.07     13687140.37      2397932.68     13686218.49
      2398364.63     13685686.09      2399861.88     13685038.24
      2399826.56     13684131.08      2400167.99     13683925.21
      2399882.58      13683218.4      2400442.32     13683208.72
      2400872.41     13682330.71      2401552.01     13682298.84
      2402029.78     13680930.61      2403519.45     13680119.41
      2403761.43     13679387.98      2405035.22     13678814.61
      2405130.67     13678326.98      2406378.23     13678567.17
      2407049.87     13677824.46      2407423.41     13678271.33
      2408230.87     13677277.15      2409411.17     13677524.54
      2411323.84     13677071.88      2411981.08     13676476.56
      2412674.03     13676571.46      2413811.52     13675738.56
      2414114.94     13674885.03      2414569.14     13675022.94
      2416077.45     13674369.54        2416825.       13673325.

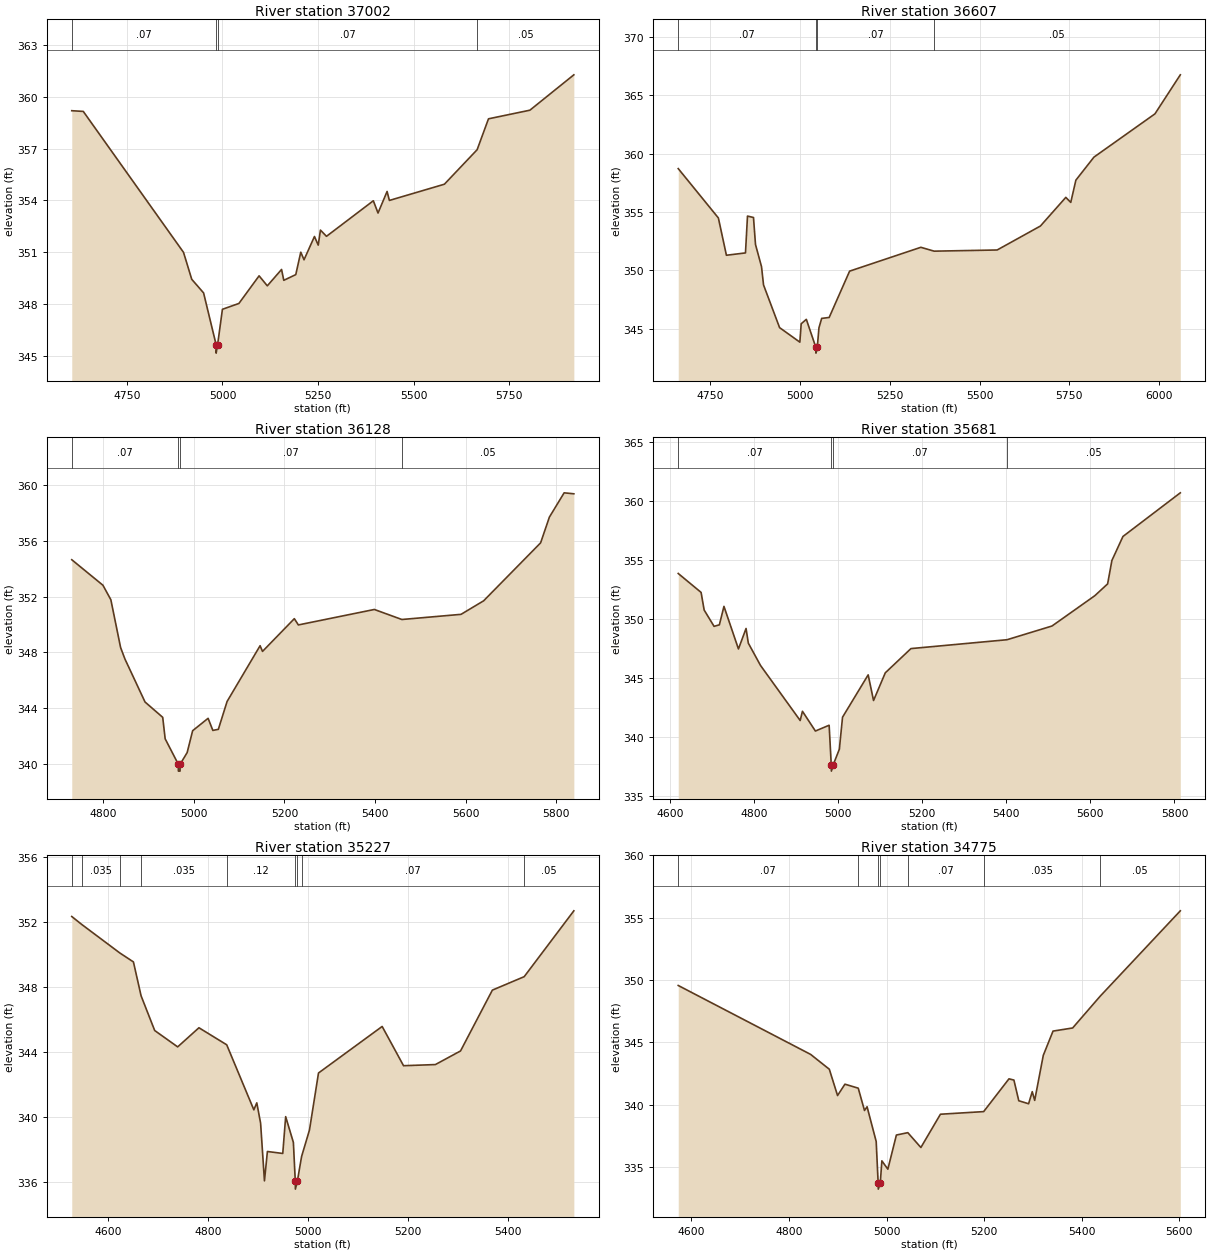
Type RM Length L Ch R = 1 ,37002   ,395,395,395
BEGIN DESCRIPTION:
X18373
END DESCRIPTION:
XS GIS Cut Line= 3
      2397433.34     13690206.64      2396859.35     13689873.22
      2396319.57     13689510.55
#Sta/Elev= 30
  4605.5   359.2  4635.6  359.16    4898  350.99  4919.5  349.43  4950.5  348.64
  4983.2  345.65  4983.4  345.15  4987.3  345.65  4999.8  347.69    5043  348.03
  5095.8  349.63  5117.3  349.05  5154.6     350  5160.4  349.37  5191.8   349.7
  5204.9     351  5213.4  350.56  5240.7  351.91  5250.6  351.41  5256.4  352.28
  5272.2  351.92  5394.8  353.98  5407.1  353.27  5430.8  354.52  5436.8     354
  5580.8  354.94  5666.5  356.94  5696.2  358.73  5804.6  359.23  5919.6  361.28
#Mann= 4 ,-1 , 0
  4605.5     .07       0  4983.2     .05       0  4987.3     .07       0
  5666.5     .05       0
Bank Sta=4983.2,4987.3
XS Rating Curve= 0 ,0
Exp/Cntr=0.3,0.1

Type RM Length L Ch R = 1 ,36607   ,479,479,479
BEGIN DESCRIPTION:
BUCKHORN CREEK 63.0
END DESCRIPTION:
XS GIS Cut Line= 3
      2397625.01       13689875.        2397325.       13689725.
      2396525.03     13689025.02
#Sta/Elev= 30
  4660.6  358.71  4772.4  354.49  4794.8   351.3  4847.9   351.5  4853.5  354.65
  4870.2  354.53  4875.8  352.22  4892.6  350.32  4898.2  348.76  4942.9  345.11
  4999.3  343.87  5003.1  345.44  5017.4  345.82  5043.8  343.43  5044.1  342.93
  5047.9  343.43  5052.5  345.09  5060.1   345.9    5081  345.98  5137.9  349.94
  5336.3  351.98  5373.4  351.65  5548.9  351.75  5669.4   353.8  5740.1  356.25
  5753.9  355.82  5768.1  357.72  5818.4  359.69  5988.3  363.39    6059  366.73
#Mann= 4 ,-1 , 0
  4660.6     .07       0  5043.8     .05       0  5047.9     .07       0
  5373.4     .05       0
Bank Sta=5043.8,5047.9
XS Rating Curve= 0 ,0
Exp/Cntr=0.3,0.1

Type RM Length L Ch R = 1 ,36128   ,447,447,447
BEGIN DESCRIPTION:
BUCKHORN CREEK 62.0
END DESCRIPTION:
XS GIS Cut Line= 3
      2397775.03     13689475.01        2397525.       13689375.
      2396725.05     13689125.01
#Sta/Elev= 30
    4731  354.65  4799.7  352.82  4817.2  351.78  4838.7  348.35  4848.2  347.53
  4892.6  344.44  4931.6  343.34    4937   341.8  4965.9  339.98  4966.2  339.48
  4969.8  339.48  4970.1  339.98  4985.5  340.81  4997.6  342.38  5031.7  343.27
  5042.2   342.4  5054.3  342.48  5073.6  344.48  5146.4  348.48  5151.7  348.07
  5221.9  350.42  5230.8  349.97  5398.4  351.08  5459.1  350.36  5589.6  350.73
  5639.4   351.7  5765.1  355.86  5784.5  357.71    5817  359.45  5838.4  359.38
#Mann= 4 ,-1 , 0
    4731     .07       0  4965.9     .05       0  4970.1     .07       0
  5459.1     .05       0
Bank Sta=4965.9,4970.1
XS Rating Curve= 0 ,0
Exp/Cntr=0.3,0.1

Type RM Length L Ch R = 1 ,35681   ,454,454,454
BEGIN DESCRIPTION:
BUCKHORN CREEK 61.0
END DESCRIPTION:
XS GIS Cut Line= 3
      2397925.02     13689125.01        2397575.       13688975.
      2396774.96     13688824.99
#Sta/Elev= 30
  4619.1  353.85  4673.5  352.25  4680.8  350.76  4704.4  349.38    4717  349.51
  4727.9  351.07  4762.4  347.47  4780.5   349.2  4785.9  347.96    4815  346.07
  4909.3  341.42  4914.7   342.2  4945.5  340.53  4978.2  341.02  4983.3  337.64
  4983.6  337.14  4987.5  337.64  5002.5  338.99  5010.1   341.7  5071.1  345.28
  5083.9  343.11  5111.8  345.45  5172.9   347.5  5401.6  348.25  5508.6  349.41
  5610.4  351.97  5640.9  352.97  5651.1  354.95  5677.4  356.98  5813.9  360.67
#Mann= 4 ,-1 , 0
  4619.1     .07       0  4983.3     .05       0  4987.5     .07       0
  5401.6     .05       0
Bank Sta=4983.3,4987.5
XS Rating Curve= 0 ,0
Exp/Cntr=0.3,0.1

Type RM Length L Ch R = 1 ,35227   ,452,452,452
BEGIN DESCRIPTION:
BUCKHORN CREEK 60.0
END DESCRIPTION:
XS GIS Cut Line= 3
      2398024.97     13688824.98        2397625.       13688575.
      2397224.98     13688224.98
#Sta/Elev= 30
  4527.7  352.36  4547.2  351.88  4623.8  350.11  4650.9  349.56  4666.2  347.47
  4693.4  345.33  4739.3  344.32  4781.8   345.5  4837.3  344.45  4891.5  340.44
  4897.4  340.87    4905  339.62  4912.7  336.06  4918.6  337.87  4949.3  337.75
  4955.1  340.02  4970.5  338.43  4974.3  336.05  4974.5  335.55  4978.5  336.05
  4986.9  337.56  5002.7   339.2  5020.7  342.71  5147.9  345.58  5190.6  343.16
  5254.2  343.23  5304.5  344.07  5368.1  347.82  5431.7  348.65  5530.9  352.71
#Mann= 9 ,-1 , 0
  4527.7     .07       0  4547.2    .035       0  4623.8     .07       0
  4666.2    .035       0  4837.3     .12       0  4974.3     .05       0
  4978.5     .12       0  4986.9     .07       0  5431.7     .05       0
Bank Sta=4974.3,4978.5
XS Rating Curve= 0 ,0
Exp/Cntr=0.3,0.1

Type RM Length L Ch R = 1 ,34775   ,528,528,528
BEGIN DESCRIPTION:
BUCKHORN CREEK 59.0
END DESCRIPTION:
XS GIS Cut Line= 3
      2398174.96     13688324.99        2397775.       13688175.
      2397175.04       13688125.
#Sta/Elev= 30
    4573  349.56  4844.4  344.03  4882.7  342.84  4899.6  340.73  4914.7  341.64
    4942  341.32  4954.8  339.53  4960.1  339.83  4978.8  337.04  4982.8  333.72
  4983.1  333.22  4987.2  333.72  4990.4  335.49  5002.7  334.82  5020.2  337.56
  5043.6  337.75  5070.4  336.56  5110.5  339.23  5199.1  339.44    5251  342.07
  5261.1  341.97  5271.1  340.31  5291.2  340.07  5298.7  341.04  5303.7  340.34
  5321.3  343.95  5341.3   345.9  5381.5  346.15  5437.7  348.69  5602.2  355.55
#Mann= 7 ,-1 , 0
    4573     .07       0    4942     .12       0  4982.8     .05       0
  4987.2     .12       0  5043.6     .07       0  5199.1    .035       0
  5437.7     .05       0
Bank Sta=4982.8,4987.2
XS Rating Curve= 0 ,0
Exp/Cntr=0.3,0.1

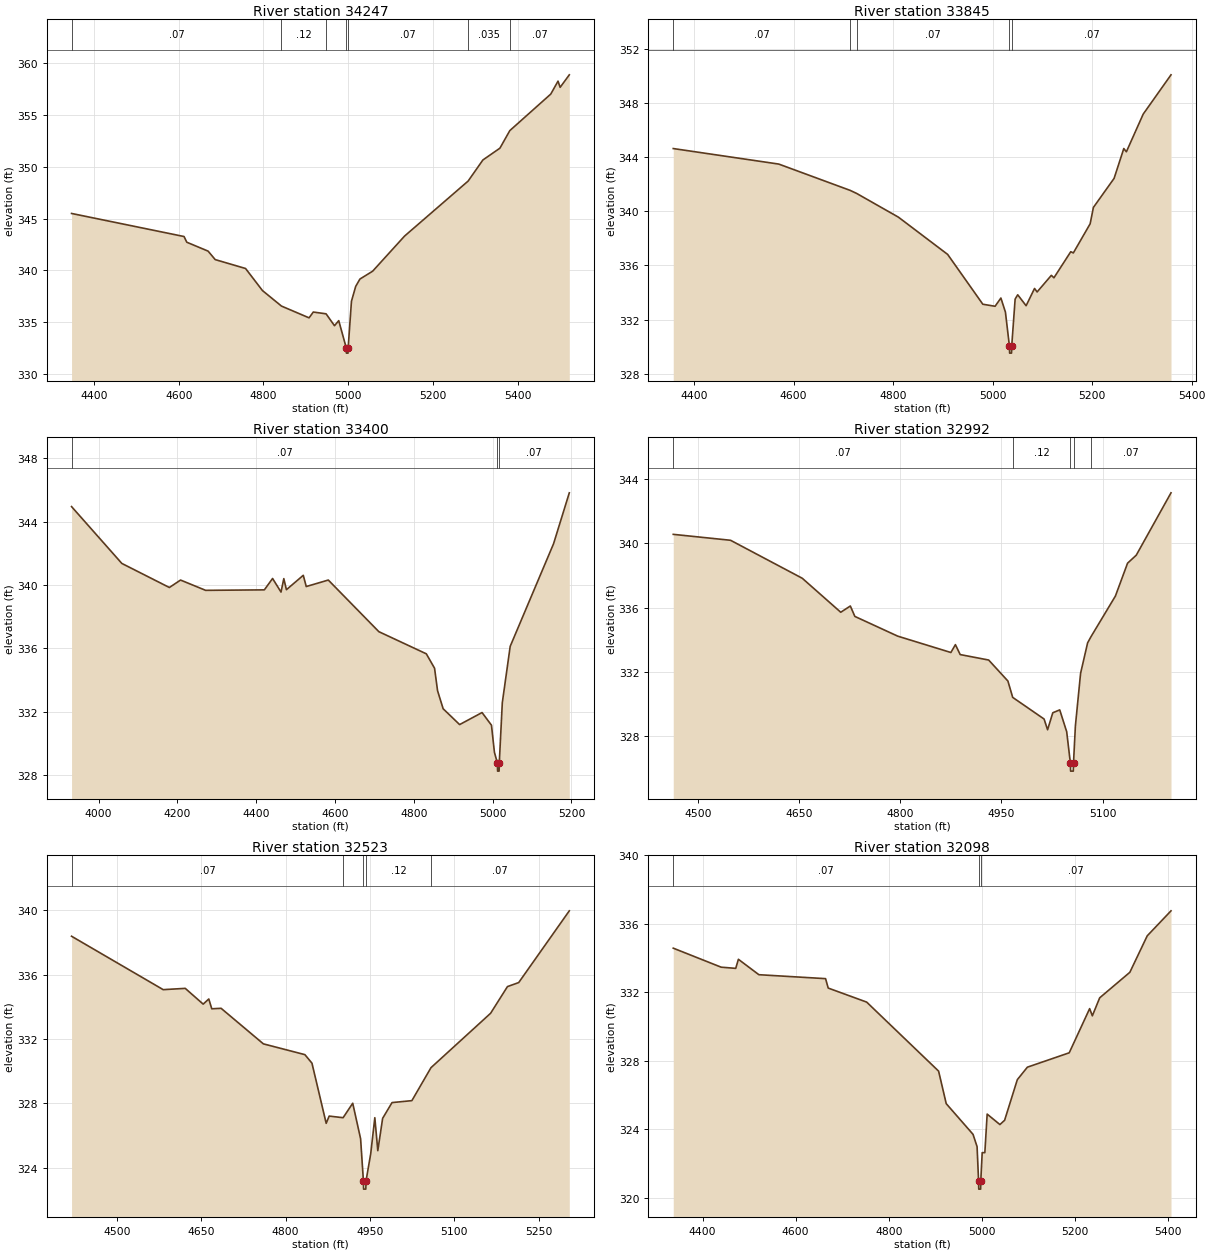
Type RM Length L Ch R = 1 ,34247   ,402,402,402
BEGIN DESCRIPTION:
X18374
END DESCRIPTION:
XS GIS Cut Line= 3
      2398142.39      13688011.9      2397779.44     13687830.43
      2397011.32     13687809.33
#Sta/Elev= 30
  4347.2  345.49  4612.6  343.26    4619  342.71  4669.3  341.85  4686.1  341.03
  4757.7  340.17  4797.5  338.04  4842.3  336.54  4907.5   335.4  4917.5  335.96
  4947.6  335.79  4967.5  334.64  4977.5  335.13  4995.3  332.49  4995.6  331.99
  4999.4  331.99  4999.7  332.49  5007.5     337  5017.5  338.44  5027.5  339.15
  5057.5  339.91  5132.7   343.3  5282.7  348.62  5317.6  350.66  5357.7   351.8
  5381.1   353.5  5477.7  357.03  5494.8  358.28  5499.8  357.68  5521.4  358.89
#Mann= 7 ,-1 , 0
  4347.2     .07       0  4842.3     .12       0  4947.6     .07       0
  4995.3     .05       0  4999.7     .07       0  5282.7    .035       0
  5381.1     .07       0
Bank Sta=4995.3,4999.7
XS Rating Curve= 0 ,0
Exp/Cntr=0.3,0.1

Type RM Length L Ch R = 1 ,33845   ,445,445,445
BEGIN DESCRIPTION:
BUCKHORN CREEK 58.0
END DESCRIPTION:
XS GIS Cut Line= 3
      2398124.97     13687924.97        2397675.       13687475.
      2397324.96     13687374.99
#Sta/Elev= 30
  4358.1  344.66  4570.2  343.51  4713.8  341.56  4726.5  341.34  4810.6  339.58
  4909.6  336.82  4980.3  333.13  5004.9  332.98  5016.6  333.59  5025.7  332.55
  5033.8  330.01  5034.1  329.51    5038  329.51  5038.3  330.01  5045.2  333.51
  5050.4  333.83  5067.3  333.02  5084.2   334.3  5089.4  334.04    5118  335.27
  5123.2  335.09    5157  337.02  5162.2  336.93    5196  339.09  5202.5   340.3
  5244.1  342.45  5263.6  344.66  5268.8  344.42  5302.6  347.21  5358.5  350.12
#Mann= 5 ,-1 , 0
  4358.1     .07       0  4713.8     .12       0  4726.5     .07       0
  5033.8     .05       0  5038.3     .07       0
Bank Sta=5033.8,5038.3
XS Rating Curve= 0 ,0
Exp/Cntr=0.3,0.1

Type RM Length L Ch R = 1 ,33400   ,408,408,408
BEGIN DESCRIPTION:
BUCKHORN CREEK 57.0
END DESCRIPTION:
XS GIS Cut Line= 3
      2398424.98     13687774.98        2397625.       13687075.
      2397424.98       13687075.
#Sta/Elev= 30
  3931.6  344.95  4059.2  341.36  4179.8  339.84  4208.2  340.31  4271.8  339.66
  4420.8  339.69  4441.7  340.41  4463.1  339.55  4470.2   340.4  4476.8   339.7
  4519.6  340.61  4527.1   339.9  4583.1  340.31  4711.3  337.05  4831.8  335.65
  4852.7  334.74  4860.3  333.32  4874.5  332.18  4916.3  331.18  4973.2  331.94
  4997.1  331.14  5004.6  329.43  5012.3  328.74  5012.6  328.24  5016.5  328.24
  5016.9  328.74  5024.6  332.56  5044.6  336.12  5154.6   342.6  5194.6  345.82
#Mann= 3 ,-1 , 0
  3931.6     .07       0  5012.3     .05       0  5016.9     .07       0
Bank Sta=5012.3,5016.9
XS Rating Curve= 0 ,0
Exp/Cntr=0.3,0.1

Type RM Length L Ch R = 1 ,32992   ,469,469,469
BEGIN DESCRIPTION:
BUCKHORN CREEK 56.0
END DESCRIPTION:
XS GIS Cut Line= 3
      2398074.99     13687124.99        2397675.       13686775.
      2397475.04     13686725.01
#Sta/Elev= 30
  4463.7  340.57  4548.6   340.2  4654.9  337.83  4711.9  335.71  4726.1   336.1
  4732.8  335.45  4796.3  334.22  4875.1   333.2  4881.8  333.69  4888.9  333.07
  4931.1  332.73  4959.6  331.42  4966.7   330.4  5013.2  329.05  5018.4  328.38
  5026.1  329.44  5036.4  329.62  5046.7  328.26  5052.2   326.3  5052.5   325.8
  5056.5   325.8  5056.8   326.3  5059.6  328.62  5067.3   331.9  5077.7   333.8
  5082.5  334.17  5118.9  336.72  5136.9  338.77  5149.8  339.27  5201.3  343.16
#Mann= 5 ,-1 , 0
  4463.7     .07       0  4966.7     .12       0  5052.2     .05       0
  5056.8     .12       0  5082.5     .07       0
Bank Sta=5052.2,5056.8
XS Rating Curve= 0 ,0
Exp/Cntr=0.3,0.1

Type RM Length L Ch R = 1 ,32523   ,425,425,425
BEGIN DESCRIPTION:
BUCKHORN CREEK 55.0
END DESCRIPTION:
XS GIS Cut Line= 3
      2398075.01     13686925.02        2397875.       13686375.
      2397574.96       13686375.
#Sta/Elev= 30
  4419.4  338.39  4582.4  335.07  4621.6  335.15  4653.5  334.17  4663.5  334.49
  4668.8  333.88  4685.4  333.91  4760.6   331.7  4834.4  331.03    4847   330.5
  4872.3  326.76  4877.6  327.21  4902.4  327.11  4919.5  328.01  4933.5   325.8
  4938.5  323.17  4938.8  322.67  4942.8  322.67  4943.1  323.17  4951.5  324.87
  4958.8  327.11  4964.1  325.06  4972.7  327.07  4989.4  328.05  5024.7  328.17
  5058.7  330.22  5164.7   333.6  5194.7  335.26  5214.7  335.51  5304.7  339.97
#Mann= 5 ,-1 , 0
  4419.4     .07       0  4902.4     .12       0  4938.5     .05       0
  4943.1     .12       0  5058.7     .07       0
Bank Sta=4938.5,4943.1
XS Rating Curve= 0 ,0
Exp/Cntr=0.3,0.1

Type RM Length L Ch R = 1 ,32098   ,408,408,408
BEGIN DESCRIPTION:
BUCKHORN CREEK 54.0
END DESCRIPTION:
XS GIS Cut Line= 3
      2398433.65     13686716.21        2398125.       13686125.
      2397775.04     13685925.02
#Sta/Elev= 30
  4336.9  334.57  4439.8  333.46  4471.2  333.39  4476.9  333.92    4521  333.02
  4664.3  332.79    4670  332.24  4752.7  331.42  4907.3  327.39  4923.7  325.49
  4981.3   323.7    4990  322.98  4993.2     321  4993.6   320.5  4997.7   320.5
    4998     321    5001  322.63  5006.7  322.63  5011.7  324.88  5039.1  324.27
  5049.2  324.52  5076.5  326.89  5098.1  327.62  5188.1  328.46    5232  331.04
  5237.8  330.62  5253.6  331.67  5318.4  333.16  5355.8  335.29  5406.9  336.75
#Mann= 3 ,-1 , 0
  4336.9     .07       0  4993.2     .05       0    4998     .07       0
Bank Sta=4993.2,4998
XS Rating Curve= 0 ,0
Exp/Cntr=0.3,0.1

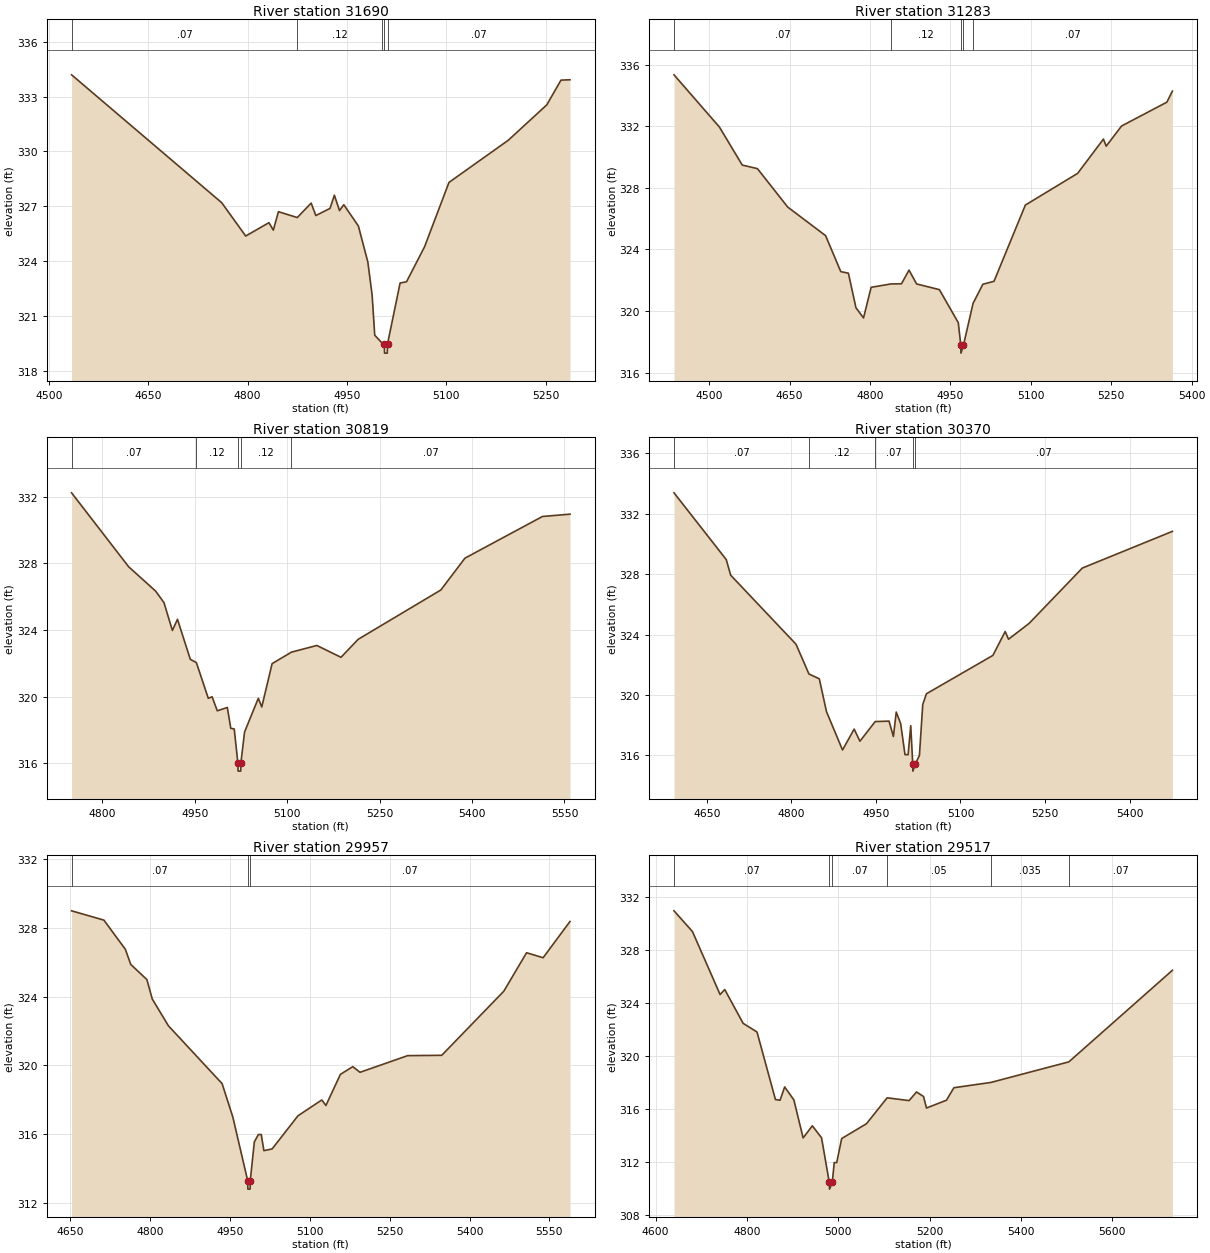
Type RM Length L Ch R = 1 ,31690   ,407,407,407
BEGIN DESCRIPTION:
BUCKHORN CREEK 53.0
END DESCRIPTION:
XS GIS Cut Line= 3
        2398575.       13686275.        2398275.       13685925.
      2398025.03     13685775.02
#Sta/Elev= 30
  4534.2  334.19  4760.9   327.2  4797.1  325.38  4832.2  326.11  4838.8   325.7
  4846.5  326.71    4875  326.39  4895.9  327.18    4903   326.5  4924.4  326.89
    4931  327.61  4938.7  326.77  4945.2  327.09  4967.2  325.93  4981.5  323.96
    4988  322.14  4991.9  319.96    5003  319.53  5006.4  319.48  5006.7  318.98
  5010.8  318.98  5011.2  319.48  5030.2  322.81  5039.9  322.88  5067.1  324.79
    5104  328.31  5193.4  330.61  5251.7  332.55  5273.1   333.9  5286.7  333.92
#Mann= 5 ,-1 , 0
  4534.2     .07       0    4875     .12       0    5003     .07       0
  5006.4     .05       0  5011.2     .07       0
Bank Sta=5006.4,5011.2
XS Rating Curve= 0 ,0
Exp/Cntr=0.3,0.1

Type RM Length L Ch R = 1 ,31283   ,464,464,464
BEGIN DESCRIPTION:
BUCKHORN CREEK 52.0
END DESCRIPTION:
XS GIS Cut Line= 3
      2398874.99     13686074.99        2398475.       13685675.
      2398124.98     13685574.99
#Sta/Elev= 30
  4434.4  335.36  4519.2  331.96  4561.7  329.49    4590  329.26  4646.5  326.76
  4717.2   324.9  4745.5  322.56  4759.7  322.46  4773.8  320.21  4787.9  319.55
  4802.1  321.54  4839.2  321.76  4858.7  321.77  4872.8  322.66  4886.9  321.76
  4929.4  321.39  4964.7  319.24  4969.4  317.76  4969.7  317.26  4974.2  317.76
  4992.3   320.5  5010.5  321.74  5031.3  321.93  5089.8  326.89  5187.3  328.95
  5235.4  331.18  5240.6  330.72  5269.2  332.03  5353.7  333.58  5364.1   334.3
#Mann= 5 ,-1 , 0
  4434.4     .07       0  4839.2     .12       0  4969.4     .05       0
  4974.2     .12       0  4992.3     .07       0
Bank Sta=4969.4,4974.2
XS Rating Curve= 0 ,0
Exp/Cntr=0.3,0.1

Type RM Length L Ch R = 1 ,30819   ,449,449,449
BEGIN DESCRIPTION:
BUCKHORN CREEK 51.0
END DESCRIPTION:
XS GIS Cut Line= 3
      2398975.01     13685925.01        2398825.       13685725.
      2398575.01     13685225.02
#Sta/Elev= 30
    4750  332.23  4842.7  327.79  4886.5  326.33    4900  325.64  4913.6  323.97
  4921.9  324.64  4942.7  322.24  4952.6  322.04  4971.9   319.9  4978.1  319.99
  4986.5  319.15  5002.8  319.35  5008.4   318.1    5014  318.06  5019.9  316.03
  5020.3  315.53  5024.5  315.53  5024.8  316.03  5030.8  317.88  5053.1   319.9
  5058.7  319.38  5075.5  321.98  5106.9  322.67  5148.1  323.07  5187.3  322.36
  5215.2  323.44  5349.4   326.4  5388.5  328.31  5514.3  330.81    5559  330.95
#Mann= 5 ,-1 , 0
    4750     .07       0  4952.6     .12       0  5019.9     .05       0
  5024.8     .12       0  5106.9     .07       0
Bank Sta=5019.9,5024.8
XS Rating Curve= 0 ,0
Exp/Cntr=0.3,0.1

Type RM Length L Ch R = 1 ,30370   ,413,413,413
BEGIN DESCRIPTION:
BUCKHORN CREEK 50.0
END DESCRIPTION:
XS GIS Cut Line= 3
      2399174.99     13685824.97        2399075.       13685425.
      2398674.98     13685174.99
#Sta/Elev= 30
  4591.9  333.38  4684.6  328.96  4692.4  327.93  4808.3  323.36  4831.2  321.39
  4849.6  321.07  4862.4  318.89  4890.8  316.36  4911.4  317.74  4921.7  316.94
  4948.7  318.24  4973.3  318.27    4981  317.25  4986.1  318.87  4993.9  318.11
  5001.6  316.05  5007.1  316.05  5011.8  317.97  5015.3  315.46  5015.6  314.96
  5020.2  315.46  5027.2     316  5033.1  319.37  5039.6  320.08  5157.5  322.62
  5179.3   324.2  5185.2  323.69  5221.8  324.74  5316.1   328.4  5475.9  330.83
#Mann= 5 ,-1 , 0
  4591.9     .07       0  4831.2     .12       0  4948.7     .07       0
  5015.3     .05       0  5020.2     .07       0
Bank Sta=5015.3,5020.2
XS Rating Curve= 0 ,0
Exp/Cntr=0.3,0.1

Type RM Length L Ch R = 1 ,29957   ,440,440,440
BEGIN DESCRIPTION:
BUCKHORN CREEK 49.0
END DESCRIPTION:
XS GIS Cut Line= 3
      2399374.99     13685675.05        2399425.       13685325.
        2398925.       13685025.
#Sta/Elev= 30
  4652.1  328.99  4712.8  328.45  4753.2  326.75  4763.3  325.87  4793.6  324.99
  4803.7  323.86    4834   322.3    4935  318.93  4955.2  316.98    4983  313.29
  4983.4  312.79  4987.6  312.79  4987.9  313.29  4995.6  315.54  5003.2  315.97
  5008.6  315.97  5013.5  315.03    5029  315.13  5077.6  317.06  5122.3  317.98
  5130.1  317.66  5157.3  319.47  5180.6  319.92  5194.2  319.59  5283.6  320.56
  5347.8  320.58  5464.4  324.31  5507.2  326.55  5538.3  326.26  5588.8  328.37
#Mann= 3 ,-1 , 0
  4652.1     .07       0    4983     .05       0  4987.9     .07       0
Bank Sta=4983,4987.9
XS Rating Curve= 0 ,0
Exp/Cntr=0.3,0.1

Type RM Length L Ch R = 1 ,29517   ,446,446,446
BEGIN DESCRIPTION:
BUCKHORN CREEK 48.0
END DESCRIPTION:
XS GIS Cut Line= 3
      2400124.97       13685175.        2399775.       13685125.
      2399124.97     13684774.98
#Sta/Elev= 30
  4640.2  330.95  4680.6  329.39  4741.2  324.64  4751.3  325.02  4791.7  322.47
    4822  321.82  4862.4  316.73  4872.5  316.68  4882.6  317.68  4902.8   316.7
    4923  313.84  4943.2  314.75  4963.4  313.85  4980.4  310.48  4980.9  309.98
  4986.8  310.48  4991.2  311.98  4996.6  311.98  5007.5  313.79  5061.9  314.91
  5107.1  316.86  5155.2  316.65  5171.4   317.3  5186.8  316.96  5193.3  316.09
  5237.1  316.68  5253.3  317.62  5334.5  318.02  5505.2  319.57    5732  326.47
#Mann= 6 ,-1 , 0
  4640.2     .07       0  4980.4     .05       0  4986.8     .07       0
  5107.1     .05       0  5334.5    .035       0  5505.2     .07       0
Bank Sta=4980.4,4986.8
XS Rating Curve= 0 ,0
Exp/Cntr=0.3,0.1

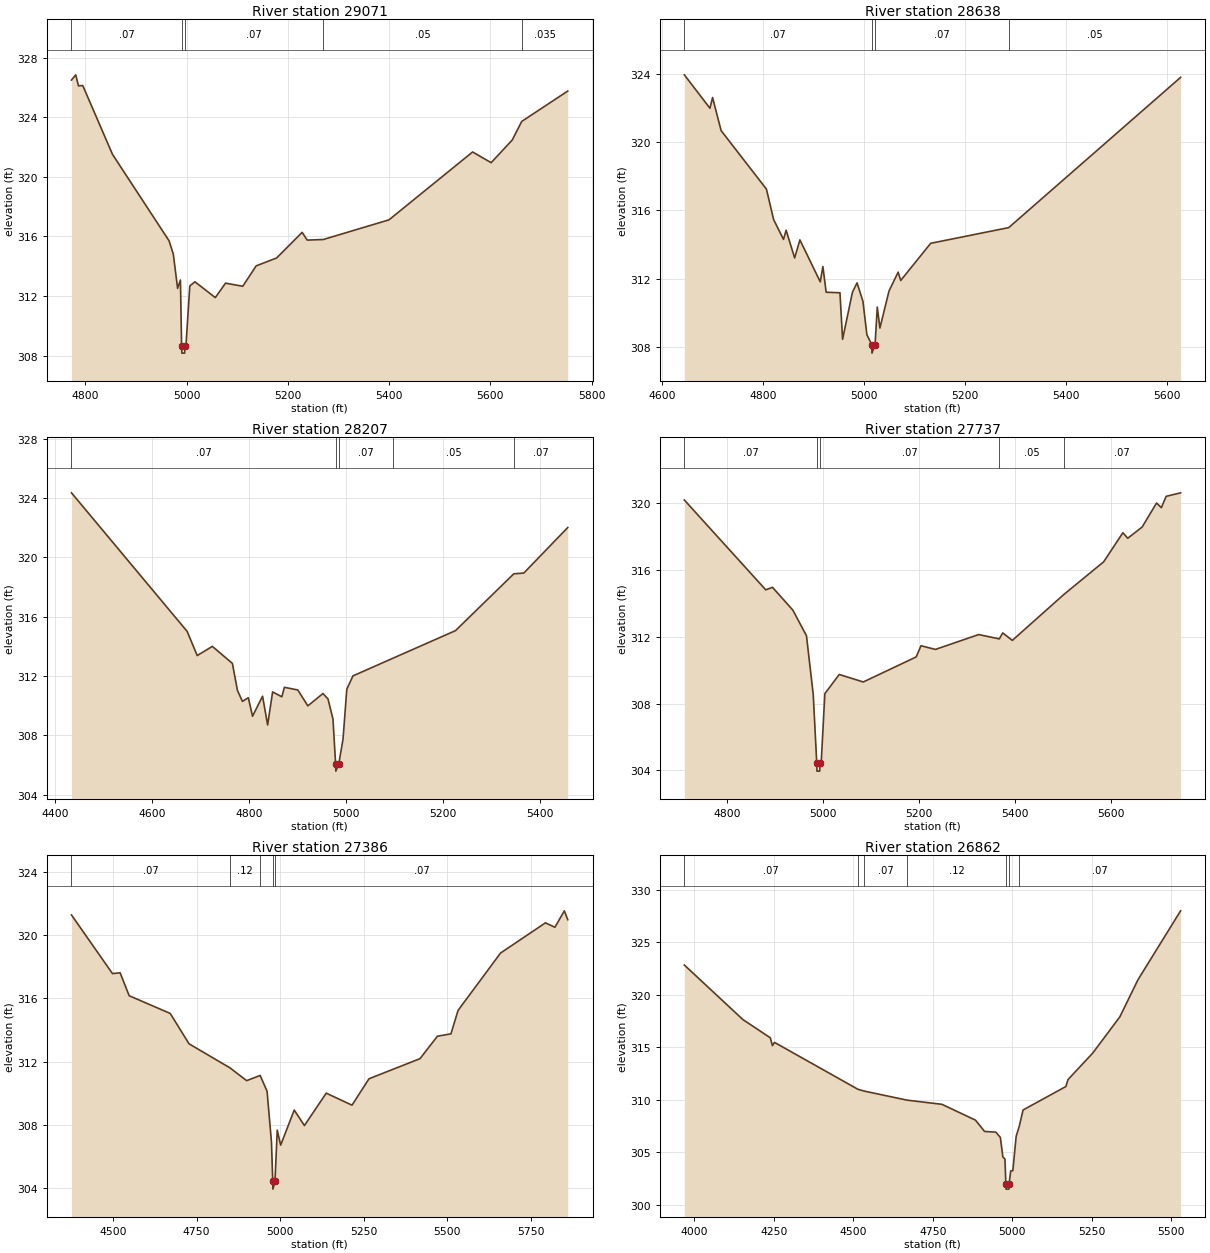
Type RM Length L Ch R = 1 ,29071   ,433,433,433
BEGIN DESCRIPTION:
BUCKHORN CREEK 47.0
END DESCRIPTION:
XS GIS Cut Line= 3
      2400124.97     13684874.99        2399925.       13684775.
      2399175.01       13684675.
#Sta/Elev= 30
  4772.7   326.5  4781.1  326.85  4786.6  326.11    4795  326.13  4853.7  321.51
  4965.5   315.7  4973.9   314.8  4982.3  312.51  4987.9  313.07  4990.2  308.66
  4990.7  308.16  4996.2  308.16  4996.7  308.66  4998.8  308.66  5006.4  312.67
  5016.5  312.95  5056.8  311.89    5077  312.86    5111  312.65  5137.5  314.02
  5177.9  314.55  5228.3  316.27  5238.4  315.75    5270  315.79  5399.8  317.11
    5565  321.67  5601.6  320.95  5643.2  322.47    5662  323.72  5752.9  325.76
#Mann= 5 ,-1 , 0
  4772.7     .07       0  4990.2     .05       0  4996.7     .07       0
    5270     .05       0    5662    .035       0
Bank Sta=4990.2,4996.7
XS Rating Curve= 0 ,0
Exp/Cntr=0.3,0.1

Type RM Length L Ch R = 1 ,28638   ,431,431,431
BEGIN DESCRIPTION:
BUCKHORN CREEK 46.0
END DESCRIPTION:
XS GIS Cut Line= 3
        2400275.       13684525.        2399925.       13684425.
      2399324.98     13684575.01
#Sta/Elev= 30
    4644  323.95  4694.7  321.99  4699.9  322.62  4716.8  320.68  4806.5  317.25
  4820.8  315.46  4840.3   314.3  4845.5  314.84  4862.4  313.21  4872.8  314.27
  4913.1  311.81  4918.3  312.71  4924.8   311.2  4952.1  311.17  4957.3  308.44
  4976.8   311.2  4985.9  311.75  4997.6  310.67  5005.4  308.71    5015  308.13
  5015.5  307.63  5021.6  308.13    5026  310.33  5031.2   309.1  5049.2  311.27
  5067.3  312.38  5072.4  311.89  5131.7  314.07  5286.2  314.99  5626.5   323.8
#Mann= 4 ,-1 , 0
    4644     .07       0    5015     .05       0  5021.6     .07       0
  5286.2     .05       0
Bank Sta=5015,5021.6
XS Rating Curve= 0 ,0
Exp/Cntr=0.3,0.1

Type RM Length L Ch R = 1 ,28207   ,470,470,470
BEGIN DESCRIPTION:
BUCKHORN CREEK 45.0
END DESCRIPTION:
XS GIS Cut Line= 3
      2400375.03     13684325.01        2399825.       13684175.
      2399374.98       13684225.
#Sta/Elev= 30
  4434.3  324.35  4672.7  315.01  4693.5  313.38  4724.6     314    4766  312.85
  4776.4  311.03  4786.7  310.29  4798.8  310.54  4807.5  309.29  4828.2  310.64
  4838.6   308.7  4848.9  310.93  4867.9   310.6  4873.1  311.24  4900.8  311.06
  4921.5  309.99  4952.6  310.82    4963  310.46  4973.3   309.1  4978.7  306.09
  4979.2  305.59  4985.3  306.09    4994  307.74  5001.8  311.11  5014.5  312.01
  5096.9   313.2  5225.8  315.06    5346  318.89  5366.6  318.94  5457.2  322.01
#Mann= 5 ,-1 , 0
  4434.3     .07       0  4978.7     .05       0  4985.3     .07       0
  5096.9     .05       0    5346     .07       0
Bank Sta=4978.7,4985.3
XS Rating Curve= 0 ,0
Exp/Cntr=0.3,0.1

Type RM Length L Ch R = 1 ,27737   ,351,351,351
BEGIN DESCRIPTION:
BUCKHORN CREEK 44.0
END DESCRIPTION:
XS GIS Cut Line= 3
        2400375.       13684125.        2400175.       13683925.
      2399425.01       13683975.
#Sta/Elev= 30
  4710.1  320.19  4879.8  314.81  4893.9  314.96  4936.4  313.59  4964.7  312.06
  4978.8  308.54  4986.1  304.45  4986.6  303.95  4992.3  303.95  4992.8  304.45
  4995.4  304.45    5003  308.59    5033  309.74  5083.1  309.29  5193.4  310.79
  5203.4  311.46  5233.5  311.24  5323.7  312.13  5366.7  311.87  5373.8  312.23
  5393.8  311.78  5501.2  314.53  5584.3  316.49  5624.3  318.23  5634.4   317.9
  5664.4  318.57  5694.5  320.01  5704.5  319.73  5714.5  320.41  5744.6  320.62
#Mann= 5 ,-1 , 0
  4710.1     .07       0  4986.1     .05       0  4992.8     .07       0
  5366.7     .05       0  5501.2     .07       0
Bank Sta=4986.1,4992.8
XS Rating Curve= 0 ,0
Exp/Cntr=0.3,0.1

Type RM Length L Ch R = 1 ,27386   ,524,524,524
BEGIN DESCRIPTION:
X18375
END DESCRIPTION:
XS GIS Cut Line= 4
      2400611.52     13683901.05      2400223.19     13683609.79
      2399606.98     13683723.75      2399341.11      13683985.4
#Sta/Elev= 30
  4375.7  321.28  4498.4  317.57  4521.3  317.62  4548.4  316.17  4671.3  315.05
  4727.5  313.13  4849.9  311.61    4900   310.8  4940.3  311.13    4961  310.13
  4974.2  306.91    4978  304.44  4978.5  303.94  4984.7  304.44  4991.5  307.67
  5001.7  306.72  5042.3  308.94  5072.8  307.96  5138.1  310.01  5215.2  309.25
  5266.1  310.92  5418.6  312.19  5470.8  313.61  5511.3  313.76  5532.5  315.24
  5659.7  318.87  5794.1  320.78  5822.4   320.5  5850.7  321.54  5860.8  320.98
#Mann= 5 ,-1 , 0
  4375.7     .07       0  4849.9     .12       0  4940.3     .07       0
    4978     .05       0  4984.7     .07       0
Bank Sta=4978,4984.7
XS Rating Curve= 0 ,0
Exp/Cntr=0.3,0.1

Type RM Length L Ch R = 1 ,26862   ,483,483,483
BEGIN DESCRIPTION:
BUCKHORN CREEK 43.0
END DESCRIPTION:
XS GIS Cut Line= 3
      2400675.03     13683925.03        2399875.       13683275.
      2399525.02     13682875.02
#Sta/Elev= 30
  3968.1  322.85  4152.7  317.64  4238.7  315.91  4245.4  315.16  4251.9  315.47
  4514.3     311  4533.4  310.83    4669  309.96  4779.1  309.56  4884.7  308.05
  4913.4  306.97  4948.6  306.91    4963   306.4  4970.9  304.54  4977.4  304.34
  4980.3  301.97  4980.8  301.47  4989.8  301.47  4990.3  301.97  4995.7  303.22
  5002.2  303.22  5012.7   306.5  5022.6  307.48  5034.5  309.02  5169.3  311.26
  5175.9  311.92  5253.8  314.45  5339.2  317.91  5396.1  321.44  5530.4  328.02
#Mann= 7 ,-1 , 0
  3968.1     .07       0  4514.3     .12       0  4533.4     .07       0
    4669     .12       0  4980.3     .05       0  4990.3     .12       0
  5022.6     .07       0
Bank Sta=4980.3,4990.3
XS Rating Curve= 0 ,0
Exp/Cntr=0.3,0.1

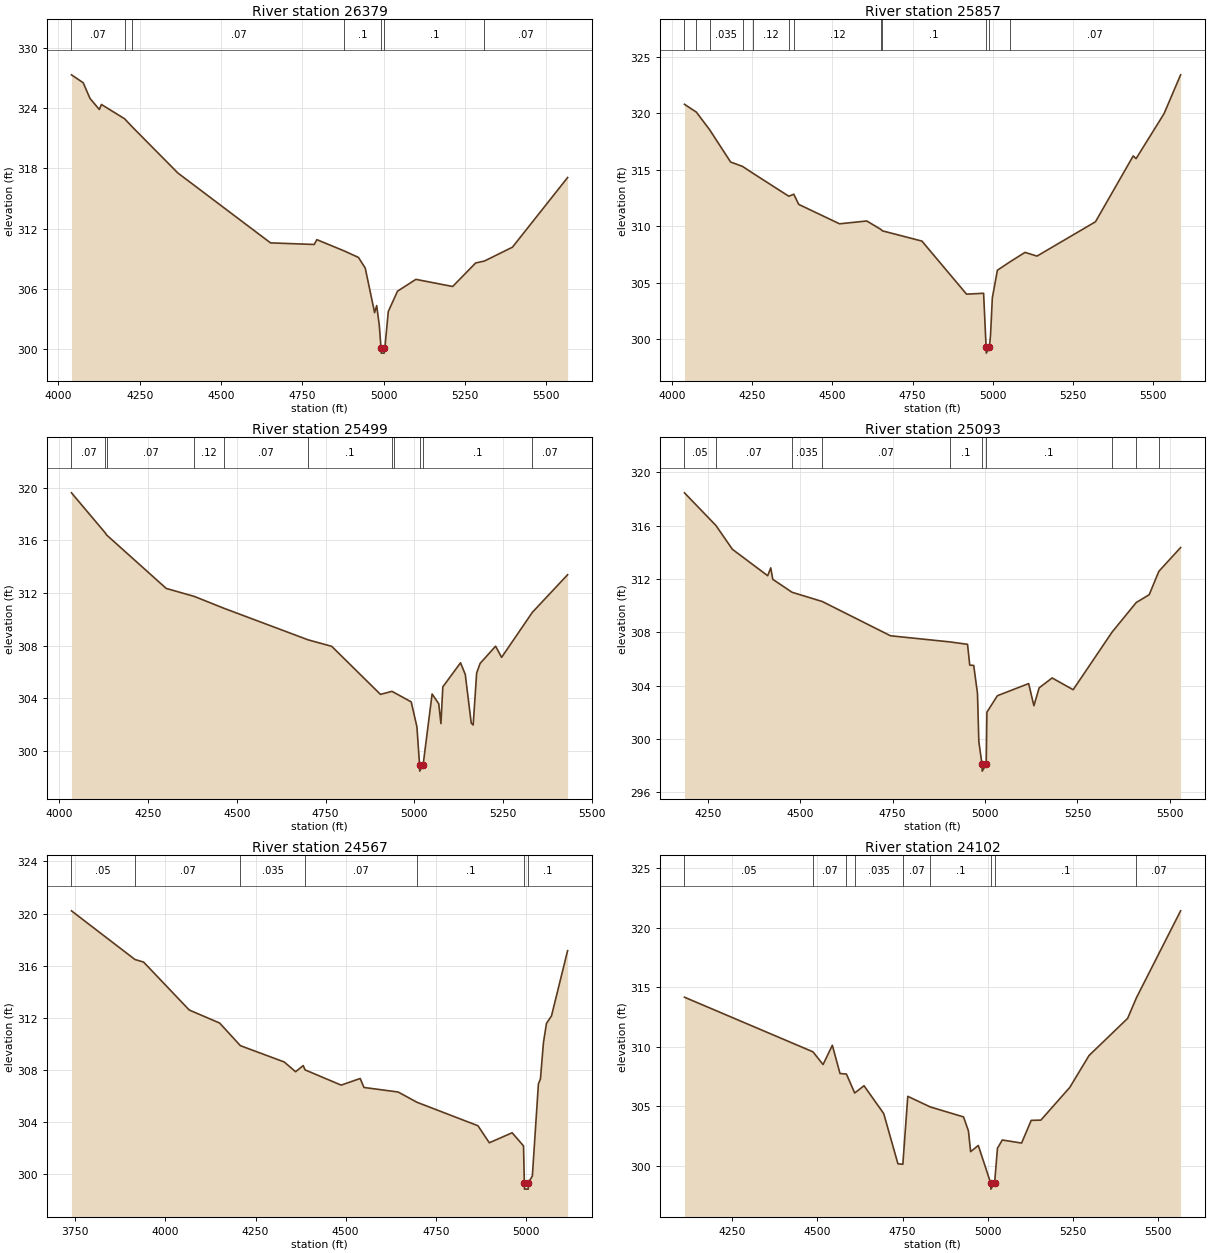
Type RM Length L Ch R = 1 ,26379   ,522,522,522
BEGIN DESCRIPTION:
BUCKHORN CREEK 42.0
END DESCRIPTION:
XS GIS Cut Line= 3
      2400875.02     13683975.03        2400275.       13683225.
      2399874.99     13682824.99
#Sta/Elev= 30
    4040  327.29  4076.1   326.5  4096.9  324.95  4125.7  323.84  4132.1  324.34
  4203.4  322.92  4227.6  322.09  4367.4  317.52  4652.3  310.57  4786.8  310.41
  4794.8  310.89  4879.7  309.76  4922.9  309.12  4943.7  308.06  4972.5  303.63
  4978.9  304.33  4986.9  302.38  4992.3   300.1  4992.8   299.6  5001.9   299.6
  5002.4   300.1    5004   300.1  5014.6  303.74  5042.9  305.76  5099.5  306.94
  5212.6  306.23  5283.3  308.57  5310.1  308.76  5396.5  310.14  5566.2  317.07
#Mann= 7 ,-1 , 0
    4040     .07       0  4203.4    .035       0  4227.6     .07       0
  4879.7      .1       0  4992.3     .05       0  5002.4      .1       0
  5310.1     .07       0
Bank Sta=4992.3,5002.4
XS Rating Curve= 0 ,0
Exp/Cntr=0.3,0.1

Type RM Length L Ch R = 1 ,25857   ,358,358,358
BEGIN DESCRIPTION:
X18376
END DESCRIPTION:
XS GIS Cut Line= 3
      2401071.57     13683571.84      2400607.27     13683111.76
      2399834.93     13682664.39
#Sta/Elev= 30
  4038.9   320.8  4075.9  320.11  4117.3  318.55  4182.7  315.69    4220   315.3
    4252   314.7  4364.1  312.66  4379.6  312.84  4394.9  311.94  4522.2  310.22
    4607  310.47  4651.8  309.71  4655.4   309.6  4778.9  308.69    4918  303.99
  4971.1  304.07    4979  299.27  4979.5  298.77  4989.1  299.27  4992.6  300.31
  4998.4  303.67  5014.1  306.11  5053.2  306.85  5100.3  307.69  5137.5  307.36
  5319.8   310.4  5437.4  316.23  5446.3  315.99  5533.5  319.97  5585.1  323.41
#Mann= 12 ,-1 , 0
  4038.9     .05       0  4075.9     .07       0  4117.3    .035       0
    4220     .07       0    4252     .12       0  4364.1     .07       0
  4379.6     .12       0  4651.8     .07       0  4655.4      .1       0
    4979     .05       0  4989.1      .1       0  5053.2     .07       0
Bank Sta=4979,4989.1
XS Rating Curve= 0 ,0
Exp/Cntr=0.3,0.1

Type RM Length L Ch R = 1 ,25499   ,406,406,406
BEGIN DESCRIPTION:
BUCKHORN CREEK 41.0
END DESCRIPTION:
XS GIS Cut Line= 3
      2401074.97     13683524.96        2400525.       13682725.
      2400374.99     13682324.98
#Sta/Elev= 30
    4034  319.62  4129.1  316.58  4133.4  316.41  4300.9  312.36  4380.2  311.75
  4463.7  310.85  4701.2  308.45  4767.3  307.96  4904.7  304.31    4937  304.54
  4943.3  304.45  4991.3  303.74  5007.4  301.85  5014.8  298.98  5015.3  298.48
    5025  298.98  5050.2  304.34  5068.9   303.6  5075.1  302.09  5080.4  304.88
  5130.3  306.71  5143.6  305.83  5160.5  302.13  5165.9  301.98  5175.7  305.93
  5185.4  306.66  5229.1  307.97    5246  307.12  5332.6  310.54    5432   313.4
#Mann= 11 ,-1 , 0
    4034     .07       0  4129.1    .035       0  4133.4     .07       0
  4380.2     .12       0  4463.7     .07       0  4701.2      .1       0
    4937     .07       0  4943.3      .1       0  5014.8     .05       0
    5025      .1       0  5332.6     .07       0
Bank Sta=5014.8,5025
XS Rating Curve= 0 ,0
Exp/Cntr=0.3,0.1

Type RM Length L Ch R = 1 ,25093   ,526,526,526
BEGIN DESCRIPTION:
BUCKHORN CREEK 40.0
END DESCRIPTION:
XS GIS Cut Line= 3
      2401175.01     13683425.02      2400890.05     13682685.48
      2400524.97     13682274.97
#Sta/Elev= 30
  4187.1  318.45  4272.3     316  4316.7  314.22  4412.2  312.24  4420.5  312.83
  4425.9  311.97  4478.1     311  4559.6  310.31  4744.4  307.74  4905.5  307.28
  4952.7   307.1  4958.7  305.54  4969.4  305.52  4979.6  303.43  4983.3   299.8
  4991.9   298.1  4992.4   297.6  5003.2   298.1  5005.1  302.02  5033.5  303.25
    5118  304.16  5132.2   302.5  5146.4  303.84  5181.5  304.58  5238.4   303.7
  5343.5  308.01  5408.9  310.23  5444.1  310.82  5470.2  312.57    5529  314.35
#Mann= 10 ,-1 , 0
  4187.1     .05       0  4272.3     .07       0  4478.1    .035       0
  4559.6     .07       0  4905.5      .1       0  4991.9     .05       0
  5003.2      .1       0  5343.5     .07       0  5408.9      .1       0
  5470.2     .07       0
Bank Sta=4991.9,5003.2
XS Rating Curve= 0 ,0
Exp/Cntr=0.3,0.1

Type RM Length L Ch R = 1 ,24567   ,465,465,465
BEGIN DESCRIPTION:
BUCKHORN CREEK 39.0
END DESCRIPTION:
XS GIS Cut Line= 3
      2401375.01     13683475.02        2400975.       13682275.
      2400925.02     13682175.03
#Sta/Elev= 30
  3739.1  320.21  3915.3  316.47  3939.4  316.27  4065.9  312.59  4150.2  311.59
  4207.9  309.85  4329.4   308.6    4361  307.85  4382.1  308.32  4387.4  307.99
  4487.5  306.82  4540.2  307.33  4550.8  306.64  4645.6  306.29  4698.1   305.5
    4867   303.7  4898.6  302.39  4961.9  303.16  4993.5  302.15  4995.7  299.33
  4996.2  298.83  5006.5  298.83    5007  299.33    5018  299.84  5034.8  306.92
  5040.4  307.29  5048.8  310.09  5057.1  311.56  5071.1  312.14  5115.8  317.15
#Mann= 7 ,-1 , 0
  3739.1     .05       0  3915.3     .07       0  4207.9    .035       0
  4387.4     .07       0  4698.1      .1       0  4995.7     .05       0
    5007      .1       0
Bank Sta=4995.7,5007
XS Rating Curve= 0 ,0
Exp/Cntr=0.3,0.1

Type RM Length L Ch R = 1 ,24102   ,450,450,450
BEGIN DESCRIPTION:
BUCKHORN CREEK 38.0
END DESCRIPTION:
XS GIS Cut Line= 3
      2402125.02     13682875.02        2401425.       13682325.
      2401025.03     13681925.03
#Sta/Elev= 30
  4109.9  314.16    4487  309.57  4516.6   308.5  4543.8  310.12  4566.3  307.75
  4585.2   307.7  4609.4  306.11  4636.8  306.72  4694.6  304.38  4736.3  300.16
  4750.7  300.12  4765.2  305.83    4831  304.94  4928.8   304.1  4943.2  302.92
  4949.6  301.18  4972.1   301.7  5008.6  298.53  5009.1  298.03  5019.9  298.53
  5028.4  301.47  5042.6  302.16  5099.1   301.9  5127.4  303.81  5155.7  303.83
  5240.6  306.58  5297.1  309.26  5410.3  312.38  5436.1  314.11  5565.8  321.42
#Mann= 9 ,-1 , 0
  4109.9     .05       0    4487     .07       0  4585.2      .1       0
  4609.4    .035       0  4750.7     .07       0    4831      .1       0
  5008.6     .05       0  5019.9      .1       0  5436.1     .07       0
Bank Sta=5008.6,5019.9
XS Rating Curve= 0 ,0
Exp/Cntr=0.3,0.1