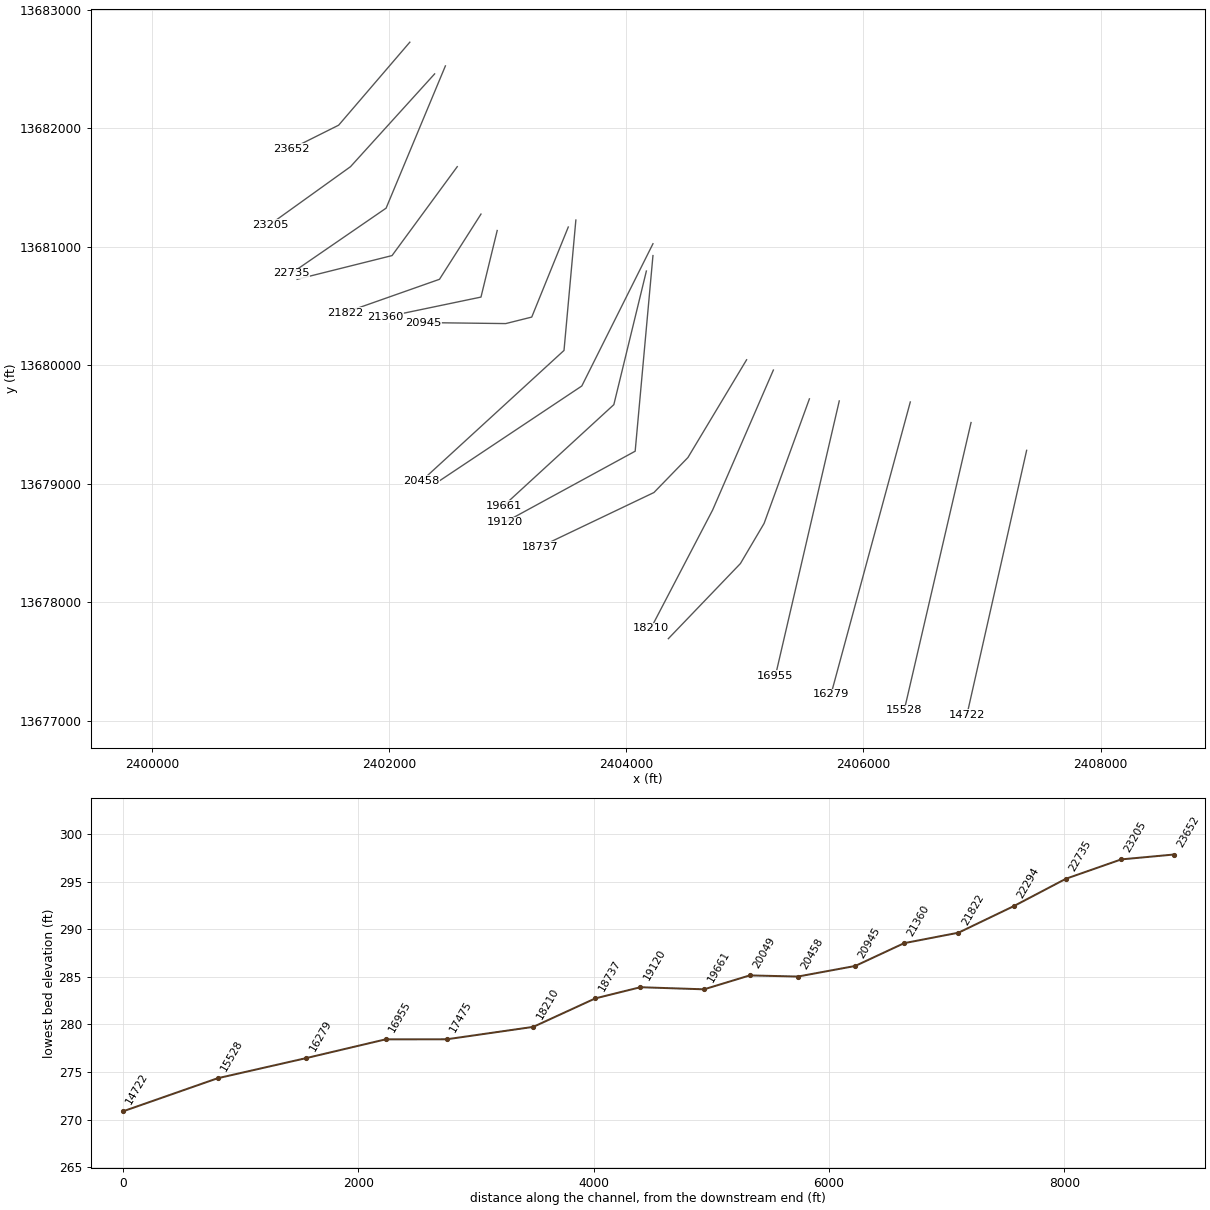
HEC-RAS study BUCKHORN CREEK.prj: BUCKHORN CREEK Base Level Engineering

--- BUCKHORN CREEK.g01 (geometry) --- (continued)

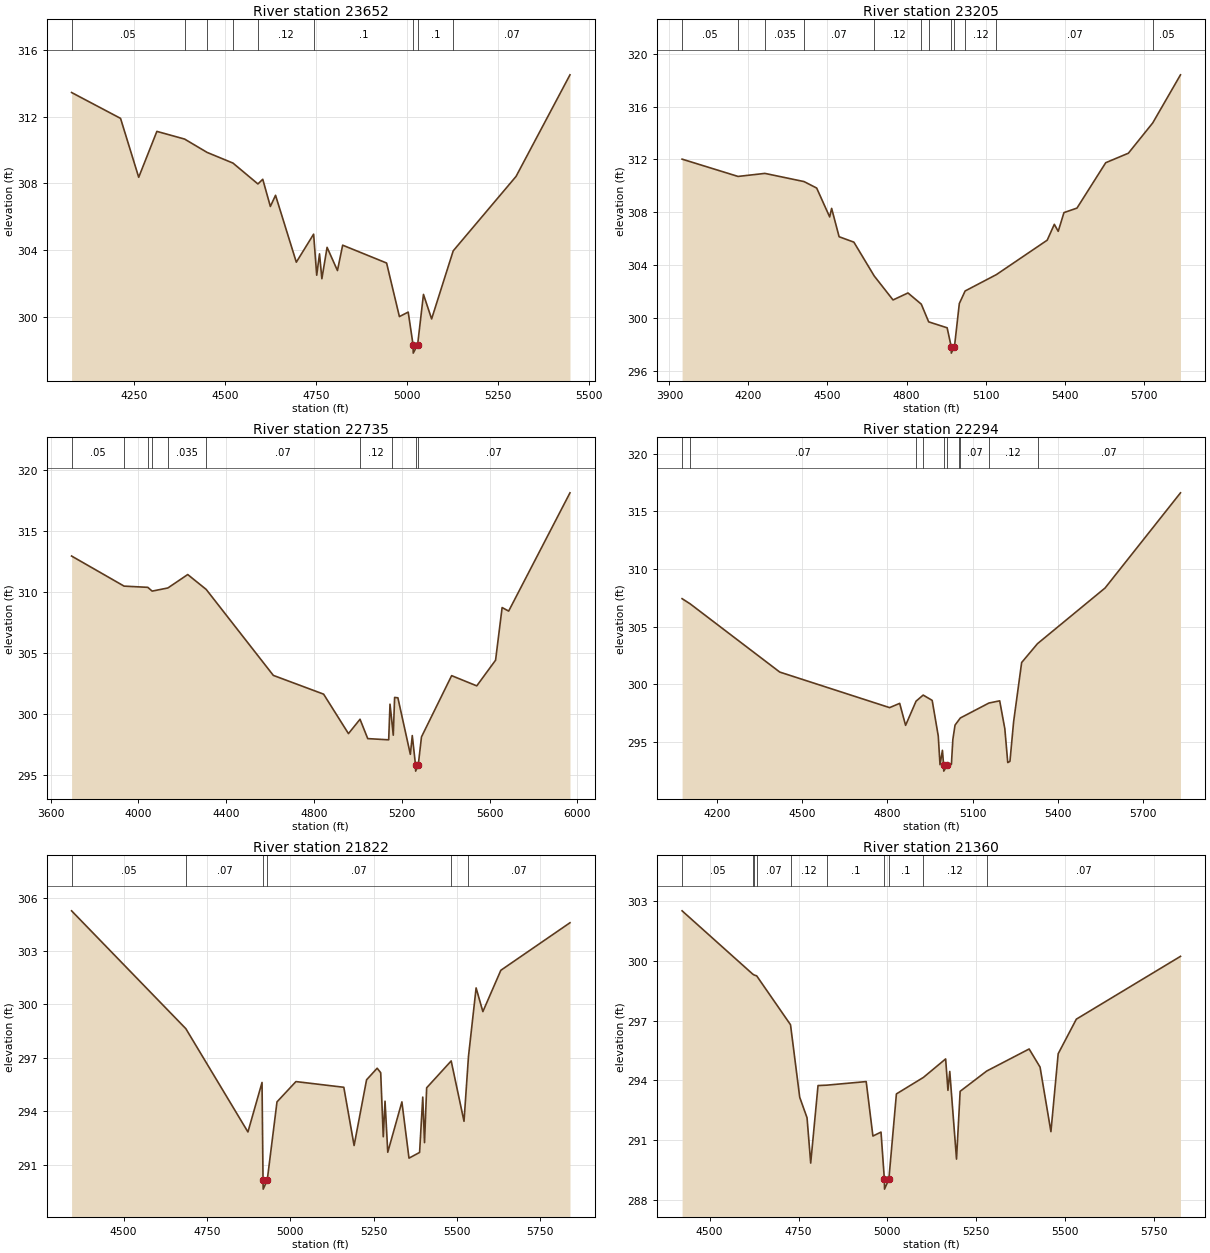
Type RM Length L Ch R = 1 ,23652   ,447,447,447
BEGIN DESCRIPTION:
BUCKHORN CREEK 37.0
END DESCRIPTION:
XS GIS Cut Line= 3
      2402175.01     13682725.01        2401575.       13682025.
      2401174.99     13681824.99
#Sta/Elev= 30
  4077.9  313.45  4212.4   311.9  4262.3  308.37  4312.2  311.12  4388.3  310.66
  4450.2  309.86  4521.3  309.22  4589.8  307.97  4603.1  308.25    4624  306.62
  4638.2  307.29  4695.3  303.28  4742.8  304.96  4751.3   302.5    4759  303.78
  4765.5  302.29  4779.8  304.17  4808.3  302.78  4822.6   304.3  4943.3  303.23
  4978.5  300.02  5002.7  300.29    5016  298.33  5016.5  297.83  5028.5  298.33
  5044.6  301.35    5067  299.88  5126.3  303.96  5298.9  308.42  5447.1  314.51
#Mann= 9 ,-1 , 0
  4077.9     .05       0  4388.3     .07       0  4450.2    .035       0
  4521.3     .07       0  4589.8     .12       0  4742.8      .1       0
    5016     .05       0  5028.5      .1       0  5126.3     .07       0
Bank Sta=5016,5028.5
XS Rating Curve= 0 ,0
Exp/Cntr=0.3,0.1

Type RM Length L Ch R = 1 ,23205   ,470,470,470
BEGIN DESCRIPTION:
BUCKHORN CREEK 36.0
END DESCRIPTION:
XS GIS Cut Line= 3
      2402384.17     13682457.58        2401675.       13681675.
       2400995.6     13681187.17
#Sta/Elev= 30
  3947.9  312.02  4160.4  310.71  4262.3  310.94    4411  310.32  4458.9  309.83
  4508.3  307.64  4515.7  308.29  4544.1  306.14  4600.2  305.73  4677.3  303.17
  4748.9  301.35  4805.6  301.88  4856.2  301.03  4884.2  299.69  4954.3  299.24
  4969.7  297.82  4970.2  297.32  4982.2  297.82  5000.6  301.08  5022.6  302.03
  5141.3  303.27  5334.3  305.88  5361.3  307.08  5376.1  306.55  5397.9  307.97
  5447.3  308.31  5556.5  311.75  5642.5  312.47  5734.8  314.76  5840.4  318.41
#Mann= 12 ,-1 , 0
  3947.9     .05       0  4160.4     .07       0  4262.3    .035       0
    4411     .07       0  4677.3     .12       0  4856.2     .07       0
  4884.2      .1       0  4969.7     .05       0  4982.2      .1       0
  5022.6     .12       0  5141.3     .07       0  5734.8     .05       0
Bank Sta=4969.7,4982.2
XS Rating Curve= 0 ,0
Exp/Cntr=0.3,0.1

Type RM Length L Ch R = 1 ,22735   ,441,441,441
BEGIN DESCRIPTION:
BUCKHORN CREEK 35.0
END DESCRIPTION:
XS GIS Cut Line= 3
      2402474.99     13682524.97        2401975.       13681325.
      2401174.99     13680774.99
#Sta/Elev= 30
  3695.6  312.95  3934.8  310.48  4042.8  310.38  4062.7  310.07  4134.4  310.33
  4224.8  311.43  4308.9  310.21  4614.8  303.15  4843.9  301.61  4957.1  298.37
  5009.8  299.55  5044.9  297.96  5140.4  297.86  5146.4  300.79  5153.5  299.61
  5161.3  298.24  5167.4  301.34  5182.3  301.31  5239.1  296.67  5247.9  298.21
  5262.6  295.79  5263.1  295.29  5275.1  295.79  5289.8   298.1  5427.2  303.13
  5541.7  302.29  5627.4   304.4  5657.2  308.72    5687  308.43  5966.4  318.14
#Mann= 10 ,-1 , 0
  3695.6     .05       0  3934.8     .07       0  4042.8     .12       0
  4062.7     .07       0  4134.4    .035       0  4308.9     .07       0
  5009.8     .12       0  5153.5     .07       0  5262.6     .05       0
  5275.1     .07       0
Bank Sta=5262.6,5275.1
XS Rating Curve= 0 ,0
Exp/Cntr=0.3,0.1

Type RM Length L Ch R = 1 ,22294   ,472,472,472
BEGIN DESCRIPTION:
BUCKHORN CREEK 34.0
END DESCRIPTION:
XS GIS Cut Line= 3
      2402574.98     13681674.97        2402025.       13680925.
      2401225.03     13680725.01
#Sta/Elev= 30
  4077.5  307.42  4105.9  306.97  4421.3  301.04    4808  297.95  4843.5  298.32
  4864.3  296.41  4901.2  298.51  4926.2  299.04  4957.9  298.58  4979.3  295.49
  4985.5  292.99    4994  294.24  4998.2  292.93  4998.7  292.43  5010.7  292.93
  5025.6  293.03  5030.7  295.18  5038.4  296.43  5053.7  296.94  5057.1  297.05
  5157.8  298.35  5195.6  298.54  5213.7  296.11    5224  293.17  5231.7  293.28
  5244.6  296.72  5272.9  301.87  5328.7  303.51  5566.7  308.35  5832.1  316.62
#Mann= 10 ,-1 , 0
  4077.5     .05       0  4105.9     .07       0  4901.2     .12       0
  4926.2     .07       0  4998.2     .05       0  5010.7     .07       0
  5053.7     .12       0  5057.1     .07       0  5157.8     .12       0
  5328.7     .07       0
Bank Sta=4998.2,5010.7
XS Rating Curve= 0 ,0
Exp/Cntr=0.3,0.1

Type RM Length L Ch R = 1 ,21822   ,462,462,462
BEGIN DESCRIPTION:
BUCKHORN CREEK 33.0
END DESCRIPTION:
XS GIS Cut Line= 3
      2402775.02     13681275.03        2402425.       13680725.
      2401629.33     13680444.56
#Sta/Elev= 30
  4343.9  305.26  4686.8  298.64  4873.1  292.84  4915.4  295.62  4918.4  290.13
  4918.9  289.63    4931  290.13  4960.3  294.53  5017.1  295.67  5160.8  295.35
  5191.7  292.08  5229.1  295.77  5260.9  296.42  5271.5  296.17  5279.2  292.57
  5284.5  294.57  5292.7   291.7  5335.1  294.53  5356.4  291.37  5388.2  291.69
  5397.7   294.8    5403  292.24  5409.4  295.32    5483  296.83  5521.5  293.44
  5534.9  297.08  5557.8  300.93  5578.1   299.6    5632  301.92  5839.5  304.59
#Mann= 6 ,-1 , 0
  4343.9     .05       0  4686.8     .07       0  4918.4     .05       0
    4931     .07       0    5483     .12       0  5534.9     .07       0
Bank Sta=4918.4,4931
XS Rating Curve= 0 ,0
Exp/Cntr=0.3,0.1

Type RM Length L Ch R = 1 ,21360   ,415,415,415
BEGIN DESCRIPTION:
BUCKHORN CREEK 32.0
END DESCRIPTION:
XS GIS Cut Line= 3
      2402911.74     13681136.51        2402775.       13680575.
      2401968.18     13680406.72
#Sta/Elev= 30
  4422.4  302.53  4620.9  299.35  4625.3   299.3  4632.2  299.26  4727.4   296.8
  4753.3  293.15  4773.9  292.12  4784.2  289.84  4804.8  293.74  4829.5  293.76
  4940.3  293.94  4959.2   291.2    4982   291.4  4991.4  289.03  4991.9  288.53
  5004.1  289.03  5025.3  293.32  5101.3  294.15  5163.8  295.08  5170.3   293.5
  5175.4  294.45  5194.4  290.04  5204.6  293.45  5279.3  294.47  5398.7  295.58
  5429.4  294.67    5460  291.42  5480.4  295.34  5531.5  297.08  5824.5  300.24
#Mann= 10 ,-1 , 0
  4422.4     .05       0  4620.9     .07       0  4625.3     .12       0
  4632.2     .07       0  4727.4     .12       0  4829.5      .1       0
  4991.4     .05       0  5004.1      .1       0  5101.3     .12       0
  5279.3     .07       0
Bank Sta=4991.4,5004.1
XS Rating Curve= 0 ,0
Exp/Cntr=0.3,0.1

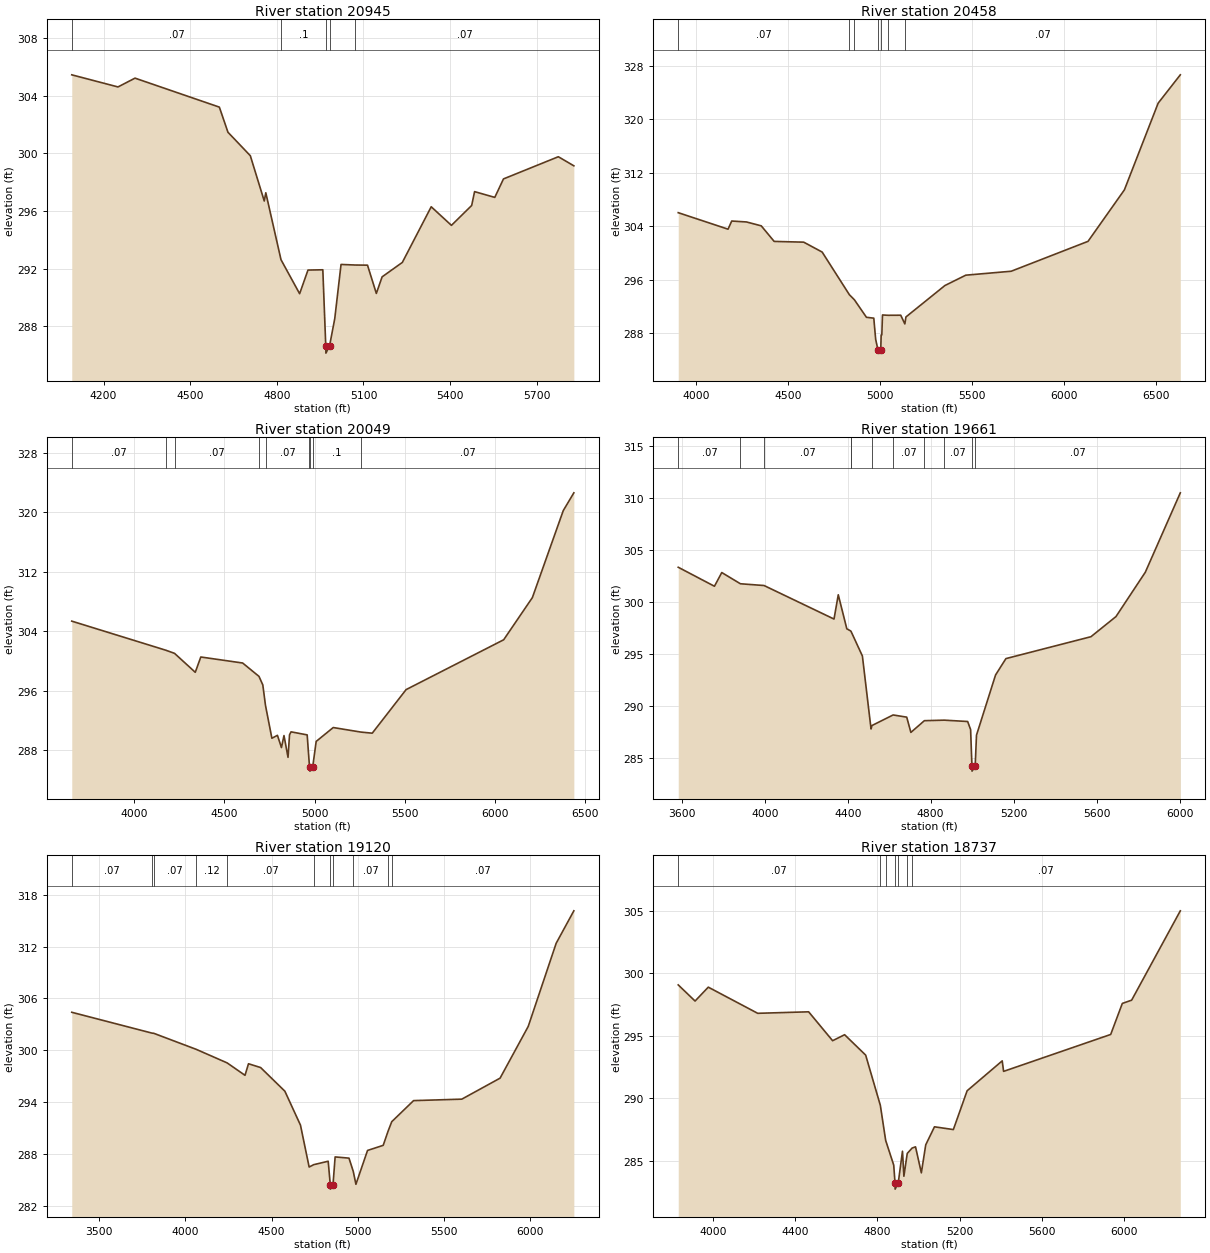
Type RM Length L Ch R = 1 ,20945   ,487,487,487
BEGIN DESCRIPTION:
X18377
END DESCRIPTION:
XS GIS Cut Line= 4
      2403511.06     13681166.05      2403202.96     13680406.33
      2402983.49     13680351.47      2402291.28     13680359.91
#Sta/Elev= 30
  4090.1  305.44  4250.1   304.6  4309.1  305.21  4601.1   303.2  4630.8  301.46
  4708.3  299.83  4756.5  296.69  4761.9  297.26  4814.5  292.62    4879  290.26
  4907.9   291.9  4959.3  291.92  4969.5  286.64    4970  286.14  4982.6  286.64
  5000.6  288.53  5022.4  292.29  5071.3  292.25    5114  292.24  5144.6  290.28
  5164.6  291.43  5234.6  292.43  5334.6  296.29  5404.6     295  5474.7  296.38
  5484.7  297.34  5554.7  296.94  5584.7  298.22  5774.7  299.76  5828.4  299.13
#Mann= 5 ,-1 , 0
  4090.1     .07       0  4814.5      .1       0  4969.5     .05       0
  4982.6      .1       0  5071.3     .07       0
Bank Sta=4969.5,4982.6
XS Rating Curve= 0 ,0
Exp/Cntr=0.3,0.1

Type RM Length L Ch R = 1 ,20458   ,409,409,409
BEGIN DESCRIPTION:
BUCKHORN CREEK 31.0
END DESCRIPTION:
XS GIS Cut Line= 3
        2403575.     13681224.95        2403475.       13680125.
      2402274.98     13679024.98
#Sta/Elev= 30
  3900.7  306.04  4171.8  303.57  4191.8  304.79  4272.2  304.65  4352.5  304.07
  4422.8  301.74  4583.5  301.63  4683.9  300.15  4831.8  293.78  4859.7     293
  4924.9  290.39    4965  290.26  4975.1  287.11  4987.5  285.53    4988  285.03
  5002.8  285.53  5005.2  287.75  5008.6  287.75  5012.3  290.74  5041.2  290.69
  5111.6   290.7    5134   289.4  5139.9  290.44    5352  295.14  5465.5  296.69
  5712.8  297.28  6130.8  301.75  6328.8  309.45  6512.5  322.42  6633.1  326.66
#Mann= 7 ,-1 , 0
  3900.7     .07       0  4831.8      .1       0  4859.7     .07       0
  4987.5     .05       0  5002.8     .07       0  5041.2      .1       0
    5134     .07       0
Bank Sta=4987.5,5002.8
XS Rating Curve= 0 ,0
Exp/Cntr=0.3,0.1

Type RM Length L Ch R = 1 ,20049   ,388,388,388
BEGIN DESCRIPTION:
BUCKHORN CREEK 30.0
END DESCRIPTION:
XS GIS Cut Line= 3
        2404225.     13681024.99        2403625.       13679825.
      2402424.96     13679024.97
#Sta/Elev= 30
  3653.9  305.35  4175.8  301.43  4223.8  301.01  4338.7  298.46  4369.4  300.52
  4601.4  299.71    4692  297.91  4713.2  296.76  4728.1  293.99  4763.5  289.58
  4794.3  289.97  4816.6  288.32  4830.6  289.94    4853  287.01  4861.4  290.05
  4869.8  290.44  4959.2  290.03  4970.3  286.32  4973.8  285.65  4974.3  285.15
  4989.4  285.65  5009.1  289.15  5103.7  291.02  5256.9  290.41    5320  290.26
  5507.8  296.13  6048.7  302.84  6207.9  308.52  6379.2  320.24  6437.8  322.63
#Mann= 9 ,-1 , 0
  3653.9     .07       0  4175.8     .12       0  4223.8     .07       0
    4692      .1       0  4728.1     .07       0  4970.3      .1       0
  4973.8     .05       0  4989.4      .1       0  5256.9     .07       0
Bank Sta=4973.8,4989.4
XS Rating Curve= 0 ,0
Exp/Cntr=0.3,0.1

Type RM Length L Ch R = 1 ,19661   ,541,541,541
BEGIN DESCRIPTION:
X18378
END DESCRIPTION:
XS GIS Cut Line= 3
      2404169.49     13680794.64      2403895.14     13679667.72
      2402966.61     13678815.16
#Sta/Elev= 30
    3583  303.33  3757.6   301.5  3792.9  302.82  3882.7  301.74  3996.7  301.57
    4334  298.34  4354.5  300.68  4395.7   297.4  4414.7  297.19  4417.3   297.1
  4470.8  294.78  4512.5  287.75  4516.8  288.08  4618.9   289.1  4684.5  288.89
  4704.5  287.42  4769.7  288.55  4865.6   288.6  4978.3  288.47  4992.5  287.69
  4998.9  284.19  4999.4  283.69  5014.5  284.19  5020.9  287.16  5112.7  292.95
  5162.7  294.53  5572.7  296.64  5693.3  298.58  5834.7  302.85  6003.4   310.5
#Mann= 11 ,-1 , 0
    3583     .07       0  3882.7     .12       0  3996.7     .07       0
  4414.7     .12       0  4417.3     .07       0  4516.8      .1       0
  4618.9     .07       0  4769.7      .1       0  4865.6     .07       0
  4998.9     .05       0  5014.5     .07       0
Bank Sta=4998.9,5014.5
XS Rating Curve= 0 ,0
Exp/Cntr=0.3,0.1

Type RM Length L Ch R = 1 ,19120   ,383,383,383
BEGIN DESCRIPTION:
BUCKHORN CREEK 29.0
END DESCRIPTION:
XS GIS Cut Line= 3
        2404225.     13680925.01        2404075.       13679275.
      2402975.01       13678675.
#Sta/Elev= 30
  3342.4  304.39  3808.9  301.97  3817.1  301.96  4063.5   300.1  4242.7  298.53
  4346.5  297.09  4366.6  298.43  4436.9  297.99  4577.5  295.25  4667.9  291.32
  4718.1  286.47  4744.3  286.74  4828.5  287.14  4840.7  284.41  4841.2  283.91
  4856.4  284.41  4868.7  287.64    4949   287.5  4973.9  285.96  4989.2  284.47
  5056.6  288.39  5147.3  288.98  5175.6  290.62  5196.9  291.72  5323.4  294.16
  5602.9  294.33  5824.6  296.76  5987.8  302.75  6149.7  312.38  6252.2  316.14
#Mann= 11 ,-1 , 0
  3342.4     .07       0  3808.9     .12       0  3817.1     .07       0
  4063.5     .12       0  4242.7     .07       0  4744.3      .1       0
  4840.7     .05       0  4856.4      .1       0  4973.9     .07       0
  5175.6      .1       0  5196.9     .07       0
Bank Sta=4840.7,4856.4
XS Rating Curve= 0 ,0
Exp/Cntr=0.3,0.1

Type RM Length L Ch R = 1 ,18737   ,527,527,527
BEGIN DESCRIPTION:
X18379
END DESCRIPTION:
XS GIS Cut Line= 4
      2405014.53     13680046.27      2404519.76     13679221.64
       2404233.3      13678926.5      2403269.86     13678466.48
#Sta/Elev= 30
  3832.2  299.06  3914.1  297.77  3978.3  298.88  4218.5  296.79  4466.1  296.91
  4582.7   294.6    4641  295.08  4743.3  293.45  4814.6  289.44  4840.6  286.63
  4879.7  284.66    4886  283.24  4886.5  282.74  4901.7  283.24  4922.2  285.77
  4929.1  283.77  4945.4  285.59  4968.9  286.02  4985.7  286.12    5014  284.04
  5035.3  286.28  5077.8  287.72  5169.6   287.5  5236.5   290.6  5407.1  292.99
  5413.8  292.15  5934.4   295.1  5990.9  297.58  6036.2  297.84  6272.8  304.98
#Mann= 7 ,-1 , 0
  3832.2     .07       0  4814.6      .1       0  4840.6     .07       0
    4886     .05       0  4901.7     .07       0  4945.4      .1       0
  4968.9     .07       0
Bank Sta=4886,4901.7
XS Rating Curve= 0 ,0
Exp/Cntr=0.3,0.1

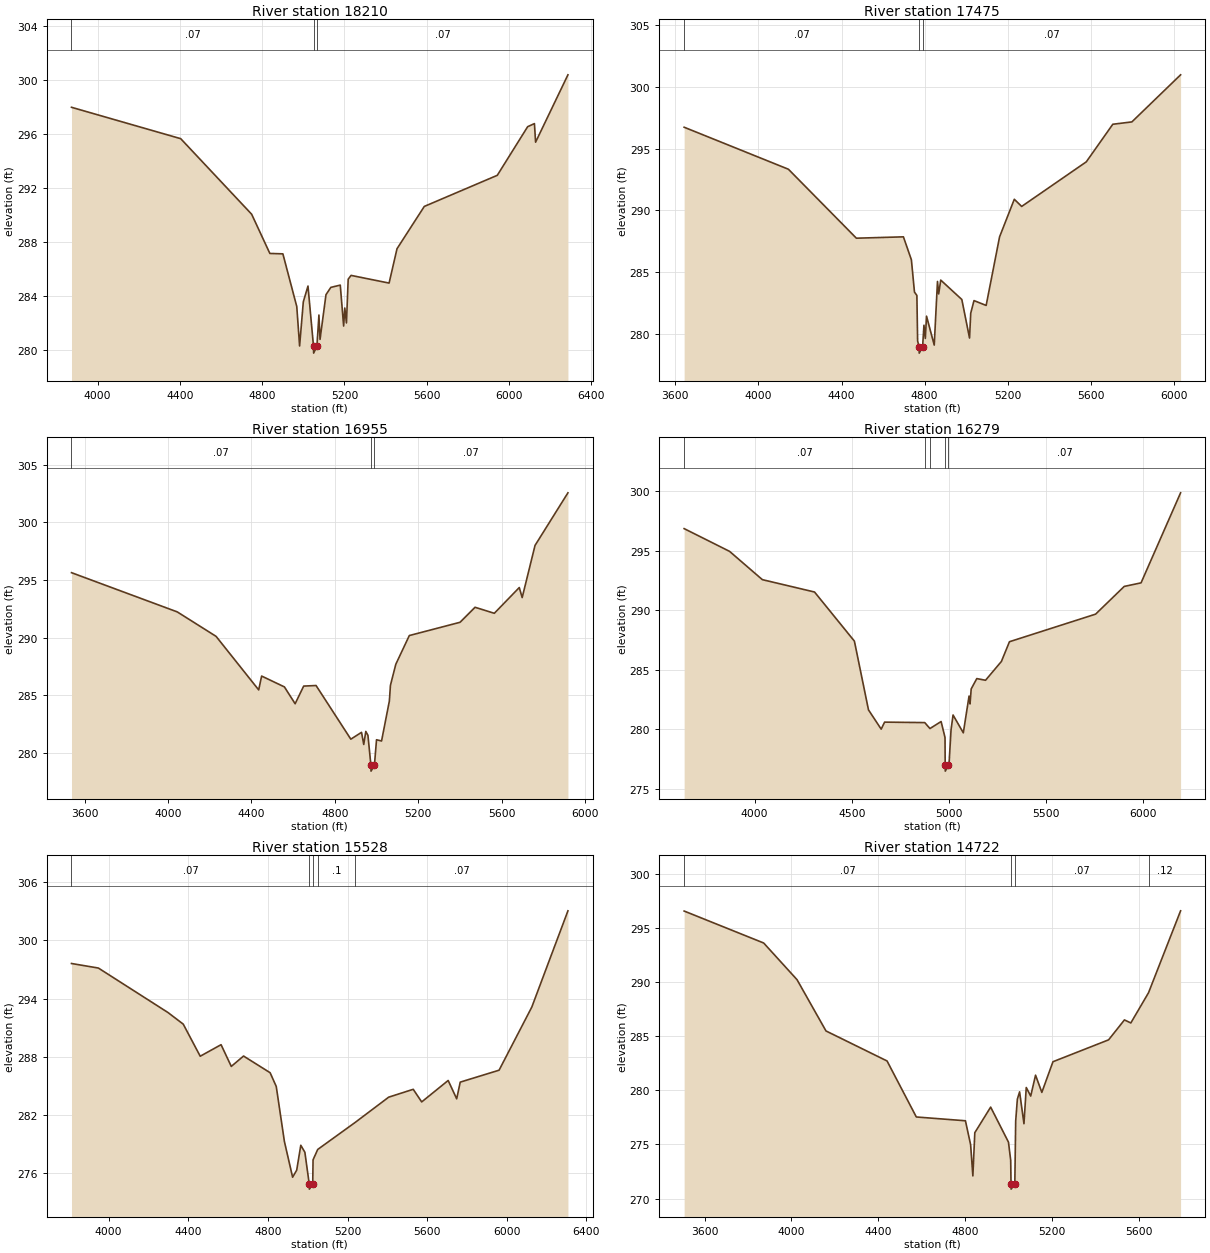
Type RM Length L Ch R = 1 ,18210   ,735,735,735
BEGIN DESCRIPTION:
X18380
END DESCRIPTION:
XS GIS Cut Line= 3
      2405240.23     13679959.46      2404728.09     13678778.93
      2404207.25     13677780.67
#Sta/Elev= 30
  3873.2     298  4404.1  295.67  4748.9  290.06  4837.3  287.15  4900.6  287.12
  4968.1  283.21  4981.9  280.28  4999.9  283.56  5022.6  284.73  5049.5  280.25
    5050  279.75    5066  280.25  5075.8  282.58  5081.2  280.77  5110.1  284.09
  5133.6  284.63  5179.5   284.8  5195.9  281.76  5201.5   283.1  5209.6  281.99
    5218  285.24  5232.1  285.52  5416.8  284.95  5455.3   287.5  5587.9  290.64
  5942.7  292.95  6090.3  296.56  6123.2  296.79  6128.8  295.41    6286  300.41
#Mann= 3 ,-1 , 0
  3873.2     .07       0  5049.5     .05       0    5066     .07       0
Bank Sta=5049.5,5066
XS Rating Curve= 0 ,0
Exp/Cntr=0.3,0.1

Type RM Length L Ch R = 1 ,17475   ,520,520,520
BEGIN DESCRIPTION:
X18381
END DESCRIPTION:
XS GIS Cut Line= 4
      2405544.07     13679716.47      2405162.12     13678666.09
      2404962.46     13678327.54      2404354.85     13677693.89
#Sta/Elev= 30
  3642.9  296.73  4144.6  293.33  4471.6  287.75  4697.9  287.86  4736.3     286
  4751.1  283.39  4762.7  283.12  4766.2  279.44  4773.5  278.95    4774  278.45
  4790.2  278.95  4796.7  280.71  4803.3  279.64  4809.1  281.44  4846.2   279.1
  4861.8  284.25  4867.6  283.24  4877.5  284.36  4978.9  282.79    5016  279.67
  5021.8  281.68  5037.5   282.7    5096  282.31  5160.6  287.86  5231.4   290.9
  5266.9  290.32  5577.9  293.93  5705.3  296.97  5797.1  297.16  6031.5  300.97
#Mann= 3 ,-1 , 0
  3642.9     .07       0  4773.5     .05       0  4790.2     .07       0
Bank Sta=4773.5,4790.2
XS Rating Curve= 0 ,0
Exp/Cntr=0.3,0.1

Type RM Length L Ch R = 1 ,16955   ,676,676,676
BEGIN DESCRIPTION:
X18382
END DESCRIPTION:
XS GIS Cut Line= 2
       2405795.8     13679699.08       2405257.6     13677381.35
#Sta/Elev= 30
  3537.6  295.64  4044.6  292.24  4230.6  290.12  4434.9  285.48  4448.9  286.68
  4558.1  285.74  4609.5  284.28  4650.5  285.81  4709.8  285.86  4876.4  281.21
  4927.7   281.8  4938.4  280.75  4948.2  281.88  4958.5  281.54  4972.7  278.94
  4973.2  278.44  4989.5  278.94  4999.6  281.16  5023.7  281.05  5061.2  284.52
  5066.3  285.88    5092   287.7  5156.8  290.19  5399.9  291.34  5471.8  292.64
  5564.2  292.12  5683.8  294.35  5697.7  293.48  5759.3     298    5917  302.56
#Mann= 3 ,-1 , 0
  3537.6     .07       0  4972.7     .05       0  4989.5     .07       0
Bank Sta=4972.7,4989.5
XS Rating Curve= 0 ,0
Exp/Cntr=0.3,0.1

Type RM Length L Ch R = 1 ,16279   ,751,751,751
BEGIN DESCRIPTION:
X18383
END DESCRIPTION:
XS GIS Cut Line= 2
      2406394.77     13679690.43      2405726.36     13677225.14
#Sta/Elev= 30
  3637.8  296.86  3871.4  294.95  4040.2  292.57  4308.7  291.53  4513.8   287.4
  4586.3  281.62  4651.6     280  4669.2  280.59  4875.8  280.55  4902.5  280.05
  4959.9  280.64    4980   279.3  4980.9  276.97  4981.4  276.47  4997.8  276.97
  5000.7  277.06  5011.1  279.95  5021.4  281.19  5074.2  279.69  5103.7  282.78
  5108.8  282.12  5114.7  283.38  5143.5  284.25  5188.5  284.11  5270.1  285.69
  5311.6  287.35  5754.9  289.67  5902.1     292  5988.7   292.3  6192.1  299.87
#Mann= 5 ,-1 , 0
  3637.8     .07       0  4875.8      .1       0  4902.5     .07       0
  4980.9     .05       0  4997.8     .07       0
Bank Sta=4980.9,4997.8
XS Rating Curve= 0 ,0
Exp/Cntr=0.3,0.1

Type RM Length L Ch R = 1 ,15528   ,806,806,806
BEGIN DESCRIPTION:
X18384
END DESCRIPTION:
XS GIS Cut Line= 2
       2406906.9     13679516.74      2406343.11     13677088.12
#Sta/Elev= 30
  3813.8  297.62    3949  297.15  4298.1  292.57    4375  291.37  4460.3  288.06
    4565  289.25  4616.3  287.01  4677.9  288.08  4811.4  286.36  4842.2  284.94
  4883.2  279.26  4924.3  275.59  4944.8  276.31  4965.4  278.88  4985.9  278.16
    5008  274.86  5008.5  274.36  5025.3  274.86    5027  277.38  5050.4  278.45
  5238.1  281.23  5406.8  283.84    5530  284.65  5572.6  283.35  5705.6  285.56
  5748.3  283.67  5766.1  285.39  5961.2  286.62  6125.4  293.12    6307  303.05
#Mann= 5 ,-1 , 0
  3813.8     .07       0    5008     .05       0  5025.3     .07       0
  5050.4      .1       0  5238.1     .07       0
Bank Sta=5008,5025.3
XS Rating Curve= 0 ,0
Exp/Cntr=0.3,0.1

Type RM Length L Ch R = 1 ,14722   ,1335,1335,1335
BEGIN DESCRIPTION:
X18385
END DESCRIPTION:
XS GIS Cut Line= 2
      2407375.67     13679282.45      2406872.18     13677051.46
#Sta/Elev= 30
  3505.5  296.55  3871.9   293.6  4025.7  290.21    4159  285.48  4440.3  282.71
  4575.1  277.54  4801.4  277.19  4825.3  274.98  4835.6   272.1  4844.6  276.09
  4917.6  278.45  4999.6  275.22  5009.9  273.54  5011.4  271.38  5011.9  270.88
  5028.9  271.38  5032.9  277.17  5040.6  279.18  5050.9  279.86    5071  276.92
  5081.6  280.26  5102.1  279.47  5124.4   281.4  5153.4  279.81  5204.6  282.64
  5460.9  284.66  5533.9   286.5  5563.4  286.22  5644.9  289.01  5792.6  296.57
#Mann= 4 ,-1 , 0
  3505.5     .07       0  5011.4     .05       0  5028.9     .07       0
  5644.9     .12       0
Bank Sta=5011.4,5028.9
XS Rating Curve= 0 ,0
Exp/Cntr=0.3,0.1