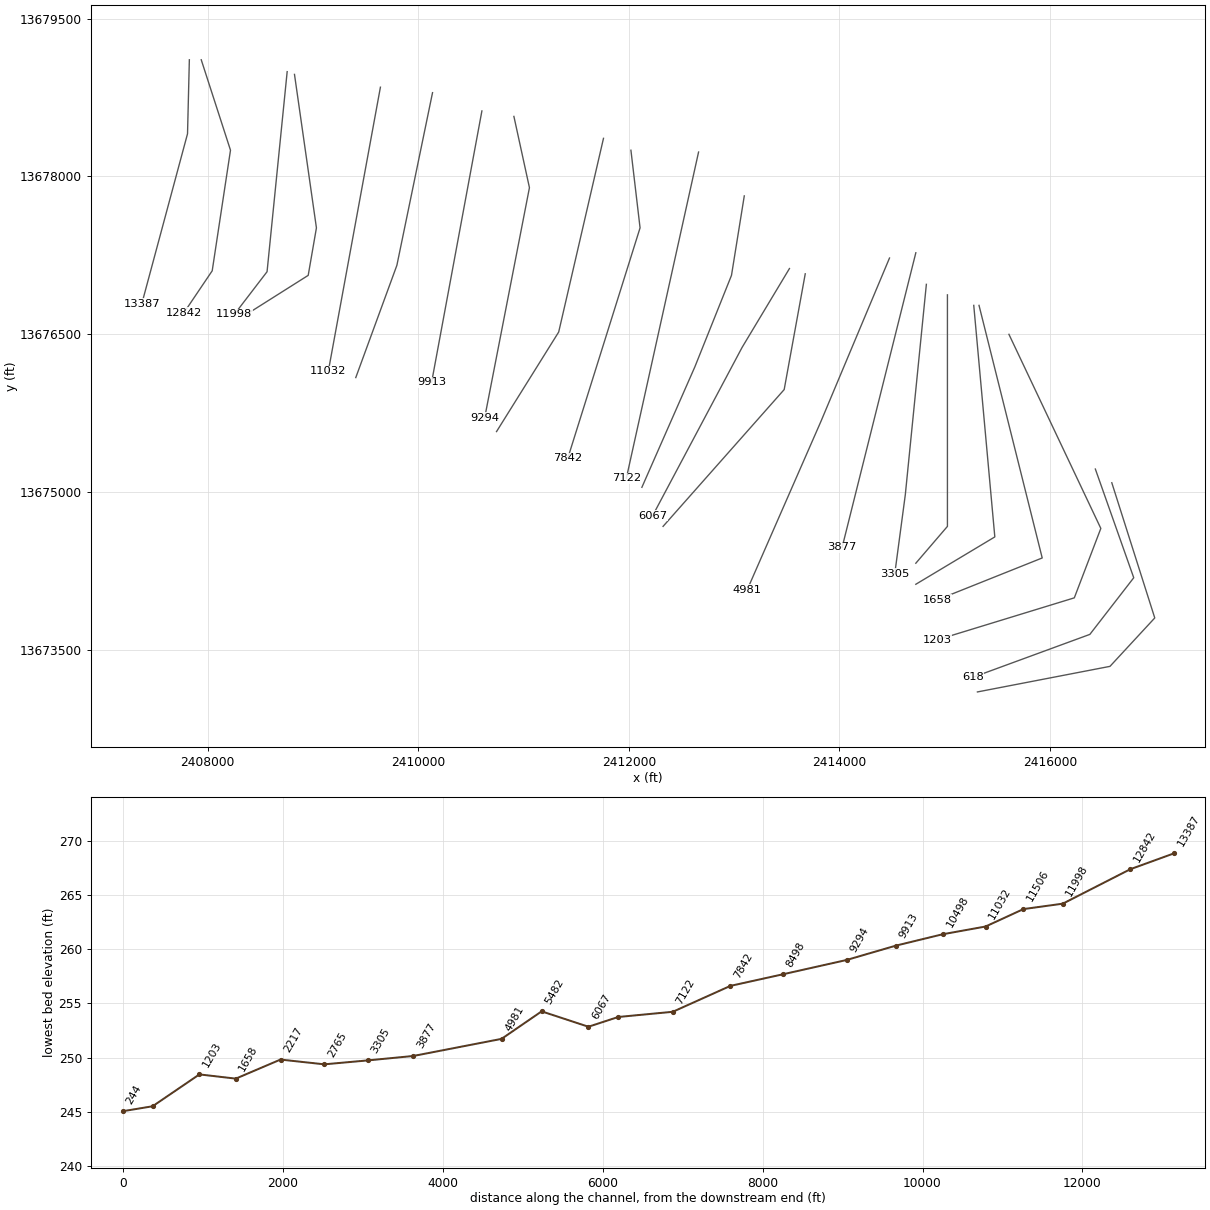
HEC-RAS study BUCKHORN CREEK.prj: BUCKHORN CREEK Base Level Engineering

--- BUCKHORN CREEK.g01 (geometry) --- (continued)

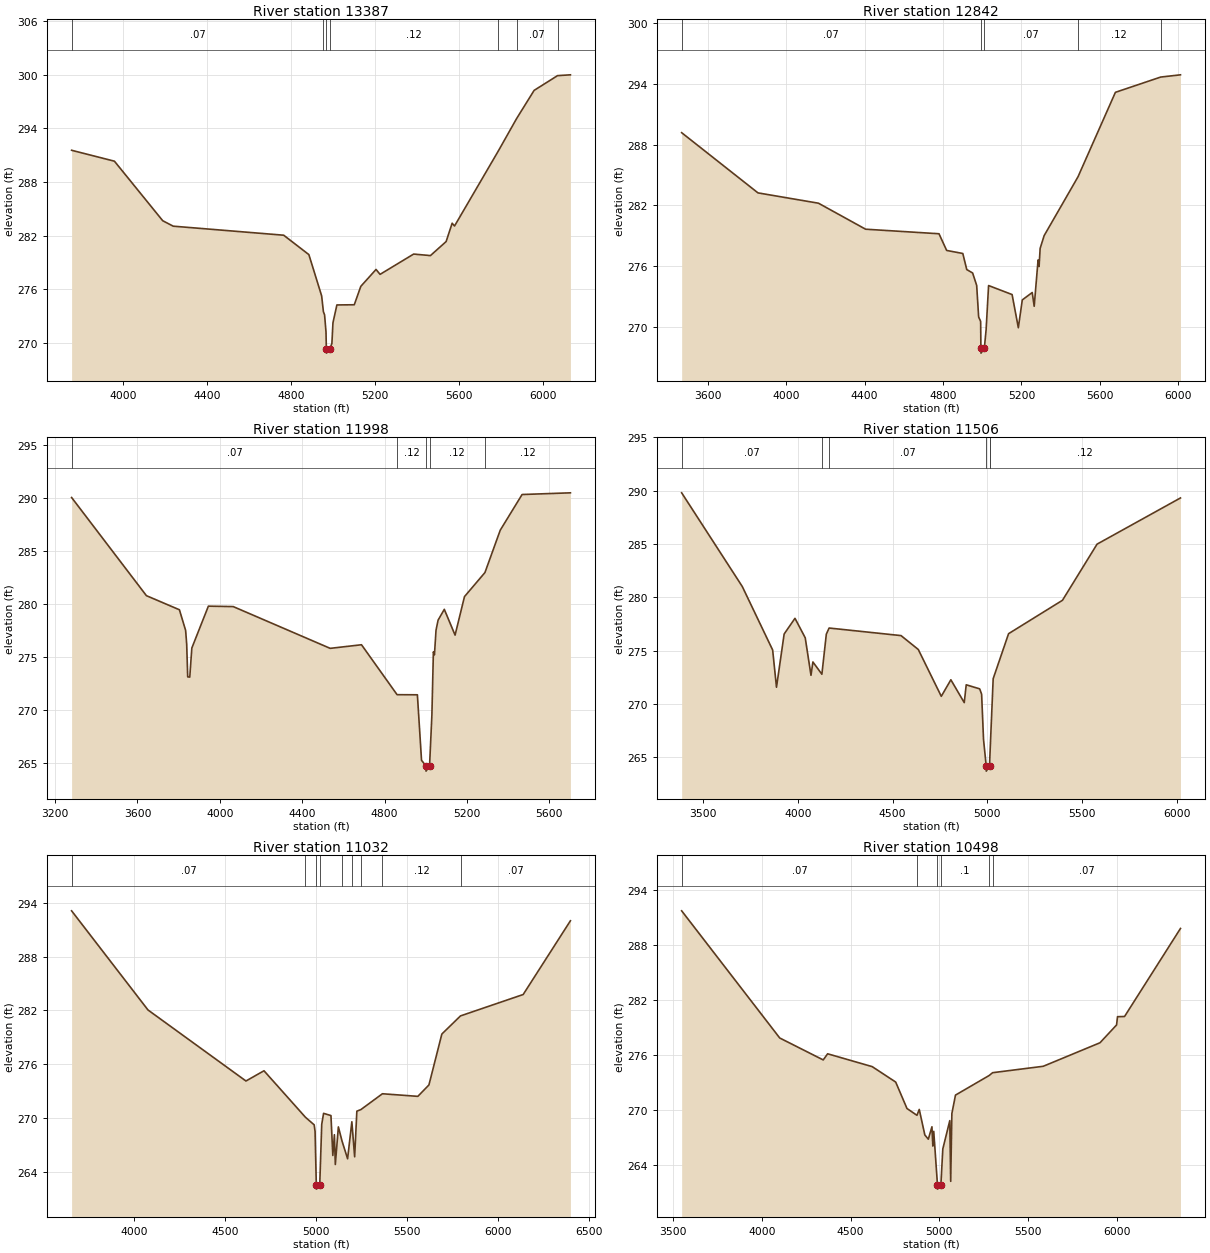
Type RM Length L Ch R = 1 ,13387   ,545,545,545
BEGIN DESCRIPTION:
X18386
END DESCRIPTION:
XS GIS Cut Line= 3
      2407827.05     13679108.79      2407809.69     13678405.67
      2407375.67     13676791.12
#Sta/Elev= 30
  3753.6  291.54  3957.5  290.32  4187.5  283.66  4237.5  283.05  4763.5  282.04
  4883.4  279.87  4944.3  275.25  4952.6  273.48  4958.2  273.13    4965  271.21
  4966.6  269.35  4967.1  268.85  4984.1  269.35    4993  269.93  4998.1  272.25
  5016.8  274.24  5099.6  274.26  5130.7  276.32  5203.2  278.21  5222.4  277.66
  5382.3  279.93  5462.3  279.76    5537  281.33  5565.6  283.38    5577  283.07
    5785  291.44  5872.9   295.1    5956  298.24  6067.6  299.89  6128.8  299.98
#Mann= 7 ,-1 , 0
  3753.6     .07       0  4952.6     .12       0  4966.6     .05       0
  4984.1     .12       0    5785     .12       0  5872.9     .07       0
  6067.6     .12       0
Bank Sta=4966.6,4984.1
XS Rating Curve= 0 ,0
Exp/Cntr=0.3,0.1

Type RM Length L Ch R = 1 ,12842   ,844,844,844
BEGIN DESCRIPTION:
X18387
END DESCRIPTION:
XS GIS Cut Line= 4
      2407939.88     13679108.83      2408217.67     13678249.42
      2408044.06     13677103.59      2407774.97     13676704.29
#Sta/Elev= 30
  3467.6  289.18  3856.7  283.23  4165.2  282.21  4405.6  279.64  4779.8  279.19
  4818.9  277.54  4901.2  277.24  4921.4  275.65  4951.4  275.31    4972  274.08
  4982.1  270.96  4992.2  270.53  4993.5  267.89    4994  267.39  5011.1  267.89
  5020.1   269.7  5032.7  274.07  5152.6  273.18  5184.4   269.9  5204.6  272.65
  5255.2  273.38  5265.3  272.02  5285.1   276.6  5290.2  275.95  5295.6  277.74
  5315.9     279  5488.7  284.82  5679.4  293.17  5910.5  294.68  6011.2   294.9
#Mann= 5 ,-1 , 0
  3467.6     .07       0  4993.5     .05       0  5011.1     .07       0
  5488.7     .12       0  5910.5     .07       0
Bank Sta=4993.5,5011.1
XS Rating Curve= 0 ,0
Exp/Cntr=0.3,0.1

Type RM Length L Ch R = 1 ,11998   ,492,492,492
BEGIN DESCRIPTION:
X18388
END DESCRIPTION:
XS GIS Cut Line= 3
      2408755.87     13678995.99      2408564.89     13677094.91
      2408253.59     13676688.48
#Sta/Elev= 30
  3280.3  290.02  3643.6  280.76  3803.9  279.43  3834.1  277.48  3839.2  276.21
  3844.2   273.1  3854.2  273.08  3864.2  275.82  3944.6  279.77  4065.2  279.73
  4536.1  275.79  4688.3  276.13  4861.1  271.42  4959.7  271.41  4979.8  265.23
  5001.2  264.71  5001.7  264.21  5018.8  264.71  5030.1  269.49  5037.4  275.46
  5042.5  275.18  5050.2   277.5  5060.2  278.45  5090.4  279.47  5142.7  277.04
  5188.4  280.67  5287.8  282.94  5362.2  286.94  5468.2   290.3  5702.9  290.46
#Mann= 5 ,-1 , 0
  3280.3     .07       0  4861.1     .12       0  5001.2     .05       0
  5018.8     .12       0  5287.8     .12       0
Bank Sta=5001.2,5018.8
XS Rating Curve= 0 ,0
Exp/Cntr=0.3,0.1

Type RM Length L Ch R = 1 ,11506   ,474,474,474
BEGIN DESCRIPTION:
X18389
END DESCRIPTION:
XS GIS Cut Line= 4
      2408825.31      13678969.9      2409033.64     13677511.57
      2408955.52     13677060.18      2408365.27     13676686.94
#Sta/Elev= 30
  3388.1  289.79  3707.7  281.01  3867.8  275.06    3888  271.57  3928.4  276.56
  3985.5  278.03  4039.6   276.2  4069.9  272.69    4080  273.94  4127.3  272.79
  4150.7  276.54  4165.4  277.12  4544.6  276.41  4635.5  275.11  4756.8  270.72
  4807.3  272.27  4877.8  270.13  4888.2   271.8  4959.2  271.42  4969.4  270.92
  4979.5  266.67  4993.5  264.21    4994  263.71  5011.2  264.21  5012.7  264.98
  5030.3  272.37  5111.5  276.59  5395.7  279.72    5578  284.98  6017.7  289.31
#Mann= 6 ,-1 , 0
  3388.1     .07       0  4127.3      .1       0  4165.4     .07       0
  4993.5     .05       0  5011.2     .07       0  5012.7     .12       0
Bank Sta=4993.5,5011.2
XS Rating Curve= 0 ,0
Exp/Cntr=0.3,0.1

Type RM Length L Ch R = 1 ,11032   ,534,534,534
BEGIN DESCRIPTION:
X18390
END DESCRIPTION:
XS GIS Cut Line= 2
      2409641.28     13678848.35      2409146.62     13676149.41
#Sta/Elev= 30
  3655.1  293.09  4075.3  282.05  4614.2  274.14  4713.4  275.28  4941.6   270.1
  4989.4  269.26  4994.4  268.52  5001.2   262.6  5001.7   262.1  5020.1   262.6
    5031  269.31  5041.2  270.54  5081.8  270.29    5092  265.85  5100.7  268.16
  5105.8  264.84  5122.5  269.03  5142.9  267.44  5173.3  265.48  5196.7   269.6
  5212.1   265.7  5224.2  270.78  5246.6  270.96  5364.9  272.72  5559.7  272.43
  5620.7   273.7  5691.8  279.37  5794.4  281.39  6139.1  283.77    6399  291.98
#Mann= 9 ,-1 , 0
  3655.1     .07       0  4941.6     .12       0  5001.2     .05       0
  5020.1     .12       0  5142.9      .1       0  5196.7     .12       0
  5246.6      .1       0  5364.9     .12       0  5794.4     .07       0
Bank Sta=5001.2,5020.1
XS Rating Curve= 0 ,0
Exp/Cntr=0.3,0.1

Type RM Length L Ch R = 1 ,10498   ,585,585,585
BEGIN DESCRIPTION:
X18391
END DESCRIPTION:
XS GIS Cut Line= 3
      2410136.08      13678796.3      2409797.53     13677155.67
      2409407.29     13676089.01
#Sta/Elev= 30
    3548   291.7  4100.7  277.85  4345.8  275.46  4370.5  276.13  4621.9  274.73
  4754.2  273.05  4817.8  270.17    4874  269.43  4886.9  270.07  4918.4  267.29
    4938  266.83  4958.4  268.18  4963.5  266.08  4968.6  267.68  4989.5  261.89
    4990  261.39  5008.9  261.89  5019.7  265.77    5059  268.85  5064.1  262.24
  5070.7  269.62  5091.1  271.63  5281.3  273.77  5300.2  274.07  5585.9  274.77
  5905.4  277.33  5998.9  279.27  6004.2  280.17  6043.8  280.19    6359  289.78
#Mann= 6 ,-1 , 0
    3548     .07       0    4874      .1       0  4989.5     .05       0
  5008.9      .1       0  5281.3     .12       0  5300.2     .07       0
Bank Sta=4989.5,5008.9
XS Rating Curve= 0 ,0
Exp/Cntr=0.3,0.1

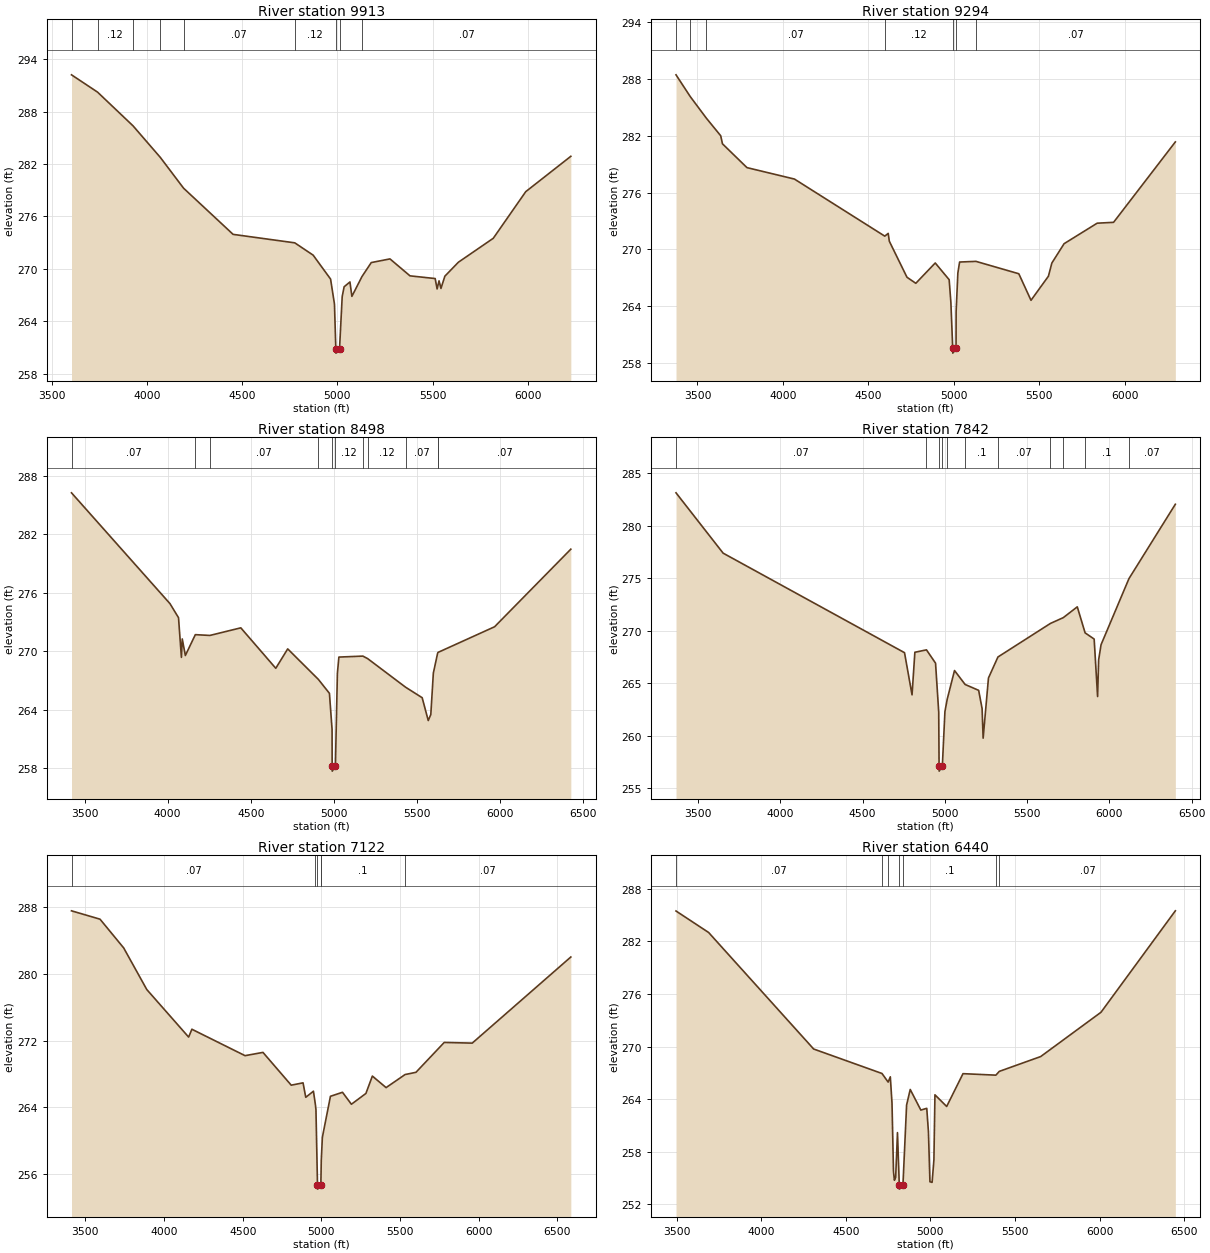
Type RM Length L Ch R = 1 ,9913    ,619,619,619
BEGIN DESCRIPTION:
X18392
END DESCRIPTION:
XS GIS Cut Line= 2
      2410604.82     13678622.68      2410127.39     13676044.51
#Sta/Elev= 30
  3603.6  292.21  3740.3  290.23  3926.6  286.37  4070.1  282.75    4192  279.23
  4452.1  273.94    4776  272.97  4872.5  271.56    4964  268.82  4984.4  265.96
  4991.6  260.84  4992.1  260.34    5011  260.84    5025  266.81  5035.2  267.94
  5065.7  268.49  5075.9  266.84  5128.9  269.11  5177.6  270.71  5275.9  271.13
    5381  269.19  5513.2  268.88  5523.4  267.69  5533.5  268.62  5543.7  267.75
  5564.1  269.15  5635.2  270.75  5818.3  273.49  5988.8  278.83  6225.6  282.88
#Mann= 9 ,-1 , 0
  3603.6     .07       0  3740.3     .12       0  3926.6     .07       0
  4070.1     .12       0    4192     .07       0    4776     .12       0
  4991.6     .05       0    5011     .12       0  5128.9     .07       0
Bank Sta=4991.6,5011
XS Rating Curve= 0 ,0
Exp/Cntr=0.3,0.1

Type RM Length L Ch R = 1 ,9294    ,796,796,796
BEGIN DESCRIPTION:
X18393
END DESCRIPTION:
XS GIS Cut Line= 3
      2410908.65     13678570.56      2411056.21     13677893.52
      2410630.87     13675706.02
#Sta/Elev= 30
  3374.5  288.46  3458.1  286.15  3552.6  283.86  3636.1  282.01  3646.3  281.16
  3789.6  278.64  4067.4  277.43  4595.9  271.39    4616  271.68  4622.5  270.85
  4725.8  267.04  4777.5   266.4  4891.1  268.55  4972.6  266.78  4982.8  264.34
  4993.4  259.51  4993.9  259.01  5012.9  259.51  5013.3  263.38  5023.5  267.49
  5033.7  268.65  5129.4  268.72  5380.1  267.41  5451.4   264.6  5553.3  267.15
  5573.6  268.55    5645  270.59  5838.5  272.76  5934.5  272.85  6295.9  281.36
#Mann= 7 ,-1 , 0
  3374.5     .07       0  3458.1     .12       0  3552.6     .07       0
  4595.9     .12       0  4993.4     .05       0  5012.9     .12       0
  5129.4     .07       0
Bank Sta=4993.4,5012.9
XS Rating Curve= 0 ,0
Exp/Cntr=0.3,0.1

Type RM Length L Ch R = 1 ,8498    ,656,656,656
BEGIN DESCRIPTION:
X18394
END DESCRIPTION:
XS GIS Cut Line= 3
      2411759.35     13678362.31      2411333.99     13676521.99
      2410743.74     13675575.84
#Sta/Elev= 30
  3421.7  286.24  4014.2  274.87  4065.5  273.43  4082.9  269.36    4088  271.25
  4106.6  269.55  4166.6  271.69  4254.3  271.61  4440.2  272.39  4650.6  268.24
  4722.4  270.23  4906.9   267.1  4973.4  265.67  4989.3  261.96  4989.8  258.19
  4990.3  257.69  5009.3  258.19  5021.3  267.72  5030.3  269.39  5174.6  269.49
  5203.5  269.23  5431.5   266.3  5531.4  265.22  5567.9  262.88  5583.3   263.5
  5598.6  267.75  5624.2  269.78  5626.8  269.87    5967   272.5  6425.7  280.46
#Mann= 11 ,-1 , 0
  3421.7     .07       0  4166.6     .12       0  4254.3     .07       0
  4906.9     .12       0  4989.8     .05       0  5009.3     .12       0
  5174.6     .07       0  5203.5     .12       0  5431.5     .07       0
  5624.2     .12       0  5626.8     .07       0
Bank Sta=4989.8,5009.3
XS Rating Curve= 0 ,0
Exp/Cntr=0.3,0.1

Type RM Length L Ch R = 1 ,7842    ,720,720,720
BEGIN DESCRIPTION:
X18395
END DESCRIPTION:
XS GIS Cut Line= 3
      2412019.76      13678249.4      2412106.56     13677511.57
      2411420.79     13675324.06
#Sta/Elev= 30
  3365.6  283.15    3652   277.4  4754.7  267.91  4800.4  263.89  4817.6  267.95
  4888.2  268.18  4943.3  266.91  4962.6  262.25  4964.8  257.12  4965.3  256.62
  4984.7  257.12  5000.3  262.29  5014.2  263.47  5058.6  266.21  5123.1  264.88
  5205.4  264.32  5226.3  262.58  5232.6  259.76    5265   265.5  5322.6   267.5
  5641.7   270.7  5719.7  271.25  5804.9  272.28  5852.5   269.8  5907.5  269.21
  5928.4  263.73  5934.7  267.22  5949.4  268.67    6119  274.97    6401  282.06
#Mann= 11 ,-1 , 0
  3365.6     .07       0  4888.2      .1       0  4964.8     .05       0
  4984.7      .1       0  5014.2     .12       0  5123.1      .1       0
  5322.6     .07       0  5641.7     .12       0  5719.7     .07       0
  5852.5      .1       0    6119     .07       0
Bank Sta=4964.8,4984.7
XS Rating Curve= 0 ,0
Exp/Cntr=0.3,0.1

Type RM Length L Ch R = 1 ,7122    ,682,682,682
BEGIN DESCRIPTION:
X18396
END DESCRIPTION:
XS GIS Cut Line= 2
      2412662.12     13678232.06      2411976.36     13675133.13
#Sta/Elev= 30
  3411.7  287.51    3593  286.51  3743.5  283.07  3890.1   278.1  4156.3  272.41
  4176.8  273.35  4514.8  270.19  4628.7  270.58  4808.3  266.66  4883.5  266.94
  4900.7  265.21  4949.5  265.94  4962.3  264.29  4965.5  263.72  4975.3  254.73
  4975.8  254.23  4996.6  254.73  4999.3  257.68  5006.4  260.44  5057.6  265.33
  5134.2  265.81  5190.8  264.38    5283  265.67  5324.1  267.75  5411.3  266.37
  5531.9  267.93  5601.2   268.2  5780.8  271.77  5958.9  271.69  6585.6  281.99
#Mann= 6 ,-1 , 0
  3411.7     .07       0  4962.3     .12       0  4975.3     .05       0
  4996.6     .12       0  4999.3      .1       0  5531.9     .07       0
Bank Sta=4975.3,4996.6
XS Rating Curve= 0 ,0
Exp/Cntr=0.3,0.1

Type RM Length L Ch R = 1 ,6440    ,373,373,373
BEGIN DESCRIPTION:
X18397
END DESCRIPTION:
XS GIS Cut Line= 4
      2413096.14      13677815.4      2412974.62     13677060.18
      2412627.39     13676192.13      2412123.93     13675046.31
#Sta/Elev= 30
  3496.8  285.45  3689.6     283  4310.4  269.72  4714.3  266.93  4750.7  265.95
  4763.5  266.55  4773.5  263.54  4782.3  255.73  4787.7  254.76  4795.1   255.1
  4805.8  260.19  4816.5  254.25    4817  253.75  4838.2  254.25  4859.7  263.33
  4881.2  265.11  4943.9  262.76  4978.9  262.96  4988.9  260.26  4997.7  254.59
  5010.5  254.52  5021.2   257.1  5027.3   264.5  5096.6  263.17  5193.1  266.91
  5387.4  266.74  5407.6  267.17  5652.3  268.86  6008.9  273.91  6448.2  285.47
#Mann= 7 ,-1 , 0
  3496.8     .07       0  4714.3     .12       0  4750.7      .1       0
  4816.5     .05       0  4838.2      .1       0  5387.4     .12       0
  5407.6     .07       0
Bank Sta=4816.5,4838.2
XS Rating Curve= 0 ,0
Exp/Cntr=0.3,0.1

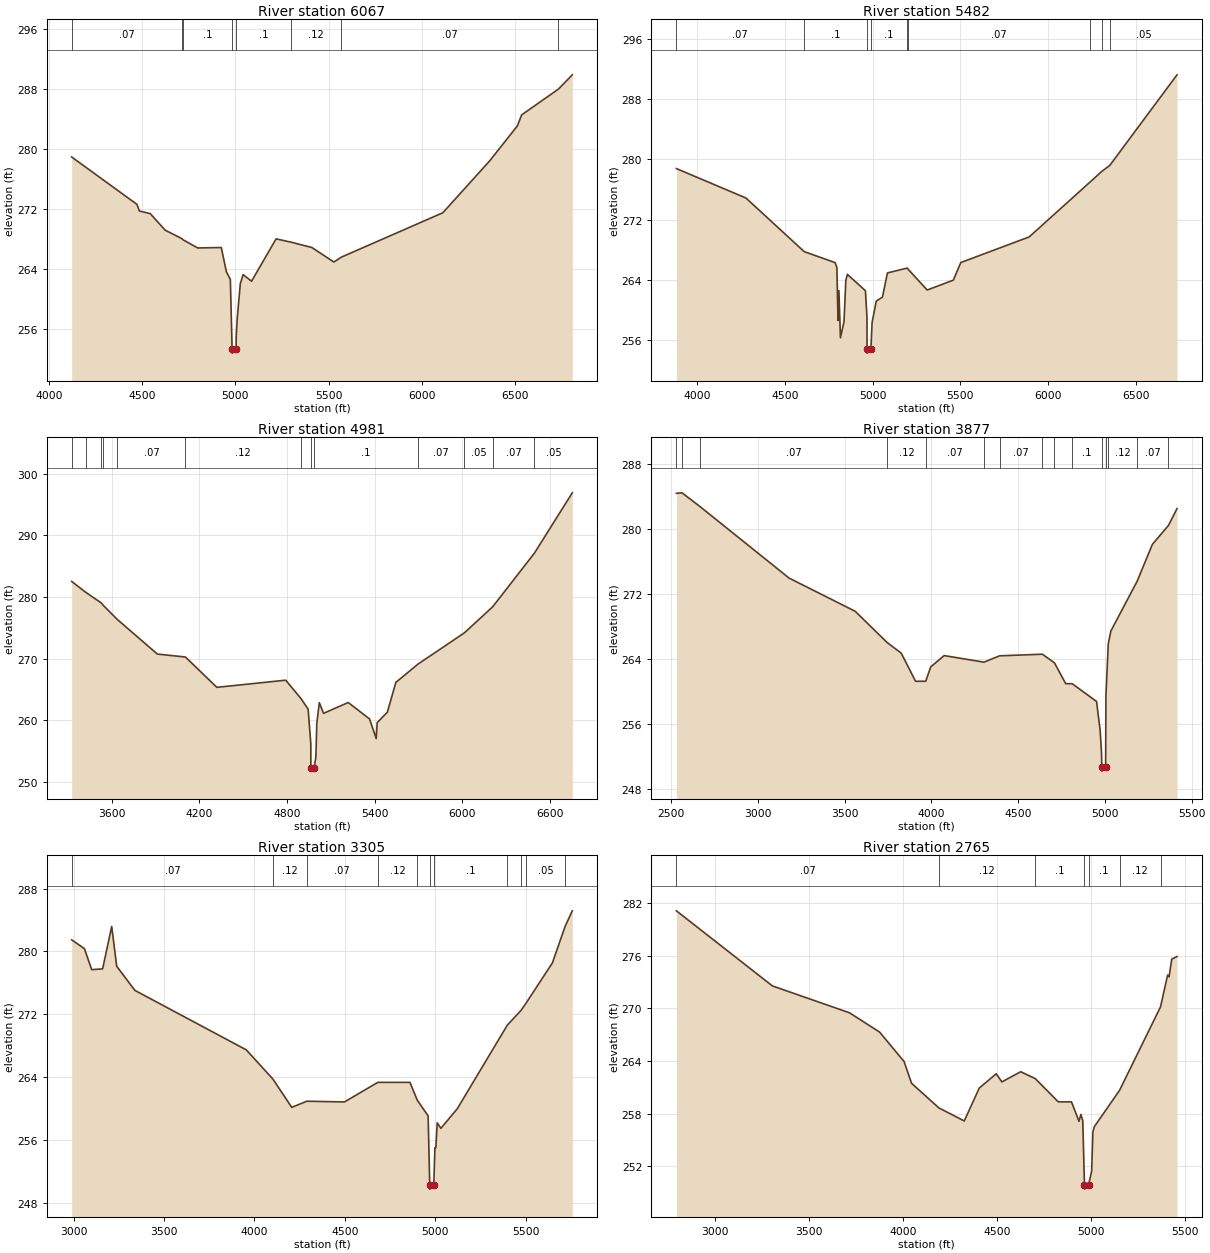
Type RM Length L Ch R = 1 ,6067    ,585,585,585
BEGIN DESCRIPTION:
BUCKHORN CREEK 8.0
END DESCRIPTION:
XS GIS Cut Line= 3
      2413525.02     13677125.04        2413075.       13676375.
      2412224.98     13674774.96
#Sta/Elev= 30
  4121.6  278.96  4471.5  272.66  4485.1  271.77  4543.4  271.42  4623.1  269.22
  4712.6   268.1  4719.9  267.93    4798  266.85  4924.4  266.91  4951.6   263.7
    4973  262.66  4982.5  253.35    4983  252.85  5004.2  253.35  5004.4  255.01
  5010.1  257.49  5026.4  262.09  5041.6   263.3  5086.7  262.42  5218.6  268.06
    5299  267.62  5410.8  266.91  5528.5  264.98  5568.9  265.63  6113.5  271.54
  6365.9  278.48  6513.6  283.11  6536.1  284.56  6733.6     288  6808.1   289.9
#Mann= 8 ,-1 , 0
  4121.6     .07       0  4712.6     .12       0  4719.9      .1       0
  4982.5     .05       0  5004.2      .1       0    5299     .12       0
  5568.9     .07       0  6733.6     .05       0
Bank Sta=4982.5,5004.2
XS Rating Curve= 0 ,0
Exp/Cntr=0.3,0.1

Type RM Length L Ch R = 1 ,5482    ,501,501,501
BEGIN DESCRIPTION:
BUCKHORN CREEK 7.0
END DESCRIPTION:
XS GIS Cut Line= 3
        2413675.     13677074.98        2413475.       13675975.
      2412324.98     13674674.98
#Sta/Elev= 30
  3882.2  278.78  4278.6  274.87  4610.6  267.75  4786.8  266.29  4796.9  265.66
  4803.3  258.62  4808.4  262.58  4817.3  256.32  4837.6  258.44  4847.8  263.89
  4856.6  264.73  4959.6  262.56  4968.5  259.07  4968.9  254.77  4969.4  254.27
  4990.8  254.77  4997.7  258.35  5021.5  261.18  5056.7  261.71  5085.1  264.92
  5198.7  265.57  5200.3  265.48  5311.8  262.65  5460.7  263.96  5503.4   266.3
  5893.1   269.7  6242.5  277.04  6306.3  278.39  6352.6   279.2  6735.9  291.23
#Mann= 9 ,-1 , 0
  3882.2     .07       0  4610.6      .1       0  4968.9     .05       0
  4990.8      .1       0  5198.7     .12       0  5200.3     .07       0
  6242.5     .05       0  6306.3     .07       0  6352.6     .05       0
Bank Sta=4968.9,4990.8
XS Rating Curve= 0 ,0
Exp/Cntr=0.3,0.1

Type RM Length L Ch R = 1 ,4981    ,1104,1104,1104
BEGIN DESCRIPTION:
BUCKHORN CREEK 6.0
END DESCRIPTION:
XS GIS Cut Line= 3
      2414475.02     13677225.04        2413825.       13675675.
      2413125.02     13674075.03
#Sta/Elev= 30
  3325.8  282.52  3421.2  280.77  3529.3  279.01  3541.6  278.65  3637.4  276.36
  3912.2  270.73  4104.6  270.25  4319.7  265.33    4791  266.49  4894.6  263.54
  4944.5  261.79  4962.8  256.19  4963.1  252.23  4963.6  251.73    4985  252.23
  4997.4  253.99  5003.9  259.49    5021  262.84  5050.3  261.11  5219.1  262.87
  5364.9   260.2  5410.5  257.01  5417.1  259.59  5486.9   261.3    5545  266.13
    5696  269.09  6014.6  274.18  6208.1  278.41  6493.4   287.1    6753   296.9
#Mann= 13 ,-1 , 0
  3325.8     .07       0  3421.2    .035       0  3529.3     .07       0
  3541.6    .035       0  3637.4     .07       0  4104.6     .12       0
  4894.6      .1       0  4963.1     .05       0    4985      .1       0
    5696     .07       0  6014.6     .05       0  6208.1     .07       0
  6493.4     .05       0
Bank Sta=4963.1,4985
XS Rating Curve= 0 ,0
Exp/Cntr=0.3,0.1

Type RM Length L Ch R = 1 ,3877    ,572,572,572
BEGIN DESCRIPTION:
BUCKHORN CREEK 5.0
END DESCRIPTION:
XS GIS Cut Line= 3
      2414725.01     13677275.04        2414125.       13674875.
        2414025.     13674475.02
#Sta/Elev= 30
  2529.5  284.34  2561.9   284.4  2664.2  282.73  3178.9  273.91  3560.3  269.82
  3744.7  265.97  3825.7  264.67  3908.2  261.21  3966.9  261.21  3995.8  262.98
  4073.1  264.37  4302.9  263.56  4392.7  264.34  4639.7  264.54  4709.3  263.47
  4774.1  260.91  4811.5  260.91  4951.9  258.72  4972.5  255.15  4980.2   252.5
    4982  250.65  4982.5  250.15  5004.1  250.65    5006  259.52  5019.5  265.82
  5034.3  267.39  5185.6  273.51    5274  278.07  5366.2  280.38  5415.7  282.46
#Mann= 15 ,-1 , 0
  2529.5     .07       0  2561.9    .035       0  2664.2     .07       0
  3744.7     .12       0  3966.9     .07       0  4302.9     .12       0
  4392.7     .07       0  4639.7     .12       0  4709.3     .07       0
  4811.5      .1       0    4982     .05       0  5004.1      .1       0
  5019.5     .12       0  5185.6     .07       0  5366.2     .05       0
Bank Sta=4982,5004.1
XS Rating Curve= 0 ,0
Exp/Cntr=0.3,0.1

Type RM Length L Ch R = 1 ,3305    ,540,540,540
BEGIN DESCRIPTION:
BUCKHORN CREEK 4.0
END DESCRIPTION:
XS GIS Cut Line= 3
        2414825.     13676975.02        2414625.       13674975.
        2414525.     13674225.03
#Sta/Elev= 30
    2990  281.48  3060.4  280.35  3100.6  277.68  3160.9  277.78  3211.1  283.18
  3238.8  278.11  3339.3  275.04  3954.8  267.47  4102.4  263.74  4206.1  260.15
  4289.2  260.93  4497.5  260.84  4681.6  263.33  4859.3  263.33    4900  261.06
  4959.8  259.06  4968.8  250.24  4969.3  249.74  4990.9  250.24  4997.5  255.02
  5002.5  255.02  5010.1  258.18  5030.3  257.48  5121.1  259.98  5398.2  270.64
  5472.5  272.47    5498  273.31  5646.9  278.55  5717.2  283.21  5756.6  285.17
#Mann= 11 ,-1 , 0
    2990     .07       0  4102.4     .12       0  4289.2     .07       0
  4681.6     .12       0    4900      .1       0  4968.8     .05       0
  4990.9      .1       0  5398.2     .05       0  5472.5     .07       0
    5498     .05       0  5717.2     .07       0
Bank Sta=4968.8,4990.9
XS Rating Curve= 0 ,0
Exp/Cntr=0.3,0.1

Type RM Length L Ch R = 1 ,2765    ,548,548,548
BEGIN DESCRIPTION:
BUCKHORN CREEK 3.0
END DESCRIPTION:
XS GIS Cut Line= 3
        2415025.     13676875.02        2415025.       13674675.
        2414725.       13674325.
#Sta/Elev= 30
  2794.7  281.15  3304.7  272.58  3714.7  269.51  3874.7  267.31  4004.7  263.95
  4044.7  261.46    4190  258.65  4324.7  257.16  4404.7  260.92  4494.7  262.55
  4524.7  261.62  4624.7  262.78  4702.1     262  4824.7  259.34  4894.7  259.34
  4934.7  257.12  4944.7  257.91  4954.7  257.21  4963.7  249.88  4964.2  249.38
  4985.8  249.88  5001.9  251.44  5008.4  255.89  5016.1  256.51  5150.3  260.66
  5367.9  270.18  5405.8  273.82  5413.4  273.61  5427.7  275.64  5455.7  275.93
#Mann= 7 ,-1 , 0
  2794.7     .07       0    4190     .12       0  4702.1      .1       0
  4963.7     .05       0  4985.8      .1       0  5150.3     .12       0
  5367.9     .07       0
Bank Sta=4963.7,4985.8
XS Rating Curve= 0 ,0
Exp/Cntr=0.3,0.1

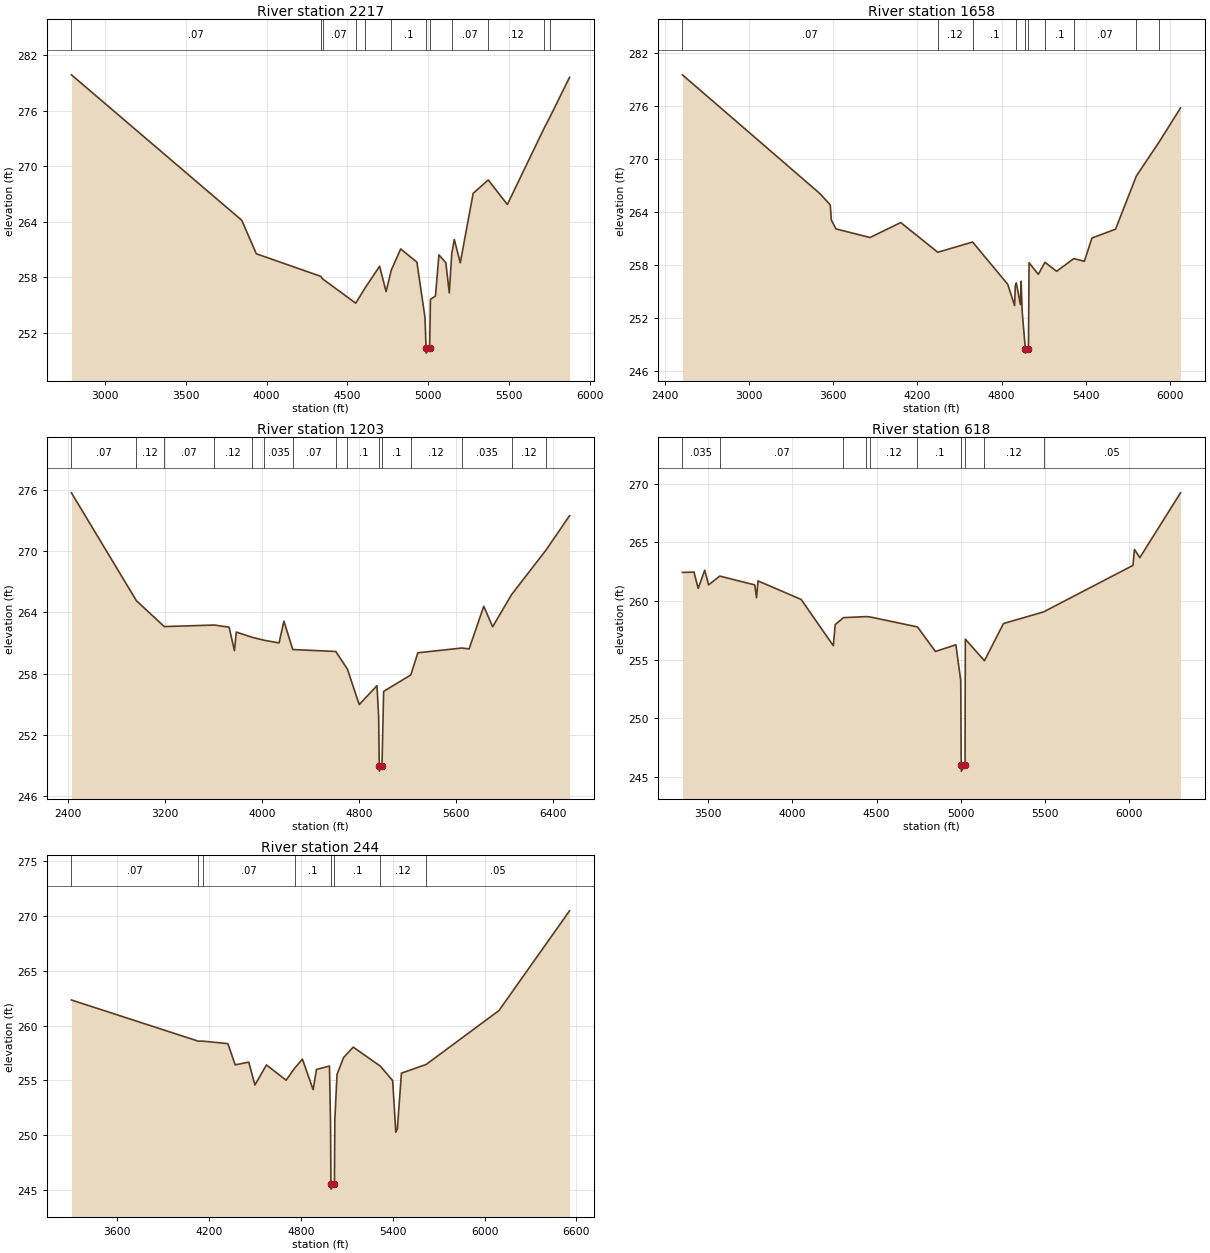
Type RM Length L Ch R = 1 ,2217    ,559,559,559
BEGIN DESCRIPTION:
BUCKHORN CREEK 2.0
END DESCRIPTION:
XS GIS Cut Line= 3
        2415275.     13676775.04        2415475.       13674575.
      2414724.97     13674124.98
#Sta/Elev= 30
  2791.3  279.85  3845.7  264.16    3936  260.54  4334.5  258.11  4346.3  257.83
  4551.4  255.21  4608.1  256.82  4699.2   259.2  4739.3  256.46  4771.8  258.79
  4829.7  261.06  4930.1  259.64  4980.3  253.66  4986.9  250.32  4987.4  249.82
    5009  250.32    5014  255.63  5045.1  255.98  5066.5  260.42  5109.3  259.57
  5130.6  256.32  5146.1  260.59  5161.7  262.08  5198.7  259.57  5278.4  267.06
  5371.7  268.51  5490.2  265.86  5716.9  274.06  5754.9  275.33  5875.1  279.58
#Mann= 12 ,-1 , 0
  2791.3     .07       0  4334.5     .12       0  4346.3     .07       0
  4551.4     .12       0  4608.1     .07       0  4771.8      .1       0
  4986.9     .05       0    5009      .1       0  5146.1     .07       0
  5371.7     .12       0  5716.9     .07       0  5754.9     .12       0
Bank Sta=4986.9,5009
XS Rating Curve= 0 ,0
Exp/Cntr=0.3,0.1

Type RM Length L Ch R = 1 ,1658    ,455,455,455
BEGIN DESCRIPTION:
BUCKHORN CREEK 1.0
END DESCRIPTION:
XS GIS Cut Line= 3
      2415325.01     13676774.96        2415925.       13674375.
      2414924.96     13673974.98
#Sta/Elev= 30
  2525.1  279.52  3504.3  266.11    3579  264.82  3586.8   263.1  3620.3   262.1
  3862.5  261.13  4081.5  262.82  4345.8  259.46  4593.8  260.62  4844.3  255.84
  4893.3  253.43  4898.4  255.72  4905.5     256  4934.5  253.55  4939.6  256.19
  4947.4  252.74  4969.7  248.56  4970.2  248.06    4992  248.56  4996.3  258.28
  5062.2  256.97  5109.6  258.33  5192.8  257.31  5314.8  258.74  5390.7  258.45
  5444.5  261.07  5612.8  262.07  5761.5  268.09  5922.9  271.91    6076  275.78
#Mann= 10 ,-1 , 0
  2525.1     .07       0  4345.8     .12       0  4593.8      .1       0
  4905.5    .035       0  4969.7    .035       0    4992    .035       0
  5109.6      .1       0  5314.8     .07       0  5761.5     .12       0
  5922.9     .07       0
Bank Sta=4969.7,4992
XS Rating Curve= 0 ,0
Exp/Cntr=0.3,0.1

Type RM Length L Ch R = 1 ,1203    ,585,585,585
BEGIN DESCRIPTION:
X18398
END DESCRIPTION:
XS GIS Cut Line= 4
      2415609.04     13676499.98      2416481.56     13674655.67
      2416229.82     13673995.95      2414928.84     13673596.98
#Sta/Elev= 30
  2426.9  275.71  2962.9  265.14  3192.2  262.61  3604.2  262.76  3726.7  262.55
    3771  260.25  3786.5  262.07  3913.7  261.57  4015.7  261.27  4138.9  261.01
  4178.9  263.14  4251.9  260.36  4606.4  260.17  4702.4  258.45  4799.7  254.97
  4946.3  256.82  4960.3   253.8  4965.2  248.95  4965.7  248.45  4987.6  248.95
  5001.1  256.26  5225.2  257.87    5283  260.04  5646.6  260.51  5705.9  260.42
  5826.9   264.6  5900.1  262.59    6056  265.74  6340.6  270.11  6534.1  273.47
#Mann= 15 ,-1 , 0
  2426.9     .07       0  2962.9     .12       0  3192.2     .07       0
  3604.2     .12       0  3913.7     .07       0  4015.7    .035       0
  4251.9     .07       0  4606.4     .12       0  4702.4      .1       0
  4965.2     .05       0  4987.6      .1       0  5225.2     .12       0
  5646.6    .035       0    6056     .12       0  6340.6     .07       0
Bank Sta=4965.2,4987.6
XS Rating Curve= 0 ,0
Exp/Cntr=0.3,0.1

Type RM Length L Ch R = 1 ,618     ,374,374,374
BEGIN DESCRIPTION:
X18399
END DESCRIPTION:
XS GIS Cut Line= 4
      2416429.48      13675219.9      2416794.06     13674186.92
      2416377.39     13673648.73      2415268.18     13673241.43
#Sta/Elev= 30
  3347.3  262.43  3416.1  262.46  3440.8  261.07  3479.8  262.62  3502.7  261.37
  3568.9  262.12  3776.7  261.37  3787.3  260.28  3796.1  261.71  4052.4  260.13
  4243.3  256.19  4254.7  257.99  4303.2  258.58  4440.3  258.67  4461.3  258.64
  4742.9  257.79  4849.9   255.7    4971  256.27    5000  253.22    5003  246.01
  5003.5  245.51  5025.5  246.01  5027.2  256.75  5140.8  254.91  5253.8  258.08
  5491.9  259.07  6022.6  263.03  6031.4  264.39  6063.4  263.69    6305  269.21
#Mann= 10 ,-1 , 0
  3347.3    .035       0  3568.9     .07       0  4303.2     .12       0
  4440.3     .07       0  4461.3     .12       0  4742.9      .1       0
    5003     .05       0  5025.5      .1       0  5140.8     .12       0
  5491.9     .05       0
Bank Sta=5003,5025.5
XS Rating Curve= 0 ,0
Exp/Cntr=0.3,0.1

Type RM Length L Ch R = 1 ,244     ,0,0,0
BEGIN DESCRIPTION:
X18400
END DESCRIPTION:
XS GIS Cut Line= 4
      2416585.73     13675089.69      2416993.71     13673804.98
      2416568.37     13673344.91      2415309.82     13673101.88
#Sta/Elev= 30
  3299.6  262.34    4130  258.57  4156.6  258.58  4322.3  258.35  4370.2  256.41
  4458.7  256.66  4499.2  254.57  4574.3   256.4    4703  255.01  4760.2  256.13
  4809.6  256.93  4879.9  254.14  4901.4  255.99  4986.5   256.3  4993.3  251.18
  4996.2  245.55  4996.7  245.05  5018.8  245.55  5021.6  251.38  5035.8  255.53
  5078.3  257.07  5141.9  258.03  5318.4   256.3  5399.7  254.97  5420.1  250.25
  5430.3  250.56    5457  255.65  5618.9  256.45  6094.3  261.37  6555.9  270.49
#Mann= 8 ,-1 , 0
  3299.6     .07       0    4130     .12       0  4156.6     .07       0
  4760.2      .1       0  4996.2     .05       0  5018.8      .1       0
  5318.4     .12       0  5618.9     .05       0
Bank Sta=4996.2,5018.8
XS Rating Curve= 0 ,0
Exp/Cntr=0.3,0.1

Chan Stop Cuts=-1
Use User Specified Reach Order=0
Composite Channel Slope=5