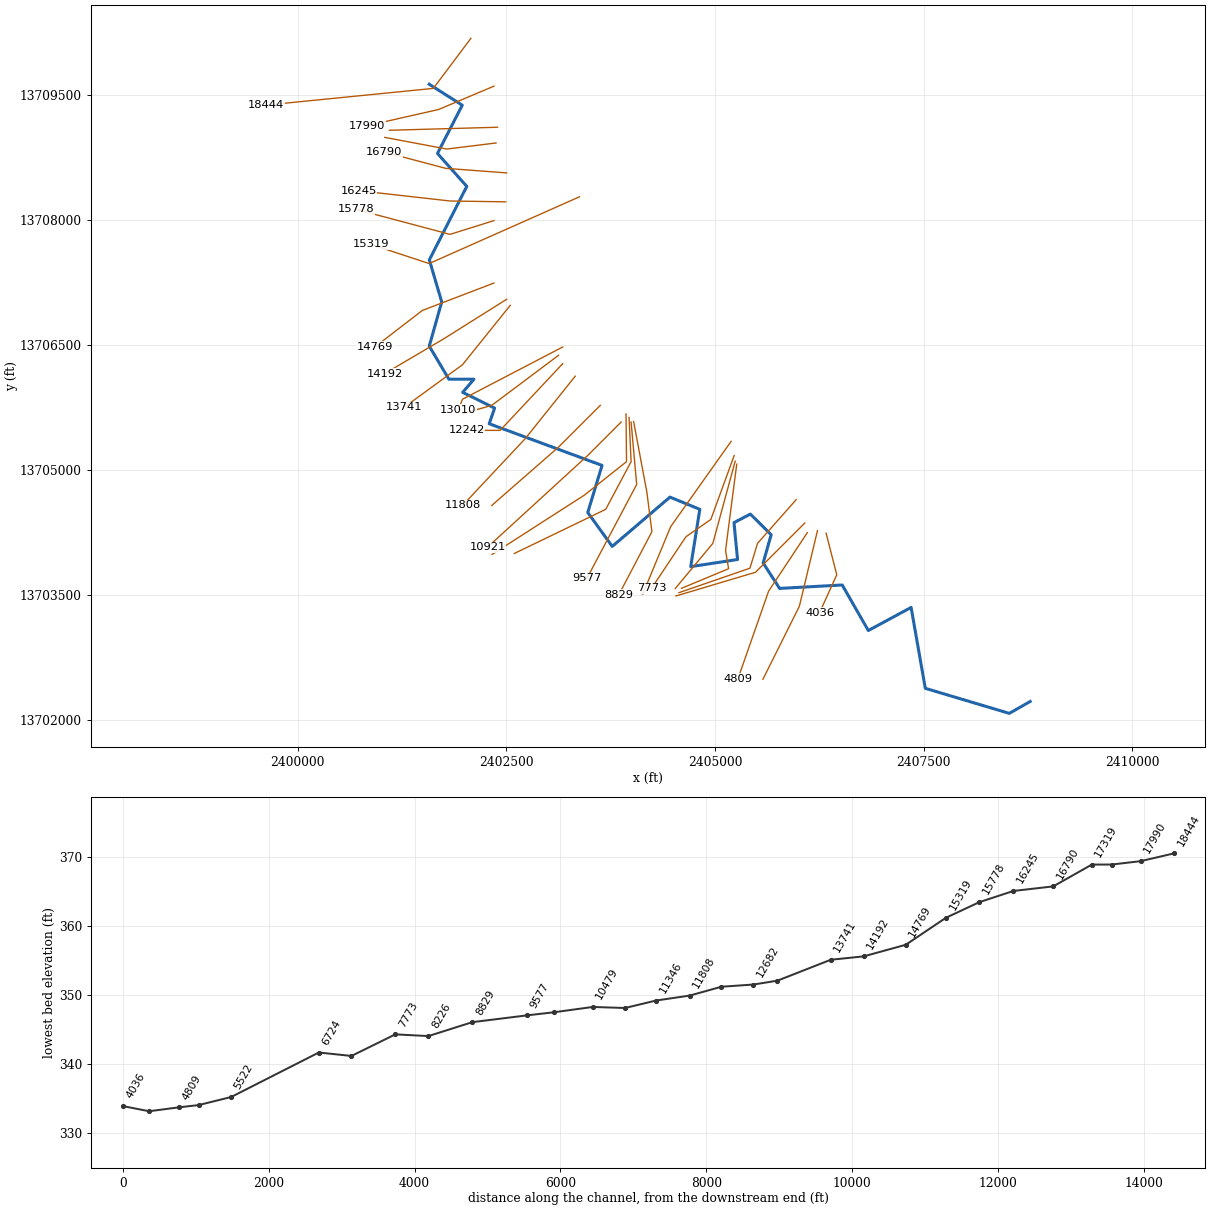
--- LIBERTY CREEK.prj (project) ---

Proj Title=LIBERTY CREEK Base Level Engineering
Current Plan=p01
Default Exp/Contr=0.3,0.1
English Units
Geom File=g01
Flow File=f01
Plan File=p01
Y Axis Title=Elevation
X Axis Title(PF)=Main Channel Distance
X Axis Title(XS)=Station
BEGIN DESCRIPTION:
LIBERTY CREEK
END DESCRIPTION:
DSS Export Rating Curves= 0
DSS Export Rating Curve Sorted= 0
DSS Export Volume Flow Curves= 0
DXF OffsetX= 0
DXF OffsetY= 0
DXF ScaleX= 1
DXF ScaleY= 10

--- LIBERTY CREEK.p01 (plan) ---

Plan Title=Multiple Run
Short Identifier=Multiple
Geom File=g01
Flow File=f01
Subcritical Flow
K Sum by GR= 0
Std Step Tol= 0.01
Critical Tol= 0.01
Num of Std Step Trials= 20
Max Error Tol= 0.3
Flow Tol Ratio= 0.001
Split Flow NTrial= 30
Split Flow Tol= 0.02
Split Flow Ratio= 0.02
Log Output Level= 0
Friction Slope Method= 1
Unsteady Friction Slope Method= 2
Unsteady Bridges Friction Slope Method= 1
Parabolic Critical Depth
Global Vel Dist=  1 , 1 , 1
Global Log Level= 0
CheckData=True
Encroach Param= -1, 0, 0, 0
BEGIN DESCRIPTION:
Multiple Run
END DESCRIPTION:

--- LIBERTY CREEK.f01 (steady flow) ---

Flow Title=Multiple
Number of Profiles=7
Profile Names=10-year,25-year,50-year,1pct_min,100-year,1pct_plu,500-year
River Rch & RM= LIBERTY CREEK,Reach-1,18444
     787    1278    1725    1126    2247    4484    3779
River Rch & RM= LIBERTY CREEK,Reach-1,14192
    1094    1809    2470    1630    3252    6489    5586
River Rch & RM= LIBERTY CREEK,Reach-1,13010
    1271    2106    2877    1898    3787    7556    6504
River Rch & RM= LIBERTY CREEK,Reach-1,5522
    1326    2195    2996    1974    3939    7860    6751
River Rch & RM= LIBERTY CREEK,Reach-1,1013
    1424    2363    3232    2133    4255    8491    7315
Boundary for River Rch & Prof#=LIBERTY CREEK,Reach-1,1
Up Type=0
Dn Type=3
Dn Slope=0.005
Boundary for River Rch & Prof#=LIBERTY CREEK,Reach-1,2
Up Type=0
Dn Type=3
Dn Slope=0.005
Boundary for River Rch & Prof#=LIBERTY CREEK,Reach-1,3
Up Type=0
Dn Type=3
Dn Slope=0.005
Boundary for River Rch & Prof#=LIBERTY CREEK,Reach-1,4
Up Type=0
Dn Type=3
Dn Slope=0.005
Boundary for River Rch & Prof#=LIBERTY CREEK,Reach-1,5
Up Type=0
Dn Type=3
Dn Slope=0.005
Boundary for River Rch & Prof#=LIBERTY CREEK,Reach-1,6
Up Type=0
Dn Type=3
Dn Slope=0.005
Boundary for River Rch & Prof#=LIBERTY CREEK,Reach-1,7
Up Type=0
Dn Type=3
Dn Slope=0.005

--- LIBERTY CREEK.g01 (geometry) ---

Geom Title=Existing Conditions

River Reach=LIBERTY CREEK,Reach-1
Reach XY= 30
      2401575.00     13709625.00      2401971.53     13709373.50
      2401674.48     13708795.03      2402025.63     13708399.92
      2401577.15     13707519.03      2401725.51     13707014.83
      2401575.97     13706485.29      2401811.24     13706088.24
      2402111.65     13706088.25      2401976.56     13705931.08
      2402359.00     13705742.13      2402294.26     13705554.53
      2403645.97     13705055.09      2403474.82     13704490.29
      2403768.06     13704083.83      2404459.60     13704674.92
      2404817.13     13704528.62      2404708.21     13703841.39
      2405269.17     13703927.06      2405226.57     13704368.96
      2405423.50     13704471.54      2405671.54     13704223.50
      2405576.19     13703885.50      2405772.54     13703580.45
      2406523.54     13703621.46      2406835.64     13703075.55
      2407348.47     13703352.29      2407518.49     13702382.73
      2408524.90     13702082.33      2408775.00     13702225.00

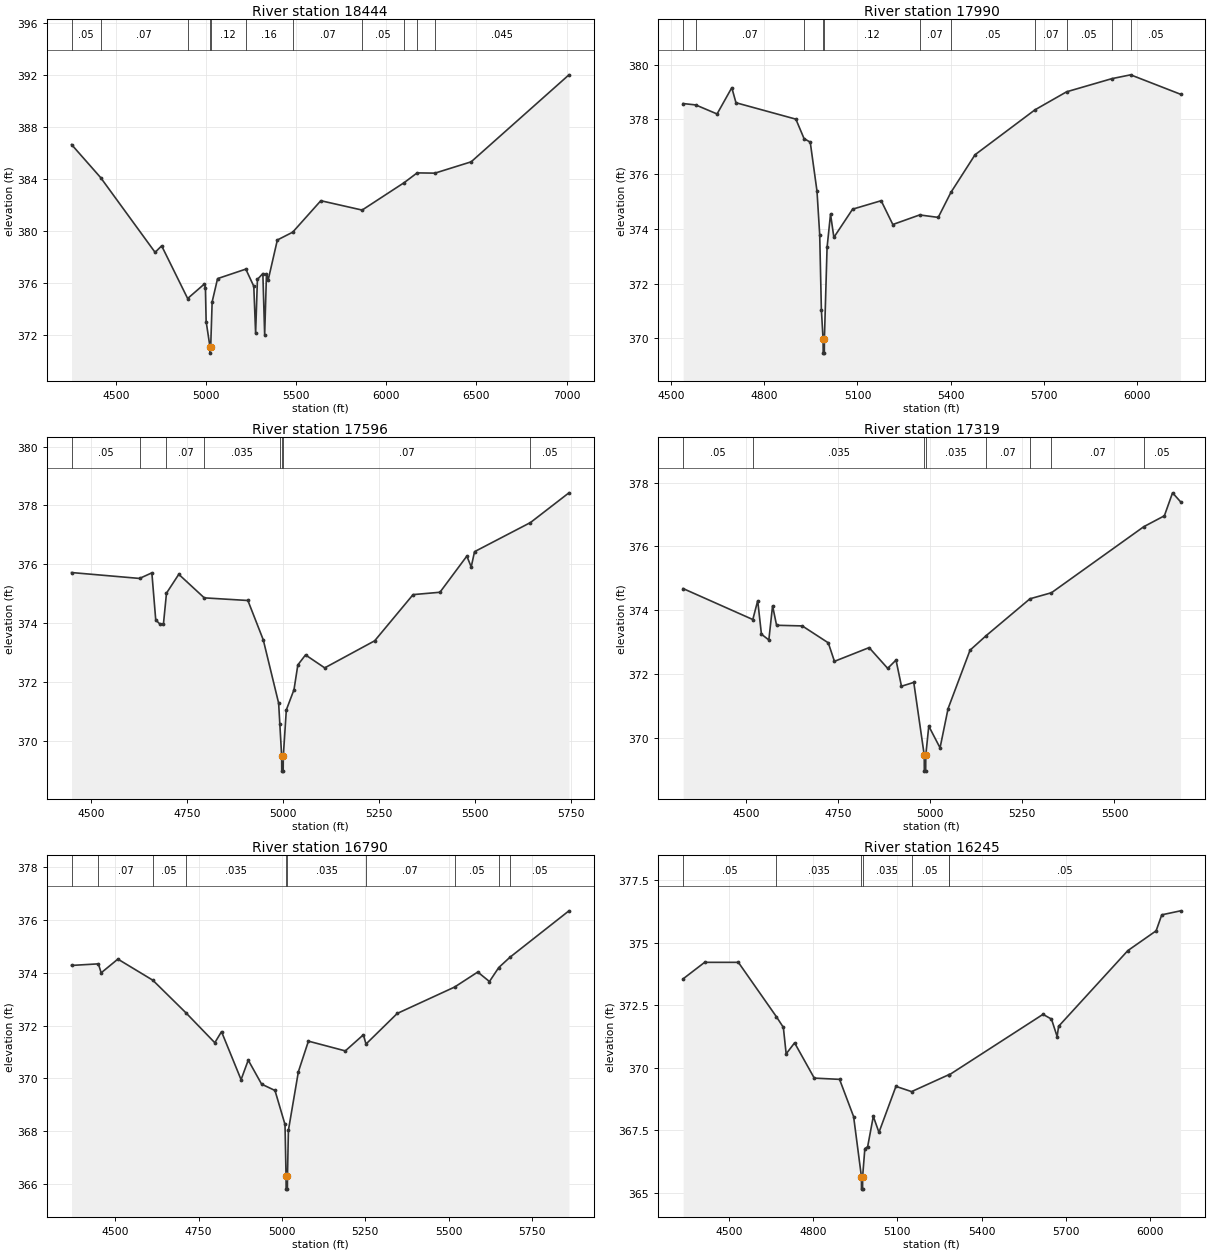
Type RM Length L Ch R = 1,18444,454,454,454
BEGIN DESCRIPTION:
LIBERTY CREEK 22.0
END DESCRIPTION:
XS GIS Cut Line= 3
      2402075.03     13710175.04      2401625.00     13709575.00
      2399625.02     13709375.00
#Sta/Elev= 30
  4253.2  386.62  4414.6  384.08  4716.8  378.33  4753.2  378.83  4897.5  374.78
  4989.7  375.89  4996.0  375.62  5000.1  373.01  5021.2  371.08  5021.5  370.58
  5025.4  371.08  5033.4  374.52  5063.5  376.31  5220.2  377.04  5264.5  375.72
  5274.6  372.10  5284.6  376.25  5314.8  376.70  5324.8  371.98  5334.9  376.68
  5344.9  376.24  5395.2  379.28  5480.3  379.88  5636.4  382.30  5865.6  381.58
  6098.9  383.69  6170.8  384.44  6269.5  384.42  6470.5  385.29  7013.2  391.98
#Mann=11,-1,0
  4253.2    0.05       0  4414.6    0.07       0  4897.5    0.12       0
  5021.2    0.07       0  5025.4    0.12       0  5220.2    0.16       0
  5480.3    0.07       0  5865.6    0.05       0  6098.9    0.07       0
  6170.8    0.05       0  6269.5   0.045       0
Bank Sta=5021.2,5025.4
Exp/Cntr=0.3,0.1

Type RM Length L Ch R = 1,17990,394,394,394
BEGIN DESCRIPTION:
A19633
END DESCRIPTION:
XS GIS Cut Line= 3
      2402351.57     13709601.96      2401688.47     13709322.12
      2400830.71     13709127.45
#Sta/Elev= 30
  4539.4  378.58  4579.9  378.53  4648.5  378.20  4695.9  379.16  4709.3  378.61
  4901.9  378.01  4928.2  377.30  4948.1  377.17  4969.8  375.38  4978.5  373.79
  4983.9  371.05  4989.4  369.96  4989.7  369.46  4993.4  369.46  4993.6  369.96
  5002.2  373.32  5013.3  374.54  5024.1  373.69  5084.2  374.72  5176.1  375.03
  5213.6  374.16  5299.9  374.51  5359.6  374.42  5400.2  375.33  5478.0  376.71
  5670.5  378.35  5772.4  379.01  5917.8  379.49  5978.2  379.63  6138.7  378.92
#Mann=11,-1,0
  4539.4    0.05       0  4579.9    0.07       0  4928.2    0.12       0
  4989.4    0.07       0  4993.6    0.12       0  5299.9    0.07       0
  5400.2    0.05       0  5670.5    0.07       0  5772.4    0.05       0
  5917.8    0.07       0  5978.2    0.05       0
Bank Sta=4989.4,4993.6
Exp/Cntr=0.3,0.1

Type RM Length L Ch R = 1,17596,277,277,277
BEGIN DESCRIPTION:
A19632
END DESCRIPTION:
XS GIS Cut Line= 2
      2402394.17     13709109.20      2401099.18     13709072.73
#Sta/Elev= 30
  4449.7  375.72  4626.8  375.52  4658.9  375.71  4669.0  374.11  4679.0  373.98
  4689.0  373.96  4697.0  375.02  4729.0  375.66  4795.4  374.86  4909.0  374.77
  4949.1  373.43  4989.1  371.28  4992.2  370.57  4997.0  369.47  4997.2  368.97
  5000.9  368.97  5001.2  369.47  5009.1  371.05  5029.1  371.74  5039.1  372.58
  5059.1  372.92  5109.1  372.48  5239.2  373.40  5339.2  374.97  5409.2  375.05
  5479.3  376.28  5490.6  375.91  5499.3  376.43  5645.0  377.42  5745.2  378.43
#Mann=8,-1,0
  4449.7    0.05       0  4626.8   0.035       0  4697.0    0.07       0
  4795.4   0.035       0  4992.2    0.07       0  4997.0    0.07       0
  5001.2    0.07       0  5645.0    0.05       0
Bank Sta=4997,5001.2
Exp/Cntr=0.3,0.1

Type RM Length L Ch R = 1,17319,529,529,529
BEGIN DESCRIPTION:
A19631
END DESCRIPTION:
XS GIS Cut Line= 3
      2402375.89     13708920.62      2401785.80     13708847.62
      2401043.66     13708987.53
#Sta/Elev= 30
  4329.5  374.68  4518.6  373.71  4531.9  374.30  4542.0  373.25  4562.1  373.07
  4572.2  374.14  4583.1  373.53  4652.8  373.51  4723.4  372.98  4740.1  372.40
  4834.2  372.83  4884.6  372.18  4907.2  372.44  4922.0  371.62  4955.4  371.74
  4983.8  369.46  4984.0  368.96  4987.7  368.96  4988.0  369.46  4996.1  370.37
  5026.7  369.69  5048.5  370.92  5108.1  372.75  5151.3  373.20  5270.7  374.36
  5329.1  374.55  5579.7  376.62  5635.4  376.96  5657.6  377.68  5679.3  377.40
#Mann=8,-1,0
  4329.5    0.05       0  4518.6   0.035       0  4983.8   0.035       0
  4988.0   0.035       0  5151.3    0.07       0  5270.7    0.05       0
  5329.1    0.07       0  5579.7    0.05       0
Bank Sta=4983.8,4988
Exp/Cntr=0.3,0.1

Type RM Length L Ch R = 1,16790,545,545,545
BEGIN DESCRIPTION:
LIBERTY CREEK 21.0
END DESCRIPTION:
XS GIS Cut Line= 3
      2402503.62     13708561.70      2401773.64     13708616.45
      2401038.73     13708810.81
#Sta/Elev= 30
  4368.9  374.28  4449.4  374.34  4457.8  374.00  4507.9  374.52  4612.7  373.72
  4711.6  372.49  4798.7  371.35  4818.8  371.77  4877.5  369.95  4899.0  370.69
  4939.1  369.78  4979.2  369.54  5009.3  368.25  5012.4  366.30  5012.7  365.80
  5016.4  365.80  5016.7  366.30  5019.5  368.03  5049.4  370.25  5079.5  371.41
  5190.2  371.04  5244.3  371.65  5252.3  371.30  5346.0  372.46  5518.0  373.46
  5587.5  374.03  5622.6  373.67  5650.5  374.20  5684.1  374.59  5861.1  376.35
#Mann=10,-1,0
  4368.9    0.05       0  4449.4    0.07       0  4612.7    0.05       0
  4711.6   0.035       0  5012.4   0.035       0  5016.7   0.035       0
  5252.3    0.07       0  5518.0    0.05       0  5650.5    0.07       0
  5684.1    0.05       0
Bank Sta=5012.4,5016.7
Exp/Cntr=0.3,0.1

Type RM Length L Ch R = 1,16245,467,467,467
BEGIN DESCRIPTION:
LIBERTY CREEK 20.0
END DESCRIPTION:
XS GIS Cut Line= 3
      2402491.52     13708214.95      2401825.00     13708225.00
      2400728.65     13708348.63
#Sta/Elev= 30
  4337.7  373.55  4414.2  374.21  4534.2  374.21  4669.3  372.04  4694.3  371.61
  4704.3  370.55  4734.3  370.99  4804.3  369.58  4894.3  369.53  4944.3  368.04
  4972.1  365.64  4972.4  365.14  4976.2  365.14  4976.4  365.64  4984.3  366.76
  4994.3  366.84  5014.4  368.05  5034.5  367.41  5094.9  369.25  5150.6  369.04
  5283.8  369.72  5284.6  369.71  5618.2  372.13  5648.4  371.94  5668.5  371.24
  5673.6  371.65  5920.1  374.68  6020.7  375.47  6040.8  376.11  6107.6  376.27
#Mann=7,-1,0
  4337.7    0.05       0  4669.3   0.035       0  4972.1   0.035       0
  4976.4   0.035       0  5150.6    0.05       0  5283.8    0.07       0
  5284.6    0.05       0
Bank Sta=4972.1,4976.4
Exp/Cntr=0.3,0.1

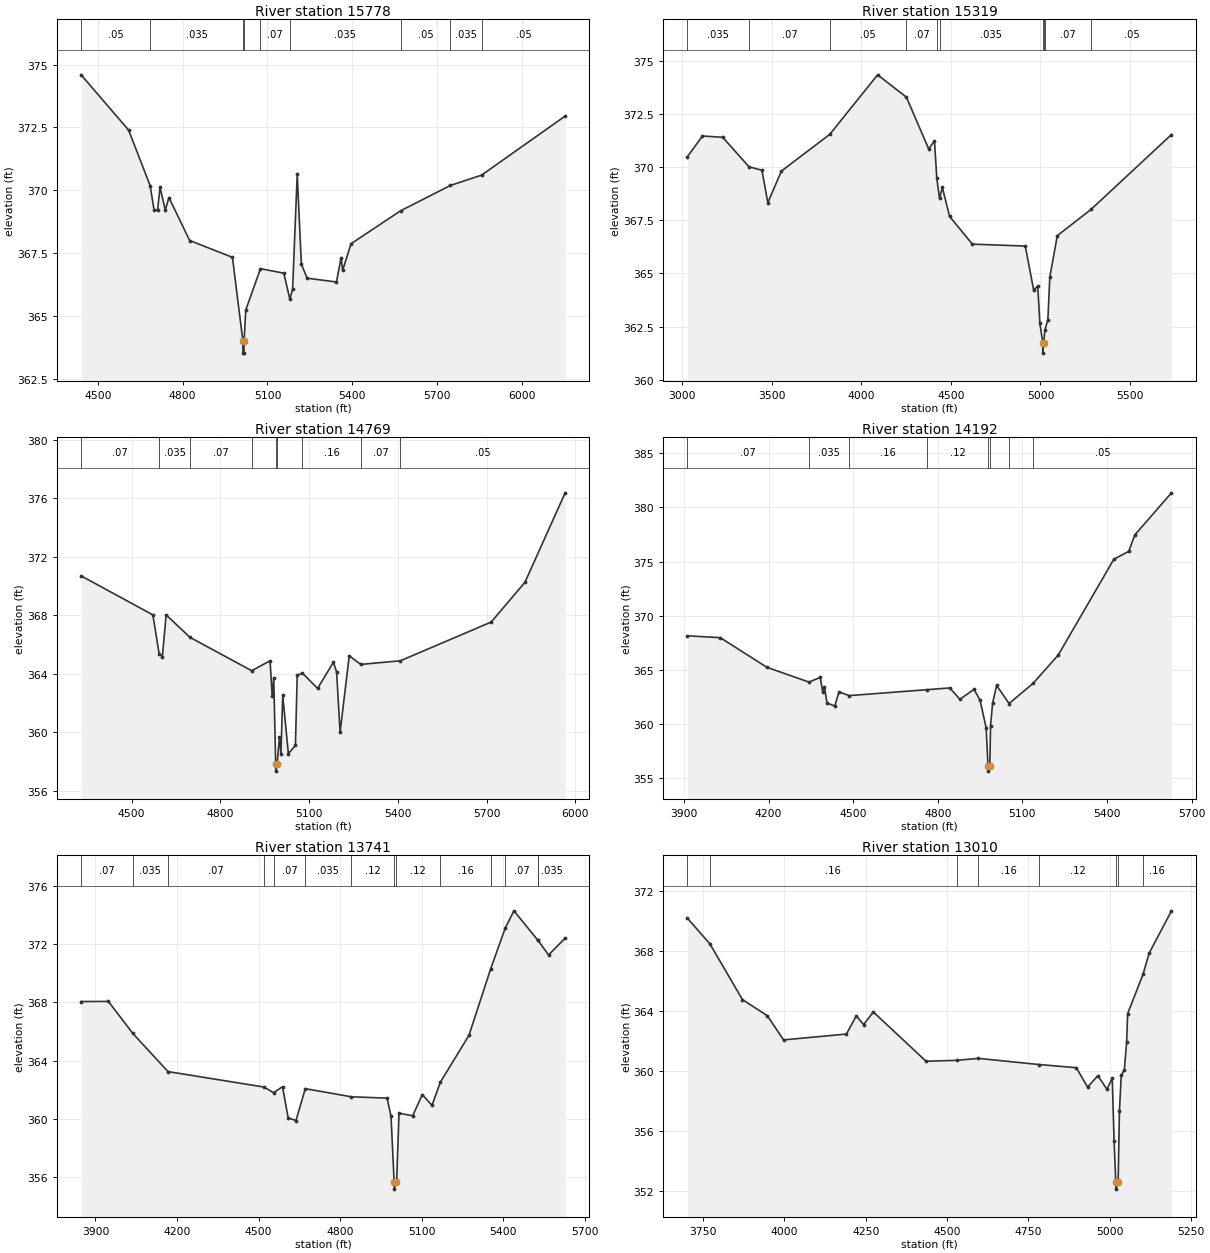
Type RM Length L Ch R = 1,15778,459,459,459
BEGIN DESCRIPTION:
LIBERTY CREEK 19.0
END DESCRIPTION:
XS GIS Cut Line= 3
      2402351.55     13707989.86      2401825.00     13707825.00
      2400702.93     13708123.70
#Sta/Elev= 30
  4440.6  374.59  4608.7  372.39  4684.9  370.18  4698.9  369.20  4711.3  369.22
  4719.9  370.11  4738.5  369.21  4751.3  369.71  4824.7  368.00  4976.1  367.33
  5012.8  364.02  5013.1  363.52  5016.9  363.52  5017.2  364.02  5023.4  365.24
  5075.3  366.88  5157.9  366.70  5179.3  365.66  5189.0  366.08  5205.3  370.63
  5220.0  367.06  5240.3  366.50  5344.2  366.35  5360.7  367.32  5365.9  366.81
  5395.6  367.87  5570.8  369.18  5747.3  370.19  5857.7  370.60  6153.5  372.95
#Mann=9,-1,0
  4440.6    0.05       0  4684.9   0.035       0  5012.8   0.035       0
  5017.2   0.035       0  5075.3    0.07       0  5179.3   0.035       0
  5570.8    0.05       0  5747.3   0.035       0  5857.7    0.05       0
Bank Sta=5012.8,5017.2
Exp/Cntr=0.3,0.1

Type RM Length L Ch R = 1,15319,550,550,550
BEGIN DESCRIPTION:
LIBERTY CREEK 18.0
END DESCRIPTION:
XS GIS Cut Line= 3
      2403375.02     13708275.01      2401575.00     13707475.00
      2400879.68     13707703.84
#Sta/Elev= 30
  3029.4  370.50  3113.5  371.47  3226.4  371.41  3373.2  370.02  3445.3  369.86
  3478.1  368.33  3554.0  369.82  3824.2  371.55  4090.9  374.35  4251.5  373.30
  4376.1  370.86  4408.3  371.24  4421.4  369.47  4436.5  368.53  4452.0  369.06
  4492.4  367.69  4619.6  366.38  4915.1  366.29  4961.6  364.23  4984.8  364.40
  4996.5  362.65  5012.7  361.75  5013.0  361.25  5017.5  361.75  5025.1  362.35
  5041.3  362.83  5052.1  364.83  5093.9  366.78  5282.9  368.02  5731.2  371.54
#Mann=10,-1,0
  3029.4   0.035       0  3373.2    0.07       0  3824.2    0.05       0
  4251.5    0.07       0  4421.4    0.05       0  4436.5   0.035       0
  5012.7   0.035       0  5017.5   0.035       0  5025.1    0.07       0
  5282.9    0.05       0
Bank Sta=5012.7,5017.5
Exp/Cntr=0.3,0.1

Type RM Length L Ch R = 1,14769,577,577,577
BEGIN DESCRIPTION:
LIBERTY CREEK 17.0
END DESCRIPTION:
XS GIS Cut Line= 3
      2402351.54     13707241.60      2401493.80     13706913.10
      2400924.96     13706474.97
#Sta/Elev= 30
  4329.4  370.70  4572.0  368.03  4593.4  365.34  4604.1  365.18  4616.8  368.03
  4697.6  366.49  4906.1  364.21  4968.2  364.89  4975.3  362.51  4980.6  363.73
  4987.2  357.84  4987.6  357.34  4992.0  357.84  4999.9  359.65  5004.9  358.52
  5011.0  362.53  5030.0  358.54  5053.9  359.10  5060.0  363.89  5077.2  364.05
  5128.8  363.00  5182.4  364.79  5193.1  364.13  5204.9  360.01  5235.9  365.23
  5274.9  364.64  5408.9  364.89  5715.8  367.54  5829.9  370.26  5965.9  376.38
#Mann=9,-1,0
  4329.4    0.07       0  4593.4   0.035       0  4697.6    0.07       0
  4906.1    0.12       0  4987.2    0.07       0  4992.0    0.12       0
  5077.2    0.16       0  5274.9    0.07       0  5408.9    0.05       0
Bank Sta=4987.2,4992
Exp/Cntr=0.3,0.1

Type RM Length L Ch R = 1,14192,451,451,451
BEGIN DESCRIPTION:
LIBERTY CREEK 16.0
END DESCRIPTION:
XS GIS Cut Line= 3
      2402503.62     13707046.92      2401749.30     13706572.44
      2401038.80     13706153.42
#Sta/Elev= 30
  3912.5  368.15  4029.0  367.98  4194.4  365.24  4343.5  363.88  4383.4  364.31
  4392.2  362.94  4398.1  363.46  4407.1  361.97  4434.6  361.66  4449.9  362.98
  4485.8  362.63  4762.7  363.18  4842.7  363.34  4878.3  362.29  4928.5  363.21
  4950.0  362.20  4971.4  359.66  4978.0  356.16  4978.5  355.66  4984.5  356.16
  4987.1  359.86  4994.4  361.94  5008.5  363.57  5052.8  361.90  5138.7  363.78
  5227.1  366.38  5424.2  375.22  5477.0  375.95  5498.4  377.46  5628.5  381.35
#Mann=8,-1,0
  3912.5    0.07       0  4343.5   0.035       0  4485.8    0.16       0
  4762.7    0.12       0  4978.0    0.07       0  4984.5    0.12       0
  5052.8    0.07       0  5138.7    0.05       0
Bank Sta=4978,4984.5
Exp/Cntr=0.3,0.1

Type RM Length L Ch R = 1,13741,731,731,731
BEGIN DESCRIPTION:
LIBERTY CREEK 15.0
END DESCRIPTION:
XS GIS Cut Line= 3
      2402546.22     13706973.94      2401974.39     13706262.18
      2401274.76     13705751.15
#Sta/Elev= 30
  3847.6  368.05  3947.9  368.06  4037.7  365.86  4167.0  363.24  4519.9  362.18
  4554.9  361.79  4587.9  362.20  4608.7  360.06  4637.5  359.88  4671.6  362.07
  4840.8  361.51  4972.2  361.42  4986.8  360.18  4998.2  355.67  4998.7  355.17
  5004.8  355.67  5007.7  355.83  5016.2  360.38  5066.4  360.21  5101.9  361.66
  5137.4  360.92  5168.1  362.51  5273.3  365.73  5353.2  370.30  5406.8  373.10
  5438.6  374.28  5526.2  372.27  5527.0  372.25  5566.1  371.25  5627.0  372.41
#Mann=14,-1,0
  3847.6    0.07       0  4037.7   0.035       0  4167.0    0.07       0
  4519.9   0.035       0  4554.9    0.07       0  4671.6   0.035       0
  4840.8    0.12       0  4998.2    0.07       0  5004.8    0.12       0
  5168.1    0.16       0  5353.2   0.035       0  5406.8    0.07       0
  5526.2    0.16       0  5527.0   0.035       0
Bank Sta=4998.2,5004.8
Exp/Cntr=0.3,0.1

Type RM Length L Ch R = 1,13010,328,328,328
BEGIN DESCRIPTION:
LIBERTY CREEK 14.0
END DESCRIPTION:
XS GIS Cut Line= 3
      2403175.01     13706475.01      2401974.39     13705848.51
      2401924.99     13705724.97
#Sta/Elev= 30
  3702.4  370.17  3771.4  368.46  3871.6  364.75  3948.0  363.68  3997.8  362.07
  4190.9  362.46  4221.3  363.67  4243.8  363.09  4273.6  363.93  4435.6  360.65
  4529.6  360.71  4596.6  360.84  4783.2  360.43  4897.3  360.22  4931.9  358.93
  4963.5  359.69  4991.3  358.79  5007.7  359.51  5013.3  355.37  5018.5  352.64
  5019.0  352.14  5025.8  352.64  5029.8  357.35  5035.4  359.73  5044.7  360.05
  5051.9  361.92  5055.0  363.82  5102.4  366.44  5121.0  367.84  5189.7  370.66
#Mann=8,-1,0
  3702.4    0.07       0  3771.4    0.16       0  4529.6    0.07       0
  4596.6    0.16       0  4783.2    0.12       0  5018.5    0.07       0
  5025.8    0.12       0  5102.4    0.16       0
Bank Sta=5018.5,5025.8
Exp/Cntr=0.3,0.1

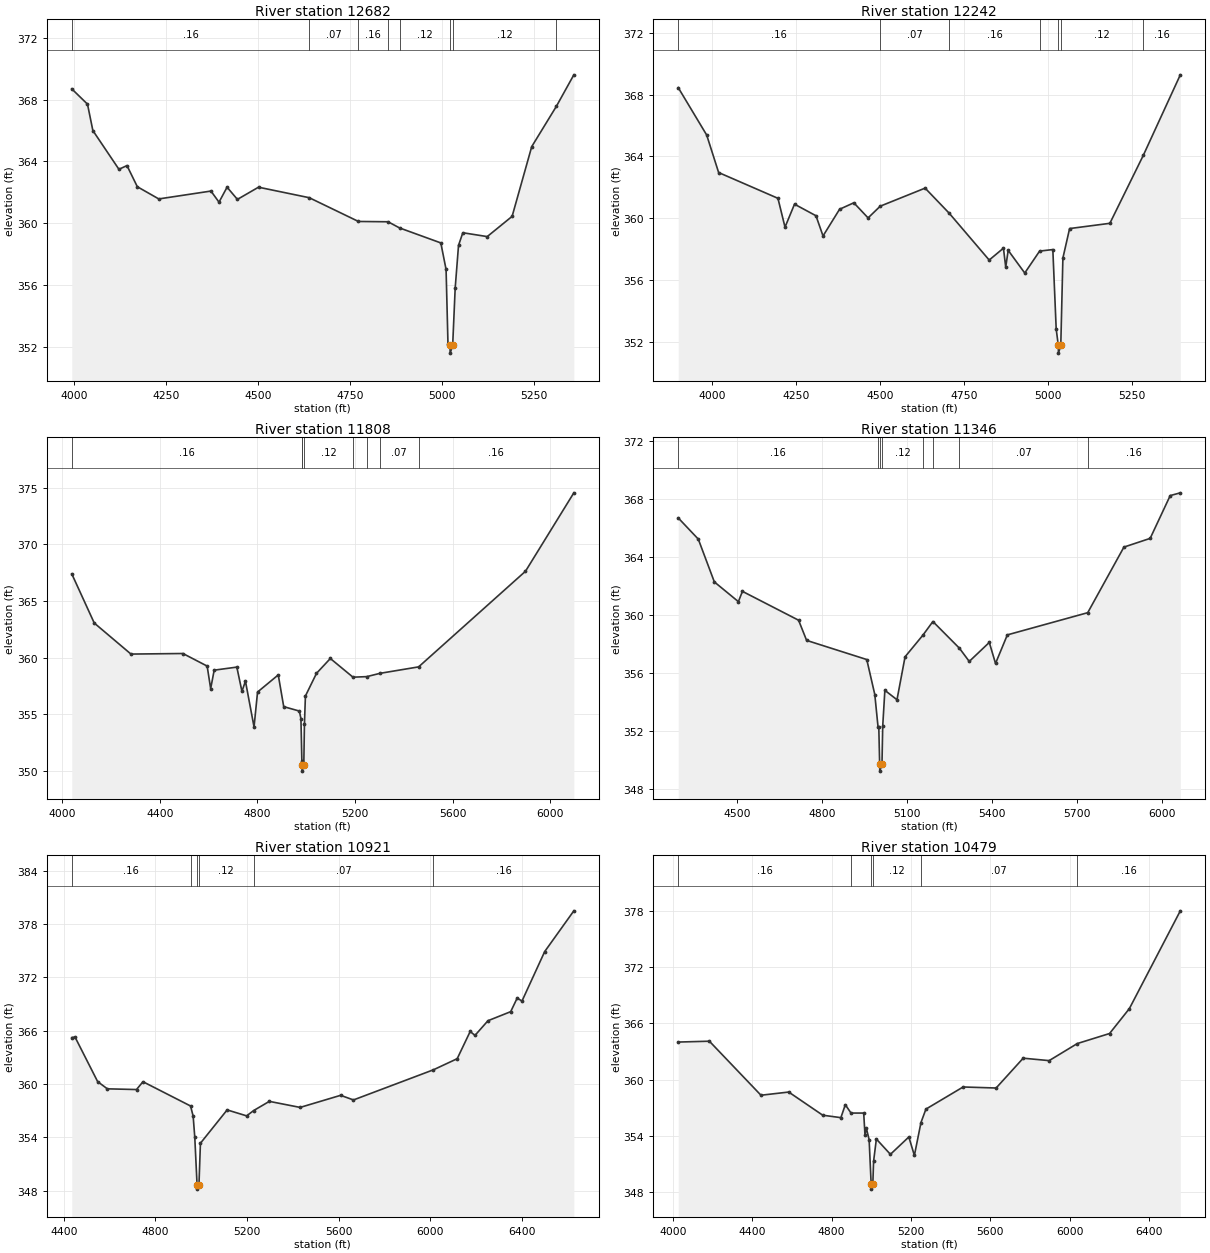
Type RM Length L Ch R = 1,12682,440,440,440
BEGIN DESCRIPTION:
LIBERTY CREEK 13.0
END DESCRIPTION:
XS GIS Cut Line= 3
      2403124.98     13706374.99      2402325.00     13705775.00
      2401974.99     13705675.00
#Sta/Elev= 30
  3993.3  368.70  4036.0  367.71  4050.6  366.00  4121.4  363.49  4143.3  363.73
  4171.4  362.36  4229.7  361.57  4371.4  362.08  4393.3  361.36  4415.2  362.33
  4443.3  361.54  4500.6  362.33  4638.4  361.65  4772.1  360.11  4852.6  360.09
  4883.9  359.69  4995.9  358.72  5010.2  357.00  5015.4  352.14  5020.8  352.08
  5021.3  351.58  5028.1  352.08  5034.9  355.78  5044.0  358.56  5055.7  359.38
  5122.0  359.13  5189.6  360.44  5242.9  364.96  5309.6  367.56  5357.3  369.61
#Mann=8,-1,0
  3993.3    0.16       0  4638.4    0.07       0  4772.1    0.16       0
  4852.6    0.07       0  4883.9    0.12       0  5020.8    0.07       0
  5028.1    0.12       0  5309.6    0.16       0
Bank Sta=5020.8,5028.1
Exp/Cntr=0.3,0.1

Type RM Length L Ch R = 1,12242,434,434,434
BEGIN DESCRIPTION:
LIBERTY CREEK 12.0
END DESCRIPTION:
XS GIS Cut Line= 3
      2403175.02     13706275.02      2402425.00     13705475.00
      2402025.01     13705475.00
#Sta/Elev= 30
  3898.8  368.46  3983.6  365.39  4019.2  362.96  4196.0  361.29  4217.1  359.42
  4245.4  360.91  4309.4  360.16  4330.4  358.85  4379.7  360.58  4422.2  361.00
  4464.7  360.02  4500.9  360.78  4634.7  361.95  4706.7  360.32  4825.7  357.29
  4868.2  358.06  4875.0  356.83  4882.3  357.92  4931.7  356.45  4976.0  357.87
  5015.4  357.97  5025.4  352.83  5031.7  351.76  5032.2  351.26  5039.1  351.76
  5045.4  357.42  5065.4  359.33  5185.4  359.67  5285.0  364.07  5395.4  369.29
#Mann=7,-1,0
  3898.8    0.16       0  4500.9    0.07       0  4706.7    0.16       0
  4976.0    0.12       0  5031.7    0.07       0  5039.1    0.12       0
  5285.0    0.16       0
Bank Sta=5031.7,5039.1
Exp/Cntr=0.3,0.1

Type RM Length L Ch R = 1,11808,462,462,462
BEGIN DESCRIPTION:
LIBERTY CREEK 11.0
END DESCRIPTION:
XS GIS Cut Line= 3
      2403325.01     13706125.01      2402725.00     13705375.00
      2401974.98     13704574.98
#Sta/Elev= 30
  4039.4  367.39  4131.5  363.05  4281.9  360.31  4494.8  360.36  4594.1  359.25
  4608.5  357.26  4622.9  358.89  4715.7  359.16  4736.6  357.02  4751.0  357.92
  4786.2  353.88  4800.6  356.96  4885.4  358.47  4907.8  355.67  4971.9  355.28
  4978.3  354.62  4982.2  350.87  4982.6  350.48  4983.1  349.98  4990.0  350.48
  4992.7  354.12  4996.7  356.61  5042.1  358.61  5098.8  359.92  5191.6  358.27
  5248.2  358.32  5302.2  358.61  5460.5  359.18  5898.4  367.62  6096.5  374.54
#Mann=8,-1,0
  4039.4    0.16       0  4982.2    0.12       0  4982.6    0.07       0
  4990.0    0.12       0  5191.6    0.07       0  5248.2    0.16       0
  5302.2    0.07       0  5460.5    0.16       0
Bank Sta=4982.6,4990
Exp/Cntr=0.3,0.1

Type RM Length L Ch R = 1,11346,425,425,425
BEGIN DESCRIPTION:
LIBERTY CREEK 10.0
END DESCRIPTION:
XS GIS Cut Line= 3
      2403625.01     13705775.01      2403125.00     13705275.00
      2402325.02     13704575.02
#Sta/Elev= 30
  4293.1  366.71  4363.8  365.25  4420.4  362.30  4505.2  360.94  4519.4  361.65
  4717.4  359.66  4745.7  358.27  4957.8  356.95  4986.1  354.54  4997.6  352.29
  5000.2  352.29  5003.2  349.76  5003.7  349.26  5011.4  349.76  5014.0  352.35
  5021.6  354.83  5064.3  354.18  5092.8  357.14  5155.7  358.63  5190.9  359.57
  5284.5  357.73  5319.1  356.82  5389.8  358.13  5411.7  356.68  5453.4  358.65
  5736.8  360.18  5864.4  364.70  5956.9  365.30  6027.6  368.25  6063.2  368.44
#Mann=8,-1,0
  4293.1    0.16       0  4997.6    0.12       0  5003.2    0.07       0
  5011.4    0.12       0  5155.7    0.07       0  5190.9    0.12       0
  5284.5    0.07       0  5736.8    0.16       0
Bank Sta=5003.2,5011.4
Exp/Cntr=0.3,0.1

Type RM Length L Ch R = 1,10921,442,442,442
BEGIN DESCRIPTION:
LIBERTY CREEK 9.0
END DESCRIPTION:
XS GIS Cut Line= 3
      2403874.97     13705574.97      2403475.00     13705175.00
      2402275.02     13704075.02
#Sta/Elev= 30
  4434.4  365.22  4448.5  365.29  4547.5  360.27  4589.9  359.46  4717.2  359.38
  4745.5  360.26  4953.4  357.53  4964.7  356.39  4971.8  354.02  4981.8  348.68
  4982.3  348.18  4990.1  348.68  4996.5  353.34  5113.2  357.09  5198.3  356.42
  5229.2  357.02  5297.6  358.05  5432.0  357.37  5609.0  358.73  5665.1  358.21
  6014.3  361.60  6118.3  362.85  6175.0  365.91  6196.0  365.47  6252.7  367.12
  6352.0  368.14  6380.4  369.67  6401.3  369.33  6500.6  374.90  6627.9  379.48
#Mann=6,-1,0
  4434.4    0.16       0  4953.4    0.12       0  4981.8    0.07       0
  4990.1    0.12       0  5229.2    0.07       0  6014.3    0.16       0
Bank Sta=4981.8,4990.1
Exp/Cntr=0.3,0.1

Type RM Length L Ch R = 1,10479,534,534,534
BEGIN DESCRIPTION:
A19630
END DESCRIPTION:
XS GIS Cut Line= 4
      2403933.23     13705672.10      2403939.32     13705100.26
      2403434.40     13704698.75      2402328.65     13703987.92
#Sta/Elev= 30
  4026.8  364.01  4183.9  364.10  4443.9  358.34  4583.9  358.68  4755.4  356.21
  4846.9  355.95  4869.2  357.33  4898.0  356.44  4961.9  356.44  4968.5  354.07
  4974.9  354.86  4989.3  353.60  4999.6  348.83  5000.1  348.33  5007.9  348.83
  5011.7  351.28  5025.8  353.67  5096.6  352.04  5189.5  353.89  5217.5  351.92
  5250.7  355.43  5275.6  356.86  5463.2  359.22  5629.6  359.11  5766.1  362.29
  5896.9  362.03  6038.9  363.85  6201.6  364.92  6301.3  367.57  6558.3  378.00
#Mann=6,-1,0
  4026.8    0.16       0  4898.0    0.12       0  4999.6    0.07       0
  5007.9    0.12       0  5250.7    0.07       0  6038.9    0.16       0
Bank Sta=4999.6,5007.9
Exp/Cntr=0.3,0.1

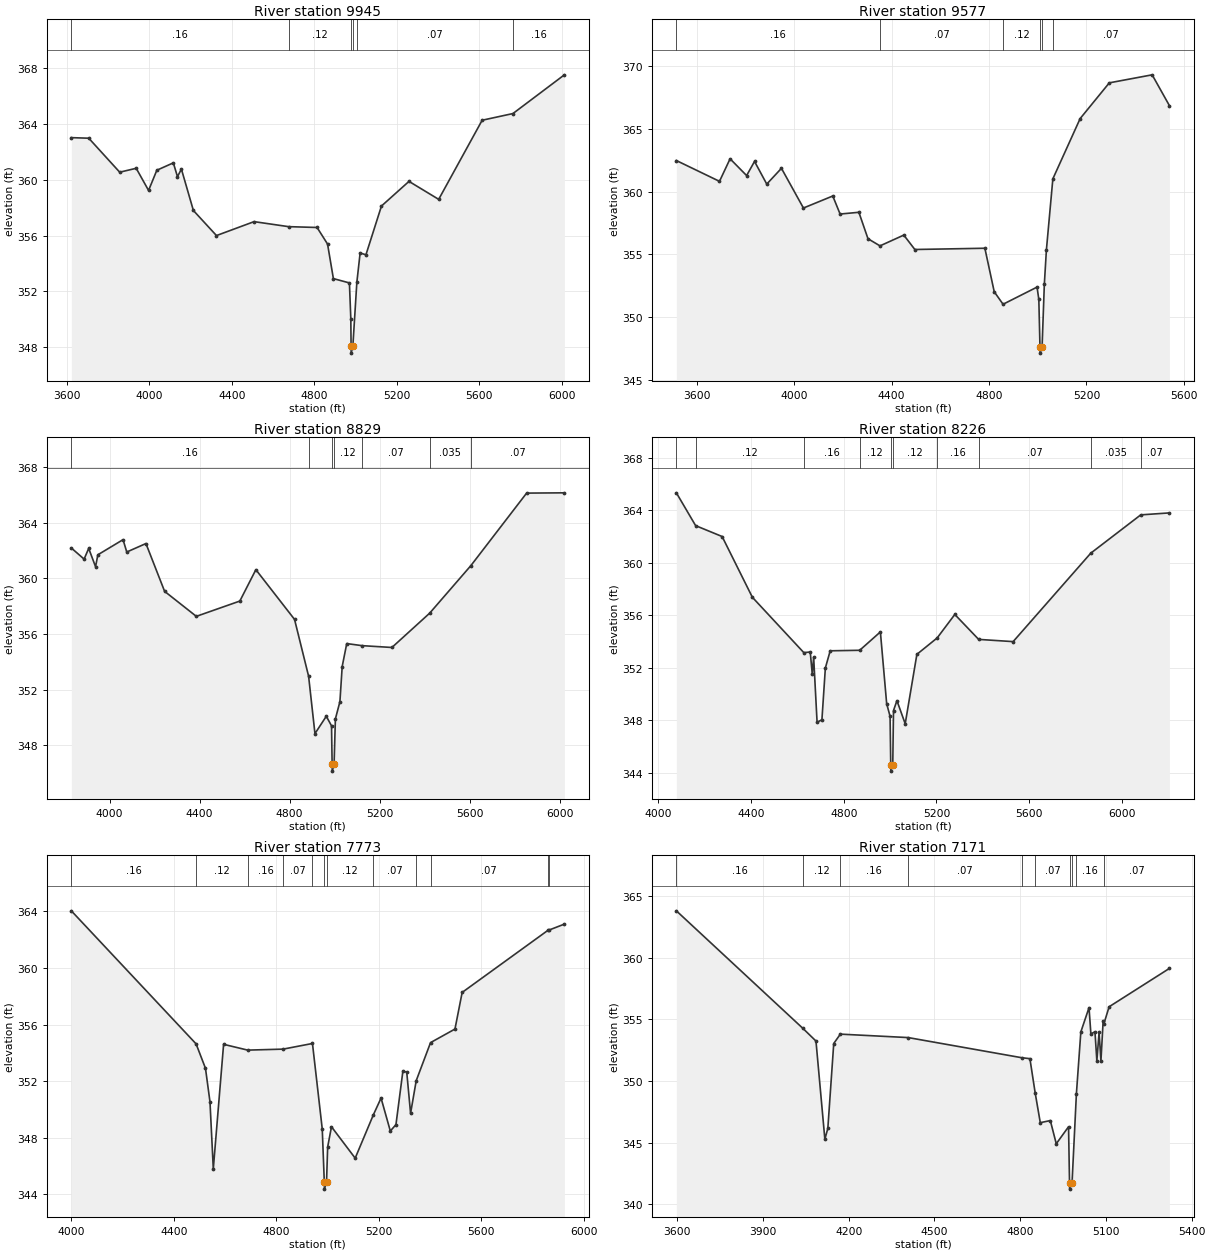
Type RM Length L Ch R = 1,9945,368,368,368
BEGIN DESCRIPTION:
A19629
END DESCRIPTION:
XS GIS Cut Line= 4
      2403969.73     13705629.54      2403994.07     13705100.26
      2403689.90     13704528.42      2402595.75     13703999.58
#Sta/Elev= 30
  3621.1  363.03  3705.7  362.99  3855.9  360.55  3936.0  360.83  3996.0  359.24
  4036.1  360.69  4116.2  361.22  4136.2  360.23  4155.4  360.77  4213.5  357.80
  4325.5  356.00  4508.0  357.00  4675.5  356.64  4813.8  356.58  4864.6  355.39
  4892.9  352.91  4970.7  352.60  4977.5  350.03  4978.8  348.06  4979.3  347.56
  4987.4  348.06  5006.8  352.65  5022.7  354.75  5050.9  354.62  5126.2  358.12
  5259.8  359.89  5403.9  358.60  5614.9  364.28  5764.3  364.76  6013.9  367.54
#Mann=6,-1,0
  3621.1    0.16       0  4675.5    0.12       0  4978.8    0.07       0
  4987.4    0.12       0  5006.8    0.07       0  5764.3    0.16       0
Bank Sta=4978.8,4987.4
Exp/Cntr=0.3,0.1

Type RM Length L Ch R = 1,9577,748,748,748
BEGIN DESCRIPTION:
A19628
END DESCRIPTION:
XS GIS Cut Line= 3
      2403994.07     13705574.74      2404060.99     13704826.51
      2403464.81     13703701.08
#Sta/Elev= 30
  3516.1  362.48  3693.2  360.82  3736.7  362.62  3804.6  361.28  3837.1  362.41
  3887.3  360.60  3947.6  361.86  4037.9  358.69  4158.4  359.65  4188.5  358.21
  4265.6  358.35  4303.0  356.24  4352.3  355.67  4450.1  356.53  4495.4  355.38
  4783.0  355.48  4821.4  352.01  4857.7  351.01  4997.3  352.38  5004.6  351.39
  5009.3  347.61  5009.8  347.11  5018.0  347.61  5027.2  352.60  5035.7  355.35
  5062.2  361.02  5174.3  365.83  5294.0  368.68  5470.0  369.32  5540.9  366.86
#Mann=6,-1,0
  3516.1    0.16       0  4352.3    0.07       0  4857.7    0.12       0
  5009.3    0.07       0  5018.0    0.12       0  5062.2    0.07       0
Bank Sta=5009.3,5018
Exp/Cntr=0.3,0.1

Type RM Length L Ch R = 1,8829,603,603,603
BEGIN DESCRIPTION:
A19627
END DESCRIPTION:
XS GIS Cut Line= 4
      2404024.48     13705580.85      2404182.65     13704735.25
      2404243.49     13704260.75      2403848.09     13703506.45
#Sta/Elev= 30
  3830.0  362.19  3886.8  361.39  3907.2  362.16  3937.7  360.84  3947.9  361.70
  4059.8  362.79  4076.3  361.90  4161.5  362.51  4244.4  359.07  4385.3  357.27
  4578.6  358.37  4649.8  360.63  4821.6  357.05  4884.1  352.96  4912.3  348.83
  4962.7  350.08  4985.9  349.39  4988.6  346.63  4989.1  346.13  4997.3  346.63
  5003.1  349.89  5023.2  351.13  5033.3  353.66  5053.5  355.31  5122.2  355.16
  5254.2  355.03  5422.0  357.50  5604.9  360.92  5852.6  366.14  6020.3  366.16
#Mann=7,-1,0
  3830.0    0.16       0  4884.1    0.12       0  4988.6    0.07       0
  4997.3    0.12       0  5122.2    0.07       0  5422.0   0.035       0
  5604.9    0.07       0
Bank Sta=4988.6,4997.3
Exp/Cntr=0.3,0.1

Type RM Length L Ch R = 1,8226,453,453,453
BEGIN DESCRIPTION:
A19626
END DESCRIPTION:
XS GIS Cut Line= 3
      2405192.47     13705343.56      2404468.57     13704321.59
      2404134.00     13703512.52
#Sta/Elev= 30
  4077.8  365.32  4160.9  362.82  4275.3  361.99  4405.8  357.36  4627.9  353.14
  4655.6  353.19  4664.2  351.51  4670.3  352.79  4685.1  347.83  4706.0  348.03
  4720.8  351.97  4741.7  353.28  4869.0  353.32  4958.3  354.72  4985.4  349.25
  5000.1  348.29  5003.0  344.61  5003.5  344.11  5011.7  344.61  5014.9  348.73
  5029.7  349.48  5065.4  347.72  5115.8  353.01  5203.3  354.26  5279.5  356.05
  5382.4  354.15  5531.2  353.98  5866.2  360.72  6081.9  363.64  6205.7  363.79
#Mann=10,-1,0
  4077.8    0.16       0  4160.9    0.12       0  4627.9    0.16       0
  4869.0    0.12       0  5003.0    0.07       0  5011.7    0.12       0
  5203.3    0.16       0  5382.4    0.07       0  5866.2   0.035       0
  6081.9    0.07       0
Bank Sta=5003,5011.7
Exp/Cntr=0.3,0.1

Type RM Length L Ch R = 1,7773,602,602,602
BEGIN DESCRIPTION:
A19625
END DESCRIPTION:
XS GIS Cut Line= 4
      2405229.01     13705173.30      2404949.16     13704406.75
      2404651.07     13704199.92      2404237.63     13703579.75
#Sta/Elev= 30
  4000.1  364.04  4487.1  354.63  4523.7  352.90  4541.2  350.54  4554.2  345.80
  4594.4  354.60  4688.5  354.19  4826.6  354.26  4941.2  354.66  4979.4  348.61
  4987.4  344.86  4987.9  344.36  4996.1  344.86  5000.5  347.34  5015.4  348.77
  5107.9  346.55  5179.0  349.62  5208.9  350.80  5245.0  348.47  5267.0  348.92
  5294.0  352.69  5309.1  352.64  5324.1  349.72  5346.1  352.03  5402.0  354.72
  5497.3  355.68  5525.4  358.27  5859.3  362.65  5864.4  362.68  5924.3  363.10
#Mann=12,-1,0
  4000.1    0.16       0  4487.1    0.12       0  4688.5    0.16       0
  4826.6    0.07       0  4941.2    0.12       0  4987.4    0.07       0
  4996.1    0.12       0  5179.0    0.07       0  5346.1    0.16       0
  5402.0    0.07       0  5859.3   0.035       0  5864.4    0.07       0
Bank Sta=4987.4,4996.1
Exp/Cntr=0.3,0.1

Type RM Length L Ch R = 1,7171,447,447,447
BEGIN DESCRIPTION:
A19624
END DESCRIPTION:
XS GIS Cut Line= 3
      2405241.16     13705106.34      2404973.49     13704120.83
      2404523.54     13703579.67
#Sta/Elev= 30
  3597.2  363.80  4039.7  354.27  4085.6  353.24  4116.7  345.28  4127.1  346.15
  4147.8  353.04  4170.9  353.80  4408.5  353.52  4804.8  351.89  4834.1  351.81
  4852.4  349.05  4870.4  346.62  4905.5  346.79  4926.3  344.91  4969.3  346.29
  4972.7  341.73  4973.2  341.23  4981.5  341.73  4996.8  348.98  5012.3  353.98
  5040.9  355.95  5047.4  353.82  5061.7  353.99  5068.3  351.64  5076.1  353.94
  5082.6  351.64  5090.4  354.89  5093.1  354.65  5111.2  356.02  5322.2  359.13
#Mann=10,-1,0
  3597.2    0.16       0  4039.7    0.12       0  4170.9    0.16       0
  4408.5    0.07       0  4804.8    0.16       0  4852.4    0.07       0
  4972.7    0.07       0  4981.5    0.07       0  4996.8    0.16       0
  5093.1    0.07       0
Bank Sta=4972.7,4981.5
Exp/Cntr=0.3,0.1

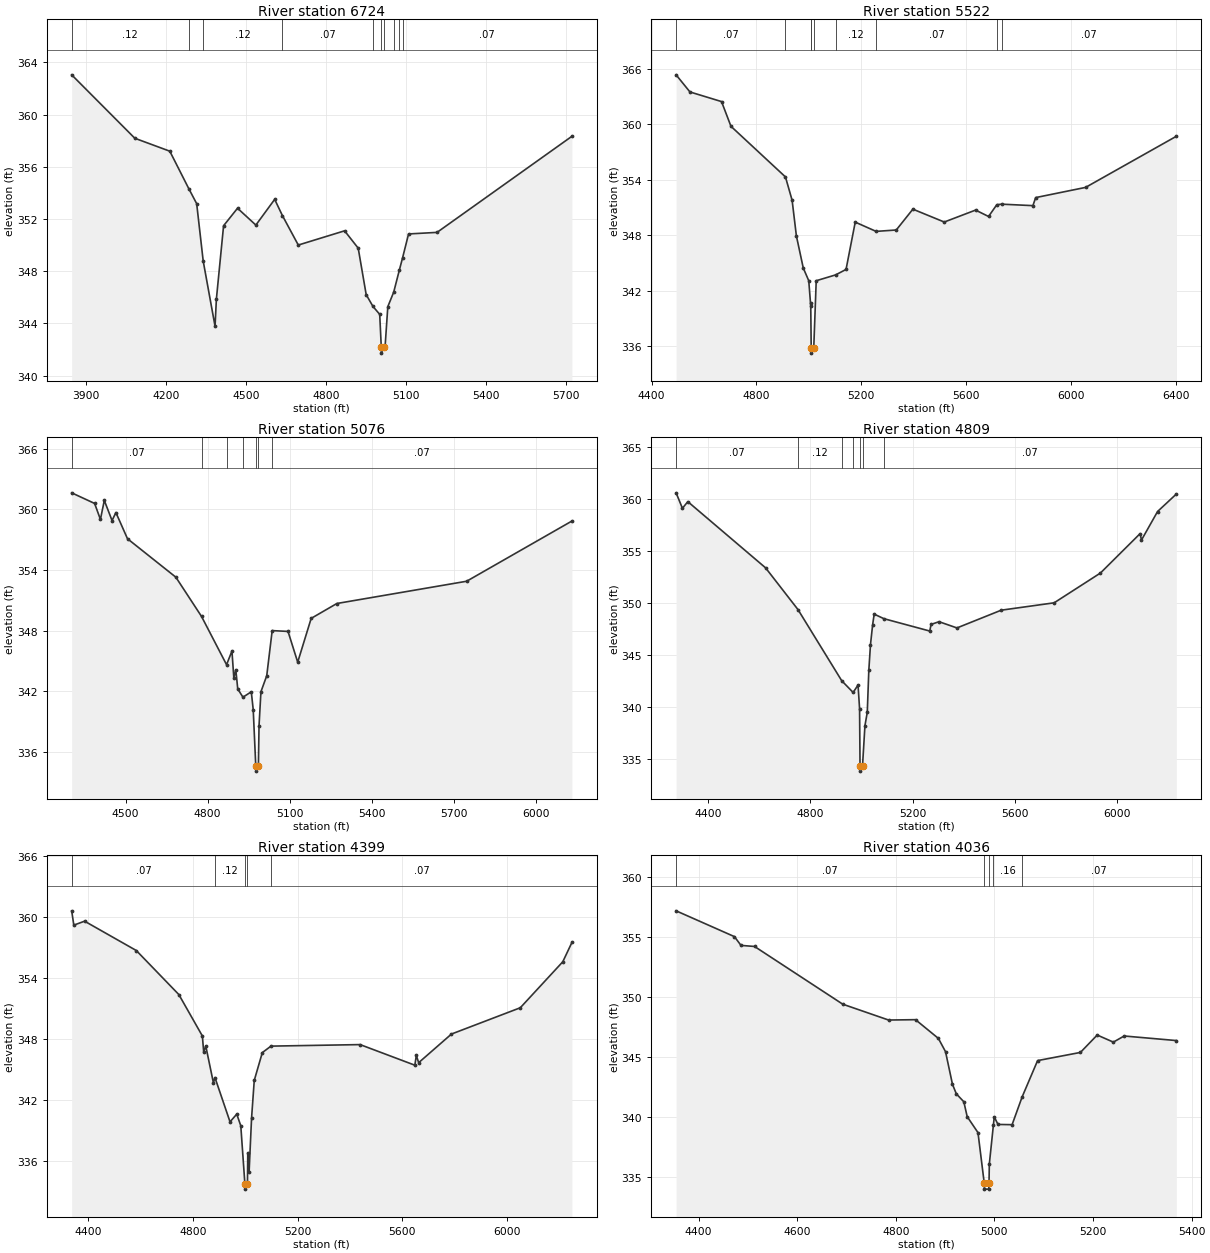
Type RM Length L Ch R = 1,6724,1202,1202,1202
BEGIN DESCRIPTION:
A19623
END DESCRIPTION:
XS GIS Cut Line= 4
      2405259.41     13705069.86      2405125.58     13704035.67
      2405162.08     13703816.66      2404598.28     13703581.81
#Sta/Elev= 30
  3845.0  363.05  4081.8  358.19  4212.9  357.20  4284.1  354.33  4313.7  353.18
  4338.2  348.78  4382.6  343.79  4387.6  345.87  4414.6  351.49  4466.9  352.83
  4535.6  351.54  4606.2  353.51  4635.1  352.27  4694.7  350.01  4868.3  351.10
  4919.4  349.77  4949.3  346.21  4974.6  345.31  5000.0  344.70  5005.8  342.23
  5006.3  341.73  5014.6  342.23  5020.3  342.27  5030.4  345.29  5052.6  346.41
  5074.0  348.12  5085.5  349.01  5108.2  350.86  5215.0  350.98  5720.6  358.34
#Mann=10,-1,0
  3845.0    0.12       0  4284.1     0.1       0  4338.2    0.12       0
  4635.1    0.07       0  4974.6    0.12       0  5005.8    0.05       0
  5014.6    0.12       0  5052.6     0.1       0  5074.0    0.12       0
  5085.5    0.07       0
Bank Sta=5005.8,5014.6
Exp/Cntr=0.3,0.1

Type RM Length L Ch R = 1,5522,446,446,446
BEGIN DESCRIPTION:
A19622
END DESCRIPTION:
XS GIS Cut Line= 4
      2405971.19     13704644.03      2405508.83     13704120.83
      2405417.58     13703822.75      2404567.60     13703529.50
#Sta/Elev= 30
  4493.7  365.34  4546.6  363.49  4667.1  362.45  4703.1  359.78  4911.1  354.31
  4936.5  351.79  4952.8  347.94  4979.1  344.47  5000.0  343.10  5006.7  340.68
  5007.6  340.35  5009.4  335.78  5009.9  335.28  5019.0  335.78  5028.5  343.10
  5102.5  343.73  5142.3  344.32  5177.4  349.43  5257.0  348.43  5334.0  348.58
  5397.4  350.83  5517.2  349.44  5636.7  350.73  5686.2  350.04  5717.7  351.31
  5736.1  351.37  5855.5  351.21  5866.1  352.08  6056.5  353.18  6402.8  358.70
#Mann=9,-1,0
  4493.7    0.07       0  4911.1    0.12       0  5006.7     0.1       0
  5009.4    0.05       0  5019.0     0.1       0  5102.5    0.12       0
  5257.0    0.07       0  5717.7    0.12       0  5736.1    0.07       0
Bank Sta=5009.4,5019
Exp/Cntr=0.3,0.1

Type RM Length L Ch R = 1,5076,267,267,267
BEGIN DESCRIPTION:
A19621
END DESCRIPTION:
XS GIS Cut Line= 3
      2406074.55     13704364.14      2405484.50     13703774.08
      2404531.51     13703489.96
#Sta/Elev= 30
  4302.9  361.62  4386.8  360.57  4408.0  358.99  4422.2  360.87  4450.5  358.88
  4464.6  359.67  4507.0  357.08  4683.8  353.28  4777.7  349.40  4869.2  344.63
  4888.9  345.98  4895.9  343.28  4903.0  344.14  4910.1  342.23  4929.1  341.42
  4959.6  341.95  4966.7  340.18  4976.0  334.61  4976.5  334.11  4985.6  334.61
  4987.9  338.59  4994.9  341.96  5016.1  343.54  5036.0  348.00  5093.9  347.92
  5129.3  344.88  5178.6  349.21  5272.5  350.68  5747.0  352.88  6131.8  358.83
#Mann=7,-1,0
  4302.9    0.07       0  4777.7     0.1       0  4869.2    0.12       0
  4929.1     0.1       0  4976.0    0.05       0  4985.6     0.1       0
  5036.0    0.07       0
Bank Sta=4976,4985.6
Exp/Cntr=0.3,0.1

Type RM Length L Ch R = 1,4809,410,410,410
BEGIN DESCRIPTION:
A19620
END DESCRIPTION:
XS GIS Cut Line= 3
      2406104.98     13704248.56      2405641.25     13703547.16
      2405273.54     13702495.95
#Sta/Elev= 30
  4275.3  360.61  4300.0  359.12  4321.1  359.76  4625.0  353.38  4751.5  349.36
  4922.5  342.50  4967.1  341.37  4986.2  342.09  4992.2  339.82  4994.0  334.29
  4994.5  333.79  5003.7  334.29  5013.2  338.18  5022.3  339.45  5028.3  343.49
  5034.8  345.97  5043.3  347.91  5049.3  348.92  5087.4  348.48  5266.4  347.29
  5271.7  347.93  5302.7  348.19  5372.7  347.59  5545.7  349.30  5752.4  350.01
  5933.3  352.88  6088.4  356.68  6093.7  356.06  6156.6  358.81  6229.8  360.49
#Mann=7,-1,0
  4275.3    0.07       0  4751.5    0.12       0  4922.5     0.1       0
  4967.1    0.12       0  4994.0    0.05       0  5003.7    0.12       0
  5087.4    0.07       0
Bank Sta=4994,5003.7
Exp/Cntr=0.3,0.1

Type RM Length L Ch R = 1,4399,363,363,363
BEGIN DESCRIPTION:
A19619
END DESCRIPTION:
XS GIS Cut Line= 3
      2406226.68     13704272.96      2406009.56     13703365.53
      2405573.03     13702491.63
#Sta/Elev= 30
  4337.4  360.64  4345.6  359.23  4386.7  359.62  4584.1  356.73  4746.6  352.39
  4836.4  348.31  4841.5  346.72  4849.4  347.32  4878.5  343.70  4884.5  344.21
  4942.0  339.85  4967.7  340.61  4983.1  339.46  4998.8  333.72  4999.3  333.22
  5008.5  333.72  5009.8  336.81  5014.9  334.94  5024.2  340.20  5034.5  343.93
  5065.3  346.67  5098.3  347.31  5438.7  347.46  5647.7  345.43  5653.3  346.39
  5662.3  345.68  5787.5  348.50  6050.3  351.09  6212.5  355.62  6247.3  357.52
#Mann=5,-1,0
  4337.4    0.07       0  4884.5    0.12       0  4998.8    0.05       0
  5008.5    0.12       0  5098.3    0.07       0
Bank Sta=4998.8,5008.5
Exp/Cntr=0.3,0.1

Type RM Length L Ch R = 1,4036,366,366,366
BEGIN DESCRIPTION:
A19618
END DESCRIPTION:
XS GIS Cut Line= 3
      2406330.10     13704242.46      2406457.84     13703743.66
      2406251.59     13703288.72
#Sta/Elev= 30
  4354.5  357.16  4472.8  355.01  4486.1  354.28  4513.6  354.19  4692.5  349.38
  4785.4  348.06  4840.0  348.09  4886.4  346.53  4900.9  345.42  4915.0  342.70
  4922.8  341.91  4938.0  341.25  4944.8  340.01  4966.7  338.68  4979.4  334.47
  4979.9  333.97  4988.6  333.97  4989.1  334.47  4989.7  336.06  4998.0  339.32
  4999.7  339.99  5007.3  339.36  5035.9  339.34  5056.3  341.66  5087.6  344.68
  5174.4  345.36  5208.5  346.81  5241.2  346.22  5263.2  346.73  5368.9  346.35
#Mann=5,-1,0
  4354.5    0.07       0  4979.4    0.07       0  4989.1    0.07       0
  4998.0    0.16       0  5056.3    0.07       0
Bank Sta=4979.4,4989.1
Exp/Cntr=0.3,0.1