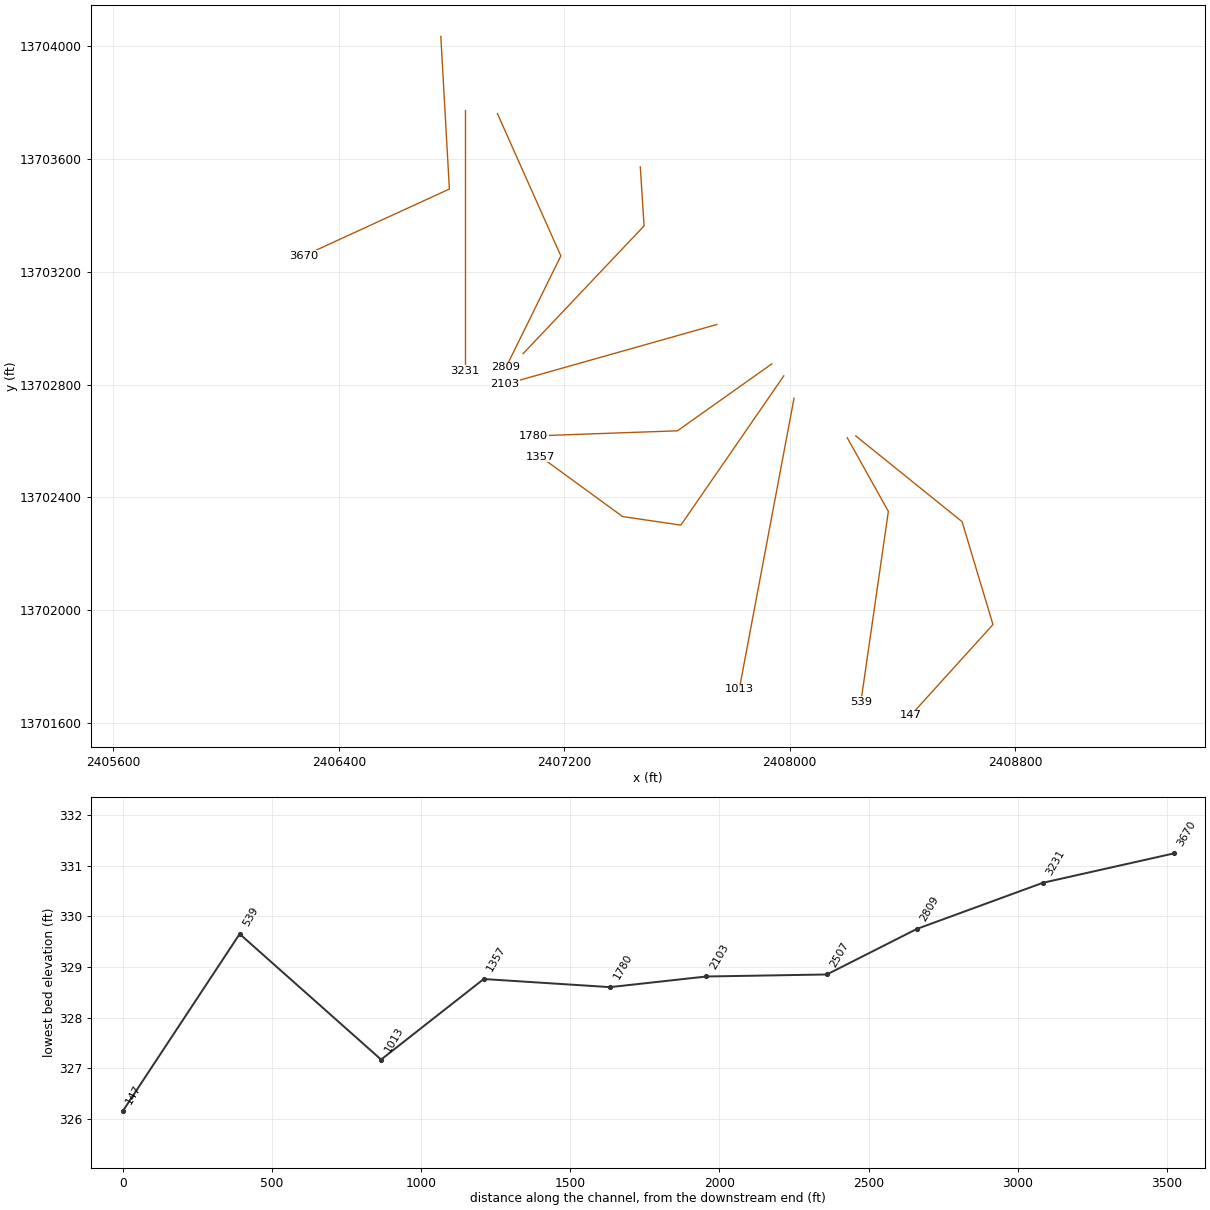
HEC-RAS study LIBERTY CREEK.prj: LIBERTY CREEK Base Level Engineering

--- LIBERTY CREEK.g01 (geometry) --- (continued)

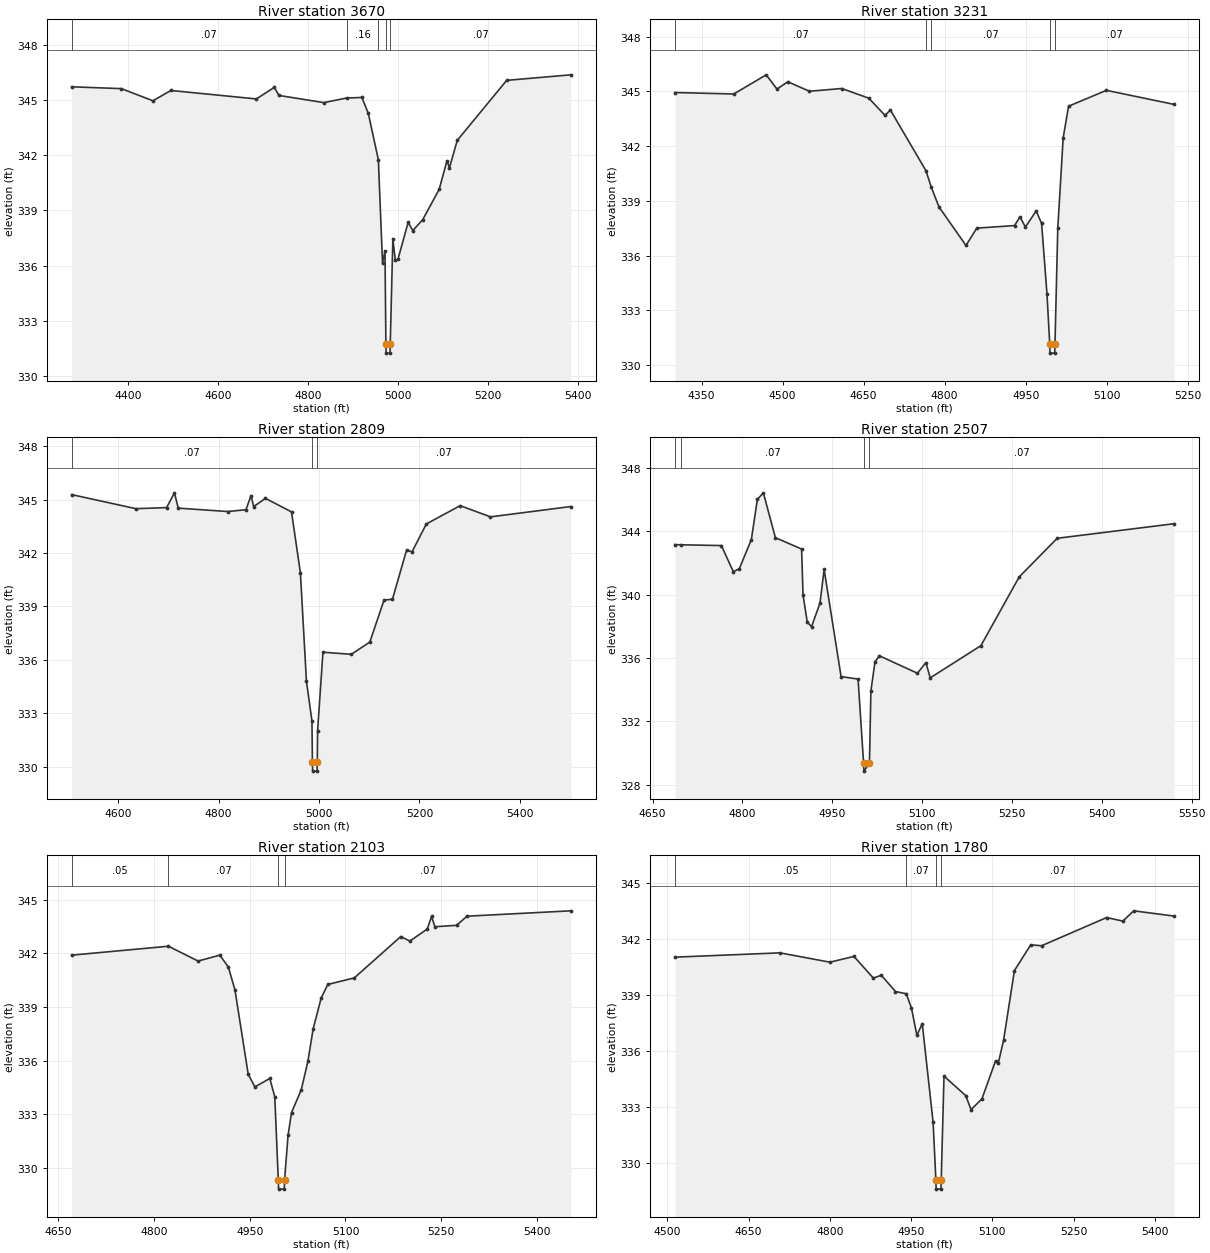
Type RM Length L Ch R = 1,3670,439,439,439
BEGIN DESCRIPTION:
A19617
END DESCRIPTION:
XS GIS Cut Line= 3
      2406762.01     13704035.63      2406792.42     13703494.25
      2406275.30     13703256.98
#Sta/Elev= 30
  4273.5  345.71  4384.3  345.61  4454.4  344.95  4494.5  345.51  4684.8  345.05
  4724.8  345.68  4734.9  345.24  4834.9  344.85  4885.7  345.10  4919.6  345.13
  4933.9  344.27  4956.3  341.75  4965.6  336.14  4971.1  336.79  4973.1  331.74
  4973.6  331.24  4982.3  331.24  4982.8  331.74  4988.6  337.44  4994.1  336.28
  4999.9  336.33  5022.6  338.34  5033.0  337.90  5055.0  338.49  5091.6  340.13
  5109.1  341.69  5114.6  341.31  5132.0  342.80  5242.0  346.06  5384.7  346.36
#Mann=5,-1,0
  4273.5    0.07       0  4885.7    0.16       0  4956.3    0.07       0
  4973.1    0.07       0  4982.8    0.07       0
Bank Sta=4973.1,4982.8
Exp/Cntr=0.3,0.1

Type RM Length L Ch R = 1,3231,422,422,422
BEGIN DESCRIPTION:
A19616
END DESCRIPTION:
XS GIS Cut Line= 2
      2406847.17     13703774.08      2406847.17     13702849.68
#Sta/Elev= 30
  4300.4  344.94  4409.5  344.86  4469.5  345.91  4489.5  345.13  4509.5  345.53
  4549.5  345.01  4609.5  345.16  4659.5  344.63  4689.5  343.69  4699.5  343.98
  4765.3  340.66  4775.0  339.77  4789.5  338.67  4839.5  336.56  4859.5  337.51
  4929.5  337.65  4939.5  338.13  4949.5  337.57  4969.5  338.45  4979.5  337.77
  4989.5  333.90  4994.6  331.16  4995.1  330.66  5003.8  330.66  5004.3  331.16
  5009.5  337.52  5019.5  342.46  5029.5  344.19  5099.5  345.06  5224.8  344.29
#Mann=5,-1,0
  4300.4    0.07       0  4765.3    0.16       0  4775.0    0.07       0
  4994.6    0.07       0  5004.3    0.07       0
Bank Sta=4994.6,5004.3
Exp/Cntr=0.3,0.1

Type RM Length L Ch R = 1,2809,302,302,302
BEGIN DESCRIPTION:
A19615
END DESCRIPTION:
XS GIS Cut Line= 3
      2406962.75     13703761.92      2407187.84     13703256.99
      2406993.16     13702861.54
#Sta/Elev= 30
  4507.6  345.28  4635.6  344.49  4696.6  344.55  4712.3  345.38  4719.8  344.52
  4818.2  344.33  4854.6  344.43  4864.6  345.22  4870.1  344.61  4893.4  345.07
  4945.3  344.31  4963.0  340.88  4975.0  334.80  4986.0  332.57  4986.9  330.25
  4987.4  329.75  4996.1  329.75  4996.6  330.25  4997.2  332.02  5007.9  336.43
  5064.3  336.31  5101.2  337.00  5129.5  339.36  5146.2  339.40  5174.2  342.15
  5185.3  342.07  5213.6  343.63  5281.0  344.66  5341.3  344.03  5501.2  344.61
#Mann=3,-1,0
  4507.6    0.07       0  4986.9    0.07       0  4996.6    0.07       0
Bank Sta=4986.9,4996.6
Exp/Cntr=0.3,0.1

Type RM Length L Ch R = 1,2507,404,404,404
BEGIN DESCRIPTION:
A19614
END DESCRIPTION:
XS GIS Cut Line= 3
      2407469.74     13703572.41      2407483.13     13703363.47
      2407054.02     13702910.25
#Sta/Elev= 30
  4687.1  343.15  4697.4  343.14  4764.7  343.09  4784.7  341.44  4794.7  341.63
  4814.8  343.47  4824.8  346.00  4834.8  346.42  4854.9  343.59  4898.7  342.87
  4901.1  339.98  4908.1  338.26  4915.3  337.97  4929.4  339.46  4936.3  341.58
  4964.6  334.82  4993.0  334.66  5002.2  329.35  5002.7  328.85  5012.0  329.35
  5014.4  333.92  5021.3  335.76  5028.6  336.13  5092.1  335.03  5106.2  335.70
  5113.5  334.74  5198.1  336.77  5262.0  341.11  5325.5  343.55  5520.6  344.47
#Mann=4,-1,0
  4687.1   0.035       0  4697.4    0.07       0  5002.2    0.05       0
  5012.0    0.07       0
Bank Sta=5002.2,5012
Exp/Cntr=0.3,0.1

Type RM Length L Ch R = 1,2103,323,323,323
BEGIN DESCRIPTION:
A19613
END DESCRIPTION:
XS GIS Cut Line= 2
      2407741.41     13703013.65      2406988.52     13702801.14
#Sta/Elev= 30
  4670.8  341.90  4822.5  342.40  4869.0  341.57  4903.0  341.90  4916.4  341.24
  4926.8  339.95  4947.6  335.23  4958.0  334.53  4981.4  335.00  4989.2  333.97
  4994.7  329.31  4995.2  328.81  5004.0  328.81  5004.5  329.31  5010.0  331.82
  5015.4  333.09  5030.7  334.37  5041.1  335.96  5049.3  337.77  5061.9  339.50
  5072.3  340.26  5113.9  340.63  5186.6  342.94  5200.9  342.69  5228.2  343.36
  5234.9  344.07  5240.1  343.49  5274.1  343.57  5290.5  344.08  5453.1  344.38
#Mann=4,-1,0
  4670.8    0.05       0  4822.5    0.07       0  4994.7    0.07       0
  5004.5    0.07       0
Bank Sta=4994.7,5004.5
Exp/Cntr=0.3,0.1

Type RM Length L Ch R = 1,1780,423,423,423
BEGIN DESCRIPTION:
A19612
END DESCRIPTION:
XS GIS Cut Line= 3
      2407936.12     13702873.76      2407601.51     13702636.49
      2407090.53     13702618.24
#Sta/Elev= 30
  4514.0  341.02  4708.0  341.25  4800.3  340.75  4844.6  341.06  4880.3  339.90
  4895.1  340.05  4921.2  339.18  4941.1  339.06  4950.7  338.30  4960.7  336.84
  4970.7  337.45  4990.7  332.18  4995.8  329.10  4996.3  328.60  5005.2  328.60
  5005.7  329.10  5010.8  334.65  5050.8  333.61  5060.8  332.86  5080.8  333.43
  5105.9  335.46  5110.9  335.33  5120.8  336.57  5140.8  340.30  5170.9  341.68
  5190.9  341.63  5311.0  343.14  5341.0  342.95  5361.0  343.50  5435.5  343.22
#Mann=4,-1,0
  4514.0    0.05       0  4941.1    0.07       0  4995.8    0.07       0
  5005.7    0.07       0
Bank Sta=4995.8,5005.7
Exp/Cntr=0.3,0.1

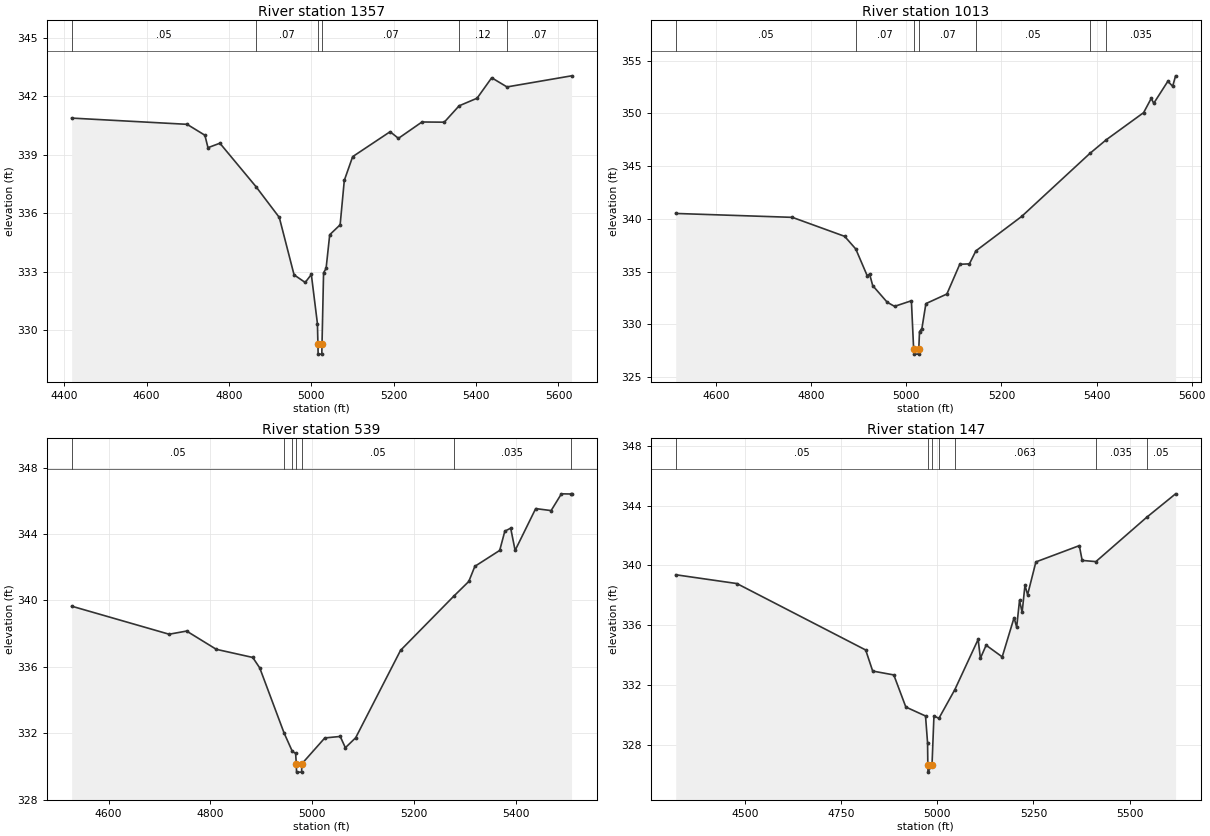
Type RM Length L Ch R = 1,1357,344,344,344
BEGIN DESCRIPTION:
A19611
END DESCRIPTION:
XS GIS Cut Line= 4
      2407978.71     13702831.20      2407613.68     13702301.90
      2407406.84     13702332.32      2407114.85     13702545.24
#Sta/Elev= 30
  4418.3  340.88  4698.5  340.56  4741.7  340.00  4749.2  339.36  4778.1  339.59
  4865.7  337.36  4922.3  335.78  4958.2  332.83  4985.2  332.44  5000.1  332.85
  5014.9  330.32  5016.1  329.26  5016.6  328.76  5025.5  328.76  5026.0  329.26
  5029.8  332.94  5035.9  333.16  5044.7  334.89  5070.0  335.40  5080.1  337.68
  5100.4  338.90  5191.3  340.18  5211.5  339.84  5268.7  340.68  5322.8  340.67
  5358.8  341.51  5402.4  341.90  5437.9  342.95  5475.0  342.48  5631.7  343.05
#Mann=6,-1,0
  4418.3    0.05       0  4865.7    0.07       0  5016.1    0.07       0
  5026.0    0.07       0  5358.8    0.12       0  5475.0    0.07       0
Bank Sta=5016.1,5026
Exp/Cntr=0.3,0.1

Type RM Length L Ch R = 1,1013,474,474,474
BEGIN DESCRIPTION:
A19610
END DESCRIPTION:
XS GIS Cut Line= 2
      2408015.19     13702752.11      2407820.71     13701718.96
#Sta/Elev= 30
  4514.9  340.51  4760.2  340.14  4870.2  338.34  4893.6  337.14  4917.6  334.61
  4922.7  334.76  4929.2  333.67  4959.7  332.09  4975.2  331.70  5010.6  332.23
  5015.3  327.67  5015.8  327.17  5025.6  327.17  5026.1  327.67  5027.7  329.31
  5032.7  329.60  5041.1  331.96  5085.2  332.87  5112.3  335.69  5132.6  335.73
  5146.2  336.96  5242.6  340.23  5385.9  346.20  5420.8  347.51  5499.0  350.07
  5515.1  351.43  5520.2  350.95  5549.9  353.04  5560.1  352.57  5566.2  353.56
#Mann=7,-1,0
  4514.9    0.05       0  4893.6    0.07       0  5015.3    0.07       0
  5026.1    0.07       0  5146.2    0.05       0  5385.9    0.07       0
  5420.8   0.035       0
Bank Sta=5015.3,5026.1
Exp/Cntr=0.3,0.1

Type RM Length L Ch R = 1,539,392,392,392
BEGIN DESCRIPTION:
A19609
END DESCRIPTION:
XS GIS Cut Line= 3
      2408203.77     13702612.15      2408349.77     13702350.57
      2408252.43     13701675.31
#Sta/Elev= 30
  4527.4  339.65  4718.8  337.96  4753.2  338.15  4811.5  337.05  4883.1  336.56
  4896.8  335.93  4944.6  332.01  4960.8  330.90  4967.3  330.78  4968.6  330.15
  4969.1  329.65  4979.0  329.65  4979.5  330.15  5024.6  331.71  5054.9  331.80
  5065.0  331.12  5085.2  331.72  5173.4  336.99  5277.5  340.24  5307.4  341.14
  5319.3  342.05  5368.1  343.01  5378.2  344.17  5389.7  344.35  5398.4  343.01
  5438.8  345.53  5469.1  345.41  5489.3  346.42  5507.9  346.41  5509.2  346.42
#Mann=7,-1,0
  4527.4    0.05       0  4944.6    0.07       0  4960.8    0.05       0
  4968.6    0.05       0  4979.5    0.05       0  5277.5   0.035       0
  5507.9    0.05       0
Bank Sta=4968.6,4979.5
Exp/Cntr=0.3,0.1

Type RM Length L Ch R = 1,147,0,0,0
BEGIN DESCRIPTION:
A19608
END DESCRIPTION:
XS GIS Cut Line= 4
      2408234.17     13702618.25      2408611.35     13702314.07
      2408720.85     13701949.07      2408429.41     13701627.26
#Sta/Elev= 30
  4319.9  339.37  4479.0  338.78  4813.9  334.33  4832.1  332.92  4887.0  332.66
  4918.3  330.51  4969.5  329.91  4974.8  328.11  4975.5  326.65  4976.0  326.15
  4986.4  326.65  4991.4  329.92  5004.2  329.75  5045.8  331.68  5106.3  335.04
  5112.2  333.78  5127.1  334.65  5168.9  333.87  5199.7  336.49  5206.5  335.86
  5213.9  337.65  5220.7  336.86  5228.1  338.67  5234.9  338.03  5256.5  340.23
  5369.4  341.32  5376.8  340.33  5412.5  340.25  5544.2  343.21  5619.7  344.79
#Mann=7,-1,0
  4319.9    0.05       0  4975.5    0.05       0  4986.4    0.05       0
  5004.2    0.07       0  5045.8   0.063       0  5412.5   0.035       0
  5544.2    0.05       0
Bank Sta=4975.5,4986.4
Exp/Cntr=0.3,0.1

Chan Stop Cuts=-1