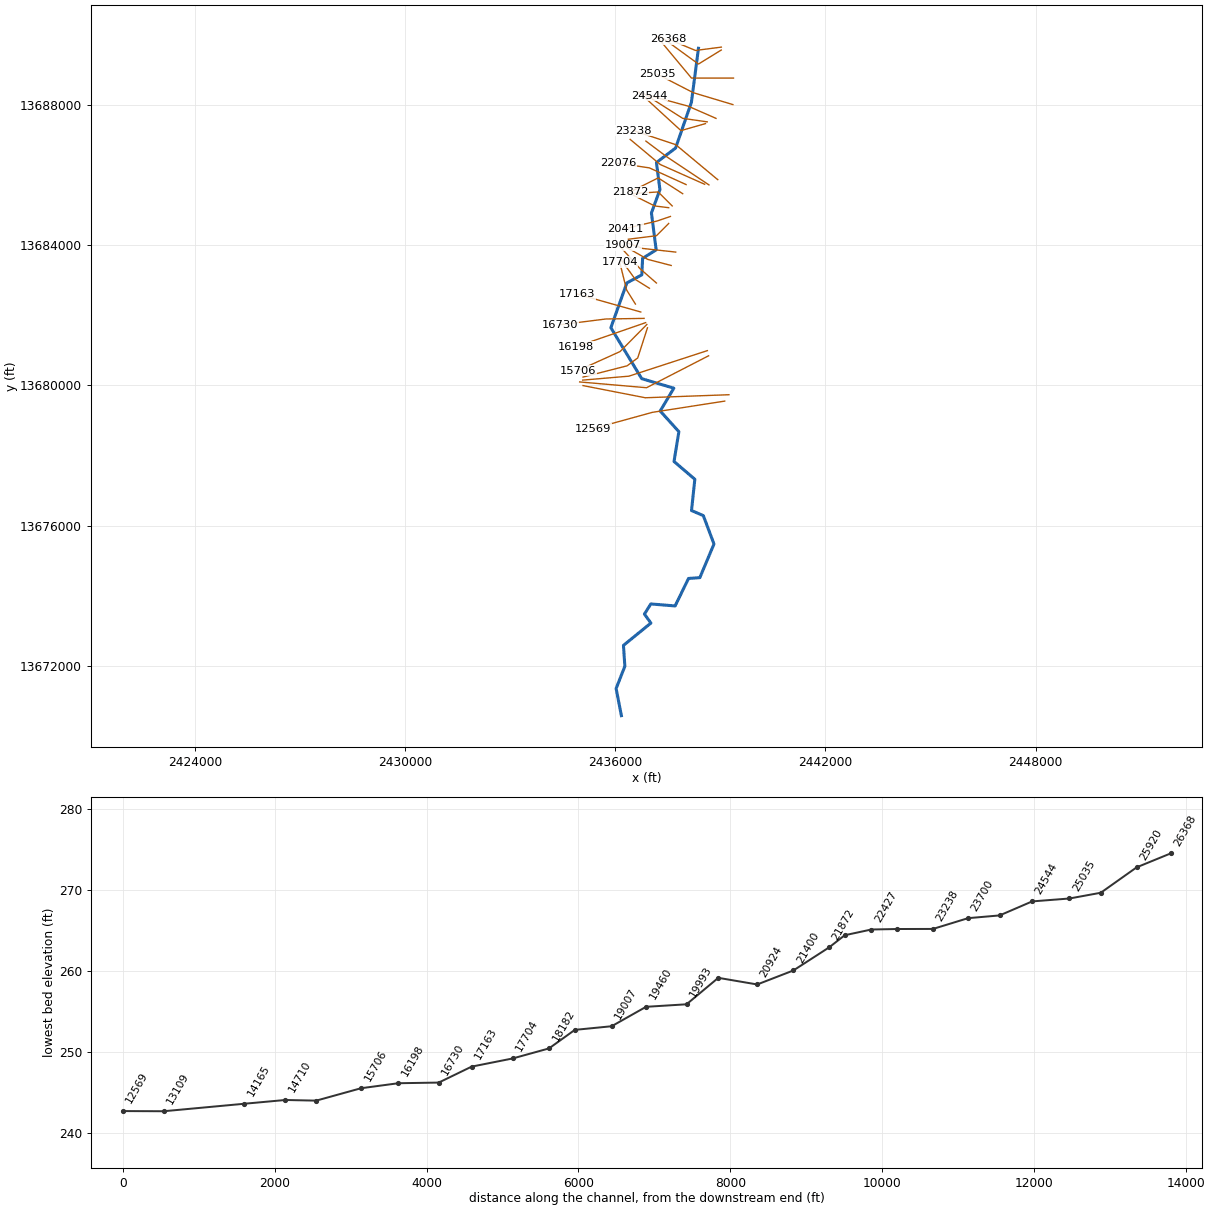
--- PUTNAM BRANCH.prj (project) ---

Proj Title=PUTNAM BRANCH Base Level Engineering
Current Plan=p01
Default Exp/Contr=0.3,0.1
English Units
Geom File=g01
Flow File=f01
Plan File=p01
Y Axis Title=Elevation
X Axis Title(PF)=Main Channel Distance
X Axis Title(XS)=Station
BEGIN DESCRIPTION:
PUTNAM BRANCH
END DESCRIPTION:
DSS Export Rating Curves= 0
DSS Export Rating Curve Sorted= 0
DSS Export Volume Flow Curves= 0
DXF OffsetX= 0
DXF OffsetY= 0
DXF ScaleX= 1
DXF ScaleY= 10

--- PUTNAM BRANCH.p01 (plan) ---

Plan Title=Multiple Run
Short Identifier=Multiple
Geom File=g01
Flow File=f01
Subcritical Flow
K Sum by GR= 0
Std Step Tol= 0.01
Critical Tol= 0.01
Num of Std Step Trials= 20
Max Error Tol= 0.3
Flow Tol Ratio= 0.001
Split Flow NTrial= 30
Split Flow Tol= 0.02
Split Flow Ratio= 0.02
Log Output Level= 0
Friction Slope Method= 1
Unsteady Friction Slope Method= 2
Unsteady Bridges Friction Slope Method= 1
Parabolic Critical Depth
Global Vel Dist=  1 , 1 , 1
Global Log Level= 0
CheckData=True
Encroach Param= -1, 0, 0, 0
BEGIN DESCRIPTION:
Multiple Run
END DESCRIPTION:

--- PUTNAM BRANCH.f01 (steady flow) ---

Flow Title=Multiple
Number of Profiles=7
Profile Names=10-year,25-year,50-year,1pct_min,100-year,1pct_plu,500-year
River Rch & RM= PUTNAM BRANCH,Reach-1,26368
     653    1048    1402     908    1813    3617    2999
River Rch & RM= PUTNAM BRANCH,Reach-1,24544
     846    1365    1833    1190    2374    4736    3943
River Rch & RM= PUTNAM BRANCH,Reach-1,17163
    1213    1990    2701    1768    3528    7040    5972
River Rch & RM= PUTNAM BRANCH,Reach-1,13109
    1423    2350    3204    2107    4203    8386    7172
River Rch & RM= PUTNAM BRANCH,Reach-1,11732
    1601    2653    3625    2387    4763    9504    8155
River Rch & RM= PUTNAM BRANCH,Reach-1,8212
    1542    2530    3432    2242    4474    8927    7543
Boundary for River Rch & Prof#=PUTNAM BRANCH,Reach-1,1
Up Type=0
Dn Type=3
Dn Slope=0.005
Boundary for River Rch & Prof#=PUTNAM BRANCH,Reach-1,2
Up Type=0
Dn Type=3
Dn Slope=0.005
Boundary for River Rch & Prof#=PUTNAM BRANCH,Reach-1,3
Up Type=0
Dn Type=3
Dn Slope=0.005
Boundary for River Rch & Prof#=PUTNAM BRANCH,Reach-1,4
Up Type=0
Dn Type=3
Dn Slope=0.005
Boundary for River Rch & Prof#=PUTNAM BRANCH,Reach-1,5
Up Type=0
Dn Type=3
Dn Slope=0.005
Boundary for River Rch & Prof#=PUTNAM BRANCH,Reach-1,6
Up Type=0
Dn Type=3
Dn Slope=0.005
Boundary for River Rch & Prof#=PUTNAM BRANCH,Reach-1,7
Up Type=0
Dn Type=3
Dn Slope=0.005

--- PUTNAM BRANCH.g01 (geometry) ---

Geom Title=Existing Conditions
Program Version=4.10

River Reach=PUTNAM BRANCH   ,Reach-1
Reach XY= 30
        2438375.       13689625.      2438172.94     13688080.85
      2437721.47     13686776.45      2437175.55     13686364.37
      2437275.11     13685590.36      2437032.33      13684925.1
      2437167.21     13683871.94      2436779.97     13683627.58
      2436758.37     13683158.29      2436330.34     13682927.74
      2435874.66     13681649.78      2436754.87     13680194.77
      2437671.91     13679923.37      2437282.76     13679271.58
      2437815.85     13678681.73      2437677.25     13677830.93
      2438271.18     13677323.42      2438176.58     13676431.03
      2438513.93     13676285.08       2438817.9       13675475.
      2438413.76     13674514.95      2438091.46     13674492.15
       2437708.7     13673707.69      2437015.18     13673764.53
      2436832.29     13673474.91      2437017.54     13673218.91
      2436234.15     13672581.73      2436273.78      13671985.5
      2436024.38     13671350.08        2436175.       13670575.

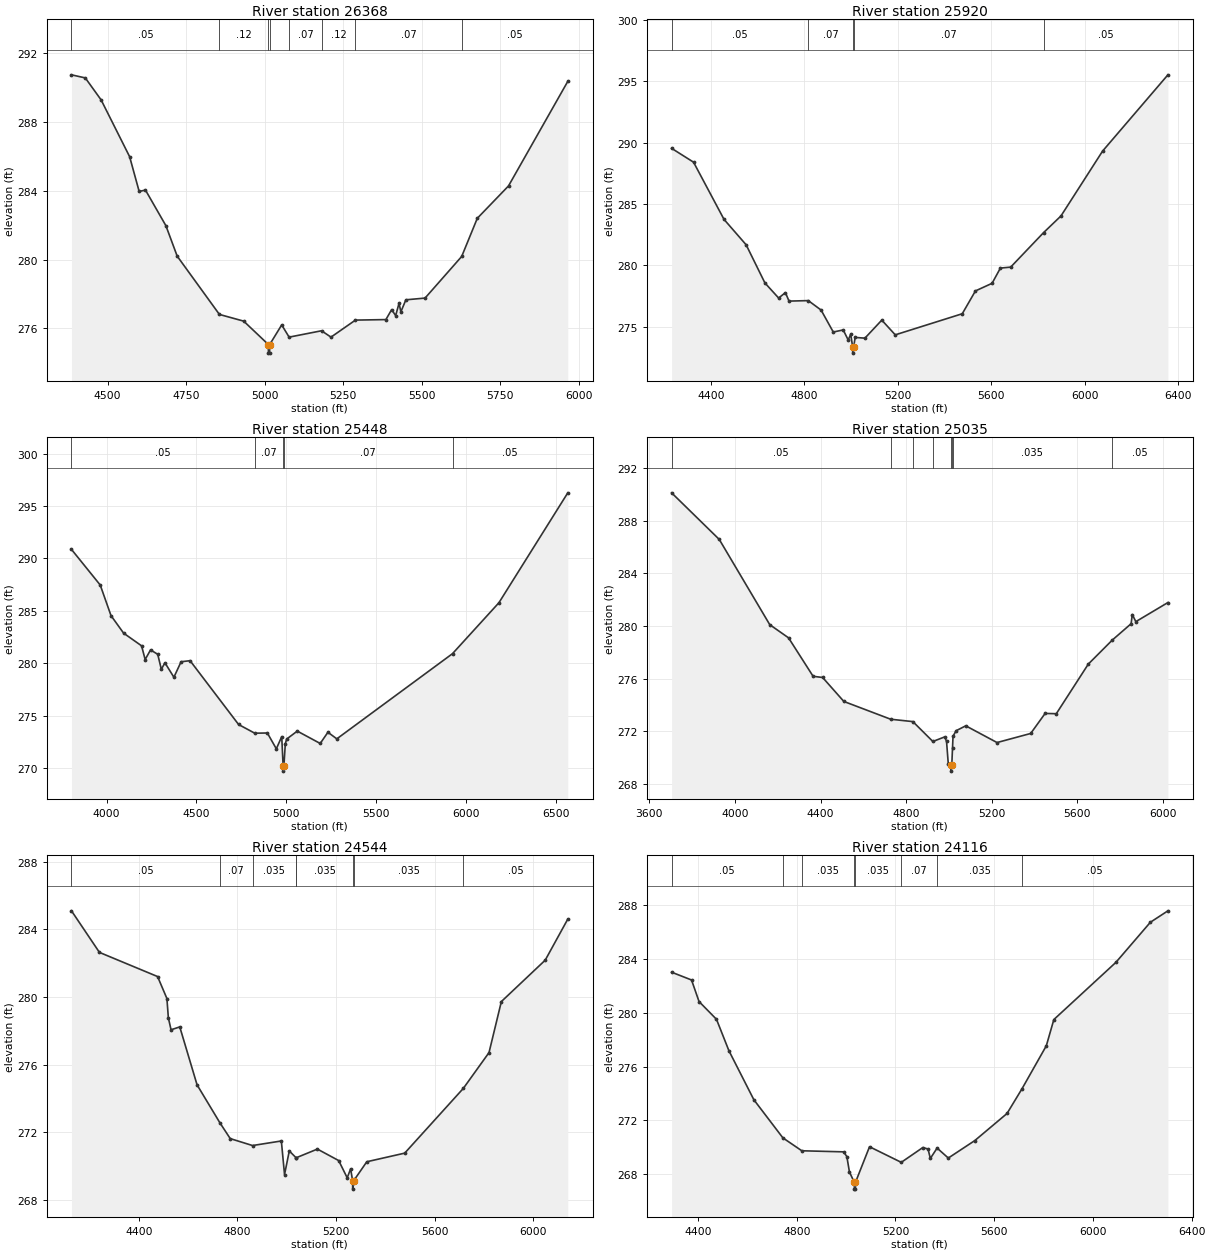
Type RM Length L Ch R = 1 ,26368   ,448,448,448
BEGIN DESCRIPTION:
B20137
END DESCRIPTION:
XS GIS Cut Line= 3
      2439028.59     13689658.49      2438290.75     13689563.01
      2437519.07     13689883.82
#Sta/Elev= 30
  4385.3  290.74  4429.3  290.56  4479.7  289.28  4570.4  285.98  4600.7  283.96
  4620.8  284.04  4685.8  281.97  4721.7   280.2  4856.1  276.81  4933.4  276.42
    5012  275.06  5012.3  274.56  5015.9  274.56  5016.2  275.06  5054.4   276.2
    5078  275.49  5181.2  275.86  5211.3  275.49  5289.1  276.48    5386  276.51
  5404.4  277.09  5417.1  276.74  5427.9  277.46  5433.7  276.96  5449.6  277.66
  5510.7  277.76  5627.3  280.18    5677   282.4  5776.3  284.28    5965  290.36
#Mann= 8 ,-1 , 0
  4385.3     .05       0  4856.1     .12       0    5012     .05       0
  5016.2     .12       0    5078     .07       0  5181.2     .12       0
  5289.1     .07       0  5627.3     .05       0
Bank Sta=5012,5016.2
XS Rating Curve= 0 ,0
Exp/Cntr=0.3,0.1

Type RM Length L Ch R = 1 ,25920   ,472,472,472
BEGIN DESCRIPTION:
PUTNAM BRANCH 50.0
END DESCRIPTION:
XS GIS Cut Line= 3
      2439024.98     13689574.99        2438375.       13689175.
      2437275.04     13689974.97
#Sta/Elev= 30
  4232.7  289.53  4326.6   288.4  4456.9  283.74  4551.5  281.67  4631.9  278.56
  4690.6  277.33  4719.6  277.77    4735  277.08  4817.5  277.12  4872.2  276.35
  4924.3  274.56  4966.9  274.73  4988.2  273.91    4999  274.38  5007.3  273.34
  5007.6  272.84  5011.6  273.34  5017.9  274.12  5059.7  274.06  5131.9  275.53
  5189.5  274.33  5476.2  276.05  5532.6  277.91  5603.7  278.53  5639.3  279.77
  5683.3  279.85    5824  282.66  5898.5  284.02  6076.7  289.31    6356  295.52
#Mann= 5 ,-1 , 0
  4232.7     .05       0  4817.5     .07       0  5007.3     .05       0
  5011.6     .07       0    5824     .05       0
Bank Sta=5007.3,5011.6
XS Rating Curve= 0 ,0
Exp/Cntr=0.3,0.1

Type RM Length L Ch R = 1 ,25448   ,413,413,413
BEGIN DESCRIPTION:
PUTNAM BRANCH 49.0
END DESCRIPTION:
XS GIS Cut Line= 3
      2439374.96       13688775.        2438175.       13688775.
      2437175.01     13689974.99
#Sta/Elev= 30
  3804.3  290.86  3964.3  287.46  4024.3  284.54  4094.3  282.87  4194.3  281.66
  4214.3  280.35  4244.3  281.27  4284.3  280.85  4304.3  279.42  4324.3  280.04
  4374.3  278.66  4414.3  280.14  4464.3  280.24  4734.3  274.15  4824.2  273.32
  4894.3  273.34  4944.3  271.83  4974.3  272.99  4982.1   270.2  4982.4   269.7
  4986.4   270.2  4994.3  272.31  5001.8  272.76  5060.9  273.52  5188.5  272.34
  5231.4  273.41  5280.9  272.78  5924.7  280.91    6183  285.77  6566.3  296.26
#Mann= 5 ,-1 , 0
  3804.3     .05       0  4824.2     .07       0  4982.1     .05       0
  4986.4     .07       0  5924.7     .05       0
Bank Sta=4982.1,4986.4
XS Rating Curve= 0 ,0
Exp/Cntr=0.3,0.1

Type RM Length L Ch R = 1 ,25035   ,491,491,491
BEGIN DESCRIPTION:
PUTNAM BRANCH 48.0
END DESCRIPTION:
XS GIS Cut Line= 3
      2439358.41     13688017.88      2438229.98     13688356.41
      2437214.35     13688877.25
#Sta/Elev= 30
  3704.1  290.12  3926.9  286.58  4162.8  280.11  4250.6  279.11  4365.4  276.19
  4409.9   276.1  4509.1  274.28    4728  272.93  4831.7  272.75  4925.1  271.24
  4980.5  271.59    4989  271.25  4997.1  269.55  5009.3  269.49  5009.6  268.99
  5013.6  269.49    5017  270.77  5019.3  271.64  5033.9  272.06  5078.9  272.43
    5225  271.16  5382.3  271.85  5449.7  273.37    5502  273.35  5651.7  277.12
  5763.6  278.94  5851.5  280.18  5857.1  280.88  5873.7  280.34  6023.6  281.79
#Mann= 8 ,-1 , 0
  3704.1     .05       0    4728     .12       0  4831.7    .035       0
  4925.1     .12       0  5009.3     .05       0  5013.6     .12       0
    5017    .035       0  5763.6     .05       0
Bank Sta=5009.3,5013.6
XS Rating Curve= 0 ,0
Exp/Cntr=0.3,0.1

Type RM Length L Ch R = 1 ,24544   ,428,428,428
BEGIN DESCRIPTION:
PUTNAM BRANCH 47.0
END DESCRIPTION:
XS GIS Cut Line= 3
      2438875.01       13687625.        2438075.       13687975.
        2436975.       13688275.
#Sta/Elev= 30
    4127   285.1  4240.4  282.64  4476.3  281.21  4514.1  279.91    4520  278.77
  4530.9  278.06  4566.3  278.23  4636.5   274.8  4728.9  272.56    4771  271.62
  4861.5  271.21  4978.4  271.48  4991.3  269.49  5010.6  270.89  5037.9  270.49
  5039.3  270.49  5124.6     271    5211  270.32  5245.5   269.3  5259.4  269.83
  5267.5  269.13  5267.8  268.63    5272  269.13    5325  270.25  5478.8  270.76
  5716.5  274.59  5820.8  276.71  5870.9  279.73  6048.8  282.18  6140.4  284.61
#Mann= 8 ,-1 , 0
    4127     .05       0  4728.9     .07       0  4861.5    .035       0
  5037.9     .07       0  5039.3    .035       0  5267.5    .035       0
    5272    .035       0  5716.5     .05       0
Bank Sta=5267.5,5272
XS Rating Curve= 0 ,0
Exp/Cntr=0.3,0.1

Type RM Length L Ch R = 1 ,24116   ,416,416,416
BEGIN DESCRIPTION:
PUTNAM BRANCH 46.0
END DESCRIPTION:
XS GIS Cut Line= 3
      2438624.98       13687525.        2437925.       13687625.
      2436825.02     13688324.99
#Sta/Elev= 30
  4292.9  283.02  4373.7  282.44    4404  280.84  4474.7  279.52  4525.2  277.18
  4626.2  273.54  4743.7  270.71  4820.4  269.75  4989.9  269.67  5002.9  269.32
  5013.5  268.17  5033.3   267.4  5033.6   266.9  5037.5   266.9  5037.8   267.4
  5094.8  270.05  5223.4  268.89  5310.7  269.99  5331.9  269.88  5341.2  269.18
  5368.6  269.95    5414  269.21  5521.5  270.51  5651.9  272.52    5713  274.37
  5811.1  277.55  5841.6   279.5    6093  283.75  6232.7  286.73  6303.8  287.58
#Mann= 8 ,-1 , 0
  4292.9     .05       0  4743.7     .07       0  4820.4    .035       0
  5033.3    .035       0  5037.8    .035       0  5223.4     .07       0
  5368.6    .035       0    5713     .05       0
Bank Sta=5033.3,5037.8
XS Rating Curve= 0 ,0
Exp/Cntr=0.3,0.1

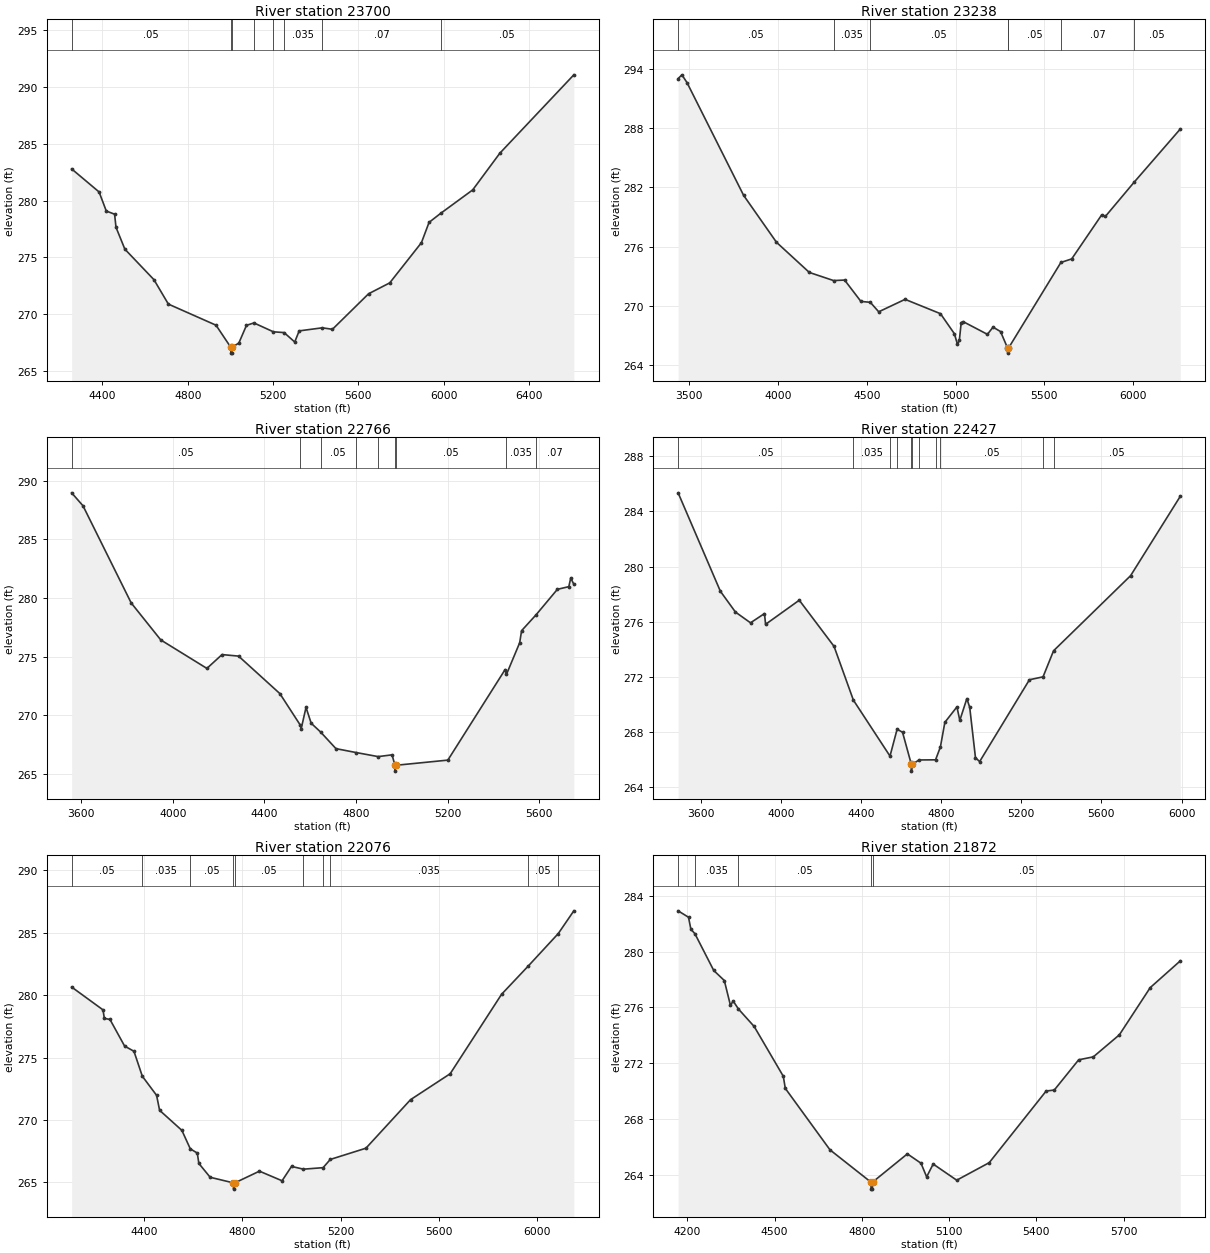
Type RM Length L Ch R = 1 ,23700   ,462,462,462
BEGIN DESCRIPTION:
PUTNAM BRANCH 45.0
END DESCRIPTION:
XS GIS Cut Line= 3
      2438574.98     13687474.99        2437875.       13687275.
      2436674.98     13688375.02
#Sta/Elev= 30
  4255.3  282.79    4384  280.76  4417.8  279.08  4456.8   278.8  4463.3  277.65
  4504.9  275.72  4641.4  273.03    4709  270.88  4932.6  269.02  5002.3  267.06
  5002.6  266.56  5006.5  266.56  5006.8  267.06  5039.7  267.45  5075.5  269.01
  5110.5  269.22  5201.5  268.44  5251.9  268.37  5301.8  267.54  5322.7  268.52
  5431.1  268.79  5478.7  268.66  5648.3  271.79  5747.6  272.75  5896.2  276.29
    5932  278.08  5986.1  278.87  6136.7  280.94  6264.3  284.18  6611.2  291.08
#Mann= 8 ,-1 , 0
  4255.3     .05       0  5002.3     .05       0  5006.8     .05       0
  5110.5    .035       0  5201.5     .05       0  5251.9    .035       0
  5431.1     .07       0  5986.1     .05       0
Bank Sta=5002.3,5006.8
XS Rating Curve= 0 ,0
Exp/Cntr=0.3,0.1

Type RM Length L Ch R = 1 ,23238   ,472,472,472
BEGIN DESCRIPTION:
PUTNAM BRANCH 44.0
END DESCRIPTION:
XS GIS Cut Line= 3
      2438924.98     13685875.02        2437725.       13686875.
      2436525.03     13687274.99
#Sta/Elev= 30
    3438     293  3459.4  293.38  3488.1  292.59    3807  281.18  3991.8  276.44
  4176.7  273.39  4313.1  272.57  4375.2  272.62    4467  270.46    4520  270.37
  4567.2  269.41  4715.6  270.67  4914.8  269.22  4992.9   267.2  5010.6  266.11
  5021.1  266.53  5031.6  268.32  5042.2  268.42  5179.2  267.13  5210.8  267.86
    5253  267.41  5292.9  265.73  5293.2  265.23  5297.4  265.73  5592.7   274.4
  5653.6  274.76  5822.2  279.21  5843.3  279.06  6003.6  282.49  6264.9   287.9
#Mann= 7 ,-1 , 0
    3438     .05       0  4313.1    .035       0    4520     .05       0
  5292.9     .05       0  5297.4     .05       0  5592.7     .07       0
  6003.6     .05       0
Bank Sta=5292.9,5297.4
XS Rating Curve= 0 ,0
Exp/Cntr=0.3,0.1

Type RM Length L Ch R = 1 ,22766   ,339,339,339
BEGIN DESCRIPTION:
PUTNAM BRANCH 43.0
END DESCRIPTION:
XS GIS Cut Line= 3
      2438674.99       13685725.        2437475.       13686525.
      2436875.01     13686974.99
#Sta/Elev= 30
  3558.3  288.98  3607.9  287.87  3818.2  279.58  3947.4  276.42  4148.7  273.99
  4214.8  275.17  4286.9  275.04  4467.2  271.84  4556.3  269.15  4560.3  268.84
  4581.4  270.66  4603.9  269.31    4645  268.56  4712.1  267.14  4799.3  266.81
  4896.2  266.46  4956.9  266.61  4969.6  265.72  4969.9  265.22  4974.4  265.72
  5200.5  266.16  5450.5  273.89  5456.4  273.48  5514.1  276.18  5522.4  277.21
  5585.8  278.57  5678.6  280.74  5728.6  280.97    5737  281.71  5750.5  281.17
#Mann= 9 ,-1 , 0
  3558.3     .05       0  4556.3    .035       0    4645     .05       0
  4799.3     .07       0  4896.2     .05       0  4969.6     .05       0
  4974.4     .05       0  5456.4    .035       0  5585.8     .07       0
Bank Sta=4969.6,4974.4
XS Rating Curve= 0 ,0
Exp/Cntr=0.3,0.1

Type RM Length L Ch R = 1 ,22427   ,351,351,351
BEGIN DESCRIPTION:
PUTNAM BRANCH 42.0
END DESCRIPTION:
XS GIS Cut Line= 3
      2438551.16     13685743.56       2437283.8      13686307.8
      2436424.98     13687025.02
#Sta/Elev= 30
  3487.7  285.35  3698.6  278.21  3773.8   276.7    3849  275.92  3918.7  276.59
  3924.2  275.81  4092.3  277.56  4265.9  274.21  4362.4  270.31  4545.1  266.25
  4580.6   268.2  4607.7  267.98  4651.5  265.66  4651.9  265.16  4656.8  265.66
  4689.8  265.97  4772.5  265.98  4796.6  266.91  4818.9   268.7  4879.2  269.82
  4893.5  268.84  4928.6  270.42  4942.9  269.79  4971.6  266.14  4992.4  265.85
    5241  271.79  5308.9     272  5361.3  273.89  5745.9  279.34  5993.9   285.1
#Mann= 11 ,-1 , 0
  3487.7     .05       0  4362.4    .035       0  4545.1     .07       0
  4580.6     .05       0  4651.5     .05       0  4656.8     .05       0
  4689.8    .035       0  4772.5     .07       0  4796.6     .05       0
  5308.9    .035       0  5361.3     .05       0
Bank Sta=4651.5,4656.8
XS Rating Curve= 0 ,0
Exp/Cntr=0.3,0.1

Type RM Length L Ch R = 1 ,22076   ,204,204,204
BEGIN DESCRIPTION:
B20136
END DESCRIPTION:
XS GIS Cut Line= 3
      2438021.62      13685734.9       2436971.3     13686212.31
      2436085.85     13686342.53
#Sta/Elev= 30
  4103.2  280.65  4231.1  278.82  4236.6  278.14  4259.6  278.05  4319.2  275.92
  4357.4   275.5  4391.5   273.5  4449.7  271.97    4462  270.77  4552.9  269.16
  4587.2  267.68  4615.8  267.34  4622.1  266.51  4668.3   265.4  4763.4  264.95
  4763.8  264.45  4768.7  264.95  4869.3  265.89  4961.6  265.12  5000.2  266.27
  5048.8  266.05  5128.9  266.17  5158.3  266.83  5303.7  267.73  5485.7  271.62
  5647.4   273.7  5857.1  280.07  5966.2  282.34  6088.5  284.94  6151.9  286.76
#Mann= 10 ,-1 , 0
  4103.2     .05       0  4391.5    .035       0  4587.2     .05       0
  4763.4     .05       0  4768.7     .05       0  5048.8    .035       0
  5128.9     .05       0  5158.3    .035       0  5966.2     .05       0
  6088.5    .035       0
Bank Sta=4763.4,4768.7
XS Rating Curve= 0 ,0
Exp/Cntr=0.3,0.1

Type RM Length L Ch R = 1 ,21872   ,472,472,472
BEGIN DESCRIPTION:
PUTNAM BRANCH 41.0
END DESCRIPTION:
XS GIS Cut Line= 3
      2437924.99       13685475.        2437225.       13685925.
      2436424.99     13685524.99
#Sta/Elev= 30
  4168.4  282.93  4204.1  282.47  4212.3  281.61  4226.1  281.29  4290.9  278.65
  4327.2  277.93  4348.4  276.14  4357.6  276.46    4376  275.88  4429.9  274.63
    4530  271.06  4536.9  270.19  4690.5  265.78  4831.5  263.46  4831.9  262.96
  4836.4  262.96  4836.8  263.46  4956.6  265.49  5003.4  264.82  5022.9  263.84
  5045.3  264.76  5126.3   263.6  5238.1  264.86  5433.8     270  5461.7  270.07
  5545.6  272.24  5595.9  272.45  5685.4  274.03  5791.6  277.42    5895  279.34
#Mann= 5 ,-1 , 0
  4168.4     .05       0  4226.1    .035       0    4376     .05       0
  4831.5     .05       0  4836.8     .05       0
Bank Sta=4831.5,4836.8
XS Rating Curve= 0 ,0
Exp/Cntr=0.3,0.1

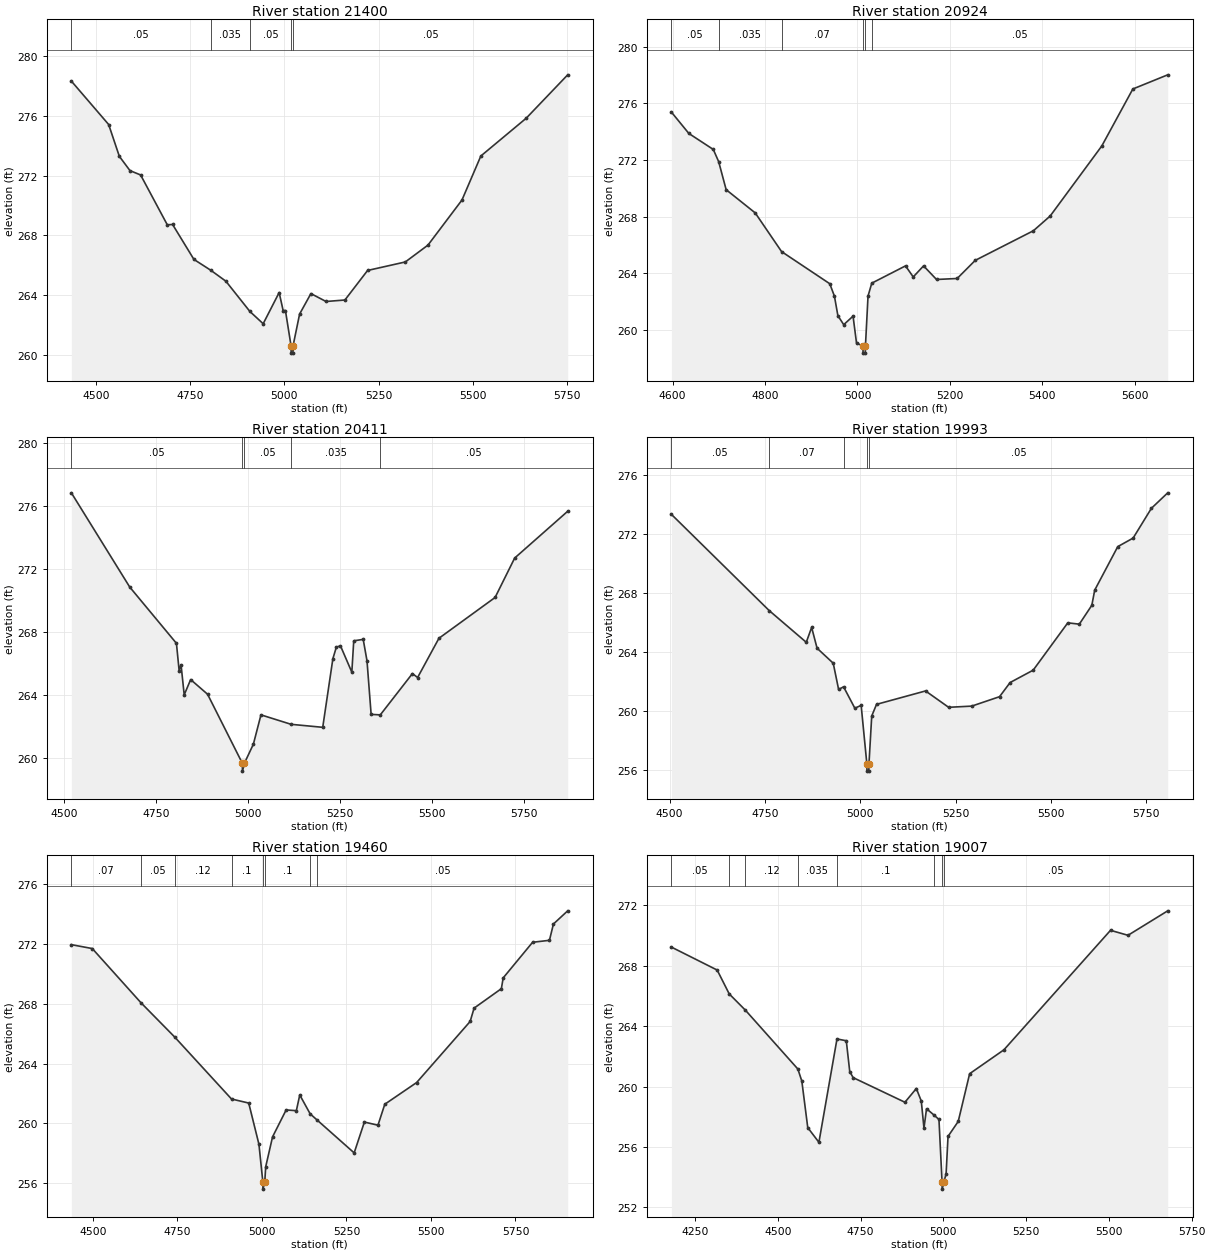
Type RM Length L Ch R = 1 ,21400   ,476,476,476
BEGIN DESCRIPTION:
PUTNAM BRANCH 40.0
END DESCRIPTION:
XS GIS Cut Line= 3
        2437625.       13685125.        2437225.       13685525.
      2436475.05       13685475.
#Sta/Elev= 30
  4434.6  278.33  4533.6  275.42  4561.9  273.29  4590.2  272.33  4618.4  272.04
  4689.2   268.7  4703.3  268.72  4759.9  266.38  4804.8  265.65  4844.7  264.92
  4908.5  262.89  4943.7  262.07  4986.1  264.16  4996.7  262.95  5002.8  262.95
  5017.6   260.6    5018   260.1  5022.6   260.1  5023.1   260.6  5040.4  262.72
  5070.4  264.09  5110.5  263.56  5160.6  263.66  5220.8  265.64    5321  266.21
  5381.1  267.34  5471.3  270.36  5521.4  273.31  5641.7  275.84  5751.9  278.75
#Mann= 5 ,-1 , 0
  4434.6     .05       0  4804.8    .035       0  4908.5     .05       0
  5017.6     .05       0  5023.1     .05       0
Bank Sta=5017.6,5023.1
XS Rating Curve= 0 ,0
Exp/Cntr=0.3,0.1

Type RM Length L Ch R = 1 ,20924   ,513,513,513
BEGIN DESCRIPTION:
PUTNAM BRANCH 39.0
END DESCRIPTION:
XS GIS Cut Line= 3
      2437525.04       13685075.        2437125.       13685125.
      2436524.98     13685425.01
#Sta/Elev= 30
  4597.3  275.39  4635.1  273.88    4688  272.75  4699.6  271.89  4715.8  269.91
  4778.7  268.27  4835.7  265.54    4940  263.27  4950.1  262.39  4957.6  261.01
  4970.2  260.38  4990.4  260.98  4997.9  259.08  5011.7  258.87  5012.1  258.37
  5016.8  258.37  5017.2  258.87  5022.8   262.4  5030.9  263.31  5103.9  264.53
  5120.6  263.75    5143  264.53    5171  263.57  5215.7  263.64  5254.8  264.92
  5380.6  267.01  5416.9  268.05  5528.7     273  5595.8  277.02  5671.3  278.02
#Mann= 6 ,-1 , 0
  4597.3     .05       0  4699.6    .035       0  4835.7     .07       0
  5011.7     .05       0  5017.2     .07       0  5030.9     .05       0
Bank Sta=5011.7,5017.2
XS Rating Curve= 0 ,0
Exp/Cntr=0.3,0.1

Type RM Length L Ch R = 1 ,20411   ,418,418,418
BEGIN DESCRIPTION:
PUTNAM BRANCH 38.0
END DESCRIPTION:
XS GIS Cut Line= 3
      2437575.04     13684825.01      2437188.31     13684693.22
      2436274.99       13684475.
#Sta/Elev= 30
  4520.3  276.85  4678.8  270.87  4805.6   267.3  4812.9  265.57  4818.1  265.94
  4826.7  264.03  4844.2     265  4890.1  264.07  4984.5  259.69  4984.9  259.19
  4990.1  259.69  5014.5   260.9  5035.1  262.76    5117  262.16  5202.8  261.97
  5230.4  266.33  5239.8  267.06    5251  267.14  5281.8  265.47    5287  267.46
  5312.7  267.55    5323  266.19  5334.2  262.79  5359.1  262.76  5446.3  265.38
  5460.4  265.13  5518.3  267.62  5670.8  270.21  5723.9  272.71  5867.9  275.68
#Mann= 5 ,-1 , 0
  4520.3     .05       0  4984.5     .05       0  4990.1     .05       0
    5117    .035       0  5359.1     .05       0
Bank Sta=4984.5,4990.1
XS Rating Curve= 0 ,0
Exp/Cntr=0.3,0.1

Type RM Length L Ch R = 1 ,19993   ,533,533,533
BEGIN DESCRIPTION:
PUTNAM BRANCH 37.0
END DESCRIPTION:
XS GIS Cut Line= 3
      2437525.03     13684625.03        2437175.       13684275.
      2436375.04       13684175.
#Sta/Elev= 30
  4504.9  273.34  4761.4  266.81  4858.5  264.66  4872.6  265.67  4886.8  264.26
  4929.2  263.24  4943.3  261.46  4956.3  261.64  4985.8  260.19  5002.4  260.38
  5017.3  256.42  5017.7  255.92  5022.4  255.92  5022.9  256.42  5030.1  259.66
  5042.7  260.45  5171.2  261.36  5231.7  260.25  5292.2  260.33  5365.2  260.97
  5392.9  261.93  5453.4  262.77  5544.1  265.98  5574.3  265.89  5607.1  267.17
  5614.7   268.2  5675.1  271.15  5715.4  271.73  5763.3  273.75  5806.1   274.8
#Mann= 5 ,-1 , 0
  4504.9     .05       0  4761.4     .07       0  4956.3     .05       0
  5017.3     .05       0  5022.9     .05       0
Bank Sta=5017.3,5022.9
XS Rating Curve= 0 ,0
Exp/Cntr=0.3,0.1

Type RM Length L Ch R = 1 ,19460   ,453,453,453
BEGIN DESCRIPTION:
B20135
END DESCRIPTION:
XS GIS Cut Line= 3
       2437726.5      13683807.8      2436780.33     13683911.97
      2436294.19     13684085.59
#Sta/Elev= 30
  4436.3  271.94  4498.2  271.68  4642.2  268.06  4741.5  265.78    4910  261.63
  4960.9  261.36  4991.1  258.61  5002.6  256.11    5003  255.61  5008.4  256.11
  5011.2  257.11  5031.4   259.1  5071.6   260.9  5101.8  260.85  5111.9   261.9
  5142.6  260.64    5163  260.23  5272.8  258.03    5303  260.09  5343.2  259.88
  5363.4  261.28  5457.6  262.73  5615.9  266.81  5627.5   267.7  5708.2     269
  5713.6  269.72  5800.6   272.1  5850.4  272.23  5862.2  273.32  5904.4   274.2
#Mann= 8 ,-1 , 0
  4436.3     .07       0  4642.2     .05       0  4741.5     .12       0
    4910      .1       0  5002.6     .05       0  5008.4      .1       0
  5142.6     .12       0    5163     .05       0
Bank Sta=5002.6,5008.4
XS Rating Curve= 0 ,0
Exp/Cntr=0.3,0.1

Type RM Length L Ch R = 1 ,19007   ,485,485,485
BEGIN DESCRIPTION:
PUTNAM BRANCH 36.0
END DESCRIPTION:
XS GIS Cut Line= 3
      2437596.33     13683425.85       2436927.9     13683599.47
      2436224.78     13683998.77
#Sta/Elev= 30
  4178.5  269.23  4316.8  267.71  4353.2  266.13  4402.2  265.05  4560.5  261.16
  4572.5  260.36  4590.4  257.28  4624.1  256.31  4678.7  263.15  4706.8  263.03
  4717.2  260.99  4727.5  260.59  4883.9  258.96  4918.4  259.87  4933.3  259.04
  4941.4  257.25  4949.2  258.53  4972.4   258.1  4986.7  257.82    4996  253.71
  4996.4  253.21  5001.9  253.71  5008.3  254.23  5014.1   256.7  5044.9  257.69
  5079.4  260.85  5182.9  262.43  5504.9  270.34  5557.7  270.01  5677.7  271.63
#Mann= 8 ,-1 , 0
  4178.5     .05       0  4353.2    .035       0  4402.2     .12       0
  4560.5    .035       0  4678.7      .1       0  4972.4     .05       0
    4996     .05       0  5001.9     .05       0
Bank Sta=4996,5001.9
XS Rating Curve= 0 ,0
Exp/Cntr=0.3,0.1

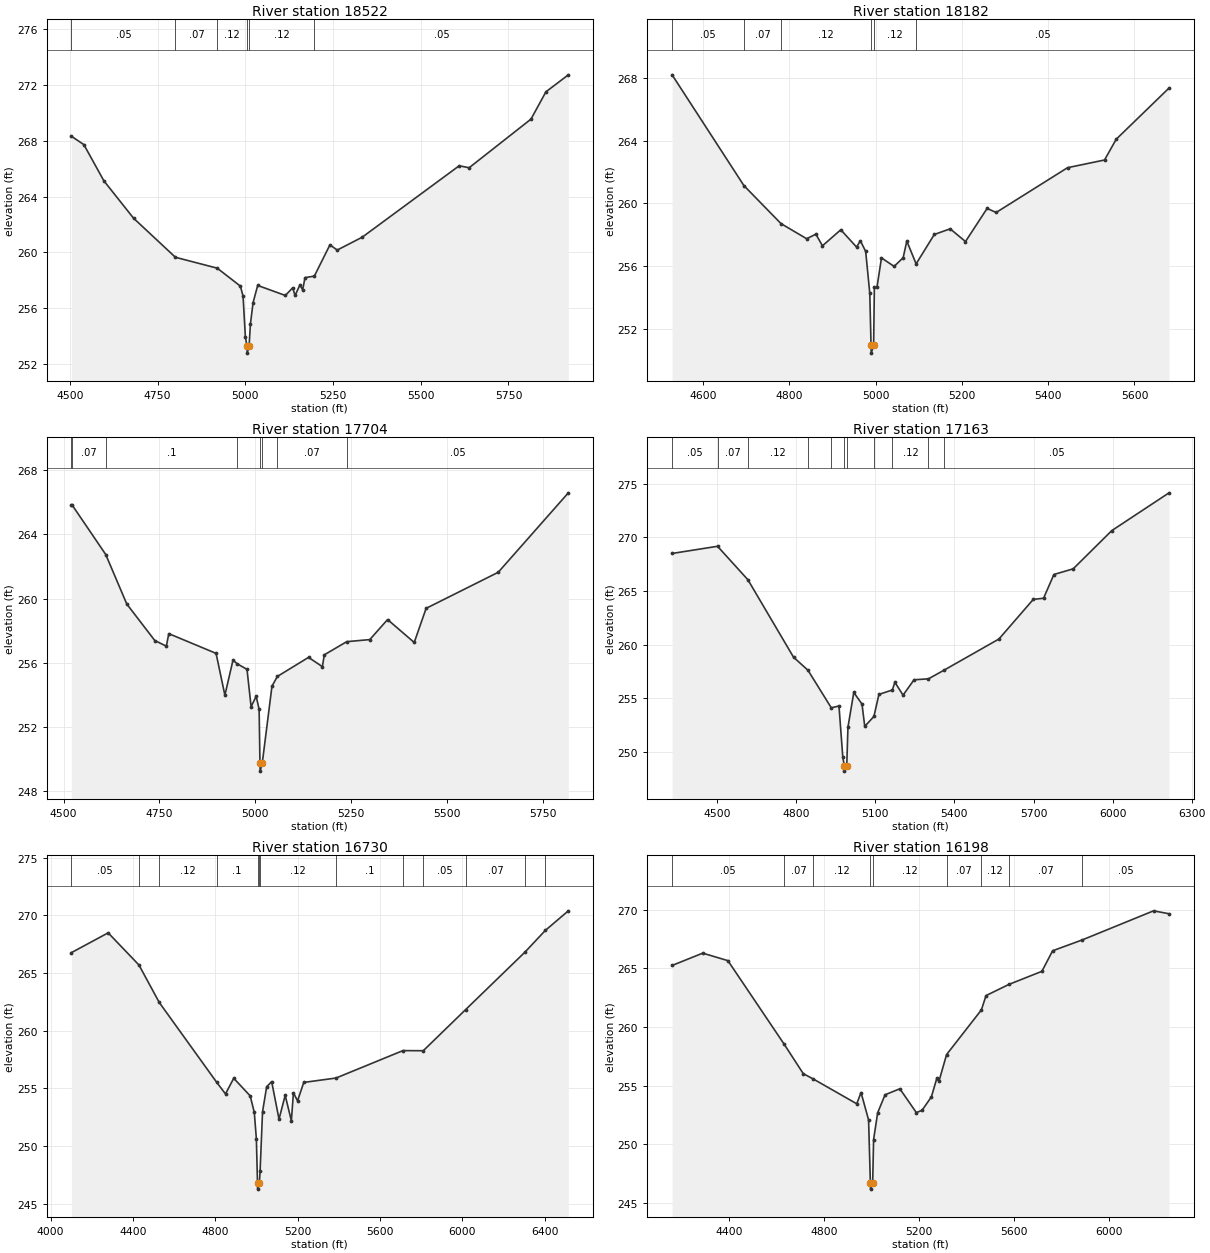
Type RM Length L Ch R = 1 ,18522   ,340,340,340
BEGIN DESCRIPTION:
PUTNAM BRANCH 35.0
END DESCRIPTION:
XS GIS Cut Line= 3
      2437175.04     13682924.97      2436710.88     13683330.37
      2436175.03     13683924.97
#Sta/Elev= 30
    4504  268.33  4539.6  267.73  4596.6  265.13  4681.1  262.45  4800.6  259.64
  4919.7  258.86  4985.8  257.57  4993.4  256.85    5000  253.93  5004.6  253.26
  5005.1  252.76  5010.6  253.26  5014.3  254.83  5021.9  256.38  5035.1  257.62
  5113.9   256.9  5134.9  257.45  5141.6   256.9  5155.8  257.67  5163.3   257.3
    5170  258.18  5196.6  258.29    5241  260.53  5261.9  260.16  5332.9  261.08
  5609.5  266.21  5637.9  266.07  5814.2  269.56  5856.8  271.52  5920.7  272.74
#Mann= 6 ,-1 , 0
    4504     .05       0  4800.6     .07       0  4919.7     .12       0
  5004.6     .05       0  5010.6     .12       0  5196.6     .05       0
Bank Sta=5004.6,5010.6
XS Rating Curve= 0 ,0
Exp/Cntr=0.3,0.1

Type RM Length L Ch R = 1 ,18182   ,478,478,478
BEGIN DESCRIPTION:
PUTNAM BRANCH 34.0
END DESCRIPTION:
XS GIS Cut Line= 3
      2436975.03     13682774.98        2436575.       13683025.
        2436175.       13683575.
#Sta/Elev= 30
  4528.3  268.18  4694.8  261.13  4780.8  258.71  4840.2  257.75  4861.5  258.04
  4876.8   257.3  4919.3  258.32  4955.8  257.22  4964.7  257.62    4977  256.94
  4986.5  254.27  4989.4  250.97  4989.9  250.47  4995.4  250.97  4997.1  254.65
  5003.1  254.65  5013.6  256.53  5042.9  255.99  5063.8  256.54  5072.3   257.6
  5093.9  256.15    5136  258.02  5172.8  258.38  5208.3  257.57  5258.5  259.68
  5279.4  259.42  5444.8  262.27  5530.6  262.76  5557.6  264.08  5680.1  267.34
#Mann= 6 ,-1 , 0
  4528.3     .05       0  4694.8     .07       0  4780.8     .12       0
  4989.4     .05       0  4995.4     .12       0  5093.9     .05       0
Bank Sta=4989.4,4995.4
XS Rating Curve= 0 ,0
Exp/Cntr=0.3,0.1

Type RM Length L Ch R = 1 ,17704   ,541,541,541
BEGIN DESCRIPTION:
PUTNAM BRANCH 33.0
END DESCRIPTION:
XS GIS Cut Line= 3
      2436575.01     13682324.99        2436325.       13682725.
      2436125.01     13683524.97
#Sta/Elev= 30
  4520.5  265.83  4522.7  265.83  4610.1  262.75    4665  259.66  4738.1  257.38
  4768.2  257.03  4774.6  257.81  4897.9  256.58  4920.9  253.97  4942.1  256.16
  4952.4  255.94  4978.6  255.58  4989.3  253.25  5002.5   253.9  5010.2  253.09
  5012.4  249.73  5012.9  249.23  5018.4  249.73  5043.7  254.53  5057.8  255.14
  5139.1  256.33  5175.2  255.75  5180.3  256.49  5238.7  257.31  5298.9  257.44
  5345.3  258.69  5414.8  257.26  5445.8  259.39  5633.9  261.64  5816.8   266.6
#Mann= 8 ,-1 , 0
  4520.5     .05       0  4522.7     .07       0  4610.1      .1       0
  4952.4     .12       0  5012.4     .05       0  5018.4     .12       0
  5057.8     .07       0  5238.7     .05       0
Bank Sta=5012.4,5018.4
XS Rating Curve= 0 ,0
Exp/Cntr=0.3,0.1

Type RM Length L Ch R = 1 ,17163   ,433,433,433
BEGIN DESCRIPTION:
B20134
END DESCRIPTION:
XS GIS Cut Line= 2
      2436728.28     13682097.72      2434913.99     13682609.89
#Sta/Elev= 30
    4329   268.5  4501.4  269.17  4616.6  266.05  4789.6  258.84  4844.4  257.62
  4932.9  254.12  4962.1  254.29  4976.6   249.5  4982.5  248.72    4983  248.22
  4991.6  248.72  4996.1  252.31  5018.2  255.55  5049.4  254.47  5059.8  252.39
  5094.6  253.31  5113.6  255.37  5164.6  255.78  5174.1   256.5  5205.2   255.3
  5246.8  256.73  5301.5  256.82  5361.6  257.64  5568.9  260.53  5699.1  264.22
  5738.2  264.33  5777.4  266.54  5850.6  267.07    5997  270.63  6214.2  274.15
#Mann= 11 ,-1 , 0
    4329     .05       0  4501.4     .07       0  4616.6     .12       0
  4844.4      .1       0  4932.9     .12       0  4982.5     .05       0
  4991.6     .12       0  5094.6     .07       0  5164.6     .12       0
  5301.5     .07       0  5361.6     .05       0
Bank Sta=4982.5,4991.6
XS Rating Curve= 0 ,0
Exp/Cntr=0.3,0.1

Type RM Length L Ch R = 1 ,16730   ,532,532,532
BEGIN DESCRIPTION:
B20133
END DESCRIPTION:
XS GIS Cut Line= 3
      2436823.69     13681915.44      2435729.98     13681898.08
      2434419.56     13681733.19
#Sta/Elev= 30
  4101.2  266.77  4279.9  268.49  4429.4   265.7  4528.1  262.45  4806.3  255.54
    4850  254.51    4890  255.87    4970  254.34    4990   252.9    5000  250.61
  5005.5  246.75    5006  246.25  5014.6  246.75  5018.1  247.83    5030  252.97
    5050  255.13  5074.4  255.58    5110  252.32    5140  254.39    5170  252.18
    5180  254.61  5200.1  253.91  5230.3  255.51  5386.9  255.89  5712.1  258.27
  5810.9  258.26  6016.8  261.83  6305.2  266.82    6404   268.7  6515.8   270.4
#Mann= 13 ,-1 , 0
  4101.2     .05       0  4429.4     .07       0  4528.1     .12       0
  4806.3      .1       0  5005.5     .05       0  5014.6      .1       0
  5018.1     .12       0  5386.9      .1       0  5712.1     .07       0
  5810.9     .05       0  6016.8     .07       0  6305.2     .05       0
    6404    .035       0
Bank Sta=5005.5,5014.6
XS Rating Curve= 0 ,0
Exp/Cntr=0.3,0.1

Type RM Length L Ch R = 1 ,16198   ,492,492,492
BEGIN DESCRIPTION:
B20132
END DESCRIPTION:
XS GIS Cut Line= 2
      2436867.16     13681793.92      2434888.95     13681108.48
#Sta/Elev= 30
  4159.2  265.25  4288.3   266.3  4394.3  265.66  4631.1  258.54  4711.8  256.02
  4752.8  255.58  4937.1  253.45  4955.2  254.41    4987  252.07  4994.6  246.67
  4995.1  246.17  5004.2  246.67  5008.1   250.4  5025.2  252.68  5056.4  254.22
  5118.7  254.73  5188.1   252.7  5212.1  252.89  5251.6  254.04  5274.4  255.62
  5283.3  255.36  5315.6  257.65  5462.3  261.46  5481.8  262.68  5577.9  263.63
  5717.2  264.75  5762.2   266.5  5887.3  267.43  6187.6  269.91  6252.8  269.66
#Mann= 9 ,-1 , 0
  4159.2     .05       0  4631.1     .07       0  4752.8     .12       0
  4994.6     .05       0  5004.2     .12       0  5315.6     .07       0
  5462.3     .12       0  5577.9     .07       0  5887.3     .05       0
Bank Sta=4994.6,5004.2
XS Rating Curve= 0 ,0
Exp/Cntr=0.3,0.1

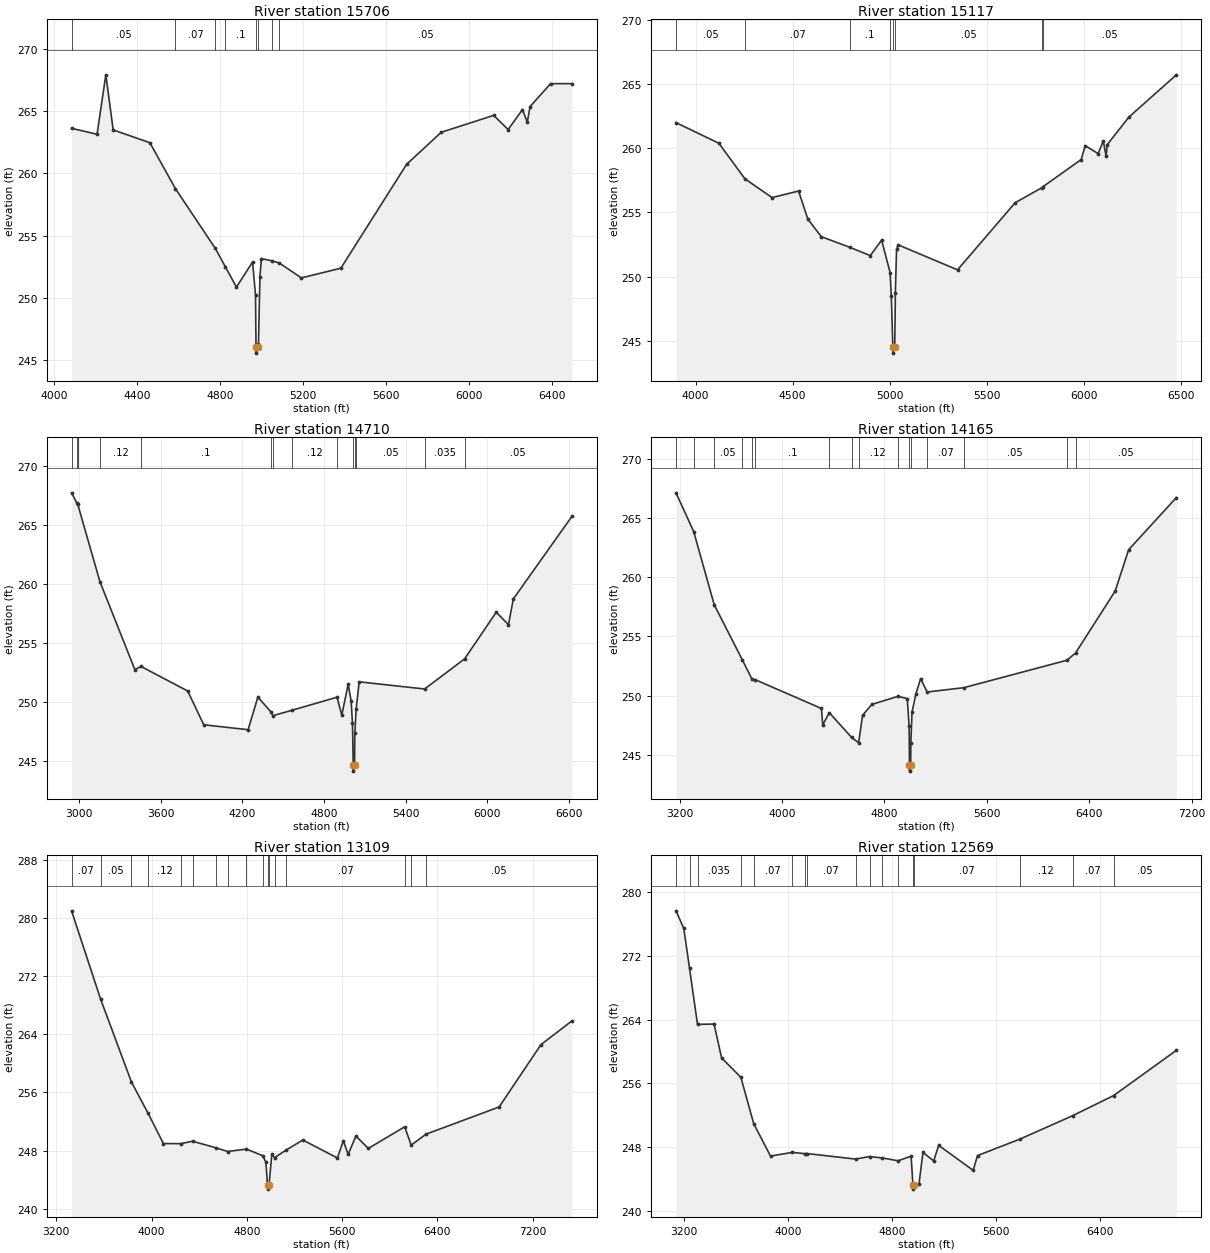
Type RM Length L Ch R = 1 ,15706   ,589,589,589
BEGIN DESCRIPTION:
B20131
END DESCRIPTION:
XS GIS Cut Line= 3
      2436901.87     13681741.84      2436137.97     13680969.26
      2434931.39     13680422.39
#Sta/Elev= 30
    4085  263.63  4207.8  263.15  4250.2  267.93  4285.6   263.5  4462.4  262.47
  4585.5  258.78  4777.8  253.97  4825.9   252.5  4879.6  250.86  4957.4  252.88
  4971.5  250.19  4973.8  246.05  4974.3  245.55  4983.4  246.05  4985.7  246.31
  4992.8  251.71  4999.8  253.15  5049.8  252.98    5086   252.8  5192.6   251.6
  5382.8  252.38  5699.4  260.73  5866.4  263.31  6119.4  264.67  6188.7  263.53
    6258  265.13  6281.1  264.12  6294.6  265.38  6393.4  267.22  6496.2  267.22
#Mann= 8 ,-1 , 0
    4085     .05       0  4585.5     .07       0  4777.8     .12       0
  4825.9      .1       0  4973.8     .05       0  4983.4      .1       0
  5049.8     .12       0    5086     .05       0
Bank Sta=4973.8,4983.4
XS Rating Curve= 0 ,0
Exp/Cntr=0.3,0.1

Type RM Length L Ch R = 1 ,15117   ,407,407,407
BEGIN DESCRIPTION:
B20130
END DESCRIPTION:
XS GIS Cut Line= 4
      2436919.22     13681646.35      2436641.44     13680786.97
      2436337.62     13680561.27      2435079.48     13680240.23
#Sta/Elev= 30
  3898.6  262.01  4119.6   260.4  4254.1  257.62    4394  256.16  4530.6  256.67
  4578.4  254.48  4647.7  253.11  4796.1  252.27  4900.3  251.63  4958.7  252.84
  5002.5  250.31  5008.8  248.44  5016.7  244.52  5017.2  244.02  5026.4  244.52
  5029.6  248.72  5035.8  252.12  5044.2  252.47  5350.2  250.52  5647.4  255.76
  5786.1  256.94    5789  256.99  5987.9  259.13  6008.6  260.21  6075.4  259.59
  6101.5  260.58  6116.3  259.41  6122.1  260.29  6233.7  262.44  6478.7  265.74
#Mann= 8 ,-1 , 0
  3898.6     .05       0  4254.1     .07       0  4796.1      .1       0
  5002.5     .05       0  5016.7     .05       0  5026.4     .05       0
  5786.1    .035       0    5789     .05       0
Bank Sta=5016.7,5026.4
XS Rating Curve= 0 ,0
Exp/Cntr=0.3,0.1

Type RM Length L Ch R = 1 ,14710   ,545,545,545
BEGIN DESCRIPTION:
B20129
END DESCRIPTION:
XS GIS Cut Line= 3
      2438629.31     13680995.31       2436389.7     13680266.13
      2435070.24     13680153.28
#Sta/Elev= 30
  2944.1  267.75    2984  266.87    2989   266.8  3152.6   260.2  3409.8  252.72
  3454.4     253  3798.1  250.91  3916.2  248.04  4242.2  247.62  4314.2  250.39
  4410.1  249.14  4423.5  248.81  4564.7  249.27  4896.2  250.38  4931.3  248.86
  4978.3  251.48  5000.4  250.05  5009.9  248.15  5015.6   244.6  5016.1   244.1
  5025.3   244.6  5027.1  247.31  5036.7  249.34    5059  251.69  5540.5  251.08
  5834.6  253.64  6066.9   257.6  6157.2  256.55  6192.6  258.73  6623.7  265.75
#Mann= 14 ,-1 , 0
  2944.1     .07       0    2984     .12       0    2989     .07       0
  3152.6     .12       0  3454.4      .1       0  4410.1     .12       0
  4423.5     .07       0  4564.7     .12       0  4896.2      .1       0
  5015.6     .05       0  5025.3      .1       0  5036.7     .05       0
  5540.5    .035       0  5834.6     .05       0
Bank Sta=5015.6,5025.3
XS Rating Curve= 0 ,0
Exp/Cntr=0.3,0.1

Type RM Length L Ch R = 1 ,14165   ,1056,1056,1056
BEGIN DESCRIPTION:
B20128
END DESCRIPTION:
XS GIS Cut Line= 3
      2438663.99     13680847.72      2436893.18     13679936.27
       2434983.5      13680101.2
#Sta/Elev= 30
  3171.9  267.12  3309.9  263.85  3470.4  257.67  3688.5  253.05  3765.7  251.38
    3792  251.34  4307.7  248.92  4317.9  247.54  4369.4  248.56  4543.1  246.48
  4598.2  246.03  4629.1  248.34  4701.2  249.26  4905.2  249.94  4978.2  249.75
  4992.8  247.41  4995.5  244.13    4996  243.63  5005.2  244.13    5006  245.97
  5015.3   248.6  5044.7  250.12  5082.7  251.44  5133.1  250.31  5418.6  250.67
  6225.6  252.99  6292.5   253.6  6601.8  258.82  6707.4  262.32  7080.3  266.72
#Mann= 16 ,-1 , 0
  3171.9     .12       0  3309.9     .07       0  3470.4     .05       0
  3688.5     .12       0  3765.7     .05       0    3792      .1       0
  4369.4     .12       0  4543.1     .07       0  4598.2     .12       0
  4905.2      .1       0  4995.5     .05       0  5005.2      .1       0
  5133.1     .07       0  5418.6     .05       0  6225.6    .035       0
  6292.5     .05       0
Bank Sta=4995.5,5005.2
XS Rating Curve= 0 ,0
Exp/Cntr=0.3,0.1

Type RM Length L Ch R = 1 ,13109   ,540,540,540
BEGIN DESCRIPTION:
B20127
END DESCRIPTION:
XS GIS Cut Line= 3
       2439245.6     13679736.62      2436858.45     13679649.81
      2435079.43     13679996.94
#Sta/Elev= 30
  3328.6  280.95    3573  268.79  3831.6  257.42    3971  253.14  4099.7  248.97
  4245.7  248.96  4344.1  249.29  4540.9  248.39  4639.2  247.88  4796.3  248.21
  4934.4   247.3  4960.3  246.41  4974.4  243.21  4974.9  242.71  4986.1  243.21
  5010.3  247.52  5032.8  247.03  5131.2  248.09  5270.5  249.46  5560.7  246.99
  5610.7  249.36  5650.7  247.48  5716.5  250.01  5820.2   248.3    6126  251.28
  6180.1  248.76  6306.3  250.27  6918.6     254  7269.5  262.56  7529.9  265.83
#Mann= 17 ,-1 , 0
  3328.6     .07       0    3573     .05       0  3831.6     .07       0
    3971     .12       0  4245.7    .035       0  4344.1      .1       0
  4540.9     .12       0  4639.2     .07       0  4796.3     .12       0
  4934.4      .1       0  4974.4     .05       0  4986.1      .1       0
  5032.8     .12       0  5131.2     .07       0    6126     .12       0
  6180.1     .07       0  6306.3     .05       0
Bank Sta=4974.4,4986.1
XS Rating Curve= 0 ,0
Exp/Cntr=0.3,0.1

Type RM Length L Ch R = 1 ,12569   ,389,389,389
BEGIN DESCRIPTION:
B20126
END DESCRIPTION:
XS GIS Cut Line= 3
      2439124.09     13679554.33      2437058.11     13679233.15
      2435358.34     13678764.84
#Sta/Elev= 30
  3137.9  277.66  3197.7  275.46    3242  270.44  3303.4  263.41    3431  263.45
  3488.8   259.2  3637.1  256.77  3736.3  250.95  3865.6  246.88  4033.7  247.34
  4132.9  247.18  4144.3   247.2  4521.6   246.5  4628.7  246.82  4727.9  246.64
    4848  246.29  4948.5  246.86  4962.9  243.23  4963.4  242.73  4974.6  243.23
  5009.2  243.35  5039.6  247.34  5122.3  246.27    5161  248.22  5426.3  245.09
  5460.1  246.94  5787.2  249.01    6193  251.95  6508.1  254.47  6991.8  260.15
#Mann= 17 ,-1 , 0
  3137.9     .07       0    3242     .05       0  3303.4    .035       0
  3637.1     .05       0  3736.3     .07       0  4033.7    .035       0
  4132.9     .12       0  4144.3     .07       0  4521.6     .12       0
  4628.7     .07       0  4727.9      .1       0    4848     .07       0
  4962.9     .05       0  4974.6     .07       0  5787.2     .12       0
    6193     .07       0  6508.1     .05       0
Bank Sta=4962.9,4974.6
XS Rating Curve= 0 ,0
Exp/Cntr=0.3,0.1