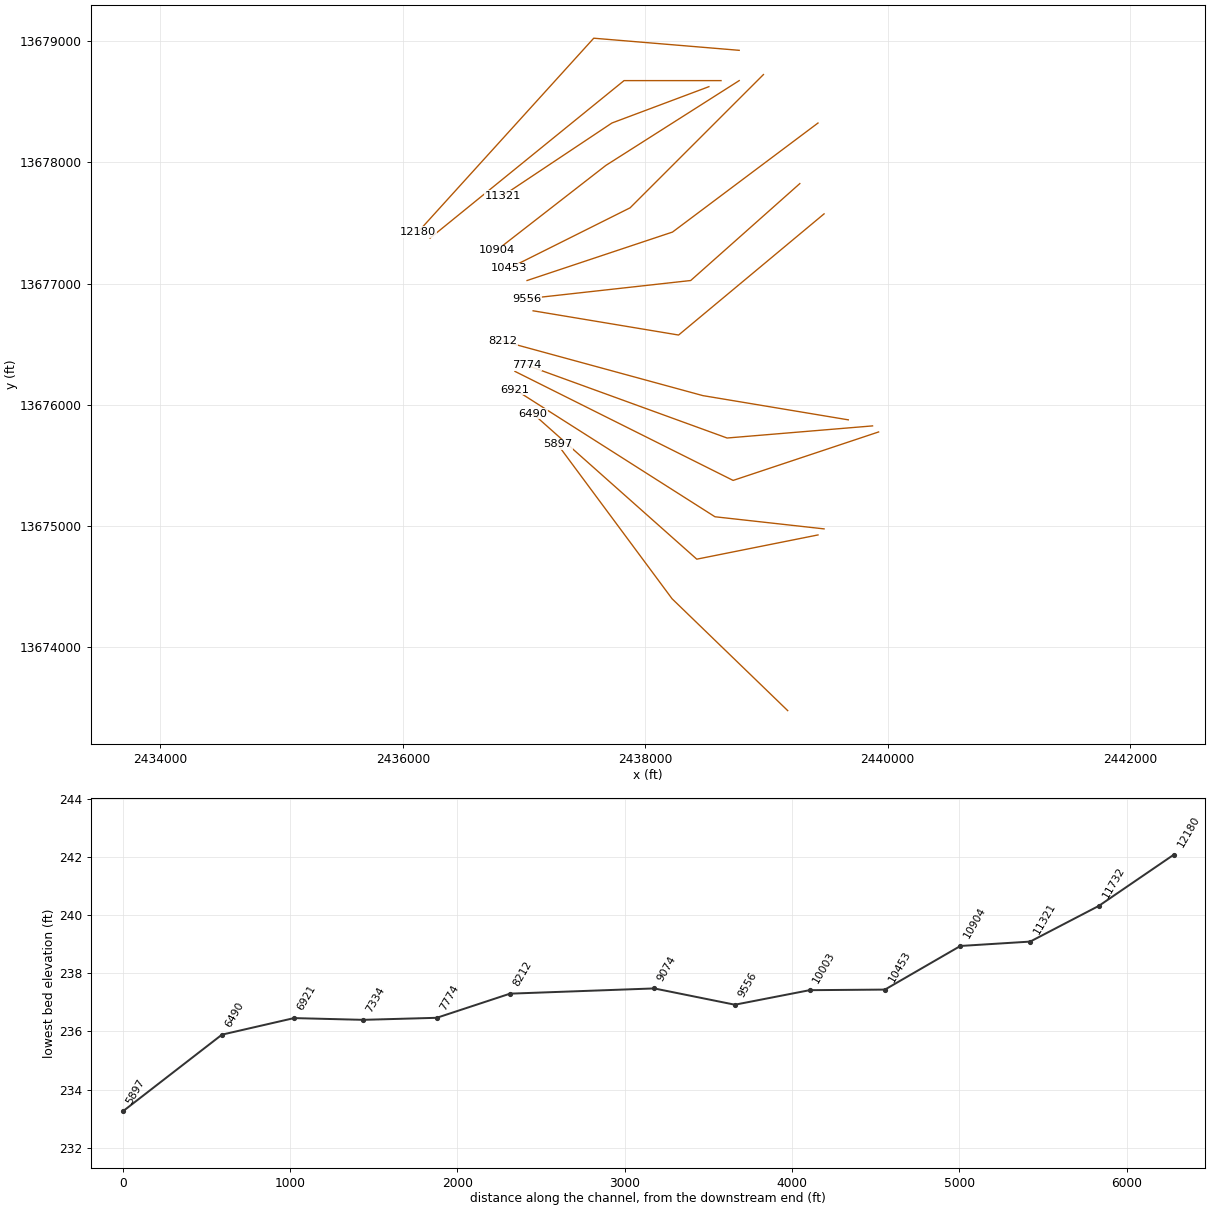
HEC-RAS study PUTNAM BRANCH.prj: PUTNAM BRANCH Base Level Engineering

--- PUTNAM BRANCH.g01 (geometry) --- (continued)

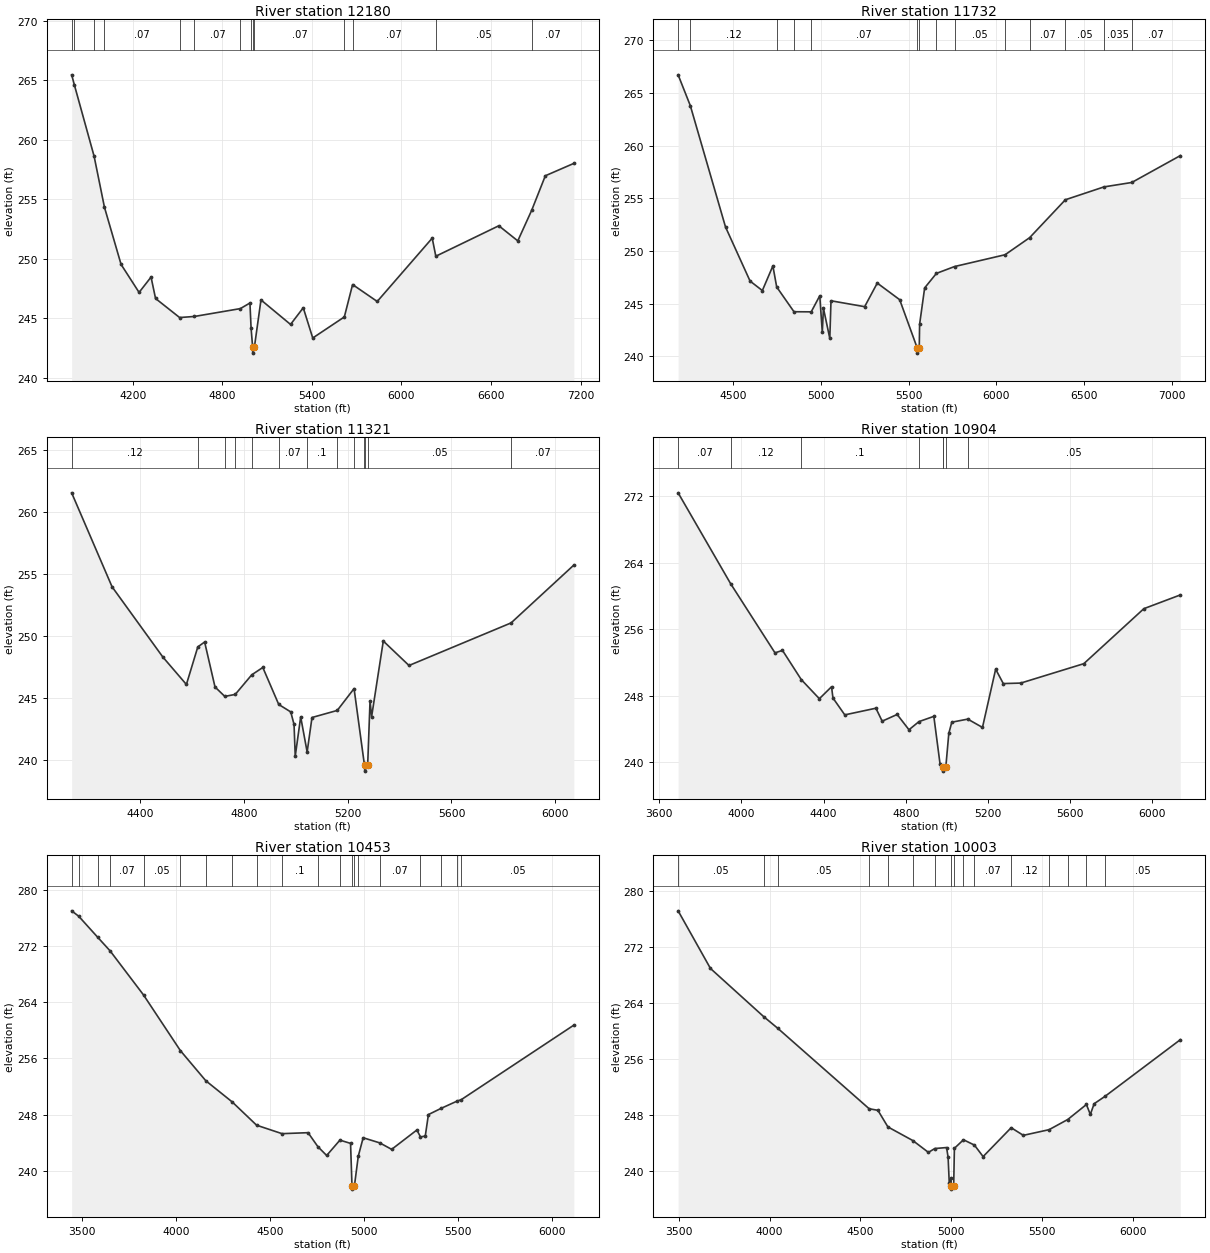
Type RM Length L Ch R = 1 ,12180   ,448,448,448
BEGIN DESCRIPTION:
PUTNAM BRANCH 24.0
END DESCRIPTION:
XS GIS Cut Line= 3
        2438775.       13678925.        2437575.       13679025.
      2436125.03     13677425.03
#Sta/Elev= 30
  3790.9  265.46  3809.4   264.6  3941.3  258.62  4010.7  254.33    4122  249.53
  4242.5  247.18  4322.7  248.47  4352.8  246.67    4514  245.07    4613  245.16
  4920.7  245.82    4985  246.29  4992.6  244.19  5003.1  242.58  5003.6  242.08
  5014.8  242.58  5058.9  246.55  5256.9  244.49  5342.1  245.89  5405.6  243.35
  5617.2  245.12  5672.5  247.84  5837.5  246.42  6205.8  251.74  6229.9  250.22
  6651.9  252.78  6778.9  251.51    6872  254.08  6963.4  256.98  7154.3  258.02
#Mann= 14 ,-1 , 0
  3790.9    .035       0  3809.4     .07       0  3941.3     .12       0
  4010.7     .07       0    4514    .035       0    4613     .07       0
  4920.7     .12       0  4992.6     .07       0  5003.1     .05       0
  5014.8     .07       0  5617.2    .035       0  5672.5     .07       0
  6229.9     .05       0    6872     .07       0
Bank Sta=5003.1,5014.8
XS Rating Curve= 0 ,0
Exp/Cntr=0.3,0.1

Type RM Length L Ch R = 1 ,11732   ,411,411,411
BEGIN DESCRIPTION:
PUTNAM BRANCH 23.0
END DESCRIPTION:
XS GIS Cut Line= 3
        2438625.       13678675.        2437825.       13678675.
      2436224.96     13677374.97
#Sta/Elev= 30
  4186.4  266.74    4256  263.81  4456.4   252.3  4596.4  247.16  4666.4  246.26
  4726.4   248.6  4748.1   246.6  4846.5  244.25  4944.9  244.24  4993.6  245.77
    5008  242.29  5014.4  244.59  5050.8  241.71  5057.5  245.29  5249.3  244.73
  5321.2  246.97    5449  245.39  5548.6  240.82  5549.1  240.32  5560.5  240.82
  5562.5  243.06  5591.2  246.51  5658.3  247.89  5761.6  248.54  6049.5  249.66
  6189.4  251.28  6393.1  254.88  6612.9   256.1  6771.4  256.52    7048  259.07
#Mann= 14 ,-1 , 0
  4186.4     .07       0    4256     .12       0  4748.1     .07       0
  4846.5    .035       0  4944.9     .07       0  5548.6     .05       0
  5560.5     .07       0  5658.3    .035       0  5761.6     .05       0
  6049.5    .035       0  6189.4     .07       0  6393.1     .05       0
  6612.9    .035       0  6771.4     .07       0
Bank Sta=5548.6,5560.5
XS Rating Curve= 0 ,0
Exp/Cntr=0.3,0.1

Type RM Length L Ch R = 1 ,11321   ,417,417,417
BEGIN DESCRIPTION:
PUTNAM BRANCH 22.0
END DESCRIPTION:
XS GIS Cut Line= 3
      2438525.04     13678625.01        2437725.       13678325.
        2436825.       13677725.
#Sta/Elev= 30
  4135.8  261.51  4291.6  253.94  4487.4  248.28  4578.2  246.07  4622.2   249.1
  4648.5  249.49  4688.5  245.87  4726.2  245.11  4766.5  245.27  4830.2  246.85
  4872.8  247.44  4934.2  244.46  4980.5  243.86  4993.2  242.85  4997.8  240.29
  5018.8  243.46  5043.7  240.63  5062.4  243.41  5159.8  243.98  5224.6  245.74
  5263.7  239.72  5265.2  239.59  5265.7  239.09  5277.1  239.59  5286.2  244.76
  5292.2  243.47  5337.3  249.57  5436.4   247.6  5829.9  251.03  6071.9  255.69
#Mann= 13 ,-1 , 0
  4135.8     .12       0  4622.2      .1       0  4726.2    .035       0
  4766.5      .1       0  4830.2    .035       0  4934.2     .07       0
  5043.7      .1       0  5159.8     .07       0  5224.6      .1       0
  5263.7     .05       0  5265.2     .05       0  5277.1     .05       0
  5829.9     .07       0
Bank Sta=5265.2,5277.1
XS Rating Curve= 0 ,0
Exp/Cntr=0.3,0.1

Type RM Length L Ch R = 1 ,10904   ,451,451,451
BEGIN DESCRIPTION:
PUTNAM BRANCH 21.0
END DESCRIPTION:
XS GIS Cut Line= 3
      2438774.97     13678674.98        2437675.       13677975.
      2436774.98     13677274.98
#Sta/Elev= 30
  3691.7  272.38  3947.3  261.46  4163.2  253.15  4199.6  253.45    4291  249.94
  4379.1  247.64  4438.4  249.08  4445.2  247.73  4502.8   245.7  4654.3   246.5
  4684.8  244.94  4757.6  245.75  4815.2  243.91  4863.8  244.89  4936.2  245.52
  4966.7  239.75  4978.4  239.49  4981.3  239.44  4981.8  238.94  4994.5  239.44
  5009.1  243.48  5023.6  244.82  5101.4  245.19  5172.9  244.19  5237.1  251.19
  5274.2  249.46  5359.3  249.52    5666  251.85  5958.3  258.46  6135.7  260.11
#Mann= 8 ,-1 , 0
  3691.7     .07       0  3947.3     .12       0    4291      .1       0
  4863.8    .035       0  4978.4      .1       0  4981.3     .05       0
  4994.5      .1       0  5101.4     .05       0
Bank Sta=4981.3,4994.5
XS Rating Curve= 0 ,0
Exp/Cntr=0.3,0.1

Type RM Length L Ch R = 1 ,10453   ,450,450,450
BEGIN DESCRIPTION:
PUTNAM BRANCH 20.0
END DESCRIPTION:
XS GIS Cut Line= 3
        2438975.       13678725.        2437875.       13677625.
      2436874.98     13677124.99
#Sta/Elev= 30
  3444.4  276.98    3482  276.21  3582.2  273.25  3649.4  271.28    3827  265.03
  4023.3  257.12  4158.6  252.84  4299.1  249.83  4429.2  246.52  4564.5  245.32
  4703.1  245.46  4755.7  243.46  4802.1  242.22  4872.7   244.4  4929.3  243.94
  4936.9  237.94  4937.4  237.44  4950.1  237.94  4970.4  242.12  4996.5  244.74
  5084.8  244.01  5148.2  243.09  5282.3  245.84  5301.7  244.86  5327.1  244.98
  5343.8  248.03  5410.2   248.9  5493.5  249.91  5518.7  250.15  6118.1  260.74
#Mann= 20 ,-1 , 0
  3444.4     .05       0    3482    .035       0  3582.2     .05       0
  3649.4     .07       0    3827     .05       0  4023.3     .07       0
  4158.6     .12       0  4299.1    .035       0  4429.2     .12       0
  4564.5      .1       0  4755.7     .12       0  4872.7      .1       0
  4936.9     .05       0  4950.1      .1       0  4970.4     .12       0
  5084.8     .07       0  5301.7    .035       0  5410.2     .05       0
  5493.5    .035       0  5518.7     .05       0
Bank Sta=4936.9,4950.1
XS Rating Curve= 0 ,0
Exp/Cntr=0.3,0.1

Type RM Length L Ch R = 1 ,10003   ,447,447,447
BEGIN DESCRIPTION:
PUTNAM BRANCH 19.0
END DESCRIPTION:
XS GIS Cut Line= 3
        2439425.       13678325.        2438225.       13677425.
      2437025.01       13677025.
#Sta/Elev= 30
  3495.9  277.11    3674  268.89  3966.6  262.03  4044.9  260.35  4547.8  248.88
  4595.9  248.66    4651  246.29  4788.6  244.34    4874  242.66  4909.1  243.21
    4974  243.35  4982.4  241.95  4988.6  238.36  4998.5  238.96  4999.8  237.92
  5000.3  237.42  5013.1  237.92    5017  243.24    5067  244.46  5127.3   243.7
  5175.1  242.06  5329.6  246.18  5396.5  245.09  5538.4   245.9  5641.1  247.35
  5743.9  249.49  5765.4  248.07  5786.5   249.6  5846.7  250.66  6260.8  258.73
#Mann= 16 ,-1 , 0
  3495.9     .05       0  3966.6    .035       0  4044.9     .05       0
  4547.8     .12       0    4651     .05       0  4788.6    .035       0
  4909.1      .1       0  4999.8     .05       0  5013.1      .1       0
    5067     .12       0  5127.3     .07       0  5329.6     .12       0
  5538.4     .07       0  5641.1     .05       0  5743.9    .035       0
  5846.7     .05       0
Bank Sta=4999.8,5013.1
XS Rating Curve= 0 ,0
Exp/Cntr=0.3,0.1

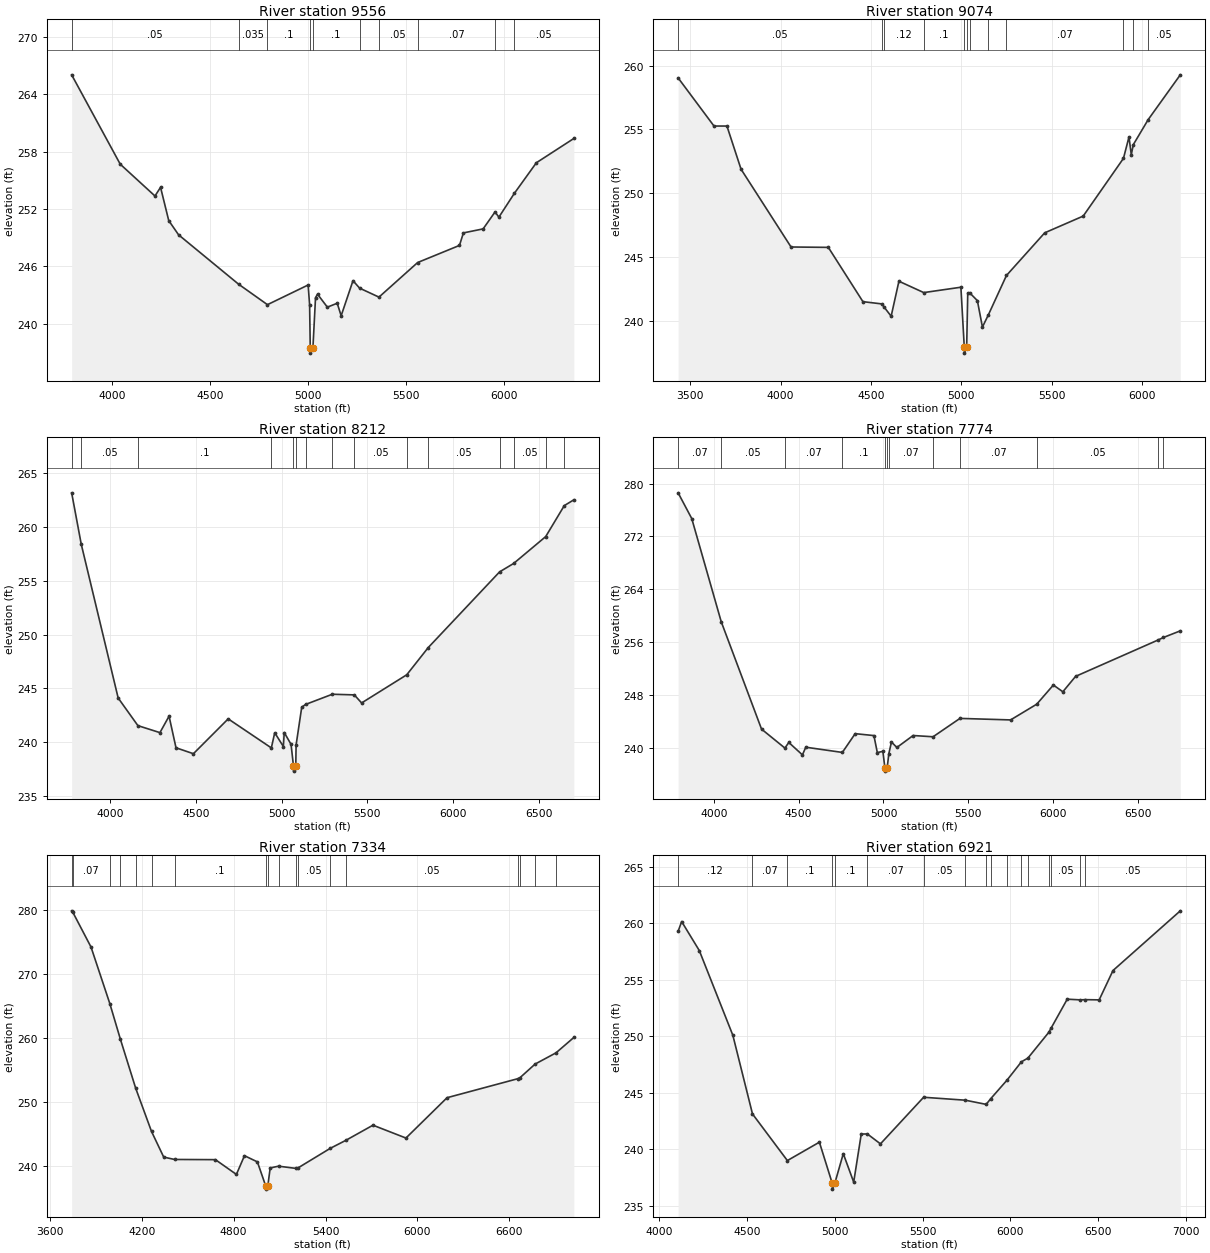
Type RM Length L Ch R = 1 ,9556    ,482,482,482
BEGIN DESCRIPTION:
PUTNAM BRANCH 18.0
END DESCRIPTION:
XS GIS Cut Line= 3
      2439274.99     13677824.99        2438375.       13677025.
      2437024.96       13676875.
#Sta/Elev= 30
  3791.8  266.04  4039.7  256.69    4217  253.36  4245.4  254.27  4287.2  250.79
  4337.4   249.3  4643.2  244.14  4790.9  241.99  4998.5  244.05    5006  241.97
  5009.4  237.42  5009.9  236.92  5022.8  237.42  5036.2  242.72  5046.3  243.09
  5096.6  241.73  5146.9  242.14    5167  240.83  5227.4   244.5  5261.1  243.72
  5359.9  242.78  5557.3   246.4  5770.7  248.19  5790.8   249.5  5891.4  249.92
  5952.1  251.69  5971.9  251.15  6050.8  253.64  6163.1  256.84  6354.3  259.38
#Mann= 10 ,-1 , 0
  3791.8     .05       0  4643.2    .035       0  4790.9      .1       0
  5009.4     .05       0  5022.8      .1       0  5261.1     .07       0
  5359.9     .05       0  5557.3     .07       0  5952.1    .035       0
  6050.8     .05       0
Bank Sta=5009.4,5022.8
XS Rating Curve= 0 ,0
Exp/Cntr=0.3,0.1

Type RM Length L Ch R = 1 ,9074    ,862,862,862
BEGIN DESCRIPTION:
PUTNAM BRANCH 17.0
END DESCRIPTION:
XS GIS Cut Line= 3
        2439475.       13677575.        2438275.       13676575.
        2437075.       13676775.
#Sta/Elev= 30
  3433.5  259.03    3632  255.26  3703.6  255.26  3781.7  251.88  4058.3  245.79
  4264.6  245.76    4456  241.51  4562.6  241.33  4570.8  241.13  4612.2  240.37
  4655.2  243.11  4792.6  242.22  4998.1  242.64  5016.7  237.98  5017.2  237.48
  5030.1  237.98  5036.1  242.19  5049.6  242.16  5089.3  241.59  5117.2  239.52
  5149.9  240.47  5250.2  243.56  5461.9   246.9  5674.8  248.21  5897.6  252.73
  5928.2  254.41  5940.9  253.01  5951.9   253.8  6034.2  255.76  6212.1  259.27
#Mann= 12 ,-1 , 0
  3433.5     .05       0  4562.6    .035       0  4570.8     .12       0
  4792.6      .1       0  5016.7     .05       0  5030.1      .1       0
  5049.6     .07       0  5149.9    .035       0  5250.2     .07       0
  5897.6     .05       0  5951.9    .035       0  6034.2     .05       0
Bank Sta=5016.7,5030.1
XS Rating Curve= 0 ,0
Exp/Cntr=0.3,0.1

Type RM Length L Ch R = 1 ,8212    ,438,438,438
BEGIN DESCRIPTION:
PUTNAM BRANCH 16.0
END DESCRIPTION:
XS GIS Cut Line= 3
      2439674.96     13675875.01        2438475.       13676075.
      2436824.97     13676525.01
#Sta/Elev= 30
  3776.8  263.18    3833  258.38  4047.9   244.1    4163  241.53  4291.3  240.88
  4344.5  242.41    4385  239.47  4486.4  238.92  4689.2  242.16  4940.6  239.46
  4960.4  240.87  5010.6  239.59  5015.8  240.89  5055.5  239.79  5069.5   237.8
    5070   237.3    5083   237.8  5084.9  239.73  5117.7  243.24  5139.9   243.5
    5296  244.45  5424.2  244.39  5466.7  243.64  5729.8  246.26    5855  248.79
  6270.9  255.83  6352.6  256.61  6539.6  259.11  6647.9  261.99  6703.6  262.53
#Mann= 15 ,-1 , 0
  3776.8     .07       0    3833     .05       0    4163      .1       0
  4940.6     .07       0  5069.5     .05       0    5083     .07       0
  5139.9     .05       0    5296    .035       0  5424.2     .05       0
  5729.8     .07       0    5855     .05       0  6270.9    .035       0
  6352.6     .05       0  6539.6    .035       0  6647.9     .05       0
Bank Sta=5069.5,5083
XS Rating Curve= 0 ,0
Exp/Cntr=0.3,0.1

Type RM Length L Ch R = 1 ,7774    ,440,440,440
BEGIN DESCRIPTION:
PUTNAM BRANCH 15.0
END DESCRIPTION:
XS GIS Cut Line= 3
      2439875.04       13675825.        2438675.       13675725.
      2437025.01       13676325.
#Sta/Elev= 30
  3789.8  278.59  3870.1   274.7  4043.9  259.08  4281.5  242.83  4419.2  239.96
  4442.1  240.81  4522.4  238.93  4542.4  240.09  4757.8   239.3  4833.4  242.14
  4943.8  241.85  4963.9  239.28  4996.7  239.46  5008.5  236.97    5009  236.47
    5022  236.97  5031.7  239.09  5047.2  240.88  5079.1  240.05  5174.9  241.86
  5292.5  241.67    5451  244.45  5749.5  244.22  5903.4   246.6  6001.5   249.5
  6057.4  248.48  6132.5  250.81  6619.1  256.32  6650.4   256.7  6749.7   257.7
#Mann= 12 ,-1 , 0
  3789.8     .07       0  4043.9     .05       0  4419.2     .07       0
  4757.8      .1       0  5008.5     .05       0    5022      .1       0
  5031.7     .07       0  5292.5     .05       0    5451     .07       0
  5903.4     .05       0  6619.1    .035       0  6650.4     .05       0
Bank Sta=5008.5,5022
XS Rating Curve= 0 ,0
Exp/Cntr=0.3,0.1

Type RM Length L Ch R = 1 ,7334    ,413,413,413
BEGIN DESCRIPTION:
PUTNAM BRANCH 14.0
END DESCRIPTION:
XS GIS Cut Line= 3
      2439925.01       13675775.        2438725.       13675375.
      2436924.98     13676275.01
#Sta/Elev= 30
  3743.2  279.93  3750.6  279.72  3869.7  274.26  3992.2  265.43  4061.5  259.83
  4161.6  252.15  4264.4  245.42    4344  241.41  4414.9  241.04  4681.4  241.01
  4818.4   238.7  4871.1  241.63  4955.4  240.66  5009.6   236.9  5010.1   236.4
  5023.4   236.9  5038.9  239.71  5093.2  239.99  5204.9  239.65  5217.2  239.67
  5430.9  242.78  5531.8  244.02  5709.7   246.4  5924.9  244.39  6193.2   250.7
  6656.1  253.68  6670.5  253.86  6767.8  255.96  6904.4  257.72  7020.6  260.12
#Mann= 18 ,-1 , 0
  3743.2     .05       0  3750.6     .07       0  3992.2     .12       0
  4061.5     .07       0  4161.6      .1       0  4264.4     .07       0
  4414.9      .1       0  5009.6     .05       0  5023.4      .1       0
  5093.2     .05       0  5204.9     .07       0  5217.2     .05       0
  5430.9     .07       0  5531.8     .05       0  6656.1    .035       0
  6670.5     .05       0  6767.8    .035       0  6904.4     .05       0
Bank Sta=5009.6,5023.4
XS Rating Curve= 0 ,0
Exp/Cntr=0.3,0.1

Type RM Length L Ch R = 1 ,6921    ,431,431,431
BEGIN DESCRIPTION:
PUTNAM BRANCH 13.0
END DESCRIPTION:
XS GIS Cut Line= 3
        2439475.       13674975.        2438575.       13675075.
        2436925.       13676125.
#Sta/Elev= 30
  4106.3   259.3  4126.4  260.17    4227   257.6  4418.2  250.09  4530.1  243.12
  4728.8  238.99  4911.2  240.62  4984.8  236.96  4985.3  236.46  4998.7  236.96
  5047.4   239.6  5106.7  237.08  5149.8  241.34  5184.5  241.35  5259.1  240.47
  5505.1   244.6  5742.7  244.34  5861.5  243.97  5886.7  244.46  5980.4  246.12
  6062.2  247.74  6099.2  248.07    6218  250.35  6230.5   250.7  6323.3  253.29
  6398.8  253.23  6424.4  253.25  6505.3  253.23  6584.1  255.83  6967.6  261.12
#Mann= 17 ,-1 , 0
  4106.3     .12       0  4530.1     .07       0  4728.8      .1       0
  4984.8     .05       0  4998.7      .1       0  5184.5     .07       0
  5505.1     .05       0  5742.7     .07       0  5861.5    .035       0
  5886.7     .07       0  5980.4    .035       0  6062.2     .05       0
  6099.2    .035       0    6218     .07       0  6230.5     .05       0
  6398.8    .035       0  6424.4     .05       0
Bank Sta=4984.8,4998.7
XS Rating Curve= 0 ,0
Exp/Cntr=0.3,0.1

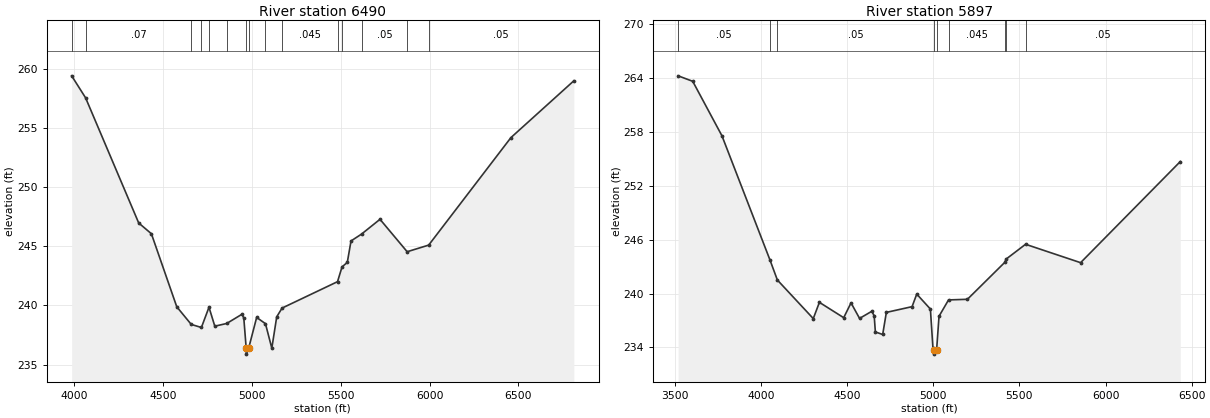
Type RM Length L Ch R = 1 ,6490    ,593,593,593
BEGIN DESCRIPTION:
PUTNAM BRANCH 12.0
END DESCRIPTION:
XS GIS Cut Line= 3
      2439424.98       13674925.        2438425.       13674725.
      2437075.02     13675924.98
#Sta/Elev= 30
  3985.7   259.4  4064.2  257.54    4363  246.97  4434.4  246.06  4577.2  239.89
  4658.7   238.4  4715.9  238.14  4758.5  239.85  4791.3  238.25  4858.3  238.48
  4944.3  239.26  4954.5  238.93  4967.9  236.39  4968.4  235.89  4981.8  236.39
  5026.8  238.99  5076.4  238.46  5112.1  236.39  5139.7  239.04  5169.8  239.78
  5481.8  242.01  5507.3  243.26  5536.9  243.64  5557.8  245.45  5616.9  246.03
  5720.9  247.28  5873.8  244.54  5994.9   245.1  6457.6  254.18  6811.7  258.98
#Mann= 15 ,-1 , 0
  3985.7     .12       0  4064.2     .07       0  4658.7     .12       0
  4715.9     .07       0  4758.5    .035       0  4858.3      .1       0
  4967.9     .05       0  4981.8      .1       0  5076.4     .05       0
  5169.8    .045       0  5481.8     .05       0  5507.3    .035       0
  5616.9     .05       0  5873.8     .07       0  5994.9     .05       0
Bank Sta=4967.9,4981.8
XS Rating Curve= 0 ,0
Exp/Cntr=0.3,0.1

Type RM Length L Ch R = 1 ,5897    ,259,259,259
BEGIN DESCRIPTION:
PUTNAM BRANCH 11.0
END DESCRIPTION:
XS GIS Cut Line= 3
        2439175.       13673475.       2438221.3     13674398.08
        2437275.     13675674.99
#Sta/Elev= 30
  3517.8  264.26  3602.6  263.65  3772.3  257.58  4050.5  243.78  4094.2  241.51
  4302.8  237.21  4338.3  239.02  4479.5  237.31    4522  238.96  4571.6  237.23
  4642.3  238.02  4656.5  237.53  4663.4  235.72  4705.9  235.44  4727.2   237.9
  4876.6  238.54  4903.7  239.94    4983  238.27  4997.6  233.98  5005.3  233.75
  5005.8  233.25  5019.2  233.75  5033.1  237.47  5088.3  239.29    5198  239.36
  5415.7  243.49  5422.8  243.84  5535.7  245.49  5855.3  243.44  6434.4  254.71
#Mann= 9 ,-1 , 0
  3517.8     .05       0  4050.5    .035       0  4094.2     .05       0
  5005.3     .05       0  5019.2     .05       0  5088.3    .045       0
  5415.7     .05       0  5422.8    .035       0  5535.7     .05       0
Bank Sta=5005.3,5019.2
XS Rating Curve= 0 ,0
Exp/Cntr=0.3,0.1