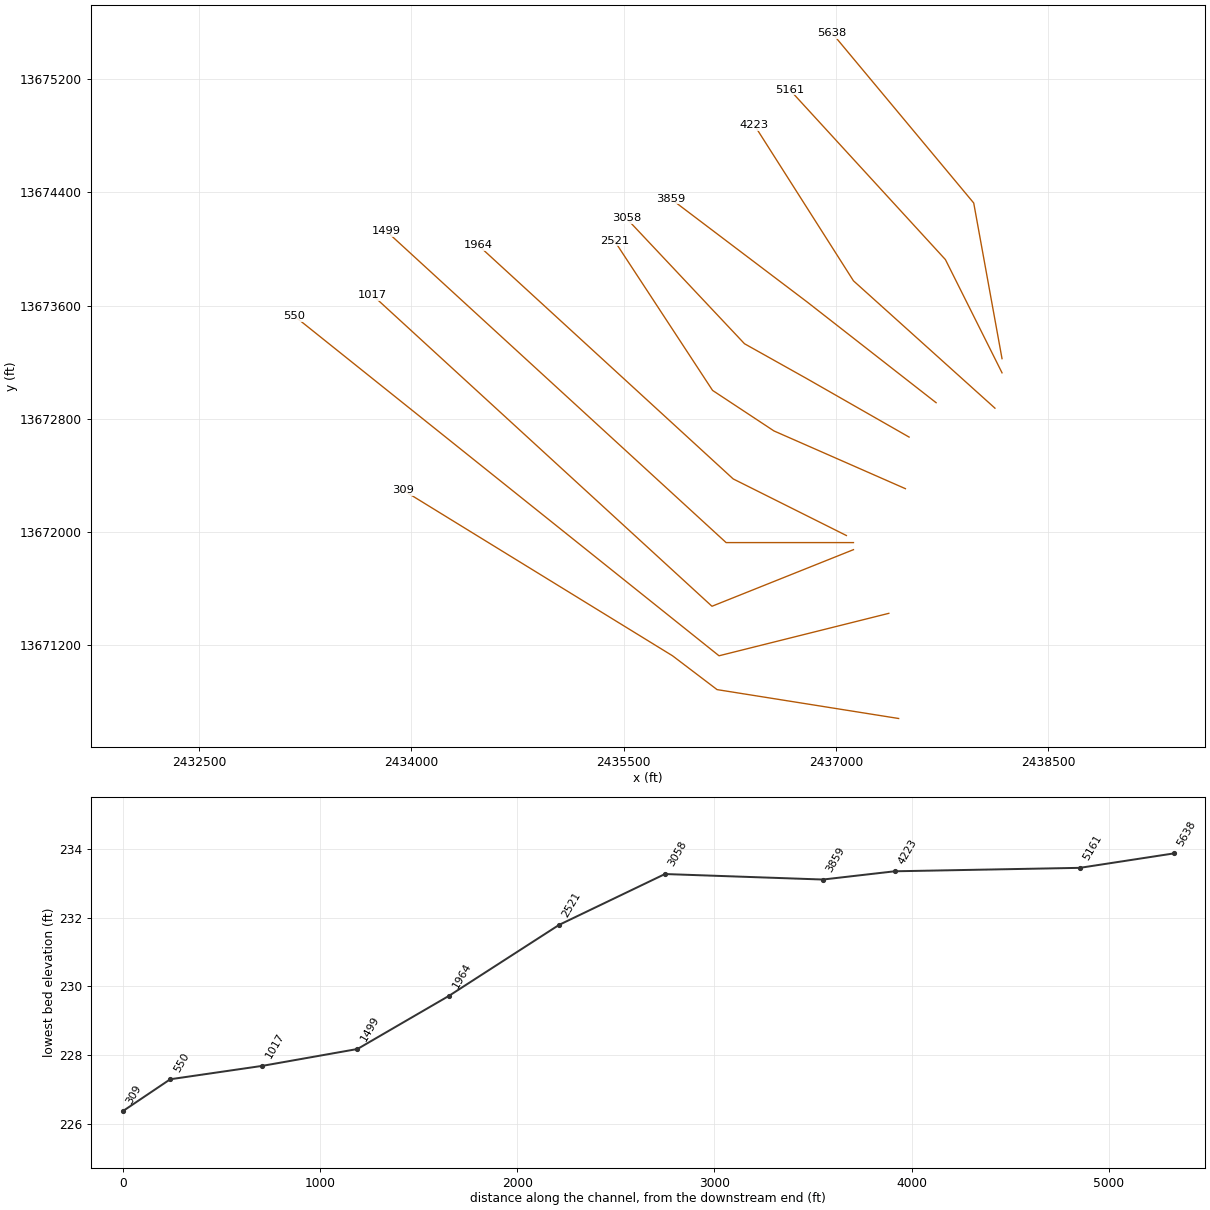
HEC-RAS study PUTNAM BRANCH.prj: PUTNAM BRANCH Base Level Engineering

--- PUTNAM BRANCH.g01 (geometry) --- (continued)

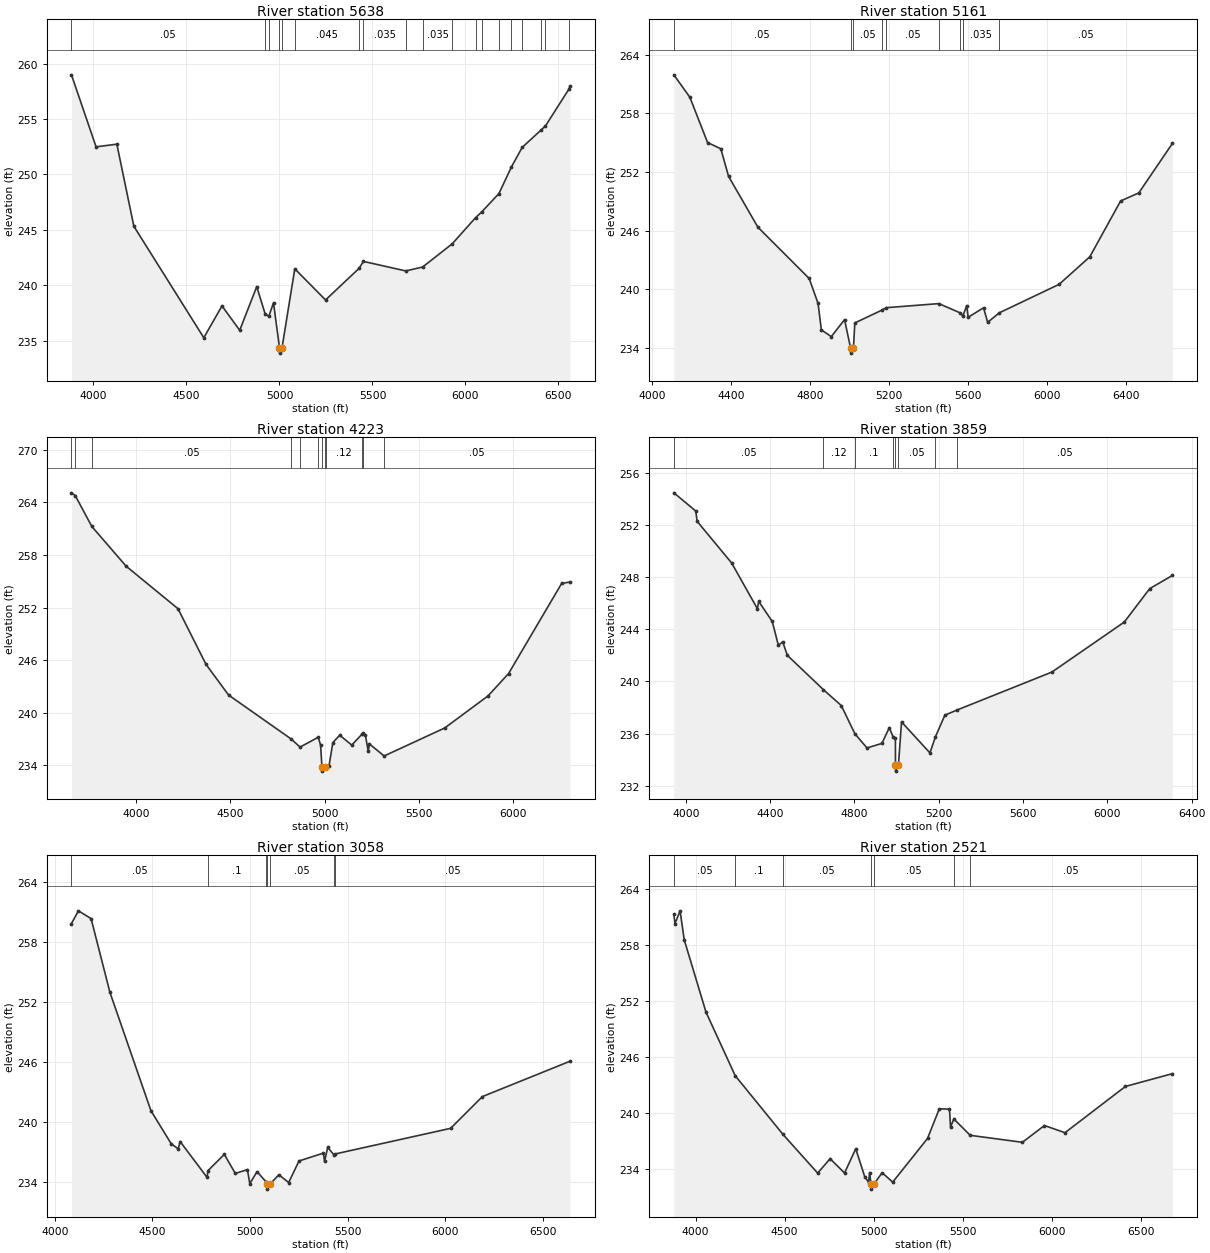
Type RM Length L Ch R = 1 ,5638    ,477,477,477
BEGIN DESCRIPTION:
PUTNAM BRANCH 10.0
END DESCRIPTION:
XS GIS Cut Line= 3
        2438175.     13673224.98        2437975.       13674325.
        2436975.       13675525.
#Sta/Elev= 30
  3881.7  258.99  4013.9  252.49  4125.7  252.73  4217.1  245.32  4593.2  235.26
    4691  238.13  4786.3  235.93  4877.8  239.87  4922.6  237.43  4942.4  237.18
    4968  238.41    5000  234.37  5000.5  233.87  5013.9  234.37  5082.4  241.48
  5247.7  238.67  5428.5  241.53  5451.3  242.15  5678.9  241.29  5769.7  241.64
    5929  243.74  6054.6   246.1  6088.1  246.63  6179.8  248.27  6247.3  250.68
    6305  252.44  6406.6  254.01  6430.2  254.38  6555.4  257.68  6561.8  257.95
#Mann= 19 ,-1 , 0
  3881.7     .05       0  4922.6     .12       0  4942.4     .05       0
    5000     .05       0  5013.9     .05       0  5082.4    .045       0
  5428.5     .05       0  5451.3    .035       0  5678.9     .05       0
  5769.7    .035       0    5929     .05       0  6054.6    .035       0
  6088.1     .05       0  6179.8    .035       0  6247.3     .05       0
    6305    .035       0  6406.6     .05       0  6430.2    .035       0
  6555.4     .05       0
Bank Sta=5000,5013.9
XS Rating Curve= 0 ,0
Exp/Cntr=0.3,0.1

Type RM Length L Ch R = 1 ,5161    ,938,938,938
BEGIN DESCRIPTION:
PUTNAM BRANCH 9.0
END DESCRIPTION:
XS GIS Cut Line= 3
      2438175.01     13673124.97        2437775.       13673925.
      2436675.03     13675124.97
#Sta/Elev= 30
  4111.9  261.94    4193  259.64  4282.4  255.01  4349.5  254.37  4388.6  251.55
  4536.8  246.35  4796.7  241.09  4841.5  238.54  4858.2  235.83  4908.5  235.14
  4975.6  236.88  5006.4  233.95  5006.9  233.45  5020.5  233.95  5027.6  236.54
  5165.4  237.86  5185.8   238.1  5452.6  238.52  5560.8  237.57  5574.1  237.25
  5593.7  238.31  5601.1  237.12  5678.8  238.09  5699.8   236.6  5758.9  237.58
  6061.1  240.49  6216.5  243.31  6372.5  249.03  6464.4  249.85  6634.2  254.91
#Mann= 9 ,-1 , 0
  4111.9     .05       0  5006.4     .05       0  5020.5     .05       0
  5165.4     .12       0  5185.8     .05       0  5452.6    .045       0
  5560.8     .05       0  5574.1    .035       0  5758.9     .05       0
Bank Sta=5006.4,5020.5
XS Rating Curve= 0 ,0
Exp/Cntr=0.3,0.1

Type RM Length L Ch R = 1 ,4223    ,364,364,364
BEGIN DESCRIPTION:
PUTNAM BRANCH 7.0
END DESCRIPTION:
XS GIS Cut Line= 3
      2438124.97     13672875.03        2437125.       13673775.
      2436424.98     13674875.03
#Sta/Elev= 30
  3655.2  265.08  3675.5  264.76  3763.2  261.25  3945.5  256.72  4221.3  251.87
  4370.1  245.53  4490.4  242.02  4823.8     237    4870  236.09  4966.5  237.21
  4979.2  236.32  4986.3  233.85  4986.8  233.35  5000.5  233.85  5008.1  233.87
  5023.4  233.89  5044.5  236.61    5081  237.45  5144.5  236.32    5200  237.58
  5202.5  237.66  5217.3  237.46  5232.5  235.59  5238.4  236.45  5317.1  235.08
  5638.9  238.27  5869.2  241.93  5978.4  244.48  6260.3  254.75  6304.4  254.91
#Mann= 12 ,-1 , 0
  3655.2     .05       0  3675.5    .035       0  3763.2     .05       0
  4823.8     .12       0    4870      .1       0  4966.5     .05       0
  4986.3     .05       0  5000.5     .05       0  5008.1     .12       0
    5200     .05       0  5202.5    .035       0  5317.1     .05       0
Bank Sta=4986.3,5000.5
XS Rating Curve= 0 ,0
Exp/Cntr=0.3,0.1

Type RM Length L Ch R = 1 ,3859    ,801,801,801
BEGIN DESCRIPTION:
B20125
END DESCRIPTION:
XS GIS Cut Line= 3
      2437709.13     13672913.71      2436797.69     13673625.51
      2435834.14     13674354.68
#Sta/Elev= 30
  3943.6  254.49  4047.6  253.09    4054   252.3  4217.7   249.1  4339.8  245.59
  4346.1  246.15  4410.3  244.61  4439.3  242.78  4460.1  243.04  4481.7  242.01
  4652.3  239.38  4737.8  238.15  4802.4  235.98  4859.8  234.89  4930.4  235.24
  4965.7  236.45  4983.8  235.73  4994.6  235.62  4994.9  233.61  4995.4  233.11
  5009.1  233.61  5023.6  236.89  5158.5  234.51  5184.6  235.75  5229.3  237.41
  5286.2   237.8    5737  240.72  6080.3  244.56    6201  247.13  6308.4  248.14
#Mann= 8 ,-1 , 0
  3943.6     .05       0  4652.3     .12       0  4802.4      .1       0
  4983.8     .05       0  4994.9     .05       0  5009.1     .05       0
  5184.6    .035       0  5286.2     .05       0
Bank Sta=4994.9,5009.1
XS Rating Curve= 0 ,0
Exp/Cntr=0.3,0.1

Type RM Length L Ch R = 1 ,3058    ,537,537,537
BEGIN DESCRIPTION:
B20124
END DESCRIPTION:
XS GIS Cut Line= 4
      2437518.16     13672670.66      2436789.01     13673087.31
      2436354.98     13673330.37      2435521.68     13674215.75
#Sta/Elev= 30
  4085.2  259.88  4120.9  261.15  4185.7  260.37  4282.2  252.98  4492.4  241.12
  4595.6  237.83    4632   237.3  4641.7  238.04  4779.9  234.44  4784.2  235.12
  4868.1  236.75  4924.4  234.84  4986.5  235.23  4998.4  233.82  5035.7  235.02
  5083.7  233.96  5087.9  233.77  5088.4  233.27  5102.1  233.77  5147.4  234.71
  5197.7  233.93  5250.5  236.09  5375.8  236.88  5381.5  236.04  5397.5  237.46
  5429.3  236.71  5435.1  236.79  6027.1  239.36  6189.7  242.54  6638.3  246.08
#Mann= 7 ,-1 , 0
  4085.2     .05       0  4784.2      .1       0  5083.7     .05       0
  5087.9     .05       0  5102.1     .05       0  5429.3    .035       0
  5435.1     .05       0
Bank Sta=5087.9,5102.1
XS Rating Curve= 0 ,0
Exp/Cntr=0.3,0.1

Type RM Length L Ch R = 1 ,2521    ,557,557,557
BEGIN DESCRIPTION:
B20123
END DESCRIPTION:
XS GIS Cut Line= 4
      2437492.14     13672306.06      2436563.31     13672714.05
      2436129.29     13673000.51      2435434.86     13674059.52
#Sta/Elev= 30
  3877.8  261.27  3883.9  260.25  3912.7  261.63    3936  258.53  4058.3  250.77
  4222.6  243.95  4491.2  237.65  4685.8  233.51  4755.9  235.05  4836.9  233.52
  4899.7  236.12  4950.2  233.13  4971.9  232.53  4977.9  233.57  4985.7  232.29
  4986.2  231.79  5000.2  232.29  5048.3  233.55  5107.3  232.54    5303  237.22
  5369.3   240.4  5426.5  240.37  5432.4  238.46  5451.1  239.31    5543  237.56
  5836.3  236.81  5959.9  238.61  6075.4  237.84  6415.1   242.8  6678.7  244.17
#Mann= 7 ,-1 , 0
  3877.8     .05       0  4222.6      .1       0  4491.2     .05       0
  4985.7     .05       0  5000.2     .05       0  5451.1    .035       0
    5543     .05       0
Bank Sta=4985.7,5000.2
XS Rating Curve= 0 ,0
Exp/Cntr=0.3,0.1

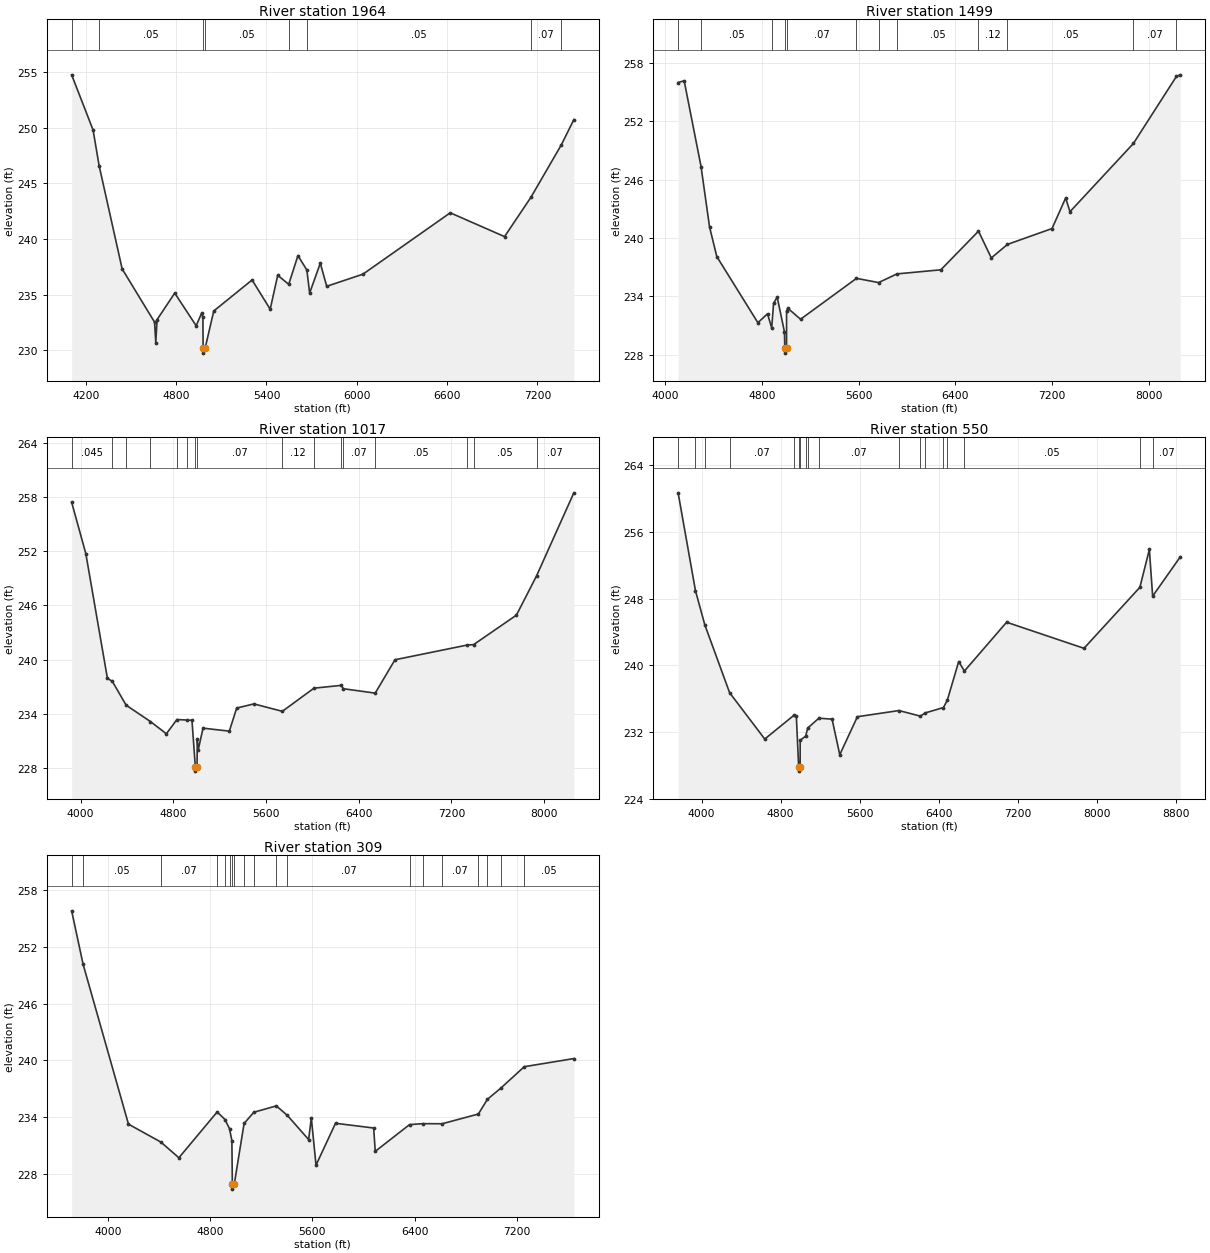
Type RM Length L Ch R = 1 ,1964    ,465,465,465
BEGIN DESCRIPTION:
PUTNAM BRANCH 4.0
END DESCRIPTION:
XS GIS Cut Line= 3
        2437075.       13671975.        2436275.       13672375.
      2434475.04     13674024.97
#Sta/Elev= 30
  4105.6  254.76  4248.1  249.79  4287.9   246.6    4441  237.31  4656.2  232.52
  4664.6  230.68    4673  232.74  4790.4  235.13  4932.9  232.19  4969.3  233.33
  4977.7  232.96  4978.8  230.23  4979.3  229.73  4993.3  230.23  5049.7  233.52
  5304.3  236.31  5424.6  233.68  5474.5  236.73  5547.7  235.92  5608.9   238.5
  5668.3   237.2  5686.6  235.13  5757.5  237.82  5800.1  235.74  6040.6  236.83
  6620.8  242.35  6981.5  240.21  7156.9  243.75  7358.6  248.46  7441.8  250.73
#Mann= 8 ,-1 , 0
  4105.6    .045       0  4287.9     .05       0  4978.8     .05       0
  4993.3     .05       0  5547.7    .035       0  5668.3     .05       0
  7156.9     .07       0  7358.6     .05       0
Bank Sta=4978.8,4993.3
XS Rating Curve= 0 ,0
Exp/Cntr=0.3,0.1

Type RM Length L Ch R = 1 ,1499    ,482,482,482
BEGIN DESCRIPTION:
PUTNAM BRANCH 3.0
END DESCRIPTION:
XS GIS Cut Line= 3
      2437124.96       13671925.        2436225.       13671925.
      2433825.01     13674124.99
#Sta/Elev= 30
  4104.7  255.98  4154.7  256.16  4294.4  247.35  4364.7  241.15  4424.7   238.1
  4764.7  231.31  4844.7  232.22    4879  230.77  4894.7   233.3  4924.7  233.93
  4984.7  230.36  4987.3  228.68  4987.8  228.18    5002  228.68  5002.2   232.5
  5011.7   232.8  5117.8  231.66  5580.7  235.86  5763.8  235.43  5916.2  236.32
  6278.9  236.74  6590.4  240.71  6696.4  237.96  6830.3  239.35  7198.9  240.98
  7311.7  244.12  7347.5  242.71  7872.4  249.72  8228.4  256.61  8260.4  256.77
#Mann= 12 ,-1 , 0
  4104.7    .045       0  4294.4     .05       0    4879     .07       0
  4987.3     .05       0    5002     .07       0  5580.7     .12       0
  5763.8    .035       0  5916.2     .05       0  6590.4     .12       0
  6830.3     .05       0  7872.4     .07       0  8228.4     .05       0
Bank Sta=4987.3,5002
XS Rating Curve= 0 ,0
Exp/Cntr=0.3,0.1

Type RM Length L Ch R = 1 ,1017    ,467,467,467
BEGIN DESCRIPTION:
PUTNAM BRANCH 2.0
END DESCRIPTION:
XS GIS Cut Line= 3
      2437125.03     13671875.01        2436125.       13671475.
      2433725.02     13673674.98
#Sta/Elev= 30
  3923.4  257.41  4045.9  251.72  4231.7  237.96    4275   237.6  4393.5  234.98
  4603.1  233.17  4740.6  231.82  4831.5  233.39  4916.4  233.34  4961.4  233.31
  4990.4  228.19  4990.9  227.69  5005.2  228.19  5007.6  231.24  5014.3  229.97
  5056.9  232.44  5283.8  232.11  5347.3  234.66  5495.9  235.12  5741.2   234.3
  6014.3  236.86    6251  237.17  6266.8   236.8  6542.4  236.31  6713.1     240
  7337.8  241.63    7391  241.67  7760.8  244.93  7934.1  249.26  8256.2  258.45
#Mann= 16 ,-1 , 0
  3923.4    .045       0    4275     .05       0  4393.5    .035       0
  4603.1     .07       0  4831.5     .12       0  4916.4     .07       0
  4990.4     .05       0  5005.2     .07       0  5741.2     .12       0
  6014.3    .035       0    6251     .05       0  6266.8     .07       0
  6542.4     .05       0  7337.8     .07       0    7391     .05       0
  7934.1     .07       0
Bank Sta=4990.4,5005.2
XS Rating Curve= 0 ,0
Exp/Cntr=0.3,0.1

Type RM Length L Ch R = 1 ,550     ,241,241,241
BEGIN DESCRIPTION:
PUTNAM BRANCH 1.0
END DESCRIPTION:
XS GIS Cut Line= 3
        2437375.       13671425.        2436175.       13671125.
      2433175.01     13673524.99
#Sta/Elev= 30
  3763.5   260.7  3938.9  248.96  4033.1  244.87  4284.4  236.71  4639.7  231.15
  4936.5  234.02  4959.2  233.89  4982.7   227.8  4983.2   227.3  4997.5   227.8
  4997.9  230.99  5053.9  231.51  5073.9  232.47    5187  233.65  5320.6  233.54
  5398.2  229.27  5576.7  233.83  5997.3  234.57  6213.4   233.9  6263.8  234.29
  6446.9  234.93  6485.4  235.79  6601.2  240.45  6658.9  239.31  7085.5  245.17
  7868.2  242.04  8433.5  249.36  8529.4   253.9  8562.5   248.3  8842.3  253.02
#Mann= 18 ,-1 , 0
  3763.5     .05       0  3938.9    .045       0  4033.1     .05       0
  4284.4     .07       0  4936.5     .12       0  4982.7     .05       0
  4997.5     .12       0  5053.9     .07       0  5073.9     .12       0
    5187     .07       0  5997.3     .12       0  6213.4      .1       0
  6263.8    .035       0  6446.9     .07       0  6485.4    .035       0
  6658.9     .05       0  8433.5    .035       0  8562.5     .07       0
Bank Sta=4982.7,4997.5
XS Rating Curve= 0 ,0
Exp/Cntr=0.3,0.1

Type RM Length L Ch R = 1 ,309     ,0,0,0
BEGIN DESCRIPTION:
B20122
END DESCRIPTION:
XS GIS Cut Line= 4
      2437444.35     13670681.77      2436161.13     13670885.92
      2435846.14     13671125.08       2433939.4     13672297.11
#Sta/Elev= 30
  3714.7  255.83  3804.2  250.18  4159.6  233.25  4413.6  231.35  4554.5  229.69
  4854.3  234.54  4915.7  233.74  4951.1  232.76  4969.6   231.5  4973.2  226.87
  4973.7  226.37    4988  226.87  5065.1  233.32  5141.9  234.51  5317.7  235.18
    5403  234.19  5570.5  231.62  5591.8   233.9  5628.5  228.91  5781.2  233.34
    6080  232.84  6092.4  230.37    6361   233.2  6465.4   233.3  6616.4  233.29
    6900  234.32  6970.4  235.87  7079.7  237.11  7259.4  239.33  7647.7  240.19
#Mann= 19 ,-1 , 0
  3714.7     .07       0  3804.2     .05       0  4413.6     .07       0
  4854.3     .12       0  4915.7     .07       0  4951.1     .12       0
  4973.2     .05       0    4988     .12       0  5065.1     .07       0
  5141.9     .12       0  5317.7      .1       0    5403     .07       0
    6361      .1       0  6465.4    .035       0  6616.4     .07       0
    6900    .035       0  6970.4     .05       0  7079.7    .035       0
  7259.4     .05       0
Bank Sta=4973.2,4988
XS Rating Curve= 0 ,0
Exp/Cntr=0.3,0.1

Chan Stop Cuts=-1
Use User Specified Reach Order=0
Composite Channel Slope=5