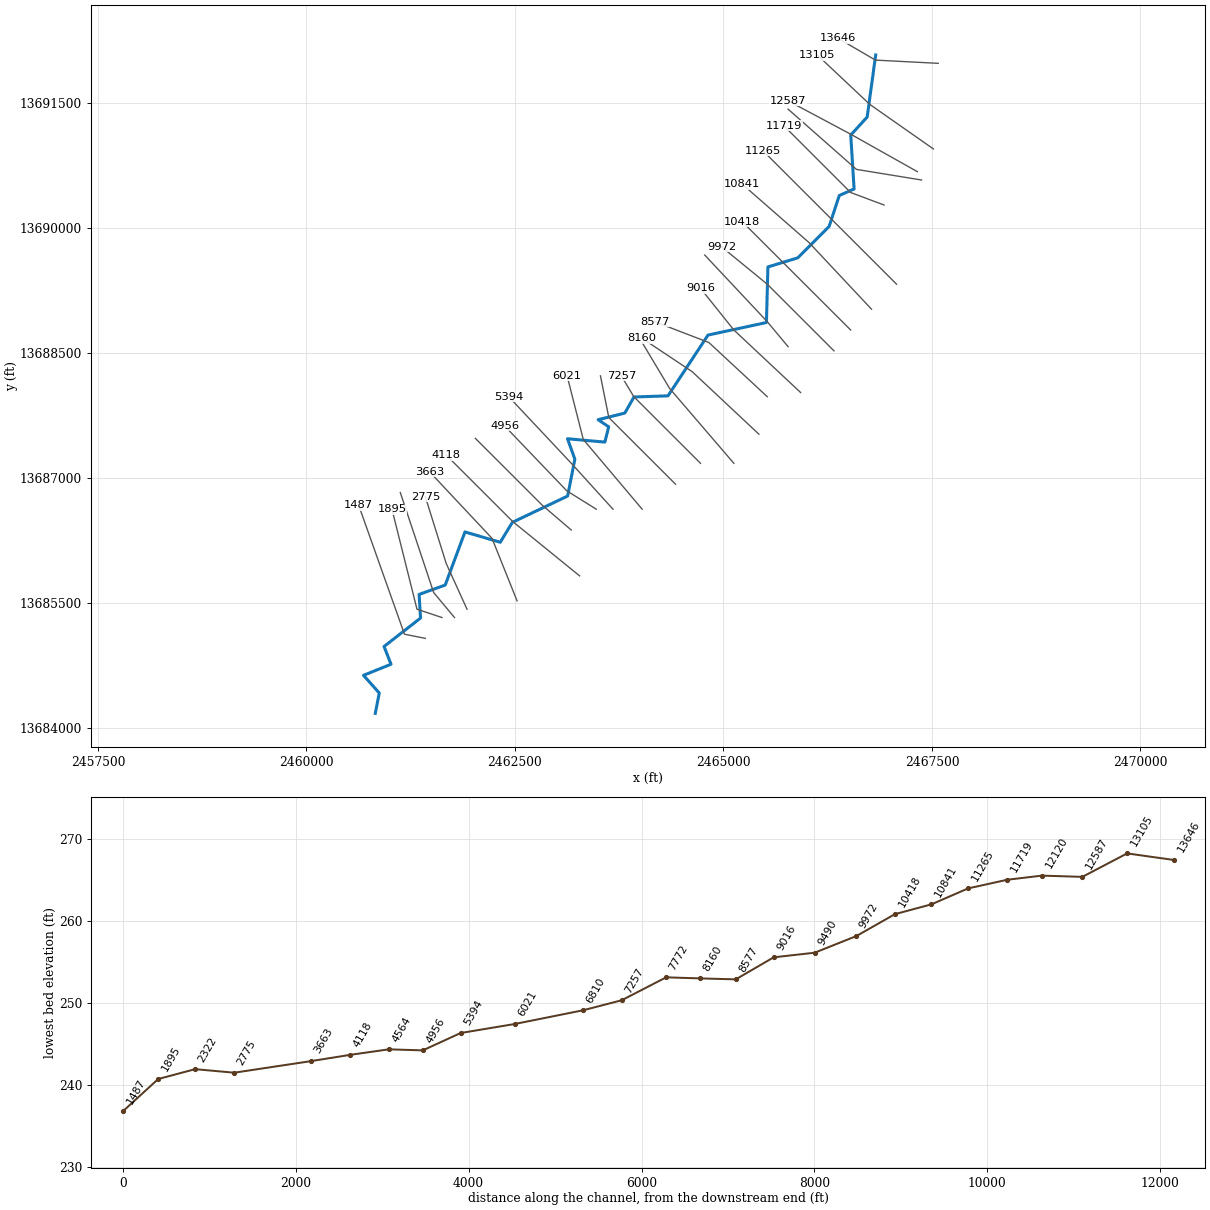
--- SADBERRY CREEK.prj (project) ---

Proj Title=SADBERRY CREEK Base Level Engineering
Current Plan=p01
Default Exp/Contr=0.3,0.1
English Units
Geom File=g01
Flow File=f01
Plan File=p01
Y Axis Title=Elevation
X Axis Title(PF)=Main Channel Distance
X Axis Title(XS)=Station
BEGIN DESCRIPTION:
SADBERRY CREEK
END DESCRIPTION:
DSS Export Rating Curves= 0
DSS Export Rating Curve Sorted= 0
DSS Export Volume Flow Curves= 0
DXF OffsetX= 0
DXF OffsetY= 0
DXF ScaleX= 1
DXF ScaleY= 10

--- SADBERRY CREEK.p01 (plan) ---

Plan Title=Multiple Run
Short Identifier=Multiple
Geom File=g01
Flow File=f01
Subcritical Flow
K Sum by GR= 0
Std Step Tol= 0.01
Critical Tol= 0.01
Num of Std Step Trials= 20
Max Error Tol= 0.3
Flow Tol Ratio= 0.001
Split Flow NTrial= 30
Split Flow Tol= 0.02
Split Flow Ratio= 0.02
Log Output Level= 0
Friction Slope Method= 1
Unsteady Friction Slope Method= 2
Unsteady Bridges Friction Slope Method= 1
Parabolic Critical Depth
Global Vel Dist=  1 , 1 , 1
Global Log Level= 0
CheckData=True
Encroach Param= -1, 0, 0, 0
BEGIN DESCRIPTION:
Multiple Run
END DESCRIPTION:

--- SADBERRY CREEK.f01 (steady flow) ---

Flow Title=Multiple
Number of Profiles=7
Profile Names=10-year,25-year,50-year,1pct_min,100-year,1pct_plu,500-year
River Rch & RM= SADBERRY CREEK,Reach-1,13646
     871    1415    1909    1246    2485    4959    4173
River Rch & RM= SADBERRY CREEK,Reach-1,12587
    1186    1954    2661    1750    3492    6968    5960
River Rch & RM= SADBERRY CREEK,Reach-1,8160
    1355    2236    3049    2005    4001    7984    6832
Boundary for River Rch & Prof#=SADBERRY CREEK,Reach-1,1
Up Type=0
Dn Type=3
Dn Slope=0.005
Boundary for River Rch & Prof#=SADBERRY CREEK,Reach-1,2
Up Type=0
Dn Type=3
Dn Slope=0.005
Boundary for River Rch & Prof#=SADBERRY CREEK,Reach-1,3
Up Type=0
Dn Type=3
Dn Slope=0.005
Boundary for River Rch & Prof#=SADBERRY CREEK,Reach-1,4
Up Type=0
Dn Type=3
Dn Slope=0.005
Boundary for River Rch & Prof#=SADBERRY CREEK,Reach-1,5
Up Type=0
Dn Type=3
Dn Slope=0.005
Boundary for River Rch & Prof#=SADBERRY CREEK,Reach-1,6
Up Type=0
Dn Type=3
Dn Slope=0.005
Boundary for River Rch & Prof#=SADBERRY CREEK,Reach-1,7
Up Type=0
Dn Type=3
Dn Slope=0.005

--- SADBERRY CREEK.g01 (geometry) ---

Geom Title=Existing Conditions
Program Version=4.10

River Reach=SADBERRY CREEK  ,Reach-1
Reach XY= 30
        2466825.       13692075.      2466723.04     13691330.89
      2466526.05     13691114.57      2466566.17       13690468.
       2466388.2     13690388.73      2466267.25     13690018.55
      2465891.75     13689641.46       2465532.8     13689531.83
      2465514.94     13688864.88      2464814.61     13688714.24
      2464334.71     13687985.18      2463926.46     13687971.46
      2463816.85     13687778.37      2463497.15     13687698.77
      2463623.51     13687613.46      2463577.71     13687430.28
      2463130.02     13687470.08      2463217.92       13687225.
      2463131.44     13686783.02      2462468.77     13686467.18
      2462323.38      13686228.1      2461900.53     13686352.16
      2461663.77     13685714.98      2461350.59     13685602.31
      2461367.62     13685318.67      2460930.08     13684977.31
      2461014.08     13684764.57      2460683.95     13684631.69
      2460872.95     13684419.15        2460825.       13684175.

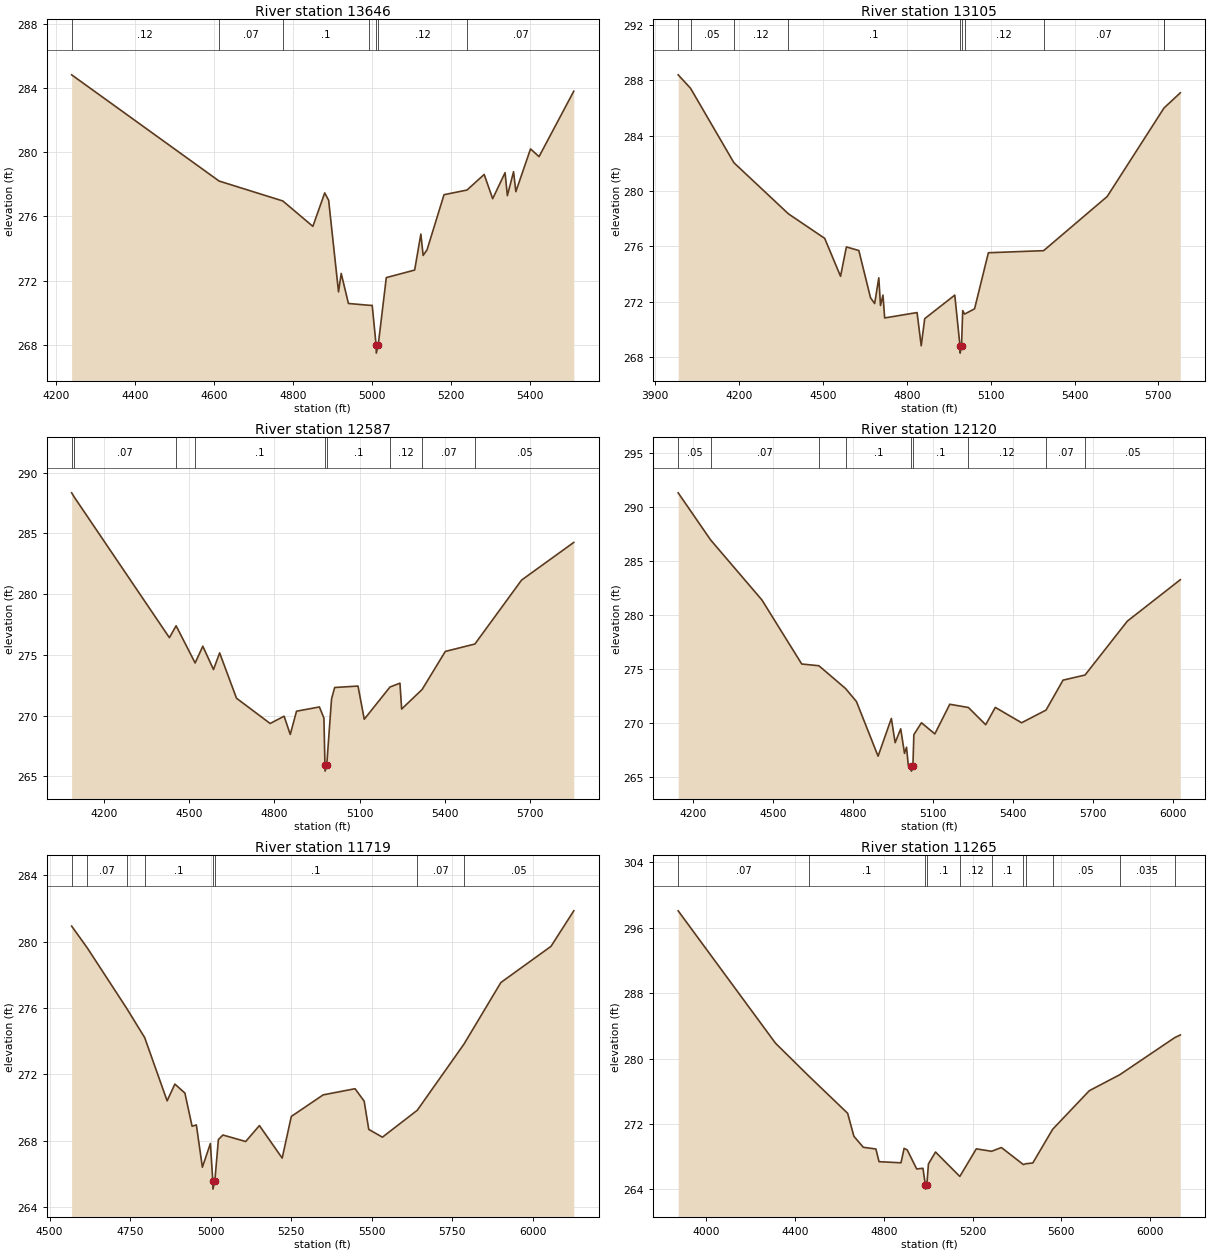
Type RM Length L Ch R = 1 ,13646   ,541,541,541
BEGIN DESCRIPTION:
SADBERRY CREEK 26.0
END DESCRIPTION:
XS GIS Cut Line= 3
      2467575.04       13691975.      2466822.28     13692013.83
      2466375.01       13692275.
#Sta/Elev= 30
  4238.4  284.81  4611.8   278.2  4773.2  276.96  4849.3  275.38  4879.3  277.46
  4889.3     277  4914.3   271.3  4921.1  272.45  4939.4  270.58  4990.5  270.47
  4999.6  270.46  5009.5  267.99    5010  267.49  5014.8  267.99  5035.3  272.19
  5107.1  272.66  5122.8   274.9  5128.6  273.57  5138.5  273.92  5181.5  277.35
  5239.7  277.64  5283.2  278.61  5304.7   277.1  5336.1  278.72  5341.9  277.29
  5357.6  278.78  5363.4  277.54  5400.6   280.2  5422.1  279.72  5510.1  283.79
#Mann= 7 ,-1 , 0
  4238.4     .12       0  4611.8     .07       0  4773.2      .1       0
  4990.5     .12       0  5009.5     .05       0  5014.8     .12       0
  5239.7     .07       0
Bank Sta=5009.5,5014.8
XS Rating Curve= 0 ,0
Exp/Cntr=0.3,0.1

Type RM Length L Ch R = 1 ,13105   ,518,518,518
BEGIN DESCRIPTION:
SADBERRY CREEK 25.0
END DESCRIPTION:
XS GIS Cut Line= 3
      2467517.02     13690947.79       2466756.4     13691480.83
      2466125.01     13692074.99
#Sta/Elev= 30
  3982.5  288.39  4026.7  287.42  4181.9  282.04  4376.8  278.35  4506.5  276.58
  4563.2  273.84  4584.1  275.96  4628.6   275.7  4670.4  272.29  4685.2  271.87
    4700  273.73  4706.1  271.73  4714.9  272.48    4721  270.83  4836.9  271.22
  4851.7  268.82  4864.2  270.78  4971.7  272.48  4990.5  268.79  4990.9  268.29
  4995.8  268.79  5000.1  271.36  5006.8  271.11  5042.5  271.49  5091.9  275.54
  5289.4  275.69  5516.7   279.6  5718.3  285.94  5719.2  285.98  5778.3  287.09
#Mann= 10 ,-1 , 0
  3982.5     .07       0  4026.7     .05       0  4181.9     .12       0
  4376.8      .1       0  4990.5     .05       0  4995.8      .1       0
  5006.8     .12       0  5289.4     .07       0  5718.3     .12       0
  5719.2     .07       0
Bank Sta=4990.5,4995.8
XS Rating Curve= 0 ,0
Exp/Cntr=0.3,0.1

Type RM Length L Ch R = 1 ,12587   ,467,467,467
BEGIN DESCRIPTION:
SADBERRY CREEK 24.0
END DESCRIPTION:
XS GIS Cut Line= 3
      2467325.01       13690675.        2466525.       13691125.
      2465774.99     13691525.01
#Sta/Elev= 30
    4086  288.33  4095.2  287.98  4430.2  276.41  4453.8  277.39  4520.8  274.33
  4547.8  275.71  4585.4  273.79  4607.1  275.16  4666.4  271.43  4784.9  269.35
    4834  269.95  4855.7  268.45  4877.7  270.36  4958.3  270.71  4974.2   269.8
  4977.8  265.93  4978.3  265.43  4984.1  265.93    5001  271.36    5012  272.31
  5094.2  272.43  5116.2   269.7  5206.8  272.35  5241.9  272.67  5247.9  270.54
    5320  272.15  5401.6  275.28  5505.8  275.89  5670.1  281.15  5853.9  284.25
#Mann= 9 ,-1 , 0
    4086     .05       0  4095.2     .07       0  4453.8     .12       0
  4520.8      .1       0  4977.8     .05       0  4984.1      .1       0
  5206.8     .12       0    5320     .07       0  5505.8     .05       0
Bank Sta=4977.8,4984.1
XS Rating Curve= 0 ,0
Exp/Cntr=0.3,0.1

Type RM Length L Ch R = 1 ,12120   ,401,401,401
BEGIN DESCRIPTION:
SADBERRY CREEK 23.0
END DESCRIPTION:
XS GIS Cut Line= 3
      2467374.99       13690575.       2466594.7     13690702.28
      2465775.01     13691424.99
#Sta/Elev= 30
  4143.6   291.3  4265.2  286.95  4457.7   281.4    4607  275.48  4671.4  275.32
  4771.6  273.21  4812.3  272.01  4893.4  266.96  4943.2  270.45  4957.4  268.21
  4978.3  269.49  4992.5  267.22  5000.1  267.79  5006.7  266.13  5017.8  266.08
  5018.3  265.58  5024.1  266.08  5027.6  268.95  5056.1  270.05  5106.3  269.02
  5162.3  271.76  5232.3  271.46    5297  269.87  5333.1  271.47  5431.7  270.05
  5523.3  271.22  5587.3  273.99  5669.6  274.46  5828.3  279.44    6027  283.27
#Mann= 9 ,-1 , 0
  4143.6     .05       0  4265.2     .07       0  4671.4     .12       0
  4771.6      .1       0  5017.8     .05       0  5024.1      .1       0
  5232.3     .12       0  5523.3     .07       0  5669.6     .05       0
Bank Sta=5017.8,5024.1
XS Rating Curve= 0 ,0
Exp/Cntr=0.3,0.1

Type RM Length L Ch R = 1 ,11719   ,454,454,454
BEGIN DESCRIPTION:
SADBERRY CREEK 22.0
END DESCRIPTION:
XS GIS Cut Line= 3
      2466924.99       13690275.        2466525.       13690425.
      2465724.98     13691225.02
#Sta/Elev= 30
  4568.6  280.93  4617.7   279.6  4739.6  275.97  4795.3  274.21    4865   270.4
    4889  271.41  4920.1  270.87  4942.4  268.87  4955.7  268.95  4974.4   266.4
  4999.3  267.83  5006.7  265.58  5007.2  265.08  5013.1  265.58  5024.1  268.07
  5038.2  268.34  5108.9  267.95  5151.4  268.91  5222.1  266.95  5250.4  269.46
  5349.3  270.76  5448.3  271.13  5476.6  270.38  5490.8  268.68  5533.2  268.21
  5641.3  269.83  5786.4  273.82  5900.9  277.53  6056.5  279.71  6127.2  281.85
#Mann= 8 ,-1 , 0
  4568.6     .12       0  4617.7     .07       0  4739.6     .12       0
  4795.3      .1       0  5006.7     .05       0  5013.1      .1       0
  5641.3     .07       0  5786.4     .05       0
Bank Sta=5006.7,5013.1
XS Rating Curve= 0 ,0
Exp/Cntr=0.3,0.1

Type RM Length L Ch R = 1 ,11265   ,424,424,424
BEGIN DESCRIPTION:
SADBERRY CREEK 21.0
END DESCRIPTION:
XS GIS Cut Line= 3
      2467075.01     13689324.99        2466275.       13690125.
      2465474.97     13690925.03
#Sta/Elev= 30
    3873  298.07  4311.4  281.88  4462.6  277.83  4636.7   273.3    4665  270.48
  4707.4  269.14    4764  268.93  4778.1  267.38  4877.1  267.24  4891.2  269.01
  4905.4  268.81  4947.8  266.49  4976.1  266.57    4987  264.52  4987.5  264.02
  4993.5  264.52  5000.8   267.1  5032.7  268.56  5142.2  265.57  5216.5  268.95
  5285.4  268.65  5329.6  269.11  5428.7  267.02  5438.4  267.12  5471.1  267.22
  5560.5  271.34  5725.6  276.06  5863.1  278.02  6111.4  282.57  6135.8  282.88
#Mann= 11 ,-1 , 0
    3873     .07       0  4462.6      .1       0    4987     .05       0
  4993.5      .1       0  5142.2     .12       0  5285.4      .1       0
  5428.7     .12       0  5438.4     .07       0  5560.5     .05       0
  5863.1    .035       0  6111.4     .05       0
Bank Sta=4987,4993.5
XS Rating Curve= 0 ,0
Exp/Cntr=0.3,0.1

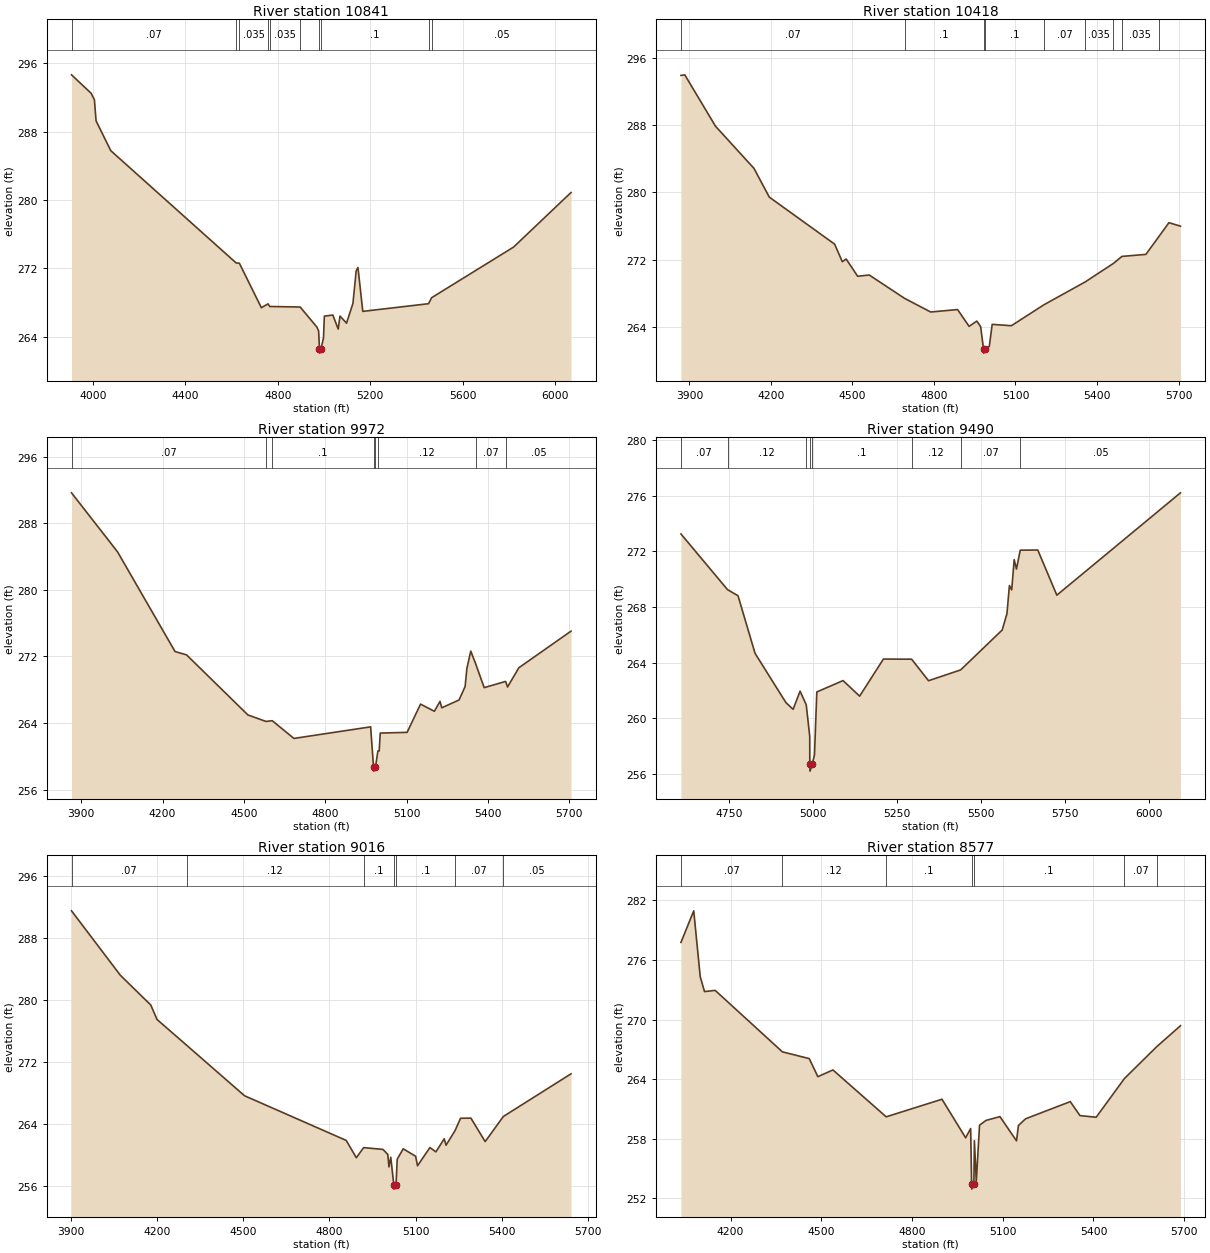
Type RM Length L Ch R = 1 ,10841   ,423,423,423
BEGIN DESCRIPTION:
SADBERRY CREEK 20.0
END DESCRIPTION:
XS GIS Cut Line= 3
        2466775.     13689024.99        2466025.       13689825.
      2465225.01       13690525.
#Sta/Elev= 30
  3908.3  294.67  3993.1  292.51  4007.2  291.76  4014.5  289.28    4078  285.79
  4620.1  272.64    4634  272.61  4729.1   267.4  4757.8  267.85  4765.5  267.54
  4896.9  267.48  4969.5  265.12  4976.8  264.67  4980.2  262.58  4980.7  262.08
    4987  262.58  4997.8  263.87  5001.5  266.41  5038.1  266.54  5061.4   264.9
    5069  266.42  5097.4  265.59    5125   267.9  5139.2  271.74  5146.8   272.1
  5167.7  266.97  5452.2  267.87  5465.3  268.57  5819.7   274.5  6067.9  280.89
#Mann= 10 ,-1 , 0
  3908.3     .07       0  4620.1      .1       0    4634    .035       0
  4757.8      .1       0  4765.5    .035       0  4896.9      .1       0
  4980.2     .05       0    4987      .1       0  5452.2     .12       0
  5465.3     .05       0
Bank Sta=4980.2,4987
XS Rating Curve= 0 ,0
Exp/Cntr=0.3,0.1

Type RM Length L Ch R = 1 ,10418   ,446,446,446
BEGIN DESCRIPTION:
SADBERRY CREEK 19.0
END DESCRIPTION:
XS GIS Cut Line= 3
      2466524.97     13688775.03        2465725.       13689575.
      2465225.02     13690074.98
#Sta/Elev= 30
  3868.7   293.9  3882.8  293.97  3995.9  287.86  4137.4  282.85  4193.9  279.43
  4434.3  273.84  4462.6  271.75  4476.8  272.07  4519.2  270.02  4561.6  270.17
  4691.9  267.39  4787.9  265.77  4886.9  266.06  4929.3  264.06  4957.6  264.69
  4971.7  264.03  4982.4  261.38  4982.9  260.88  4989.3  261.38  5003.6  261.67
  5014.2   264.3  5084.9  264.14  5205.8  266.65  5356.3  269.34  5460.6  271.55
  5491.7  272.38  5579.9  272.62  5627.1  274.71  5664.7  276.39  5707.1  275.98
#Mann= 9 ,-1 , 0
  3868.7     .07       0  4691.9      .1       0  4982.4     .05       0
  4989.3      .1       0  5205.8     .07       0  5356.3    .035       0
  5460.6     .07       0  5491.7    .035       0  5627.1     .07       0
Bank Sta=4982.4,4989.3
XS Rating Curve= 0 ,0
Exp/Cntr=0.3,0.1

Type RM Length L Ch R = 1 ,9972    ,482,482,482
BEGIN DESCRIPTION:
SADBERRY CREEK 18.0
END DESCRIPTION:
XS GIS Cut Line= 3
      2466324.98     13688525.02        2465525.       13689325.
      2464974.99     13689775.01
#Sta/Elev= 30
  3864.3  291.65    4034  284.56  4246.1  272.58  4288.5  272.18  4514.8  264.96
  4581.6  264.18  4604.5  264.27  4684.5  262.14  4967.4  263.53    4978  258.71
  4978.5  258.21  4985.1  258.71  4994.2  260.63  4998.9  260.63  5002.8  262.78
  5101.9  262.87  5151.4  266.26  5202.4   265.4  5223.2  266.59  5229.7  265.82
  5293.5  266.76  5315.8  268.38  5322.3  270.54  5336.6  272.63  5354.1  271.16
  5386.1  268.24  5465.2  268.99  5472.3  268.32  5513.9  270.63  5706.3  275.03
#Mann= 8 ,-1 , 0
  3864.3     .07       0  4581.6     .12       0  4604.5      .1       0
    4978     .05       0  4985.1      .1       0  4994.2     .12       0
  5354.1     .07       0  5465.2     .05       0
Bank Sta=4978,4985.1
XS Rating Curve= 0 ,0
Exp/Cntr=0.3,0.1

Type RM Length L Ch R = 1 ,9490    ,474,474,474
BEGIN DESCRIPTION:
SADBERRY CREEK 17.0
END DESCRIPTION:
XS GIS Cut Line= 3
      2465775.02     13688574.98        2465525.       13688875.
      2464775.02     13689674.98
#Sta/Elev= 30
  4605.7  273.26  4744.3  269.25  4775.6  268.81  4826.4  264.66  4918.1  261.12
  4939.6  260.63  4960.4  261.94  4978.7  260.96  4989.1   258.7  4989.4  256.68
  4989.9  256.18  4996.6  256.68  5003.3  257.36  5010.2  261.88  5088.3   262.7
  5137.7  261.58  5208.5  264.25  5292.5  264.24  5342.8  262.69  5438.5  263.47
  5562.1  266.34  5576.3  267.52  5583.6  269.54  5590.5  269.23  5597.8  271.41
  5604.6  270.73  5615.9  272.09  5668.1   272.1  5724.8  268.85  6092.8  276.22
#Mann= 8 ,-1 , 0
  4605.7     .07       0  4744.3     .12       0  4978.7      .1       0
  4989.4     .05       0  4996.6      .1       0  5292.5     .12       0
  5438.5     .07       0  5615.9     .05       0
Bank Sta=4989.4,4996.6
XS Rating Curve= 0 ,0
Exp/Cntr=0.3,0.1

Type RM Length L Ch R = 1 ,9016    ,439,439,439
BEGIN DESCRIPTION:
SADBERRY CREEK 16.0
END DESCRIPTION:
XS GIS Cut Line= 3
      2465925.03     13688024.97        2465125.       13688775.
      2464725.03     13689274.97
#Sta/Elev= 30
  3903.5  291.56  4073.3  283.24  4179.3  279.39  4200.8  277.53  4304.2  274.19
  4505.1  267.68  4858.7  261.91  4893.9  259.67  4919.2  260.98  4986.2  260.75
  5003.3  260.11  5007.3  258.49  5013.7  259.73  5024.4  256.12  5024.9  255.62
  5031.8  256.12  5036.1  259.49    5057  260.83  5100.2  259.86  5106.6  258.63
  5149.8  260.99  5170.6  260.43  5199.4  262.12  5205.8  261.29  5237.2  263.18
  5256.3  264.77  5292.3  264.79  5341.9  261.76  5405.1     265  5640.4  270.51
#Mann= 7 ,-1 , 0
  3903.5     .07       0  4304.2     .12       0  4919.2      .1       0
  5024.4     .05       0  5031.8      .1       0  5237.2     .07       0
  5405.1     .05       0
Bank Sta=5024.4,5031.8
XS Rating Curve= 0 ,0
Exp/Cntr=0.3,0.1

Type RM Length L Ch R = 1 ,8577    ,417,417,417
BEGIN DESCRIPTION:
SADBERRY CREEK 15.0
END DESCRIPTION:
XS GIS Cut Line= 3
      2465525.04     13687974.97        2464825.       13688625.
      2464175.02     13688874.99
#Sta/Elev= 30
  4035.8  277.77  4078.1  280.95  4099.6  274.31  4113.8  272.82    4149  272.94
  4371.3  266.75  4460.2  266.07  4488.5  264.25  4538.4  264.93  4714.5  260.21
    4899  261.98  4977.2   258.1  4993.8  259.03    4997  253.43  4997.5  252.93
  5004.4  253.43  5006.1   257.8  5012.5  253.72  5023.2  259.37  5044.7  259.85
  5090.7  260.23  5145.4  257.79  5151.8  259.34  5175.4  260.01  5323.2  261.74
  5355.4  260.33  5408.9  260.17  5502.4  264.07    5609  267.27  5687.5  269.38
#Mann= 7 ,-1 , 0
  4035.8     .07       0  4371.3     .12       0  4714.5      .1       0
    4997     .05       0  5004.4      .1       0  5502.4     .07       0
    5609    .035       0
Bank Sta=4997,5004.4
XS Rating Curve= 0 ,0
Exp/Cntr=0.3,0.1

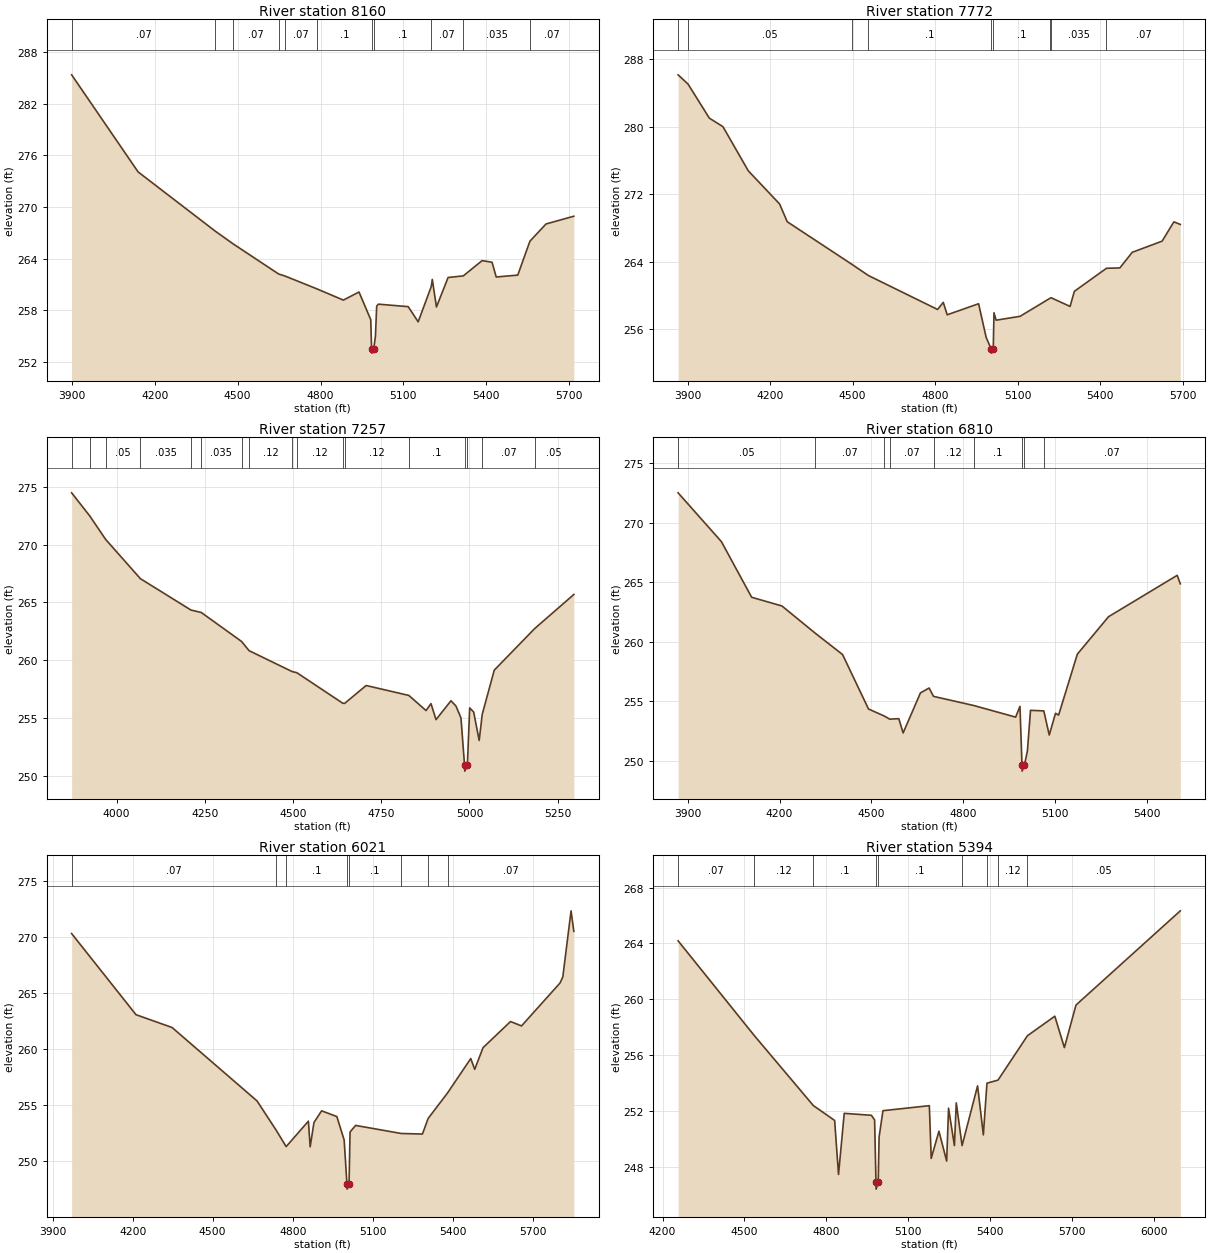
Type RM Length L Ch R = 1 ,8160    ,388,388,388
BEGIN DESCRIPTION:
SADBERRY CREEK 14.0
END DESCRIPTION:
XS GIS Cut Line= 3
      2465424.97     13687525.02        2464625.       13688275.
      2464024.97     13688675.02
#Sta/Elev= 30
  3899.2  285.33  4139.7  274.07  4419.3  267.19  4483.4  265.73  4648.3  262.23
  4671.7  261.99    4788  260.49  4882.7   259.2  4939.3  260.14  4981.8  256.93
  4984.8  253.55  4985.3  253.05  4992.5  253.55  4998.8  255.02  5003.3  258.49
  5009.3  258.73  5117.4  258.44  5153.5  256.68  5200.7  260.76  5204.6   261.6
  5219.6   258.4  5261.7  261.82  5316.8  262.01  5384.9  263.78  5420.9  263.59
  5435.9  261.88    5514   262.1  5557.9  266.03  5616.2  268.03  5716.9  268.93
#Mann= 11 ,-1 , 0
  3899.2     .07       0  4419.3     .12       0  4483.4     .07       0
  4648.3     .12       0  4671.7     .07       0    4788      .1       0
  4984.8     .05       0  4992.5      .1       0  5200.7     .07       0
  5316.8    .035       0  5557.9     .07       0
Bank Sta=4984.8,4992.5
XS Rating Curve= 0 ,0
Exp/Cntr=0.3,0.1

Type RM Length L Ch R = 1 ,7772    ,515,515,515
BEGIN DESCRIPTION:
SADBERRY CREEK 13.0
END DESCRIPTION:
XS GIS Cut Line= 3
      2465125.03     13687174.97      2464354.88     13688073.19
      2464024.99     13688625.02
#Sta/Elev= 30
  3865.8  286.14    3902  285.04  3979.4  281.01  4028.8     280    4121  274.77
  4234.7  270.85  4262.6  268.74  4497.6   263.7  4557.8  262.37  4809.2  258.35
    4830  259.19  4844.3  257.72  4958.4  259.03  4985.9  255.05    5004  253.68
  5004.5  253.18  5011.7  253.68  5014.4  257.96  5022.1  257.08  5109.3  257.54
  5218.3  259.68  5222.1  259.74  5291.1  258.71  5306.7   260.5  5423.5  263.23
  5472.1  263.27  5517.1  265.12  5625.7  266.44  5668.6  268.73  5691.9  268.42
#Mann= 9 ,-1 , 0
  3865.8     .07       0    3902     .05       0  4497.6     .07       0
  4557.8      .1       0    5004     .05       0  5011.7      .1       0
  5218.3     .07       0  5222.1    .035       0  5423.5     .07       0
Bank Sta=5004,5011.7
XS Rating Curve= 0 ,0
Exp/Cntr=0.3,0.1

Type RM Length L Ch R = 1 ,7257    ,447,447,447
BEGIN DESCRIPTION:
SADBERRY CREEK 12.0
END DESCRIPTION:
XS GIS Cut Line= 3
      2464724.99     13687175.01        2463925.       13687975.
      2463775.01     13688224.99
#Sta/Elev= 30
  3872.9   274.5  3924.4  272.49  3969.3  270.46  4067.7  267.06    4211  264.34
  4240.1  264.13  4354.3  261.62  4375.6  260.82  4497.5  259.01    4511  258.91
  4640.8  256.27  4646.4  256.25  4707.3   257.8  4828.3  256.94    4877  255.63
  4891.1  256.23  4905.3  254.84  4947.7  256.48  4961.8  256.02    4976  254.99
  4986.2  250.88  4986.7  250.38  4994.1  250.88  5000.7  255.86    5012   255.5
  5027.6  253.04  5036.3  255.31  5070.3  259.13  5184.7  262.73  5295.8  265.69
#Mann= 17 ,-1 , 0
  3872.9     .05       0  3924.4    .035       0  3969.3     .05       0
  4067.7    .035       0    4211     .07       0  4240.1    .035       0
  4354.3     .07       0  4375.6     .12       0  4497.5     .07       0
    4511     .12       0  4640.8     .07       0  4646.4     .12       0
  4828.3      .1       0  4986.2     .05       0  4994.1      .1       0
  5036.3     .07       0  5184.7     .05       0
Bank Sta=4986.2,4994.1
XS Rating Curve= 0 ,0
Exp/Cntr=0.3,0.1

Type RM Length L Ch R = 1 ,6810    ,789,789,789
BEGIN DESCRIPTION:
SADBERRY CREEK 11.0
END DESCRIPTION:
XS GIS Cut Line= 3
      2464425.02     13686924.98        2463625.       13687725.
        2463525.     13688225.01
#Sta/Elev= 30
  3868.6   272.5    4010  268.41    4109  263.74    4208  263.01  4317.1  260.72
    4406  258.94  4490.9  254.37  4542.4  253.78  4560.2  253.52  4589.9  253.56
    4604  252.36  4660.6  255.72  4688.9  256.13  4703.3  255.43  4835.3  254.66
  4971.7  253.69  4985.9  254.59  4992.5  249.66    4993  249.16  5000.5  249.66
  5010.2  250.86  5020.4  254.26  5063.8  254.21  5081.6  252.19    5102  254.01
  5112.2  253.86  5173.4  258.97  5275.3  262.11  5499.7  265.58  5509.9  264.87
#Mann= 9 ,-1 , 0
  3868.6     .05       0  4317.1     .07       0  4542.4     .12       0
  4560.2     .07       0  4703.3     .12       0  4835.3      .1       0
  4992.5     .05       0  5000.5      .1       0  5063.8     .07       0
Bank Sta=4992.5,5000.5
XS Rating Curve= 0 ,0
Exp/Cntr=0.3,0.1

Type RM Length L Ch R = 1 ,6021    ,627,627,627
BEGIN DESCRIPTION:
SADBERRY CREEK 10.0
END DESCRIPTION:
XS GIS Cut Line= 3
      2464024.99     13686625.01      2463318.81     13687462.33
      2463124.99     13688225.04
#Sta/Elev= 30
  3971.4  270.27  4212.6  263.04  4347.8   261.9  4666.4  255.35  4738.1  252.74
  4775.4  251.28  4858.8  253.55  4865.4  251.26  4879.7  253.43  4908.3  254.47
  4965.4  253.96  4992.8  251.87  5003.1  247.99  5003.6  247.49  5011.2  247.99
  5014.9  252.58  5035.7  253.17  5206.7  252.45  5286.2   252.4  5307.6  253.79
  5380.5  256.07  5467.3  259.13  5482.2  258.17  5513.4   260.1  5616.3  262.43
  5657.6  262.04  5802.1  265.87  5812.4  266.41  5843.3   272.3  5853.7  270.47
#Mann= 8 ,-1 , 0
  3971.4     .07       0  4738.1     .12       0  4775.4      .1       0
  5003.1     .05       0  5011.2      .1       0  5206.7     .07       0
  5307.6    .035       0  5380.5     .07       0
Bank Sta=5003.1,5011.2
XS Rating Curve= 0 ,0
Exp/Cntr=0.3,0.1

Type RM Length L Ch R = 1 ,5394    ,438,438,438
BEGIN DESCRIPTION:
SADBERRY CREEK 9.0
END DESCRIPTION:
XS GIS Cut Line= 3
      2463675.01     13686624.99      2463193.05      13687156.9
      2462425.01     13687974.99
#Sta/Elev= 30
    4257  264.18  4536.2  257.39  4752.3  252.38  4830.5  251.31  4844.7  247.44
  4865.6  251.82    4965  251.68  4976.9  251.35  4981.9  246.89  4982.4  246.39
  4990.1  246.89  4993.3  250.12  5007.5  252.01  5177.4  252.37  5184.3  248.59
  5212.6  250.54  5240.9   248.4  5247.8  252.19  5269.3  249.51  5276.1  252.57
  5297.4  249.51  5354.2  253.79  5375.3  250.28  5388.5  253.98    5429   254.2
  5536.8  257.38  5637.1  258.78  5672.2  256.53  5714.7  259.58  6096.9  266.33
#Mann= 9 ,-1 , 0
    4257     .07       0  4536.2     .12       0  4752.3      .1       0
  4981.9     .05       0  4990.1      .1       0  5297.4     .12       0
  5388.5    .035       0    5429     .12       0  5536.8     .05       0
Bank Sta=4981.9,4990.1
XS Rating Curve= 0 ,0
Exp/Cntr=0.3,0.1

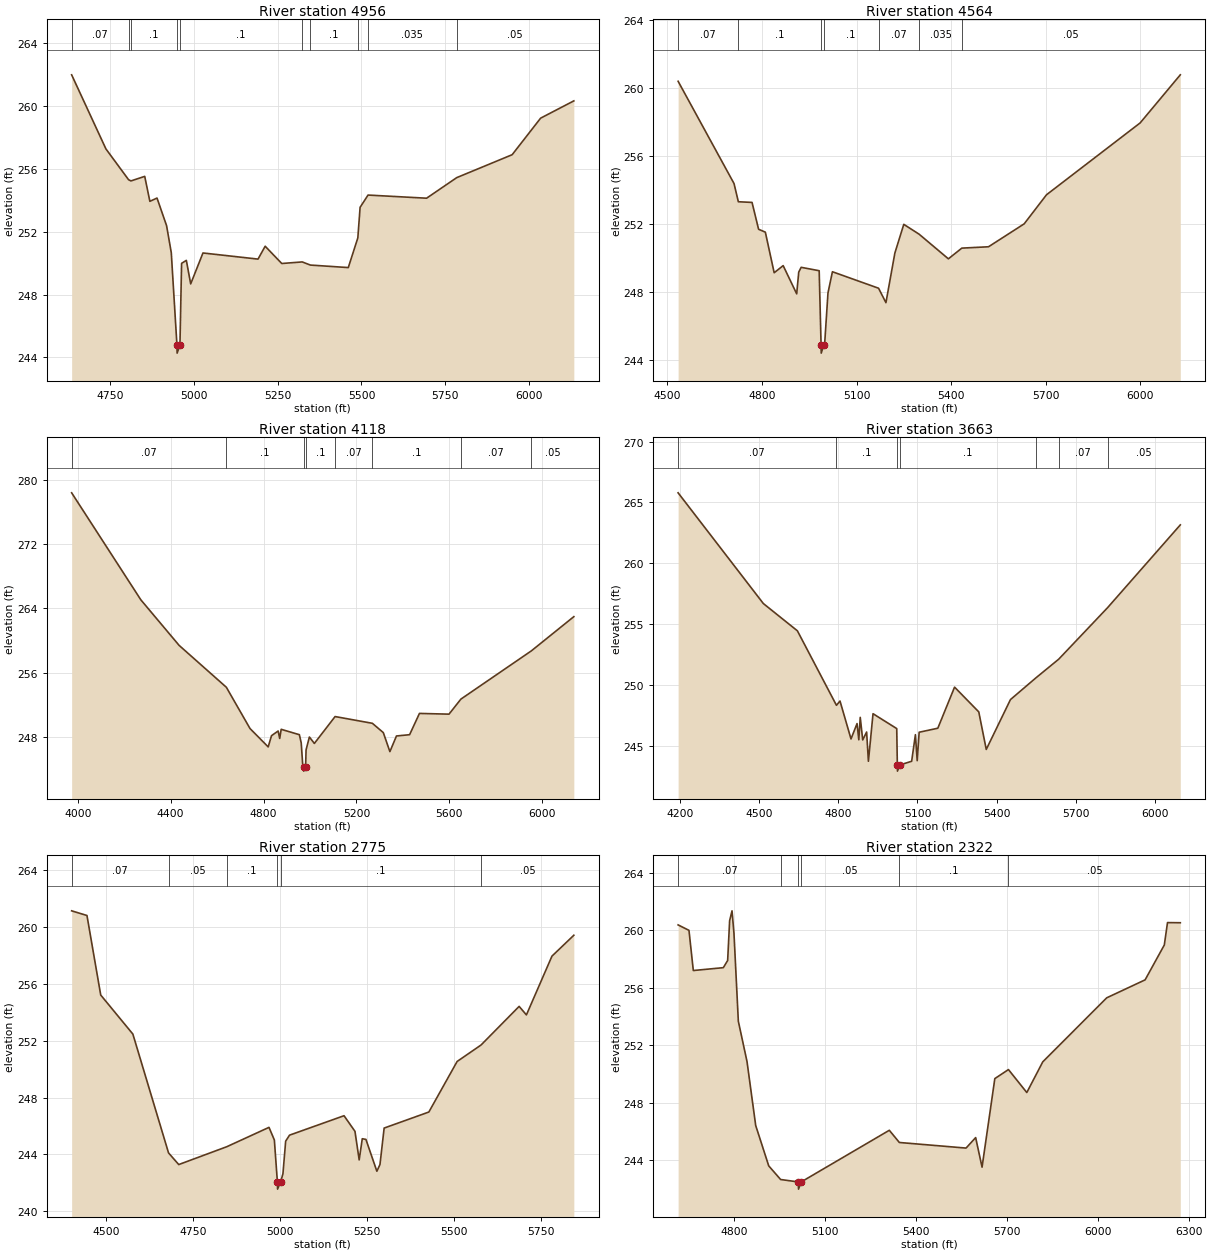
Type RM Length L Ch R = 1 ,4956    ,392,392,392
BEGIN DESCRIPTION:
SADBERRY CREEK 8.0
END DESCRIPTION:
XS GIS Cut Line= 3
      2463474.99       13686625.      2463121.18     13686845.48
      2462374.98     13687625.02
#Sta/Elev= 30
  4636.6     262  4738.7  257.28  4806.1  255.32  4813.1  255.24  4854.3  255.53
  4869.6  253.94  4890.9  254.15  4919.4  252.39  4933.4  250.67  4950.3  244.77
  4950.8  244.27  4959.2  244.77  4964.1  249.99  4978.3  250.18  4991.2  248.68
  5027.8  250.65  5191.8  250.26  5213.1  251.08  5262.5  249.98  5323.5  250.08
  5347.8  249.88  5460.7  249.72  5489.1  251.61  5495.9  253.56  5519.6  254.34
    5694  254.14  5783.7  255.45  5948.8  256.91  6033.7  259.24  6132.6  260.34
#Mann= 10 ,-1 , 0
  4636.6     .07       0  4806.1     .12       0  4813.1      .1       0
  4950.3     .05       0  4959.2      .1       0  5323.5     .07       0
  5347.8      .1       0  5489.1     .07       0  5519.6    .035       0
  5783.7     .05       0
Bank Sta=4950.3,4959.2
XS Rating Curve= 0 ,0
Exp/Cntr=0.3,0.1

Type RM Length L Ch R = 1 ,4564    ,446,446,446
BEGIN DESCRIPTION:
SADBERRY CREEK 7.0
END DESCRIPTION:
XS GIS Cut Line= 3
      2463175.03     13686374.98        2462825.       13686675.
      2462024.99     13687475.01
#Sta/Elev= 30
  4533.9   260.4  4711.2  254.38  4724.9  253.31  4768.3  253.27  4789.1  251.69
  4810.5  251.52  4838.5  249.13    4867  249.55  4909.9  247.89  4916.4  249.17
  4924.1  249.45  4981.2  249.25  4987.2   244.9  4987.7   244.4  4996.1   244.9
  4998.4   244.9  5009.1  247.94  5023.2  249.19  5169.5  248.22  5192.9  247.37
  5221.2  250.29  5249.5  251.98  5298.1   251.4  5390.9  249.95  5433.5  250.58
  5518.2  250.66  5631.3  252.01    5702  253.72    5999  257.95  6126.3  260.78
#Mann= 7 ,-1 , 0
  4533.9     .07       0  4724.9      .1       0  4987.2     .05       0
  4996.1      .1       0  5169.5     .07       0  5298.1    .035       0
  5433.5     .05       0
Bank Sta=4987.2,4996.1
XS Rating Curve= 0 ,0
Exp/Cntr=0.3,0.1

Type RM Length L Ch R = 1 ,4118    ,455,455,455
BEGIN DESCRIPTION:
SADBERRY CREEK 6.0
END DESCRIPTION:
XS GIS Cut Line= 3
      2463275.03     13685824.97        2462475.       13686475.
      2461674.99     13687275.01
#Sta/Elev= 30
  3973.7  278.41  4271.8  265.07  4436.4   259.4  4639.8  254.18  4741.6  249.04
  4819.9  246.75  4834.3  248.15  4862.8  248.73  4869.5   247.8  4875.9  248.94
  4954.2  248.27  4962.1  247.25  4968.6   244.5    4972  244.23  4972.5  243.73
    4981  244.23    4983  246.38  4997.3  247.98  5018.7  247.18    5108  250.53
  5268.4  249.69  5315.6  248.53  5343.9  246.16  5372.2  248.11  5428.8  248.27
  5471.2  250.92  5598.5  250.83  5649.5   252.7  5953.2  258.72  6135.9  262.98
#Mann= 8 ,-1 , 0
  3973.7     .07       0  4639.8      .1       0    4972     .05       0
    4981      .1       0    5108     .07       0  5268.4      .1       0
  5649.5     .07       0  5953.2     .05       0
Bank Sta=4972,4981
XS Rating Curve= 0 ,0
Exp/Cntr=0.3,0.1

Type RM Length L Ch R = 1 ,3663    ,888,888,888
BEGIN DESCRIPTION:
SADBERRY CREEK 5.0
END DESCRIPTION:
XS GIS Cut Line= 3
      2462524.98     13685525.04        2462225.       13686275.
      2461475.01     13687074.99
#Sta/Elev= 30
  4192.4  265.79  4515.5  256.71  4644.7  254.47  4792.8  248.36  4806.3  248.71
    4848   245.6  4870.9  246.86  4877.6  245.53    4883  247.37  4892.4  245.52
  4907.2  246.17    4914  243.77  4931.5  247.67  5021.4  246.45  5023.7  243.46
  5024.2  242.96  5032.8  243.46    5078  243.77  5092.2  245.95    5099  243.82
  5106.4  246.15  5177.2  246.48  5240.7  249.85  5332.5  247.82  5360.9  244.74
  5452.7  248.83  5549.1  250.61  5635.5  252.14    5821  256.37  6096.7  263.16
#Mann= 7 ,-1 , 0
  4192.4     .07       0  4792.8      .1       0  5023.7     .05       0
  5032.8      .1       0  5549.1     .05       0  5635.5     .07       0
    5821     .05       0
Bank Sta=5023.7,5032.8
XS Rating Curve= 0 ,0
Exp/Cntr=0.3,0.1

Type RM Length L Ch R = 1 ,2775    ,453,453,453
BEGIN DESCRIPTION:
SADBERRY CREEK 4.0
END DESCRIPTION:
XS GIS Cut Line= 3
      2461925.02     13685424.96        2461675.       13685975.
      2461425.01     13686774.95
#Sta/Elev= 30
  4401.4  261.15  4445.4  260.82  4484.9  255.22  4577.2  252.47  4679.7   244.1
    4709  243.28  4847.3  244.54  4968.2   245.9  4983.6  245.01  4992.3  242.05
  4992.8  241.55  5001.4  242.05  5008.2  242.63  5016.1  244.93  5027.1  245.35
  5183.7  246.72  5215.1  245.62  5227.2  243.61  5236.1   245.1  5246.6  245.05
    5278  242.81  5286.9  243.28  5298.9  245.85  5427.3  246.98  5508.5  250.54
  5577.2   251.7  5686.6  254.42  5707.5  253.82  5780.9  257.96  5843.7  259.43
#Mann= 6 ,-1 , 0
  4401.4     .07       0  4679.7     .05       0  4847.3      .1       0
  4992.3     .05       0  5001.4      .1       0  5577.2     .05       0
Bank Sta=4992.3,5001.4
XS Rating Curve= 0 ,0
Exp/Cntr=0.3,0.1

Type RM Length L Ch R = 1 ,2322    ,427,427,427
BEGIN DESCRIPTION:
SADBERRY CREEK 3.0
END DESCRIPTION:
XS GIS Cut Line= 3
      2461774.98     13685325.03        2461525.       13685625.
        2461125.     13686825.01
#Sta/Elev= 30
  4614.6  260.39  4650.4  260.01  4664.7  257.21  4763.6  257.41  4777.9  257.91
  4784.4  260.68  4792.3  261.37  4798.8  259.77  4813.1  253.68  4841.7  250.87
  4870.4  246.41  4913.3   243.6  4952.5  242.65    5011  242.48  5011.5  241.98
  5020.2  242.48  5310.8  246.08  5343.9  245.23  5563.7  244.84  5595.4  245.57
  5616.5  243.51  5658.6  249.68  5703.5  250.31    5764  248.71  5816.7  250.85
  6027.5  255.31    6154  256.56  6217.3  258.99  6227.8  260.55    6270  260.54
#Mann= 6 ,-1 , 0
  4614.6     .07       0  4952.5     .05       0    5011     .05       0
  5020.2     .05       0  5343.9      .1       0  5703.5     .05       0
Bank Sta=5011,5020.2
XS Rating Curve= 0 ,0
Exp/Cntr=0.3,0.1

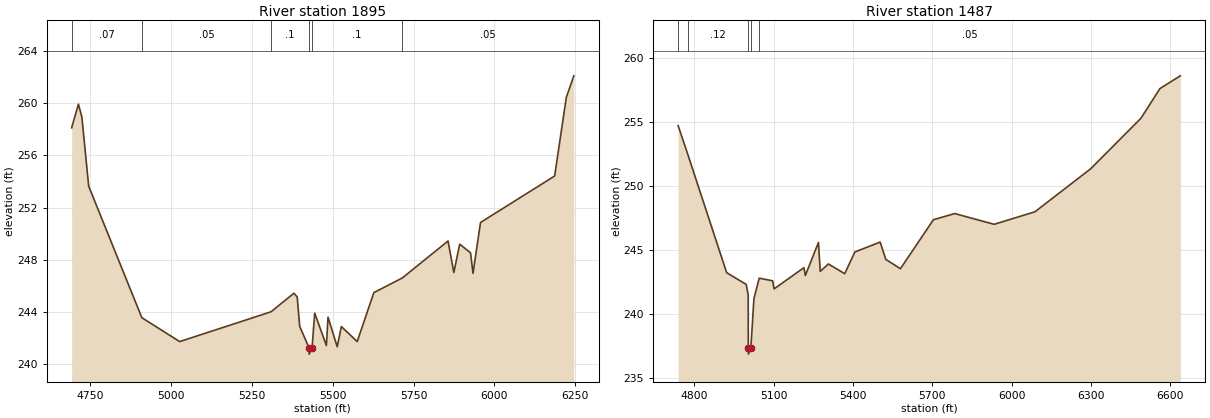
Type RM Length L Ch R = 1 ,1895    ,408,408,408
BEGIN DESCRIPTION:
SADBERRY CREEK 2.0
END DESCRIPTION:
XS GIS Cut Line= 3
      2461624.96     13685325.01        2461325.       13685425.
        2461025.     13686624.99
#Sta/Elev= 30
  4692.3  258.11  4713.3  259.92  4723.9  258.94    4745  253.64  4909.4  243.57
  5026.5  241.74  5308.8  244.02  5379.6  245.44  5389.9  245.16  5397.6   242.9
  5426.3  241.28  5426.8  240.78  5435.9  241.28    5444  243.92  5480.1  241.44
  5485.2  243.61  5513.6  241.34  5526.4  242.89  5575.4  241.74  5626.9  245.49
  5714.8  246.61  5856.3  249.44  5874.3  247.03  5892.4   249.2  5925.9  248.54
  5933.6  246.97  5956.8  250.86  6186.1  254.42  6222.2  260.45  6245.4  262.09
#Mann= 6 ,-1 , 0
  4692.3     .07       0  4909.4     .05       0  5308.8      .1       0
  5426.3     .05       0  5435.9      .1       0  5714.8     .05       0
Bank Sta=5426.3,5435.9
XS Rating Curve= 0 ,0
Exp/Cntr=0.3,0.1

Type RM Length L Ch R = 1 ,1487    ,0,0,0
BEGIN DESCRIPTION:
SADBERRY CREEK 1.0
END DESCRIPTION:
XS GIS Cut Line= 3
      2461425.04     13685074.99        2461175.       13685125.
      2460624.99     13686675.02
#Sta/Elev= 30
  4738.1  254.72  4773.6  252.54  4921.7  243.22  4995.7   242.3  5003.2  241.48
  5003.7  237.35  5004.2  236.85  5013.3  237.35  5024.9  241.18  5044.9  242.79
  5095.8  242.58  5101.1  241.95    5214  243.61  5219.3     243    5269  245.58
  5275.7  243.32  5306.6   243.9  5368.3  243.14  5406.9  244.84  5502.4  245.61
  5523.6  244.26  5579.1  243.53    5704  247.36  5784.6  247.84  5933.6     247
  6087.9  247.98  6298.7  251.34  6489.2   255.3  6560.6  257.61  6637.8  258.61
#Mann= 5 ,-1 , 0
  4738.1     .07       0  4773.6     .12       0  5003.7     .05       0
  5013.3     .12       0  5044.9     .05       0
Bank Sta=5003.7,5013.3
XS Rating Curve= 0 ,0
Exp/Cntr=0.3,0.1

Chan Stop Cuts=-1
Use User Specified Reach Order=0
Composite Channel Slope=5