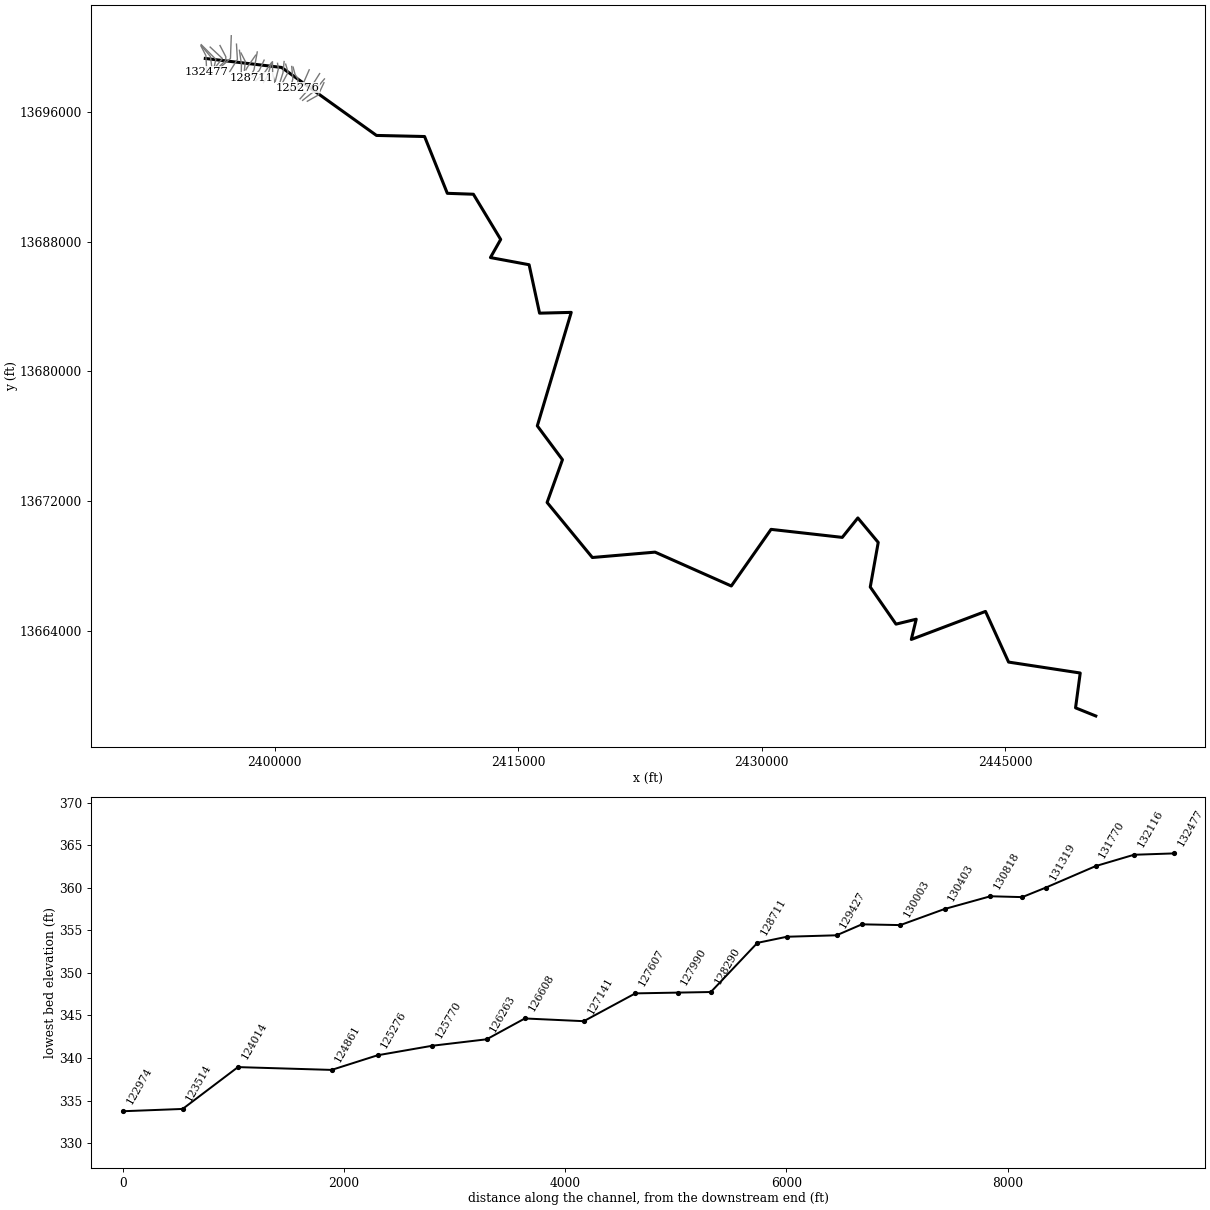
--- SALTY CREEK_SUGAR CREEK.prj (project) ---

Proj Title=SALTY CREEK_SUGAR CREEK Base Level Engineering
Current Plan=p01
Default Exp/Contr=0.3,0.1
English Units
Geom File=g01
Flow File=f01
Plan File=p01
Y Axis Title=Elevation
X Axis Title(PF)=Main Channel Distance
X Axis Title(XS)=Station
BEGIN DESCRIPTION:
SALTY CREEK_SUGAR CREEK
END DESCRIPTION:
DSS Export Rating Curves= 0
DSS Export Rating Curve Sorted= 0
DSS Export Volume Flow Curves= 0
DXF OffsetX= 0
DXF OffsetY= 0
DXF ScaleX= 1
DXF ScaleY= 10

--- SALTY CREEK_SUGAR CREEK.p01 (plan) ---

Plan Title=Multiple Run
Program Version=4.10
Short Identifier=Multiple
Geom File=g01
Flow File=f01
Subcritical Flow
K Sum by GR= 0
Std Step Tol= 0.01
Critical Tol= 0.01
Num of Std Step Trials= 20
Max Error Tol= 0.3
Flow Tol Ratio= 0.001
Split Flow NTrial= 30
Split Flow Tol= 0.02
Split Flow Ratio= 0.02
Log Output Level= 0
Friction Slope Method= 1
Unsteady Friction Slope Method= 2
Unsteady Bridges Friction Slope Method= 1
Parabolic Critical Depth
Global Vel Dist= 1 , 1 , 1
Global Log Level= 0
CheckData=True
Encroach Param=-1 ,0,0, 0
BEGIN DESCRIPTION:
Multiple Run
END DESCRIPTION:
Computation Interval=1HOUR
Output Interval=1HOUR
Run HTab= 0
Run UNet= 0
Run PostProcess= 0
Run WQNet= 0
UNET Theta= 1
UNET Theta Warmup= 1
UNET ZTol= 0.02
UNET ZSATol= 0.05
UNET MxIter= 20
UNET MaxInSteps= 0
UNET DtIC= 0
UNET DtMin= 0
UNET MaxCRTS= 20
UNET WFStab= 2
UNET SFStab= 1
UNET WFX= 1
UNET SFX= 1
UNET DSS MLevel= 4
UNET DZMax Abort= 100
UNET Convert EG Bridges= 0
UNET Use Existing IB Tables=-1
UNET Froude Reduction=False
UNET Froude Limit= 1
UNET Froude Power= 10
UNET Time Slicing=0,0, 5
UNET Junction Losses=0
Instantaneous Interval=1HOUR
Write IC File= 0
Write IC File at Sim End=0
Echo Input=False
Echo Parameters=False
Echo Output=False
Write Detailed= 0
WQ AD Non Conservative
WQ ULTIMATE=-1
WQ Max Comp Step=1HOUR
WQ Output Interval=15MIN
WQ Output Selected Increments= 0
WQ Output face flow=0
WQ Output face velocity=0
WQ Output face area=0
WQ Output face dispersion=0
WQ Output cell volume=0
WQ Output cell surface area=0
WQ Output cell continuity=0
WQ Output cumulative cell continuity=0
WQ Output face conc=0
WQ Output face dconc_dx=0
WQ Output face courant=0
WQ Output face peclet=0
WQ Output face adv mass=0
WQ Output face disp mass=0
WQ Output cell mass=0
WQ Output cell source sink temp=0
WQ Output cell source sink nsm=0
WQ Output MaxMinRange=-1
WQ Daily Max Min Mean=-1
WQ Daily Range=0
WQ Daily Time=0
WQ Create Restart=0
WQ Fixed Restart=0
WQ System Summary=0
WQ Use Fixed Temperature=0
Sorting and Armoring Iterations= 10
XS Update Threshold= 0.02
Hydraulics Update Threshold= 0.02
Energy Slope Method= 1
Volume Change Method= 0
XS Weighting Method= 0
Number of US Weighted Cross Sections= 1
Number of DS Weighted Cross Sections= 1
Upstream XS Weight=0.25
Main XS Weight=0.5
Downstream XS Weight=0.25
Number of DS XS's Weighted with US Boundary= 1
Upstream Boundary Weight= 1
Weight of XSs Associated with US Boundary= 0
Number of US XS's Weighted with DS Boundary= 1
Downstream Boundary Weight= 0.5
Weight of XSs Associated with DS Boundary= 0.5
Sediment Output Level= 4
Mass or Volume Output= 0
Output Increment Type= 1
Profile and TS Output Increment= 10
XS Output Flag= 0
XS Output Increment= 10
Disregard all LS=0
Disregard all Conn=0
Disregard all Breaches=0
Disregard all Pumps=0

--- SALTY CREEK_SUGAR CREEK.f01 (steady flow) ---

Flow Title=Multiple
Number of Profiles=7
Profile Names=10-year,25-year,50-year,1pct_min,100-year,1pct_plu,500-year
River Rch & RM= SALTY CREEK_SUGA,Reach-1,132477
     846    1389    1888    1242    2477    4943    4228
River Rch & RM= SALTY CREEK_SUGA,Reach-1,129427
    1644    2781    3856    2580    5147   10269    9098
River Rch & RM= SALTY CREEK_SUGA,Reach-1,124861
    1774    2999    4154    2776    5539   11052    9768
River Rch & RM= SALTY CREEK_SUGA,Reach-1,122974
    1833    3094    4282    2858    5703   11380   10033
River Rch & RM= SALTY CREEK_SUGA,Reach-1,116620
    2054    3482    4832    3233    6451   12872   11404
River Rch & RM= SALTY CREEK_SUGA,Reach-1,115077
    2190    3721    5172    3465    6914   13795   12253
River Rch & RM= SALTY CREEK_SUGA,Reach-1,111969
    2325    3943    5472    3659    7301   14567   12887
River Rch & RM= SALTY CREEK_SUGA,Reach-1,102018
    2369    4008    5554    3707    7397   14759   13010
River Rch & RM= SALTY CREEK_SUGA,Reach-1,95580
    2696    4585    6376    4269    8519   16997   15081
River Rch & RM= SALTY CREEK_SUGA,Reach-1,91034
    5000    8595   12040    8104   16170   32263   28910
River Rch & RM= SALTY CREEK_SUGA,Reach-1,83031
    5328    9165   12844    8648   17254   34427   30867
River Rch & RM= SALTY CREEK_SUGA,Reach-1,75628
    5344    9182   12856    8648   17255   34428   30808
River Rch & RM= SALTY CREEK_SUGA,Reach-1,73871
    6516   11235   15773   10633   21216   42331   38036
River Rch & RM= SALTY CREEK_SUGA,Reach-1,67102
    6690   11543   16213   10935   21818   43532   39150
River Rch & RM= SALTY CREEK_SUGA,Reach-1,65491
    6760   11646   16339   11007   21961   43818   39310
River Rch & RM= SALTY CREEK_SUGA,Reach-1,62370
    6711   11516   16113   10823   21594   43086   38428
River Rch & RM= SALTY CREEK_SUGA,Reach-1,49069
    7548   12954   18128   12175   24291   48468   43209
River Rch & RM= SALTY CREEK_SUGA,Reach-1,37959
    7833   13418   18753   12576   25093   50067   44501
River Rch & RM= SALTY CREEK_SUGA,Reach-1,31835
    8131   13931   19475   13063   26064   52004   46235
River Rch & RM= SALTY CREEK_SUGA,Reach-1,18927
    8323   14226   19856   13295   26527   52929   46890
River Rch & RM= SALTY CREEK_SUGA,Reach-1,7599
    8430   14379   20041   13398   26732   53338   47103
Boundary for River Rch & Prof#=SALTY CREEK_SUGA,Reach-1,1
Up Type=0
Dn Type=3
Dn Slope=0.00075
Boundary for River Rch & Prof#=SALTY CREEK_SUGA,Reach-1,2
Up Type=0
Dn Type=3
Dn Slope=0.00075
Boundary for River Rch & Prof#=SALTY CREEK_SUGA,Reach-1,3
Up Type=0
Dn Type=3
Dn Slope=0.00075
Boundary for River Rch & Prof#=SALTY CREEK_SUGA,Reach-1,4
Up Type=0
Dn Type=3
Dn Slope=0.00075
Boundary for River Rch & Prof#=SALTY CREEK_SUGA,Reach-1,5
Up Type=0
Dn Type=3
Dn Slope=0.00075
Boundary for River Rch & Prof#=SALTY CREEK_SUGA,Reach-1,6
Up Type=0
Dn Type=3
Dn Slope=0.00075
Boundary for River Rch & Prof#=SALTY CREEK_SUGA,Reach-1,7
Up Type=0
Dn Type=3
Dn Slope=0.00075

--- SALTY CREEK_SUGAR CREEK.g01 (geometry) ---

Geom Title=Existing Conditions
Program Version=4.10

River Reach=SALTY CREEK_SUGA,Reach-1
Reach XY= 30
        2395725.       13699275.      2400423.78     13698721.63
      2406268.24     13694534.12      2409231.19     13694467.19
      2410632.45     13690968.93      2412238.67     13690911.77
      2413919.95     13688127.28      2413288.63     13687011.79
      2415669.83     13686569.59      2416314.56     13683585.94
      2418264.58     13683634.81      2416175.05     13676645.04
      2417724.49     13674559.79      2416778.82     13671926.58
        2419565.     13668535.63      2423428.21     13668867.14
        2428125.     13666782.07      2430572.71     13670269.19
      2434959.72     13669775.38      2435919.09     13670972.78
      2437174.13     13669464.67      2436683.97     13666718.34
      2438268.93     13664432.48      2439514.96       13664735.
      2439211.67     13663488.32      2443781.95     13665215.81
      2445204.52     13662094.63      2449616.52     13661421.49
      2449328.75     13659276.55        2450575.       13658775.

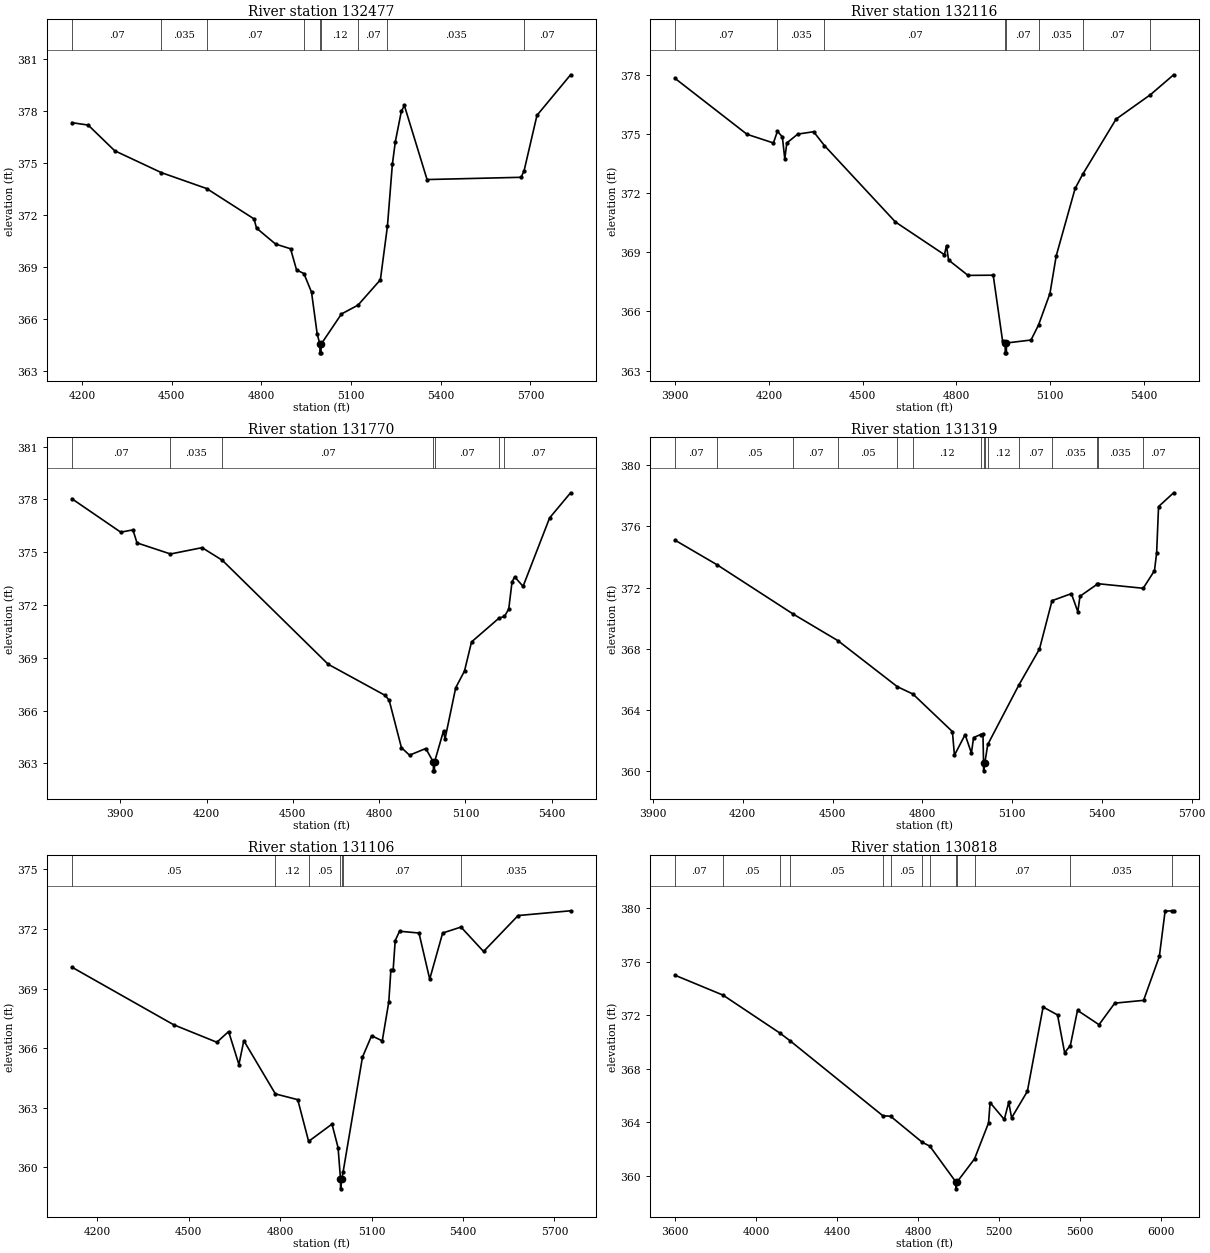
Type RM Length L Ch R = 1 ,132477  ,361,361,361
BEGIN DESCRIPTION:
E20616
END DESCRIPTION:
XS GIS Cut Line= 3
      2395463.14     13700034.35      2395760.54     13699454.42
      2395816.29     13698439.79
#Sta/Elev= 30
  4166.3  377.33  4220.7  377.19  4309.4  375.71  4465.4  374.45  4617.2  373.53
  4775.5  371.78  4783.7  371.25  4847.5  370.33  4897.6  370.06  4917.6  368.84
  4942.2  368.63  4967.7  367.56  4986.6  365.15  4995.7  364.56  4995.9  364.06
  4999.5  364.06  4999.8  364.56  5067.8   366.3  5123.2  366.81    5198  368.27
  5221.6  371.36  5238.1  374.93  5248.1  376.24  5268.1  377.98  5278.2  378.32
  5354.1  374.05  5668.7  374.18  5678.7  374.56  5721.7  377.75  5834.2  380.09
#Mann= 9 ,-1 , 0
  4166.3     .07       0  4465.4    .035       0  4617.2     .07       0
  4942.2     .12       0  4995.7     .05       0  4999.8     .12       0
  5123.2     .07       0  5221.6    .035       0  5678.7     .07       0
Bank Sta=4995.7,4999.8
XS Rating Curve= 0 ,0
Exp/Cntr=0.3,0.1

Type RM Length L Ch R = 1 ,132116  ,346,346,346
BEGIN DESCRIPTION:
E20615
END DESCRIPTION:
XS GIS Cut Line= 3
      2395470.55     13700075.29      2396039.36     13699398.66
       2396132.3      13698692.3
#Sta/Elev= 30
  3899.5  377.83  4130.1  374.99  4214.7  374.55  4227.5  375.14  4243.3  374.86
  4251.1  373.74  4257.6  374.55  4292.7     375  4343.4  375.12  4377.9  374.42
  4605.3  370.54  4762.1  368.88  4768.8  369.34  4775.3  368.61  4837.6  367.83
  4918.3  367.84  4948.5  364.48  4956.6   364.4  4956.8   363.9  4960.4   363.9
  4960.7   364.4  5039.3  364.55  5063.3  365.31  5099.9  366.91    5120  368.82
  5180.5  372.24  5204.4  372.95  5311.6  375.76  5421.7     377  5495.9  378.01
#Mann= 8 ,-1 , 0
  3899.5     .07       0  4227.5    .035       0  4377.9     .07       0
  4956.6     .05       0  4960.7     .07       0  5063.3    .035       0
  5204.4     .07       0  5421.7    .035       0
Bank Sta=4956.6,4960.7
XS Rating Curve= 0 ,0
Exp/Cntr=0.3,0.1

Type RM Length L Ch R = 1 ,131770  ,451,451,451
BEGIN DESCRIPTION:
SALTY CREEK_SUGAR CREEK 106.0
END DESCRIPTION:
XS GIS Cut Line= 3
      2395474.97     13700125.03        2396375.       13699225.
        2396275.     13698775.01
#Sta/Elev= 30
  3731.8  378.04  3901.5  376.14    3944  376.27  3958.1  375.53  4074.5   374.9
  4184.4  375.26  4254.9  374.54  4622.8  368.63  4820.8  366.86  4834.9  366.58
  4877.4  363.89  4905.6  363.46  4962.2  363.84  4988.4  363.07  4988.7  362.57
  4992.3  362.57  4992.5  363.07  5023.8  364.84    5029  364.38  5066.1  367.29
  5096.8  368.25  5121.2   369.9  5217.2  371.26  5235.7  371.35  5250.5  371.77
    5262  373.31    5271   373.6  5300.4  373.06  5392.6  376.95  5465.6  378.38
#Mann= 7 ,-1 , 0
  3731.8     .07       0  4074.5    .035       0  4254.9     .07       0
  4988.4     .05       0  4992.5     .07       0  5217.2    .035       0
  5235.7     .07       0
Bank Sta=4988.4,4992.5
XS Rating Curve= 0 ,0
Exp/Cntr=0.3,0.1

Type RM Length L Ch R = 1 ,131319  ,213,213,213
BEGIN DESCRIPTION:
SALTY CREEK_SUGAR CREEK 105.0
END DESCRIPTION:
XS GIS Cut Line= 3
        2396025.       13699975.        2396775.       13699275.
      2396375.02     13698775.02
#Sta/Elev= 30
  3973.6  375.09  4113.7  373.49  4368.4  370.27  4518.3  368.53  4716.6  365.53
  4768.7  365.05  4900.6   362.6  4907.4  361.06  4943.1   362.4  4964.1   361.2
  4971.4  362.21  4994.7  362.41  5002.7  362.44  5004.7  360.54  5004.9  360.04
  5008.8  360.54  5018.8  361.76  5122.7  365.64  5191.6  367.99  5233.5  371.14
  5298.1   371.6  5319.7  370.42  5326.9  371.43  5384.1  372.21    5386  372.25
  5538.1  371.95  5575.8   373.1    5583  374.26  5589.4  377.28  5639.8  378.18
#Mann= 15 ,-1 , 0
  3973.6     .07       0  4113.7     .05       0  4368.4     .07       0
  4518.3     .05       0  4716.6     .07       0  4768.7     .12       0
  4994.7     .05       0  5004.7     .05       0  5008.8     .05       0
  5018.8     .12       0  5122.7     .07       0  5233.5    .035       0
  5384.1     .07       0    5386    .035       0  5538.1     .07       0
Bank Sta=5004.7,5008.8
XS Rating Curve= 0 ,0
Exp/Cntr=0.3,0.1

Type RM Length L Ch R = 1 ,131106  ,288,288,288
BEGIN DESCRIPTION:
E20614
END DESCRIPTION:
XS GIS Cut Line= 4
      2396630.46     13700071.52      2396987.34     13699383.79
      2396987.34     13699157.02      2396527.25     13698719.19
#Sta/Elev= 30
  4116.4  370.08  4450.5  367.18  4592.2   366.3  4630.7  366.84  4664.5  365.18
  4680.6  366.38  4784.2   363.7  4857.6  363.41  4893.3  361.31    4970  362.18
    4990  360.99  4997.9  359.42  4998.2  358.92  5002.1  359.42  5006.6  359.78
    5070  365.55    5100  366.63    5135  366.37  5156.4  368.33  5163.3  369.94
  5170.6  369.92  5177.5  371.42  5191.7  371.89  5255.5   371.8  5290.7  369.48
  5333.2   371.8  5393.4   372.1  5467.5  370.87  5580.8  372.68  5753.1  372.92
#Mann= 7 ,-1 , 0
  4116.4     .05       0  4784.2     .12       0  4893.3     .05       0
  4997.9     .05       0  5002.1     .05       0  5006.6     .07       0
  5393.4    .035       0
Bank Sta=4997.9,5002.1
XS Rating Curve= 0 ,0
Exp/Cntr=0.3,0.1

Type RM Length L Ch R = 1 ,130818  ,415,415,415
BEGIN DESCRIPTION:
SALTY CREEK_SUGAR CREEK 104.0
END DESCRIPTION:
XS GIS Cut Line= 3
        2397325.     13700674.99        2397275.       13699275.
        2396475.       13698575.
#Sta/Elev= 30
  3599.5     375  3837.1  373.51  4118.2  370.67  4167.9   370.1  4626.4  364.49
  4664.9  364.45  4822.4  362.49  4858.4  362.22  4988.1  359.52  4988.4  359.02
  4992.6  359.52  5079.6  361.26  5148.9  363.95  5156.5  365.47  5226.7  364.21
  5248.6   365.5  5262.8  364.33  5340.6  366.31  5418.5  372.62  5489.7  372.03
  5524.8   369.2    5553  369.74  5588.4  372.37  5694.7   371.3  5772.5  372.91
  5914.9  373.12  5992.7   376.4  6021.2  379.79  6056.9  379.82  6063.4  379.79
#Mann= 13 ,-1 , 0
  3599.5     .07       0  3837.1     .05       0  4118.2    .035       0
  4167.9     .05       0  4626.4     .07       0  4664.9     .05       0
  4822.4     .12       0  4858.4     .05       0  4988.1     .05       0
  4992.6     .05       0  5079.6     .07       0    5553    .035       0
  6056.9     .07       0
Bank Sta=4988.1,4992.6
XS Rating Curve= 0 ,0
Exp/Cntr=0.3,0.1

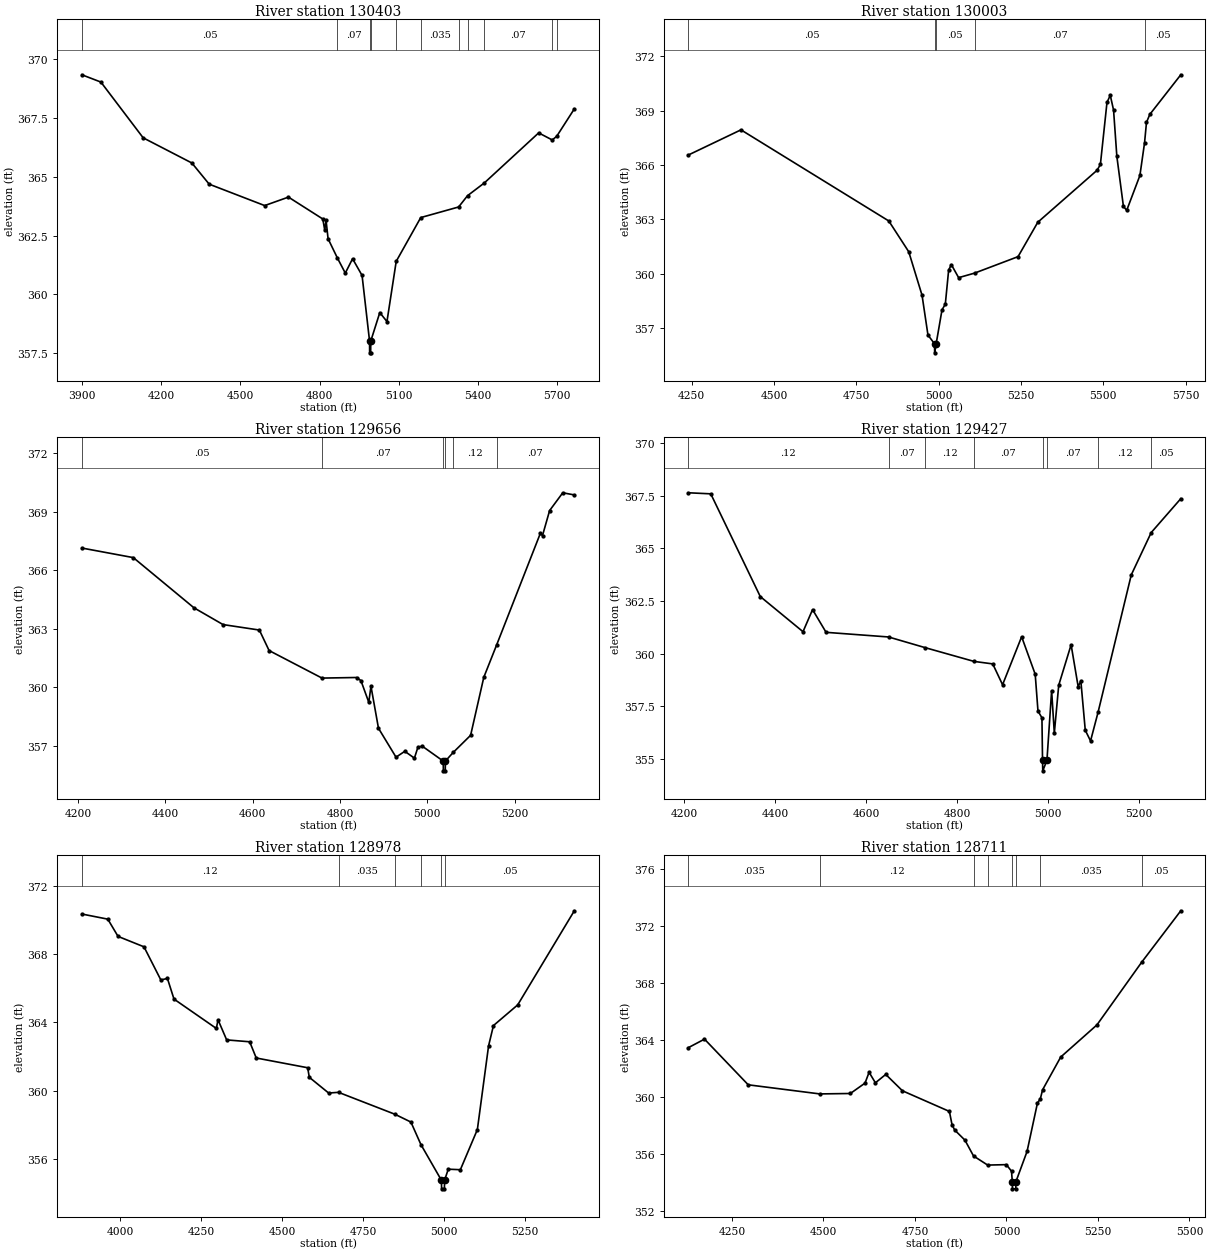
Type RM Length L Ch R = 1 ,130403  ,400,400,400
BEGIN DESCRIPTION:
E20613
END DESCRIPTION:
XS GIS Cut Line= 3
      2397645.35     13700157.06      2397701.11      13699216.5
      2397210.38     13698432.07
#Sta/Elev= 30
  3898.4  369.34  3970.6  369.03  4130.9  366.66  4315.6  365.59  4381.3  364.69
  4591.7  363.78  4681.8  364.14  4812.1  363.21  4819.4  362.74  4824.5  363.15
  4832.1  362.37  4867.5  361.55  4897.4  360.91    4925  361.52    4961  360.81
  4989.4  358.02  4989.7  357.52  4993.6  357.52    4994  358.02  5028.2  359.23
  5055.4  358.85  5090.5  361.41  5183.5  363.27  5327.1  363.72  5360.9   364.2
  5424.4  364.74  5630.7  366.87    5682  366.57  5698.8  366.72  5765.9  367.89
#Mann= 11 ,-1 , 0
  3898.4     .05       0  4867.5     .07       0  4989.4     .05       0
    4994     .07       0  5090.5     .05       0  5183.5    .035       0
  5327.1     .05       0  5360.9    .035       0  5424.4     .07       0
    5682    .035       0  5698.8     .07       0
Bank Sta=4989.4,4994
XS Rating Curve= 0 ,0
Exp/Cntr=0.3,0.1

Type RM Length L Ch R = 1 ,130003  ,347,347,347
BEGIN DESCRIPTION:
E20612
END DESCRIPTION:
XS GIS Cut Line= 3
      2397827.51     13699777.85      2397950.19     13698911.66
      2397939.04     13698290.79
#Sta/Elev= 30
  4239.6  366.55  4399.5  367.94  4848.5  362.91  4909.1  361.21  4949.5  358.81
  4967.5  356.61  4987.4  356.13  4987.8  355.63  4992.4  356.13  5010.1     358
  5020.2  358.32  5030.3   360.2  5038.5   360.5  5060.6  359.78  5108.9  360.03
  5241.1  360.94  5301.1  362.84  5481.2  365.71  5491.2  366.03  5511.2  369.45
  5521.2  369.85  5531.2  369.03  5541.2  366.47  5561.2  363.71  5571.2   363.5
  5611.2  365.42  5625.3  367.22  5631.2  368.35  5641.2  368.79  5735.4  370.98
#Mann= 5 ,-1 , 0
  4239.6     .05       0  4987.4     .05       0  4992.4     .05       0
  5108.9     .07       0  5625.3     .05       0
Bank Sta=4987.4,4992.4
XS Rating Curve= 0 ,0
Exp/Cntr=0.3,0.1

Type RM Length L Ch R = 1 ,129656  ,229,229,229
BEGIN DESCRIPTION:
E20611
END DESCRIPTION:
XS GIS Cut Line= 3
      2397924.15      13699610.6      2398188.11     13699093.82
      2398132.48     13698548.64
#Sta/Elev= 30
  4208.7  367.13  4326.6  366.64  4465.5  364.07  4532.2  363.21  4615.4  362.93
  4637.7  361.88  4758.9  360.47  4838.1   360.5  4848.1  360.34  4866.1  359.23
  4871.1  360.05  4888.3   357.9  4928.5  356.42  4948.6  356.72  4970.6  356.37
  4978.8  356.94  4988.8  356.98  5036.6  356.22    5037  355.72  5041.3  355.72
  5041.6  356.22  5059.4  356.66  5099.4  357.54  5129.6  360.51  5158.7  362.15
  5259.1  367.88  5264.1  367.77  5280.4  369.05  5310.5  369.96    5337  369.85
#Mann= 6 ,-1 , 0
  4208.7     .05       0  4758.9     .07       0  5036.6     .05       0
  5041.6     .07       0  5059.4     .12       0  5158.7     .07       0
Bank Sta=5036.6,5041.6
XS Rating Curve= 0 ,0
Exp/Cntr=0.3,0.1

Type RM Length L Ch R = 1 ,129427  ,449,449,449
BEGIN DESCRIPTION:
SALTY CREEK_SUGAR CREEK 102.0
END DESCRIPTION:
XS GIS Cut Line= 3
      2398824.99     13699474.99        2398375.       13698825.
        2398225.       13698575.
#Sta/Elev= 30
  4209.6  367.64  4258.9  367.59  4367.7  362.71  4461.6  361.04  4482.6  362.09
  4512.3  361.01  4649.5  360.79  4730.4  360.28  4837.1  359.63  4878.5  359.51
  4900.1  358.52    4942   360.8  4971.8  359.02  4977.9  357.27  4986.6  356.95
  4987.9  354.93  4988.4  354.43  4997.6  354.93  5007.9  358.24  5013.8  356.22
  5023.5   358.5  5050.7  360.42  5066.2  358.43  5072.1   358.7  5081.8  356.36
  5093.4  355.85  5109.9  357.21  5182.9  363.74  5226.7  365.75  5291.7  367.36
#Mann= 8 ,-1 , 0
  4209.6     .12       0  4649.5     .07       0  4730.4     .12       0
  4837.1     .07       0  4987.9     .05       0  4997.6     .07       0
  5109.9     .12       0  5226.7     .05       0
Bank Sta=4987.9,4997.6
XS Rating Curve= 0 ,0
Exp/Cntr=0.3,0.1

Type RM Length L Ch R = 1 ,128978  ,267,267,267
BEGIN DESCRIPTION:
SALTY CREEK_SUGAR CREEK 101.0
END DESCRIPTION:
XS GIS Cut Line= 3
      2398925.01     13699675.04        2398725.       13698575.
        2398525.     13698224.99
#Sta/Elev= 30
  3881.9  370.35    3962  370.05  3993.7  369.04  4073.8  368.43  4125.9  366.49
  4146.2  366.58  4166.5  365.37  4297.4  363.65  4302.5  364.16  4329.2  362.98
  4400.3  362.87  4420.6  361.92  4579.4  361.35  4584.5  360.79  4644.2  359.87
  4674.7  359.91  4848.6  358.63  4898.3  358.17  4929.3  356.85  4992.6  354.76
  4993.1  354.26  5001.8  354.26  5002.3  354.76  5013.7  355.41  5051.1  355.38
  5103.6  357.73  5138.2  362.63  5153.3  363.82  5228.2  365.03  5403.1  370.54
#Mann= 6 ,-1 , 0
  3881.9     .12       0  4674.7    .035       0  4848.6     .07       0
  4929.3     .05       0  4992.6     .05       0  5002.3     .05       0
Bank Sta=4992.6,5002.3
XS Rating Curve= 0 ,0
Exp/Cntr=0.3,0.1

Type RM Length L Ch R = 1 ,128711  ,421,421,421
BEGIN DESCRIPTION:
SALTY CREEK_SUGAR CREEK 100.0
END DESCRIPTION:
XS GIS Cut Line= 3
      2399347.98     13699171.86      2399046.87     13698532.47
      2398593.35     13698082.66
#Sta/Elev= 30
  4130.9  363.46  4175.1  364.06  4294.6  360.85  4490.2  360.21  4573.6  360.24
  4613.7  360.97  4624.8  361.73    4642  360.99  4670.3  361.58  4715.9  360.43
  4844.2  358.98  4851.3  358.06  4858.4  357.68  4886.7  356.96  4910.1  355.85
  4948.7  355.21  4999.8  355.24  5013.9  354.78  5016.1  354.04  5016.6  353.54
  5025.4  353.54  5025.9  354.04  5056.4  356.17  5084.7  359.56  5092.7  359.87
  5098.8   360.5  5148.3   362.8  5247.3  365.06  5369.1  369.45  5476.4  373.08
#Mann= 8 ,-1 , 0
  4130.9    .035       0  4490.2     .12       0  4910.1     .05       0
  4948.7     .12       0  5016.1     .05       0  5025.9     .12       0
  5092.7    .035       0  5369.1     .05       0
Bank Sta=5016.1,5025.9
XS Rating Curve= 0 ,0
Exp/Cntr=0.3,0.1

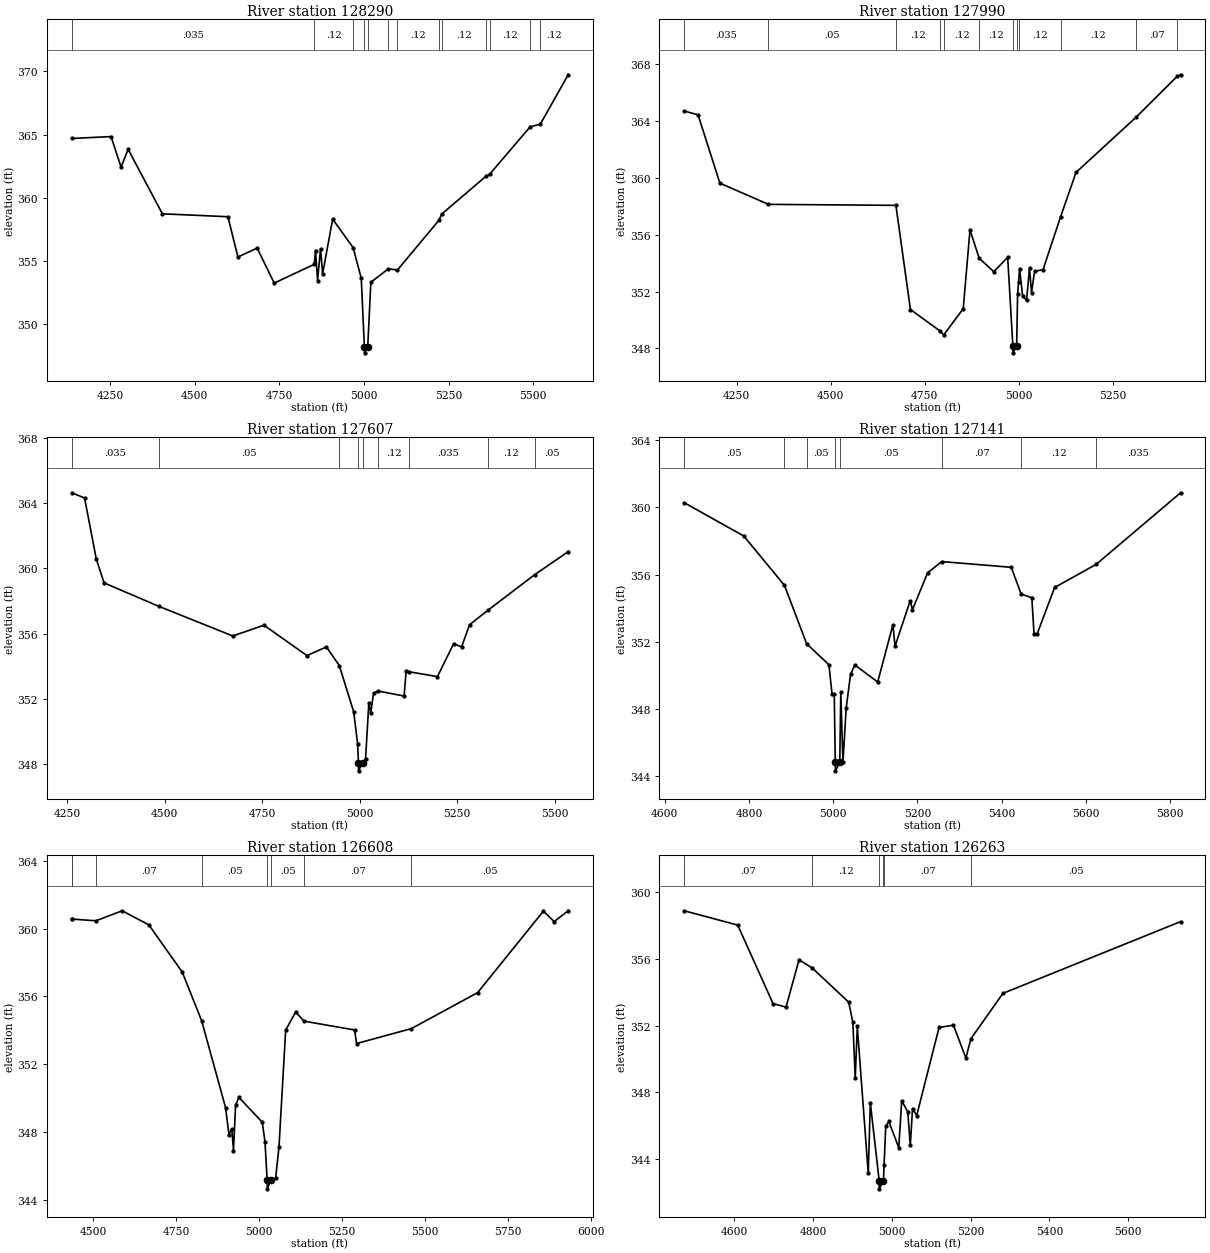
Type RM Length L Ch R = 1 ,128290  ,300,300,300
BEGIN DESCRIPTION:
E20610
END DESCRIPTION:
XS GIS Cut Line= 3
      2399794.11     13699008.33      2399347.99     13698372.61
      2398842.37     13697904.17
#Sta/Elev= 30
  4137.2  364.69  4253.1  364.84  4282.7  362.43  4303.6  363.83  4404.7  358.74
  4598.2  358.51  4627.8  355.33  4684.5  356.03    4735  353.27  4853.2  354.75
    4857  355.84  4863.1  353.47  4871.8  355.99  4877.9  353.99  4907.6  358.32
  4968.2  356.06  4992.1  353.64  5001.2  348.26  5001.7  347.76  5011.2  348.26
  5020.4  353.33  5072.2   354.4  5098.9   354.3  5221.8  358.24  5229.6  358.72
  5360.2   361.7  5371.4  361.87  5490.9  365.61  5520.9  365.82  5603.1  369.72
#Mann= 13 ,-1 , 0
  4137.2    .035       0  4853.2     .12       0  4968.2     .12       0
  5001.2     .05       0  5011.2     .12       0  5072.2     .12       0
  5098.9     .12       0  5221.8    .035       0  5229.6     .12       0
  5360.2    .035       0  5371.4     .12       0  5490.9     .07       0
  5520.9     .12       0
Bank Sta=5001.2,5011.2
XS Rating Curve= 0 ,0
Exp/Cntr=0.3,0.1

Type RM Length L Ch R = 1 ,127990  ,383,383,383
BEGIN DESCRIPTION:
SALTY CREEK_SUGAR CREEK 99.0
END DESCRIPTION:
XS GIS Cut Line= 3
      2399820.12     13699019.45      2399522.72     13698123.54
      2399318.23     13697807.51
#Sta/Elev= 30
  4110.4  364.71  4147.2  364.44  4205.3  359.63  4334.5  358.14  4673.5  358.07
  4712.1  350.74  4790.2  349.24  4800.8  348.95  4852.6   350.8  4870.5  356.34
    4895  354.35  4933.9   353.4  4970.8  354.41  4984.6  348.19  4985.1  347.69
  4994.7  348.19  4997.2  351.85  4999.7  352.67  5002.5  353.59  5010.7  351.67
  5021.2   351.4  5028.9  353.68  5034.2  351.91  5042.3  353.42  5064.9  353.55
  5111.6  357.27  5152.7  360.39  5312.6  364.28  5421.7  367.15  5430.8  367.26
#Mann= 12 ,-1 , 0
  4110.4    .035       0  4334.5     .05       0  4673.5     .12       0
  4790.2     .12       0  4800.8     .12       0    4895     .12       0
  4984.6     .05       0  4994.7     .12       0  4999.7     .12       0
  5111.6     .12       0  5312.6     .07       0  5421.7    .035       0
Bank Sta=4984.6,4994.7
XS Rating Curve= 0 ,0
Exp/Cntr=0.3,0.1

Type RM Length L Ch R = 1 ,127607  ,466,466,466
BEGIN DESCRIPTION:
SALTY CREEK_SUGAR CREEK 98.0
END DESCRIPTION:
XS GIS Cut Line= 3
      2399861.02     13699067.76        2399875.       13698325.
      2399994.57     13697808.76
#Sta/Elev= 30
  4261.8  364.63  4294.6  364.31  4324.6  360.57  4344.6  359.11  4485.6  357.67
  4674.6  355.86  4754.6  356.52  4864.7  354.66  4914.7  355.19  4947.7  354.05
  4984.7  351.21  4994.7  349.25  4996.8   348.1  4997.3   347.6  5007.5   348.1
    5015  348.31  5023.5  351.75  5028.6  351.17  5035.5  352.35    5047  352.49
    5114  352.18  5119.1   353.7  5126.3  353.67  5199.4  353.37  5240.8  355.38
  5261.3  355.19  5281.8  356.55  5328.5  357.43  5448.6  359.61  5534.6  361.02
#Mann= 9 ,-1 , 0
  4261.8    .035       0  4485.6     .05       0  4947.7     .12       0
  4996.8     .05       0  5007.5     .12       0    5047     .12       0
  5126.3    .035       0  5328.5     .12       0  5448.6     .05       0
Bank Sta=4996.8,5007.5
XS Rating Curve= 0 ,0
Exp/Cntr=0.3,0.1

Type RM Length L Ch R = 1 ,127141  ,533,533,533
BEGIN DESCRIPTION:
SALTY CREEK_SUGAR CREEK 97.0
END DESCRIPTION:
XS GIS Cut Line= 3
        2400175.     13698974.99        2400225.       13698625.
      2400024.99     13697824.97
#Sta/Elev= 30
  4646.5  360.27  4787.9  358.29  4884.3  355.36  4937.1  351.88  4989.9  350.64
  4997.5  348.87  5002.6  348.87    5005  344.83  5005.5  344.33  5015.7  344.83
  5018.1     349  5023.2  344.83    5031  348.08  5041.3  350.08  5051.6  350.62
  5105.7  349.61  5141.8  353.01  5146.9  351.74    5183  354.45  5188.2  353.91
  5224.2   356.1  5257.8  356.77  5422.7  356.43  5446.3  354.84  5471.6  354.62
  5476.8  352.45  5484.5  352.49  5525.7  355.23    5624   356.6  5824.7  360.86
#Mann= 8 ,-1 , 0
  4646.5     .05       0  4884.3     .07       0  4937.1     .05       0
    5005     .05       0  5015.7     .05       0  5257.8     .07       0
  5446.3     .12       0    5624    .035       0
Bank Sta=5005,5015.7
XS Rating Curve= 0 ,0
Exp/Cntr=0.3,0.1

Type RM Length L Ch R = 1 ,126608  ,345,345,345
BEGIN DESCRIPTION:
E20609
END DESCRIPTION:
XS GIS Cut Line= 3
      2400578.85     13699085.79      2400508.53     13698390.32
      2400266.27     13697632.31
#Sta/Elev= 30
  4435.9  360.56  4436.5  360.56  4508.5  360.46  4587.5  361.05  4667.9  360.22
  4768.4  357.44    4827  354.56    4899  349.44  4909.1  347.85  4917.8  348.19
  4922.8   346.9  4929.2  349.58  4939.2  350.04  5009.6  348.58  5017.7  347.42
  5024.3  345.15  5024.8  344.65  5035.1  345.15  5049.8  345.28  5059.9  347.14
    5080  354.01  5110.1  355.08  5135.2  354.54  5287.5  354.02  5293.5  353.22
  5458.5   354.1  5657.9  356.22  5856.2  361.03  5888.4  360.41  5930.7  361.05
#Mann= 8 ,-1 , 0
  4435.9     .07       0  4436.5     .05       0  4508.5     .07       0
    4827     .05       0  5024.3     .05       0  5035.1     .05       0
  5135.2     .07       0  5458.5     .05       0
Bank Sta=5024.3,5035.1
XS Rating Curve= 0 ,0
Exp/Cntr=0.3,0.1

Type RM Length L Ch R = 1 ,126263  ,493,493,493
BEGIN DESCRIPTION:
SALTY CREEK_SUGAR CREEK 96.0
END DESCRIPTION:
XS GIS Cut Line= 3
      2400674.99     13698925.04        2400825.       13698425.
        2400475.     13697774.99
#Sta/Elev= 30
  4472.6   358.9  4608.4  358.04    4698  353.33    4731  353.11  4764.1  355.96
  4798.2  355.45  4890.2  353.41  4900.7   352.2  4906.8  348.86    4912  351.95
  4939.8  343.14  4945.1  347.37  4967.5   342.7    4968   342.2  4978.4   342.7
  4980.1  343.65  4984.2  345.95    4992  346.25  5017.4  344.67  5024.7  347.49
  5040.1  346.83  5046.6  344.82  5052.3  347.02  5062.8   346.6  5119.6  351.89
  5156.1  352.03  5187.7  350.06  5200.6  351.22  5281.8  353.94  5732.9  358.25
#Mann= 6 ,-1 , 0
  4472.6     .07       0  4798.2     .12       0  4967.5     .05       0
  4978.4     .12       0  4980.1     .07       0  5200.6     .05       0
Bank Sta=4967.5,4978.4
XS Rating Curve= 0 ,0
Exp/Cntr=0.3,0.1

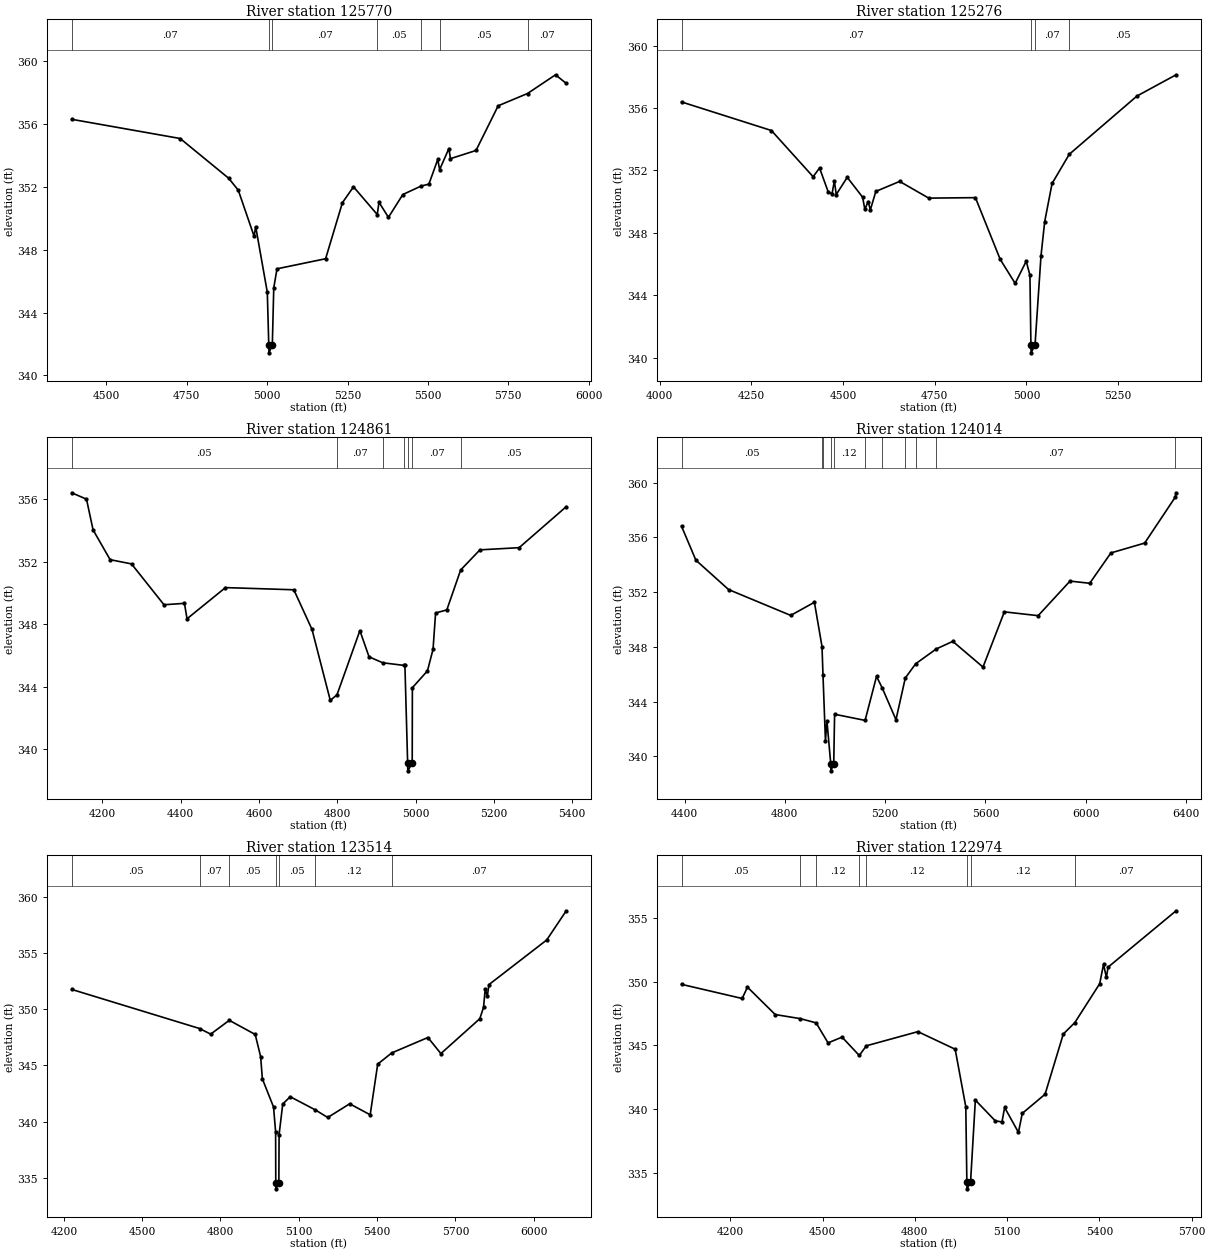
Type RM Length L Ch R = 1 ,125770  ,494,494,494
BEGIN DESCRIPTION:
E20608
END DESCRIPTION:
XS GIS Cut Line= 3
      2401047.74     13698781.07      2401118.07     13698015.22
      2400914.88      13697272.8
#Sta/Elev= 30
  4391.8  356.28  4729.3  355.06  4879.9  352.54    4910  351.78  4959.3  348.85
  4964.3  349.46  5000.4  345.29    5005  341.94  5005.5  341.44    5016  341.94
  5020.5  345.57  5030.6  346.78  5181.8  347.42  5234.1  350.98  5268.6  351.99
  5342.5  350.23  5347.9  351.01  5377.3  350.05  5422.1   351.5  5479.1  352.04
  5503.2  352.16  5530.8  353.73  5536.6  353.08  5565.3  354.42  5570.4  353.78
  5649.8   354.3  5718.8  357.14  5810.1  357.92  5897.2  359.11  5930.6  358.56
#Mann= 7 ,-1 , 0
  4391.8     .07       0    5005     .05       0    5016     .07       0
  5342.5     .05       0  5479.1     .07       0  5536.6     .05       0
  5810.1     .07       0
Bank Sta=5005,5016
XS Rating Curve= 0 ,0
Exp/Cntr=0.3,0.1

Type RM Length L Ch R = 1 ,125276  ,415,415,415
BEGIN DESCRIPTION:
E20607
END DESCRIPTION:
XS GIS Cut Line= 4
       2401133.7     13698741.98      2401250.92     13698296.55
      2401438.47     13698015.22      2401376.06     13697469.09
#Sta/Elev= 30
  4059.7  356.39  4304.7  354.56  4418.5   351.6    4436  352.16  4459.9  350.61
  4470.2  350.52  4476.4  351.34  4481.5  350.46  4511.5  351.56  4553.4  350.29
  4559.5  349.51  4568.5  350.01  4574.5  349.48  4589.5  350.66  4654.4   351.3
  4733.7  350.23    4861  350.26  4928.5  346.31  4969.3  344.77  4999.5  346.19
  5009.6  345.29  5012.3  340.82  5012.8  340.32  5023.5  340.82  5039.8  346.54
  5049.9  348.73    5070  351.17    5117  353.04  5301.5  356.77  5408.1  358.13
#Mann= 4 ,-1 , 0
  4059.7     .07       0  5012.3     .05       0  5023.5     .07       0
    5117     .05       0
Bank Sta=5012.3,5023.5
XS Rating Curve= 0 ,0
Exp/Cntr=0.3,0.1

Type RM Length L Ch R = 1 ,124861  ,847,847,847
BEGIN DESCRIPTION:
SALTY CREEK_SUGAR CREEK 94.0
END DESCRIPTION:
XS GIS Cut Line= 3
      2402124.99     13698574.99        2401775.       13697775.
      2401475.01     13697525.01
#Sta/Elev= 30
  4121.5  356.43  4159.3  356.02  4176.1  354.05  4219.7  352.14  4274.3  351.87
  4357.3  349.25  4409.6  349.34  4416.2  348.35  4514.4  350.35  4689.1  350.21
  4735.5  347.67  4782.2  343.12  4799.3  343.47  4857.9  347.59  4881.3  345.91
  4916.1  345.53    4971  345.36  4972.9  345.39  4979.9   339.1  4980.4   338.6
  4991.6   339.1    4992  343.93  5030.5  345.01  5044.8  346.39  5051.3  348.72
    5080  348.92  5115.4  351.48  5164.6  352.77  5264.8  352.91  5385.2  355.54
#Mann= 7 ,-1 , 0
  4121.5     .05       0  4799.3     .07       0  4916.1     .12       0
    4971     .07       0  4979.9     .05       0  4991.6     .07       0
  5115.4     .05       0
Bank Sta=4979.9,4991.6
XS Rating Curve= 0 ,0
Exp/Cntr=0.3,0.1

Type RM Length L Ch R = 1 ,124014  ,500,500,500
BEGIN DESCRIPTION:
E20606
END DESCRIPTION:
XS GIS Cut Line= 3
      2402766.97     13698343.44      2402329.34     13697647.93
      2401564.25     13696789.15
#Sta/Elev= 30
  4388.1  356.82  4445.3  354.34  4575.7  352.19  4823.4   350.3  4917.9  351.26
  4948.2  348.02  4952.1  345.94  4961.9  341.12  4967.8   342.6  4983.1  339.43
  4983.6  338.93  4994.9  339.43  4998.4  343.07    5120  342.62  5165.6  345.84
  5189.1  344.96  5243.1  342.67  5280.3  345.72  5321.5  346.76  5404.1  347.85
  5469.7   348.4  5590.1  346.52  5675.3  350.56    5810  350.28  5937.1  352.81
  6015.6  352.65  6100.1  354.87  6234.7  355.59  6356.7  358.95    6360  359.27
#Mann= 11 ,-1 , 0
  4388.1     .05       0  4948.2     .07       0  4952.1     .12       0
  4983.1     .05       0  4994.9     .12       0    5120     .07       0
  5189.1     .12       0  5280.3     .07       0  5321.5     .12       0
  5404.1     .07       0  6356.7     .05       0
Bank Sta=4983.1,4994.9
XS Rating Curve= 0 ,0
Exp/Cntr=0.3,0.1

Type RM Length L Ch R = 1 ,123514  ,540,540,540
BEGIN DESCRIPTION:
E20605
END DESCRIPTION:
XS GIS Cut Line= 3
      2403063.91     13698015.21      2402438.75     13697265.01
      2401719.89     13696694.61
#Sta/Elev= 30
  4230.1  351.76  4719.7  348.28  4762.4  347.78  4833.7  349.01    4933  347.75
  4953.8  345.77  4960.3   343.8  5003.2  341.29  5011.1  339.08  5011.7  334.51
  5012.2  334.01  5023.5  334.51  5024.4  338.83  5038.4  341.56    5067  342.21
  5163.8  341.03  5210.7  340.36  5294.8  341.58  5373.3   340.6  5402.1  345.11
    5456  346.11  5594.4  347.48  5644.1  346.05  5793.1  349.15  5807.5  350.16
  5813.9   351.8  5821.9  351.16  5828.3  352.19  6049.4  356.16  6124.3  358.76
#Mann= 7 ,-1 , 0
  4230.1     .05       0  4719.7     .07       0  4833.7     .05       0
  5011.7     .05       0  5023.5     .05       0  5163.8     .12       0
    5456     .07       0
Bank Sta=5011.7,5023.5
XS Rating Curve= 0 ,0
Exp/Cntr=0.3,0.1

Type RM Length L Ch R = 1 ,122974  ,361,361,361
BEGIN DESCRIPTION:
E20604
END DESCRIPTION:
XS GIS Cut Line= 3
      2403032.66     13697780.76      2402673.19     13697014.94
      2402009.58      13696640.2
#Sta/Elev= 30
  4041.3  349.78  4238.4  348.67  4255.7  349.56  4345.9  347.41  4427.5  347.09
  4478.8  346.76  4517.7  345.19  4563.3  345.64  4619.2   344.2  4642.4  344.96
  4809.9  346.07  4931.1  344.69  4965.6  340.18  4969.1  334.24  4969.6  333.74
    4981  334.24  4996.7   340.7  5061.6  339.07  5083.3  338.99  5091.9  340.12
  5136.8  338.17  5149.3  339.66  5223.4  341.16  5282.6  345.88  5320.2  346.78
    5401  349.83  5413.5  351.35  5422.7  350.33  5428.4  351.13  5649.4  355.55
#Mann= 8 ,-1 , 0
  4041.3     .05       0  4427.5     .07       0  4478.8     .12       0
  4619.2     .05       0  4642.4     .12       0  4969.1     .05       0
    4981     .12       0  5320.2     .07       0
Bank Sta=4969.1,4981
XS Rating Curve= 0 ,0
Exp/Cntr=0.3,0.1