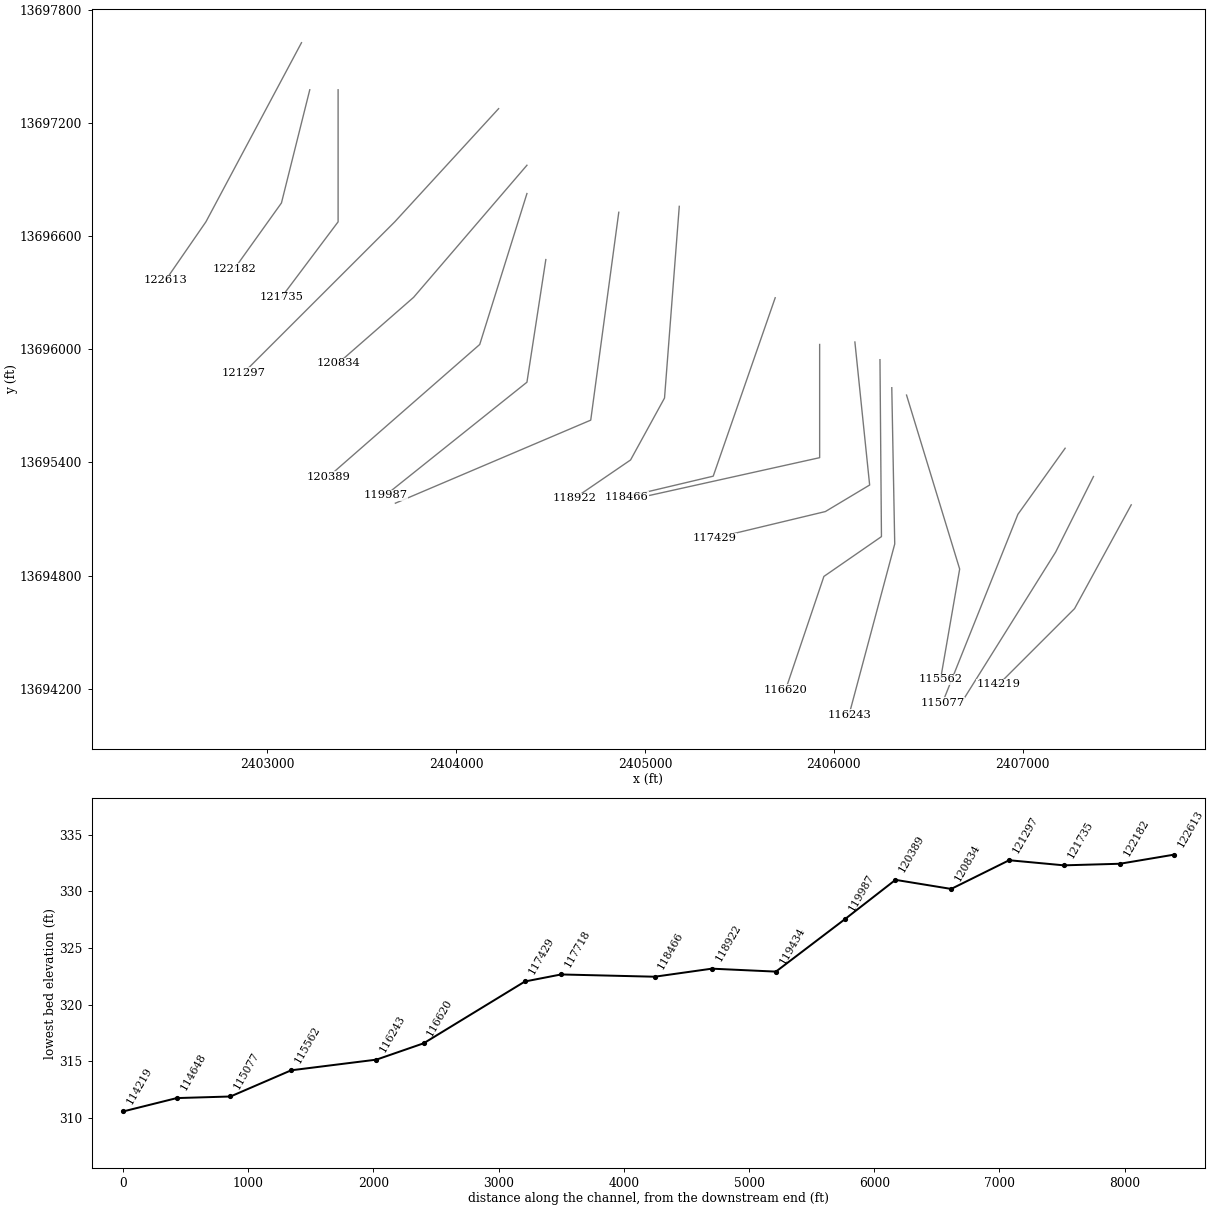
HEC-RAS study SALTY CREEK_SUGAR CREEK.prj: SALTY CREEK_SUGAR CREEK Base Level Engineering

--- SALTY CREEK_SUGAR CREEK.g01 (geometry) --- (continued)

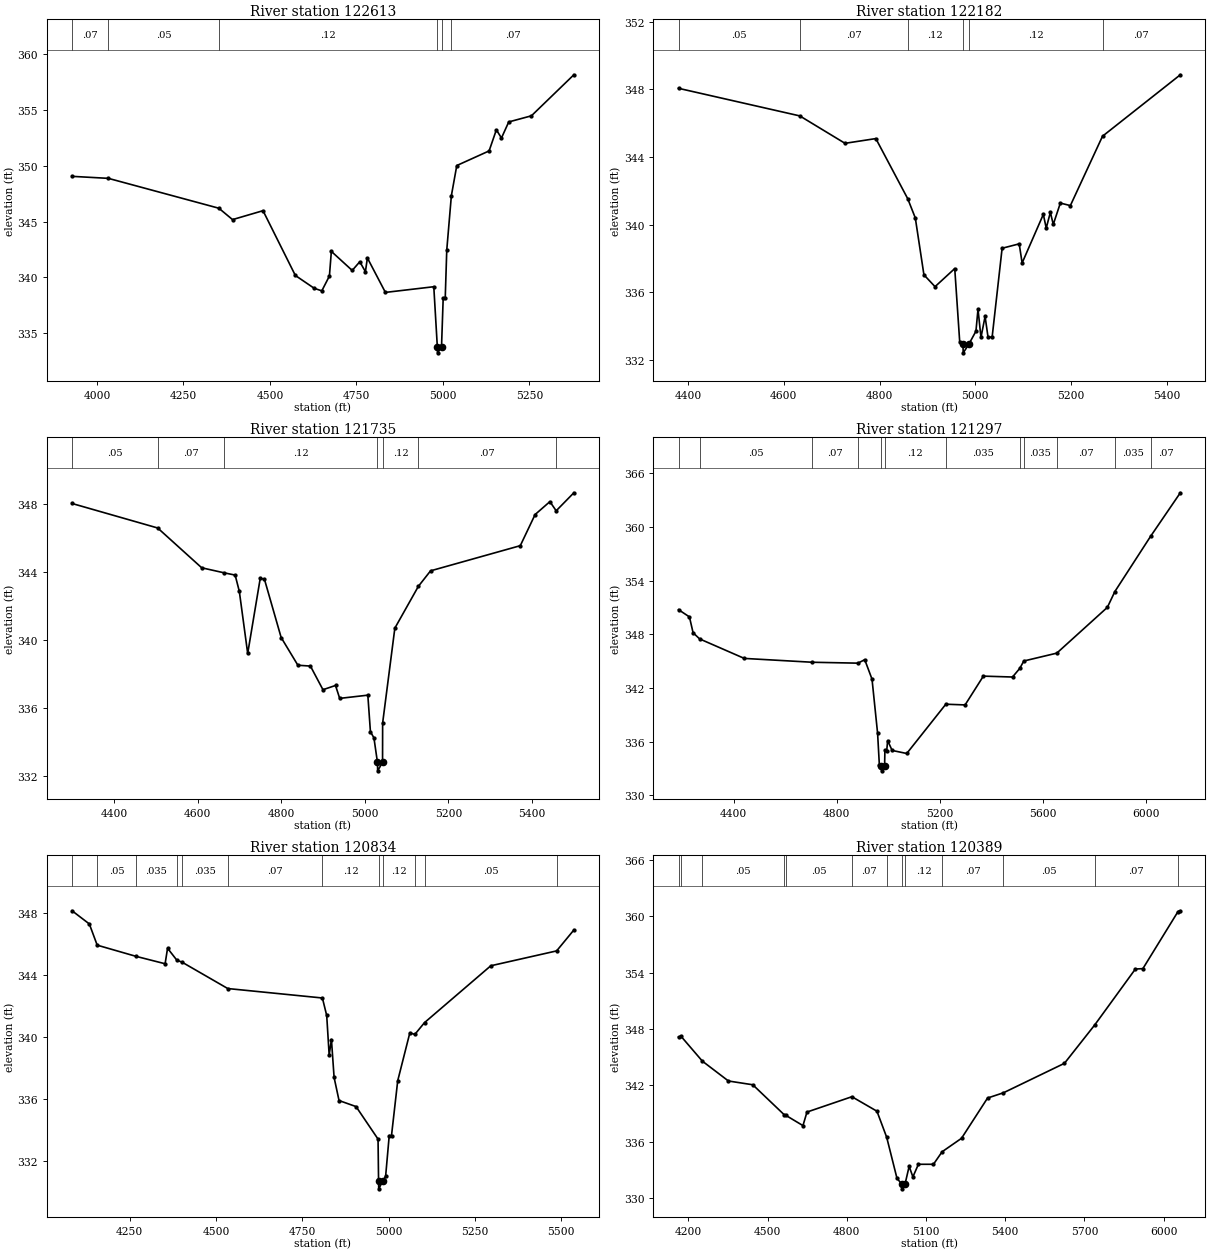
Type RM Length L Ch R = 1 ,122613  ,431,431,431
BEGIN DESCRIPTION:
SALTY CREEK_SUGAR CREEK 91.0
END DESCRIPTION:
XS GIS Cut Line= 3
      2403181.14     13697624.49        2402675.       13696675.
      2402462.19     13696366.32
#Sta/Elev= 30
  3927.9  349.06  4032.8  348.88  4352.4   346.2  4391.9  345.18    4480  345.98
  4573.5  340.17    4628  339.02    4650  338.79    4672  340.12  4677.6  342.33
  4737.9  340.62  4759.8   341.4  4776.1  340.51  4781.8  341.74  4833.9  338.65
  4973.8  339.16  4984.1  333.73  4984.6  333.23  4996.1  333.73    5001  338.16
  5006.9  338.16  5011.3  342.45  5024.6  347.32  5040.3  350.03  5133.7  351.34
  5154.7  353.23  5169.5   352.5  5190.5  353.94  5256.1  354.49  5378.8  358.17
#Mann= 6 ,-1 , 0
  3927.9     .07       0  4032.8     .05       0  4352.4     .12       0
  4984.1     .05       0  4996.1     .12       0  5024.6     .07       0
Bank Sta=4984.1,4996.1
XS Rating Curve= 0 ,0
Exp/Cntr=0.3,0.1

Type RM Length L Ch R = 1 ,122182  ,447,447,447
BEGIN DESCRIPTION:
SALTY CREEK_SUGAR CREEK 90.0
END DESCRIPTION:
XS GIS Cut Line= 3
        2403225.     13697375.01        2403075.       13696775.
      2402824.99     13696424.99
#Sta/Elev= 30
    4380  348.06  4633.4  346.43  4727.9  344.81  4792.3  345.09  4858.9  341.54
  4874.8   340.4  4892.8  337.04    4916  336.34  4957.2  337.41  4967.6  333.07
  4974.4  332.93  4974.9  332.43  4986.5  332.93  5001.5  333.71  5005.8  335.01
    5012  333.34  5020.6  334.58  5026.7  333.37  5035.3  333.35  5056.2  338.61
  5091.9  338.87    5098  337.74  5142.3  340.61  5148.4   339.8    5157  340.73
  5163.1  340.02  5177.9  341.28  5198.8  341.13    5266  345.23  5428.6  348.86
#Mann= 6 ,-1 , 0
    4380     .05       0  4633.4     .07       0  4858.9     .12       0
  4974.4     .05       0  4986.5     .12       0    5266     .07       0
Bank Sta=4974.4,4986.5
XS Rating Curve= 0 ,0
Exp/Cntr=0.3,0.1

Type RM Length L Ch R = 1 ,121735  ,438,438,438
BEGIN DESCRIPTION:
SALTY CREEK_SUGAR CREEK 89.0
END DESCRIPTION:
XS GIS Cut Line= 3
        2403375.     13697374.98        2403375.       13696675.
      2403074.99     13696274.98
#Sta/Elev= 30
  4299.8  348.01  4504.5  346.57  4609.8  344.23    4664  343.93  4689.8   343.8
  4699.8  342.84  4719.8  339.19  4749.8  343.61  4759.8  343.56  4799.8  340.13
  4839.8   338.5  4869.8  338.45  4899.8  337.06  4929.8  337.31  4939.8  336.55
  5007.1  336.74  5013.3  334.59  5021.7  334.23  5030.1  332.79  5030.6  332.29
  5042.3  332.79  5042.5   335.1  5071.7  340.68    5128  343.14  5157.1  344.05
  5371.7  345.53  5407.1  347.36  5442.5  348.12  5457.5  347.58  5499.8  348.64
#Mann= 7 ,-1 , 0
  4299.8     .05       0  4504.5     .07       0    4664     .12       0
  5030.1     .05       0  5042.3     .12       0    5128     .07       0
  5457.5    .035       0
Bank Sta=5030.1,5042.3
XS Rating Curve= 0 ,0
Exp/Cntr=0.3,0.1

Type RM Length L Ch R = 1 ,121297  ,463,463,463
BEGIN DESCRIPTION:
SALTY CREEK_SUGAR CREEK 88.0
END DESCRIPTION:
XS GIS Cut Line= 3
      2404225.01     13697275.01        2403675.       13696675.
      2402875.02     13695875.02
#Sta/Elev= 30
  4186.6  350.76  4228.9  349.95    4243  348.18  4268.4  347.49  4441.6  345.31
  4705.8  344.88  4882.2  344.78  4908.4  345.17  4936.7  342.99  4958.3  336.94
  4965.1  333.41  4973.2  333.24  4973.7  332.74  4985.4  333.24  4986.7  335.08
  4993.5  334.92  4997.2  336.12  5014.7  335.02  5071.3  334.68  5222.8  340.19
  5297.5  340.11  5368.3  343.33  5481.4  343.23  5509.6   344.2  5525.1  345.02
    5653   345.9  5849.1  351.02  5878.2  352.79  6016.6  358.96  6131.9  363.83
#Mann= 12 ,-1 , 0
  4186.6    .035       0  4268.4     .05       0  4705.8     .07       0
  4882.2     .12       0  4973.2     .05       0  4985.4     .12       0
  5222.8    .035       0  5509.6     .07       0  5525.1    .035       0
    5653     .07       0  5878.2    .035       0  6016.6     .07       0
Bank Sta=4973.2,4985.4
XS Rating Curve= 0 ,0
Exp/Cntr=0.3,0.1

Type RM Length L Ch R = 1 ,120834  ,445,445,445
BEGIN DESCRIPTION:
SALTY CREEK_SUGAR CREEK 87.0
END DESCRIPTION:
XS GIS Cut Line= 3
      2404375.01     13696975.01        2403775.       13696275.
      2403374.98     13695924.99
#Sta/Elev= 30
    4083  348.16    4133  347.31  4155.8  345.94    4268  345.22  4352.5  344.74
  4359.6  345.74  4386.9  344.96    4401  344.85    4534  343.14  4808.1  342.53
  4820.6   341.4  4827.7  338.85  4834.3  339.85    4842   337.4  4856.3  335.91
  4905.6  335.52  4969.3  333.42  4970.8  330.71  4971.3  330.21  4983.1  330.71
  4991.3  331.03  5001.7  333.65  5008.3  333.65  5026.3  337.19  5061.4  340.28
  5075.9  340.18  5103.9  340.94  5295.9  344.61  5486.6  345.57  5536.5  346.92
#Mann= 12 ,-1 , 0
    4083    .035       0  4155.8     .05       0    4268    .035       0
  4386.9     .07       0    4401    .035       0    4534     .07       0
  4808.1     .12       0  4970.8     .05       0  4983.1     .12       0
  5075.9    .035       0  5103.9     .05       0  5486.6     .07       0
Bank Sta=4970.8,4983.1
XS Rating Curve= 0 ,0
Exp/Cntr=0.3,0.1

Type RM Length L Ch R = 1 ,120389  ,402,402,402
BEGIN DESCRIPTION:
SALTY CREEK_SUGAR CREEK 86.0
END DESCRIPTION:
XS GIS Cut Line= 3
      2404374.99     13696824.95        2404125.       13696025.
      2403325.01     13695325.01
#Sta/Elev= 30
  4162.4  347.14  4172.2  347.21  4252.7  344.58  4351.5  342.47  4443.7  342.07
  4561.8  338.91  4568.3  338.83  4633.8  337.73    4649  339.17  4819.2   340.8
  4914.1  339.26    4951  336.49    4990  332.13  5008.1  331.51  5008.6  331.01
  5020.5  331.51  5036.1   333.4  5050.3  332.28  5071.2  333.62  5128.2  333.62
    5161  334.95  5234.5  336.38  5333.2  340.66  5393.5  341.22  5624.5  344.35
    5739  348.42  5893.2  354.37  5921.6  354.41  6054.8  360.48  6063.5  360.56
#Mann= 13 ,-1 , 0
  4162.4     .05       0  4172.2    .035       0  4252.7     .05       0
  4561.8     .07       0  4568.3     .05       0  4819.2     .07       0
    4951     .12       0  5008.1     .05       0  5020.5     .12       0
    5161     .07       0  5393.5     .05       0    5739     .07       0
  6054.8    .035       0
Bank Sta=5008.1,5020.5
XS Rating Curve= 0 ,0
Exp/Cntr=0.3,0.1

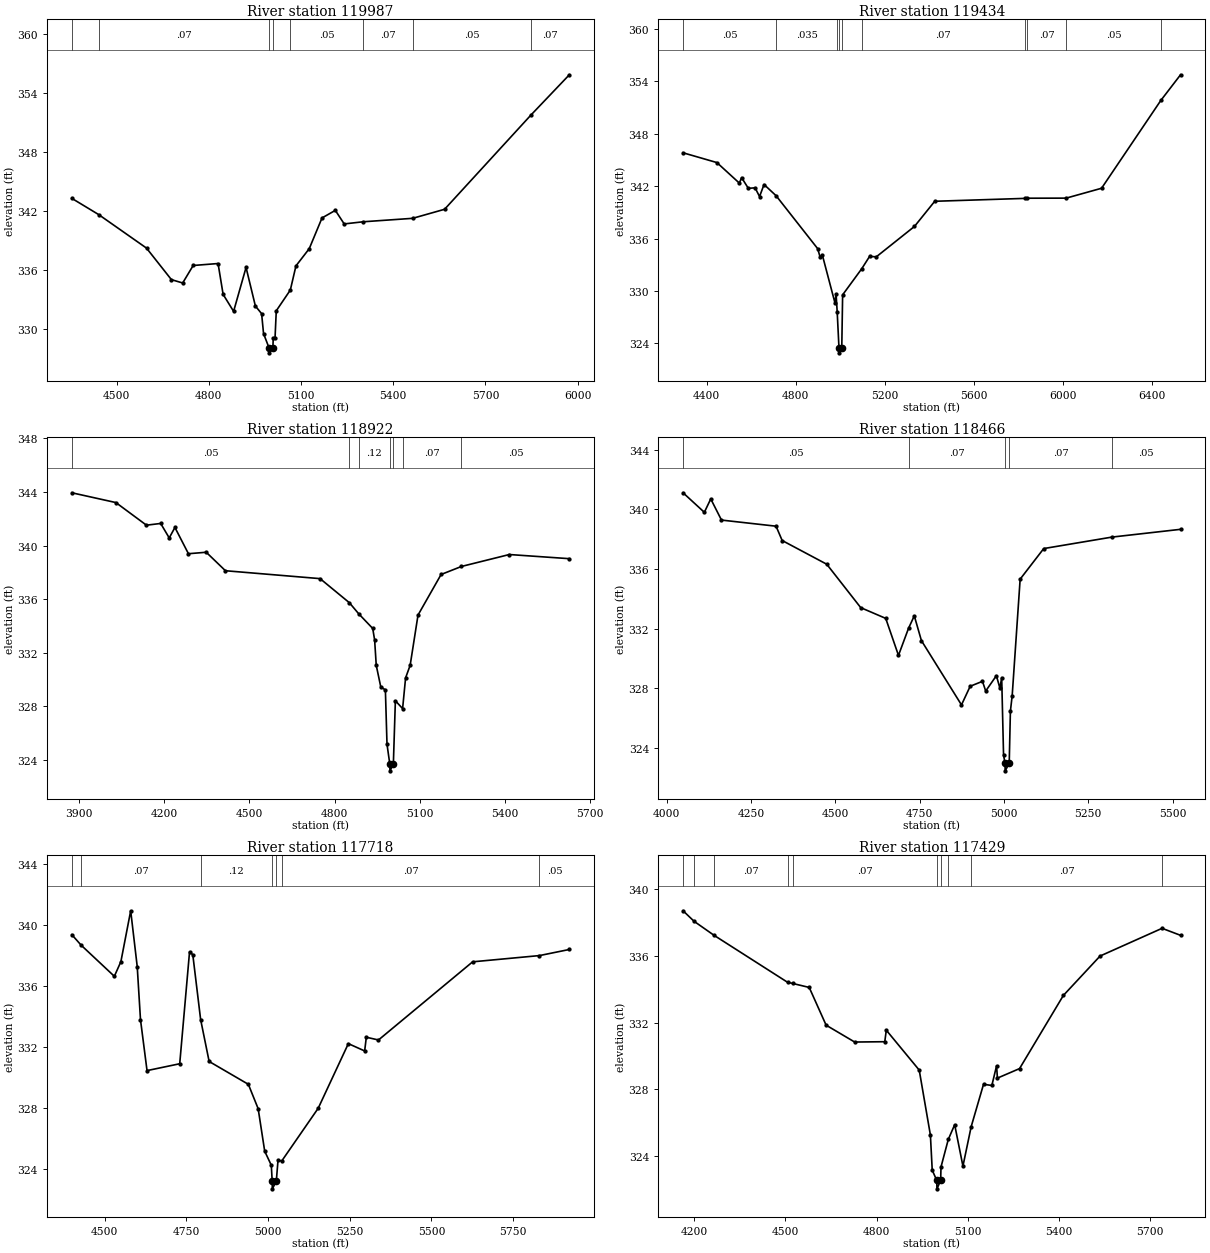
Type RM Length L Ch R = 1 ,119987  ,553,553,553
BEGIN DESCRIPTION:
SALTY CREEK_SUGAR CREEK 85.0
END DESCRIPTION:
XS GIS Cut Line= 3
        2404475.     13696475.02        2404375.       13695825.
      2403625.03     13695225.02
#Sta/Elev= 30
  4354.7  343.28    4442  341.63  4597.5  338.22  4678.5  335.01  4715.2  334.67
  4749.3  336.45  4830.3  336.65  4846.7  333.51  4880.8  331.78  4921.3  336.25
  4951.7  332.32  4971.9  331.55  4978.2  329.52  4996.1  328.06  4996.6  327.56
  5008.5  328.06  5009.8  329.09  5015.6  329.09  5019.6  331.84  5065.3  333.95
  5083.6  336.41  5126.8  338.16  5168.4  341.29  5211.7  342.06  5240.5  340.68
  5302.7   340.9  5463.2  341.25    5567  342.17  5847.9  351.76  5972.8  355.86
#Mann= 8 ,-1 , 0
  4354.7     .05       0    4442     .07       0  4996.1     .05       0
  5008.5     .07       0  5065.3     .05       0  5302.7     .07       0
  5463.2     .05       0  5847.9     .07       0
Bank Sta=4996.1,5008.5
XS Rating Curve= 0 ,0
Exp/Cntr=0.3,0.1

Type RM Length L Ch R = 1 ,119434  ,512,512,512
BEGIN DESCRIPTION:
E20603
END DESCRIPTION:
XS GIS Cut Line= 3
      2404861.29     13696725.77      2404712.82     13695623.93
      2403678.38     13695183.74
#Sta/Elev= 30
  4293.4  345.82  4445.5   344.7  4546.4  342.35  4556.5  342.98  4586.8  341.75
  4617.1  341.81  4637.2  340.81  4657.4  342.19  4711.4  340.91  4898.3  334.85
  4909.7  333.86  4919.8  334.08  4976.1  328.64  4981.2  329.64  4986.2   327.6
  4994.3  323.42  4994.8  322.92  5006.7  323.42  5010.6  329.56  5096.6  332.55
  5131.8  333.96  5161.9  333.91  5333.5  337.39  5424.6  340.27  5829.3   340.6
  5839.8  340.62  6015.3  340.63  6174.4  341.76  6440.7  351.81  6529.4  354.75
#Mann= 10 ,-1 , 0
  4293.4     .05       0  4711.4    .035       0  4986.2     .12       0
  4994.3     .05       0  5006.7     .12       0  5096.6     .07       0
  5829.3     .05       0  5839.8     .07       0  6015.3     .05       0
  6440.7     .07       0
Bank Sta=4994.3,5006.7
XS Rating Curve= 0 ,0
Exp/Cntr=0.3,0.1

Type RM Length L Ch R = 1 ,118922  ,456,456,456
BEGIN DESCRIPTION:
E20602
END DESCRIPTION:
XS GIS Cut Line= 4
       2405181.7     13696757.09      2405103.55     13695741.15
      2404923.82     13695412.93      2404626.83     13695209.73
#Sta/Elev= 30
  3874.4  343.94  4029.5  343.21  4137.3  341.52  4187.4  341.65  4217.5  340.57
  4237.6  341.35  4285.2  339.39  4347.9   339.5  4415.6  338.12  4749.1  337.53
  4852.4  335.73    4885  334.91  4934.6  333.81  4941.3  332.95    4947  331.06
  4963.1  329.43  4979.2  329.23  4984.9  325.17  4994.8  323.68  4995.3  323.18
  5007.3  323.68  5014.4  328.41  5039.9  327.83  5050.4  330.12  5066.5  331.06
  5094.2  334.81  5175.5  337.84  5247.4  338.44    5416  339.33  5627.4  339.02
#Mann= 7 ,-1 , 0
  3874.4     .05       0  4852.4     .07       0    4885     .12       0
  4994.8     .05       0  5007.3     .12       0  5039.9     .07       0
  5247.4     .05       0
Bank Sta=4994.8,5007.3
XS Rating Curve= 0 ,0
Exp/Cntr=0.3,0.1

Type RM Length L Ch R = 1 ,118466  ,748,748,748
BEGIN DESCRIPTION:
E20601
END DESCRIPTION:
XS GIS Cut Line= 3
      2405689.66     13696272.57      2405361.44     13695326.97
      2404900.39     13695217.57
#Sta/Elev= 30
    4049  341.11  4112.1   339.8  4131.1   340.7  4162.9  339.28  4324.7  338.87
  4342.8  337.91    4475  336.32  4575.7  333.41  4649.8  332.69  4687.6  330.21
  4717.5  332.03  4734.5  332.86  4755.6   331.2  4874.4  326.89  4900.2  328.14
  4936.6  328.47  4946.2  327.82  4977.9  328.85  4988.3  328.01  4993.6  328.72
  4999.1  323.54  5003.4  322.97  5003.9  322.47  5015.9  322.97  5019.4  326.47
  5024.7  327.51  5048.3  335.32  5118.2  337.37  5320.7  338.14  5523.8  338.66
#Mann= 5 ,-1 , 0
    4049     .05       0  4717.5     .07       0  5003.4     .05       0
  5015.9     .07       0  5320.7     .05       0
Bank Sta=5003.4,5015.9
XS Rating Curve= 0 ,0
Exp/Cntr=0.3,0.1

Type RM Length L Ch R = 1 ,117718  ,289,289,289
BEGIN DESCRIPTION:
SALTY CREEK_SUGAR CREEK 81.0
END DESCRIPTION:
XS GIS Cut Line= 3
        2405925.       13696025.        2405925.       13695425.
      2405024.96     13695224.99
#Sta/Elev= 30
    4400  339.35  4428.5  338.66    4530  336.62    4550  337.58    4580  340.92
    4600  337.26    4610  333.77    4630  330.43    4730  330.88    4760  338.21
    4770  338.04    4794  333.78    4820  331.03    4940  329.53    4970  327.93
    4990  325.14  5010.2  324.22  5012.9  323.17  5013.4  322.67  5025.5  323.17
  5030.7  324.54  5042.2   324.5  5153.7  327.96  5245.9   332.2  5295.8  331.72
  5300.9  332.62  5338.1  332.44  5626.2  337.57  5830.7  337.98    5922  338.38
#Mann= 7 ,-1 , 0
    4400     .05       0  4428.5     .07       0    4794     .12       0
  5012.9     .05       0  5025.5     .12       0  5042.2     .07       0
  5830.7     .05       0
Bank Sta=5012.9,5025.5
XS Rating Curve= 0 ,0
Exp/Cntr=0.3,0.1

Type RM Length L Ch R = 1 ,117429  ,809,809,809
BEGIN DESCRIPTION:
E20600
END DESCRIPTION:
XS GIS Cut Line= 4
      2406111.65     13696038.09      2406189.79     13695280.08
      2405955.35     13695139.42      2405369.61     13694998.84
#Sta/Elev= 30
    4163   338.7  4199.3  338.07  4265.1  337.23  4506.9  334.42  4523.4  334.35
  4578.3  334.11    4634  331.85    4728  330.84  4827.1  330.86  4832.1  331.55
  4940.5  329.16  4977.3  325.27  4983.3  323.17  4998.3  322.55  4998.8  322.05
    5011  322.55  5012.2  323.36  5036.2  325.01  5057.2  325.89  5084.4  323.41
  5111.5  325.77  5152.2  328.31  5179.6  328.24  5195.2  329.42  5197.9  328.68
  5270.8  329.25    5415  333.63  5535.9  335.99    5740  337.65  5800.8  337.23
#Mann= 10 ,-1 , 0
    4163     .07       0  4199.3     .05       0  4265.1     .07       0
  4506.9     .05       0  4523.4     .07       0  4998.3     .05       0
    5011     .07       0  5036.2     .12       0  5111.5     .07       0
    5740     .05       0
Bank Sta=4998.3,5011
XS Rating Curve= 0 ,0
Exp/Cntr=0.3,0.1

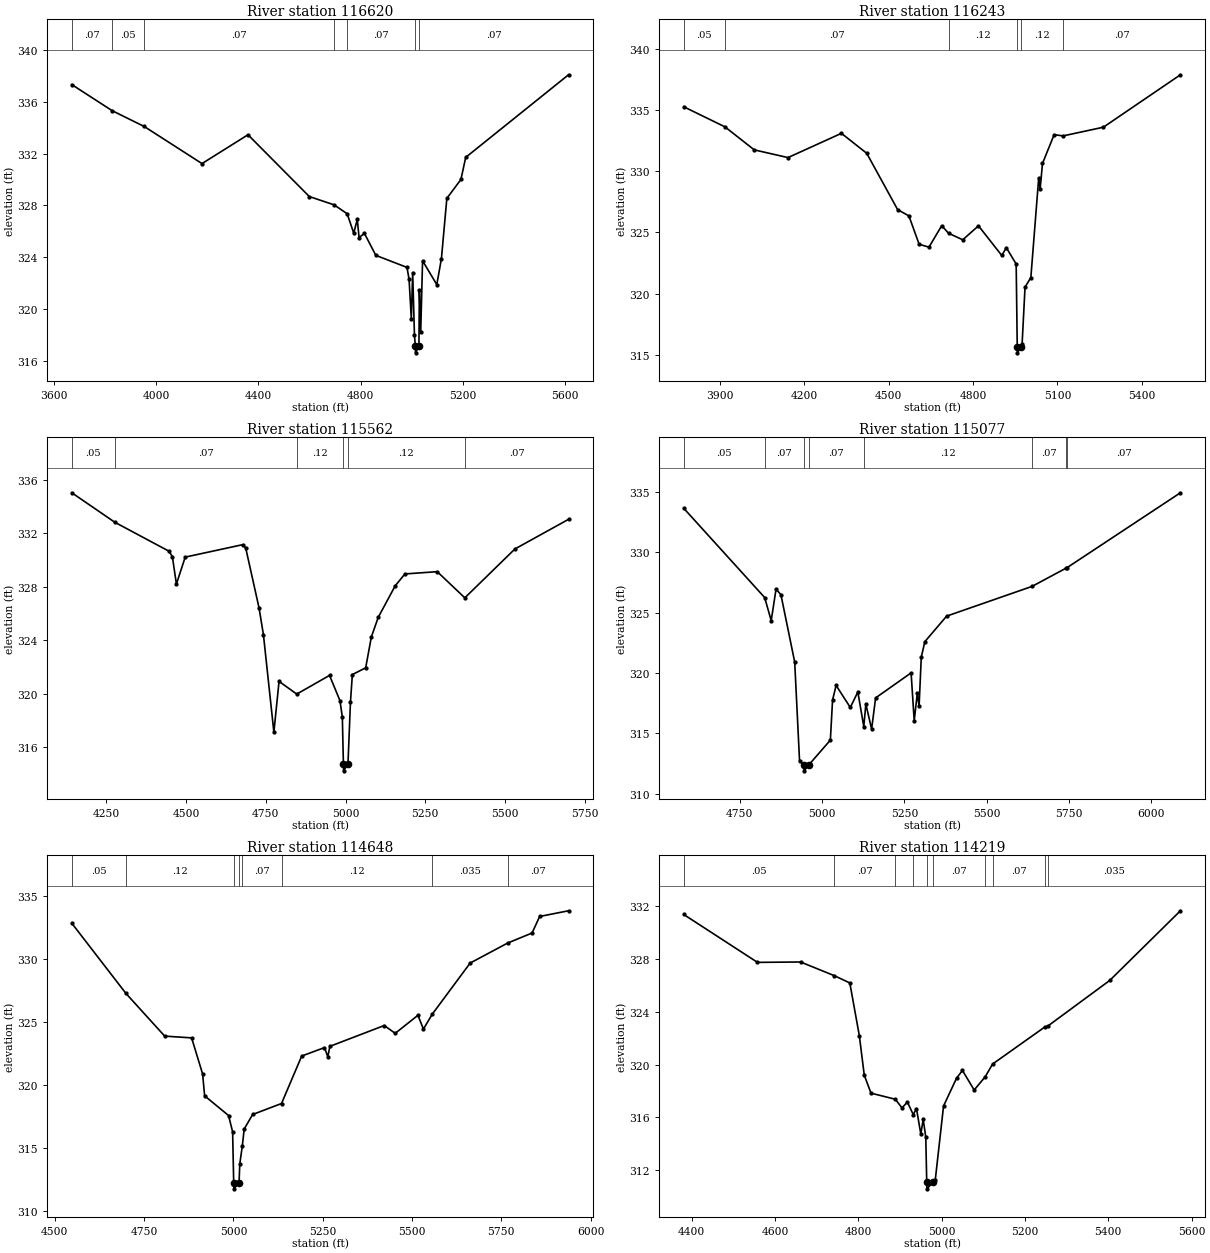
Type RM Length L Ch R = 1 ,116620  ,377,377,377
BEGIN DESCRIPTION:
E20599
END DESCRIPTION:
XS GIS Cut Line= 4
      2406244.49     13695944.38      2406252.31     13695006.57
      2405947.54     13694795.57      2405744.37     13694193.87
#Sta/Elev= 30
  3669.7  337.35  3827.8  335.33    3953  334.11  4179.1  331.24  4359.1  333.47
  4599.1  328.69  4695.8  328.05  4747.2  327.36  4772.8  325.86  4786.7  326.92
  4793.8  325.52  4814.7  325.84  4859.3  324.14  4981.2  323.21  4989.4  322.29
  4998.2  319.22  5003.5  322.81  5010.5  317.95  5014.1   317.1  5014.6   316.6
    5028   317.1  5029.7  321.46    5035  318.24  5042.2  323.72  5097.9  321.88
    5116  323.89  5137.2  328.55  5192.3  330.01    5211  331.72  5613.3  338.11
#Mann= 7 ,-1 , 0
  3669.7     .07       0  3827.8     .05       0    3953     .07       0
  4695.8     .12       0  4747.2     .07       0  5014.1     .05       0
    5028     .07       0
Bank Sta=5014.1,5028
XS Rating Curve= 0 ,0
Exp/Cntr=0.3,0.1

Type RM Length L Ch R = 1 ,116243  ,681,681,681
BEGIN DESCRIPTION:
E20598
END DESCRIPTION:
XS GIS Cut Line= 3
      2406307.01     13695795.88      2406322.64      13694967.5
       2406080.4     13694061.04
#Sta/Elev= 30
  3770.5  335.25  3917.1  333.61  4021.4  331.73  4141.4   331.1  4331.5  333.08
  4421.5  331.45  4531.5  326.85  4571.5  326.34    4608  324.02  4642.9  323.79
  4688.2  325.54  4712.7  324.92  4763.1  324.39    4819  325.53  4901.8  323.11
  4918.2  323.74  4953.1  322.41  4956.9  315.66  4957.4  315.16  4970.8  315.66
  4974.2  315.89  4984.6  320.52  5005.3  321.31  5033.2  329.43  5038.4  328.55
  5046.7  330.62  5088.1  332.97  5119.9  332.87  5263.3  333.58  5537.3  337.86
#Mann= 6 ,-1 , 0
  3770.5     .05       0  3917.1     .07       0  4712.7     .12       0
  4956.9     .05       0  4970.8     .12       0  5119.9     .07       0
Bank Sta=4956.9,4970.8
XS Rating Curve= 0 ,0
Exp/Cntr=0.3,0.1

Type RM Length L Ch R = 1 ,115562  ,485,485,485
BEGIN DESCRIPTION:
E20597
END DESCRIPTION:
XS GIS Cut Line= 3
      2406385.15      13695756.8      2406666.49     13694834.65
      2406565.03     13694249.29
#Sta/Elev= 30
  4141.3  335.05  4276.3  332.84  4446.4  330.67  4456.8  330.26  4469.4  328.21
    4497  330.23  4676.8  331.16  4686.8  330.92  4728.7  326.42  4742.4  324.42
  4775.2  317.12  4791.4  320.92    4847  319.97  4949.8  321.37  4982.6  319.47
    4990  318.24  4993.3  314.72  4993.8  314.22  5007.6  314.72  5015.4  319.36
  5021.4  321.43  5063.2  321.94    5081  324.25  5102.6  325.72  5155.8  328.08
  5186.3  328.97  5287.7  329.14  5374.2  327.18  5531.3  330.84  5699.5  333.06
#Mann= 6 ,-1 , 0
  4141.3     .05       0  4276.3     .07       0    4847     .12       0
  4993.3     .05       0  5007.6     .12       0  5374.2     .07       0
Bank Sta=4993.3,5007.6
XS Rating Curve= 0 ,0
Exp/Cntr=0.3,0.1

Type RM Length L Ch R = 1 ,115077  ,429,429,429
BEGIN DESCRIPTION:
SALTY CREEK_SUGAR CREEK 78.0
END DESCRIPTION:
XS GIS Cut Line= 3
      2407225.02     13695475.03        2406975.       13695125.
      2406574.99     13694124.98
#Sta/Elev= 30
  4580.6  333.62  4826.2  326.24  4846.1  324.33  4860.8  326.94  4875.6  326.47
  4917.4   320.9  4932.1  312.73  4945.4  312.41  4945.9  311.91  4960.5  312.41
  5025.6  314.45  5032.3  317.77  5043.1  318.97  5086.1  317.15    5109  318.43
    5127  315.57  5133.3  317.43  5150.8  315.36  5162.9  317.94  5270.6  320.01
    5280  316.06  5289.4  318.31  5294.8  317.25  5301.5  321.31  5312.3  322.59
  5378.3   324.7  5637.6  327.16  5739.6  328.65  5743.9  328.71  6087.8   334.9
#Mann= 8 ,-1 , 0
  4580.6     .05       0  4826.2     .07       0  4945.4     .05       0
  4960.5     .07       0    5127     .12       0  5637.6     .07       0
  5739.6     .12       0  5743.9     .07       0
Bank Sta=4945.4,4960.5
XS Rating Curve= 0 ,0
Exp/Cntr=0.3,0.1

Type RM Length L Ch R = 1 ,114648  ,429,429,429
BEGIN DESCRIPTION:
SALTY CREEK_SUGAR CREEK 77.0
END DESCRIPTION:
XS GIS Cut Line= 3
      2407375.01     13695325.01        2407175.       13694925.
      2406675.01     13694125.02
#Sta/Elev= 30
  4547.5  332.81  4699.1  327.25  4807.5  323.87  4882.9  323.73  4913.7  320.87
  4919.3  319.14  4986.3  317.58  4997.7  316.29  5000.7  312.27  5001.2  311.77
  5015.8  312.27  5017.7  313.73  5024.8  315.16  5030.1  316.51  5053.7  317.66
  5134.6  318.53  5191.1  322.29  5254.8  322.96  5264.2  322.24  5270.1  323.06
  5422.2  324.71  5452.9  324.09  5516.5  325.52  5531.9  324.43  5556.7  325.61
  5662.8  329.66  5767.5  331.24  5836.1  332.04  5857.3  333.35  5938.1   333.8
#Mann= 8 ,-1 , 0
  4547.5     .05       0  4699.1     .12       0  5000.7     .05       0
  5015.8     .12       0  5024.8     .07       0  5134.6     .12       0
  5556.7    .035       0  5767.5     .07       0
Bank Sta=5000.7,5015.8
XS Rating Curve= 0 ,0
Exp/Cntr=0.3,0.1

Type RM Length L Ch R = 1 ,114219  ,470,470,470
BEGIN DESCRIPTION:
SALTY CREEK_SUGAR CREEK 76.0
END DESCRIPTION:
XS GIS Cut Line= 3
      2407575.02     13695175.03        2407275.       13694625.
      2406875.01     13694225.01
#Sta/Elev= 30
  4380.9  331.38    4558  327.75  4661.4  327.78  4742.6  326.74  4779.6  326.19
  4802.4   322.2  4814.3   319.2  4830.4  317.84  4888.7  317.38  4904.9  316.72
  4917.7  317.17  4931.8  316.22  4939.6  316.67    4950  314.74  4955.7  315.85
  4961.9  314.52  4964.2  311.09  4964.7  310.59  4979.4  311.09  4984.6  311.24
  5004.6  316.87  5035.7  318.97  5049.9  319.56  5078.1  318.08  5104.5  319.08
  5122.4  320.05  5247.9  322.86  5255.1  322.93  5403.4  326.38  5573.1  331.66
#Mann= 10 ,-1 , 0
  4380.9     .05       0  4742.6     .07       0  4888.7     .12       0
  4931.8     .07       0  4964.2     .05       0  4979.4     .07       0
  5104.5     .12       0  5122.4     .07       0  5247.9     .12       0
  5255.1    .035       0
Bank Sta=4964.2,4979.4
XS Rating Curve= 0 ,0
Exp/Cntr=0.3,0.1