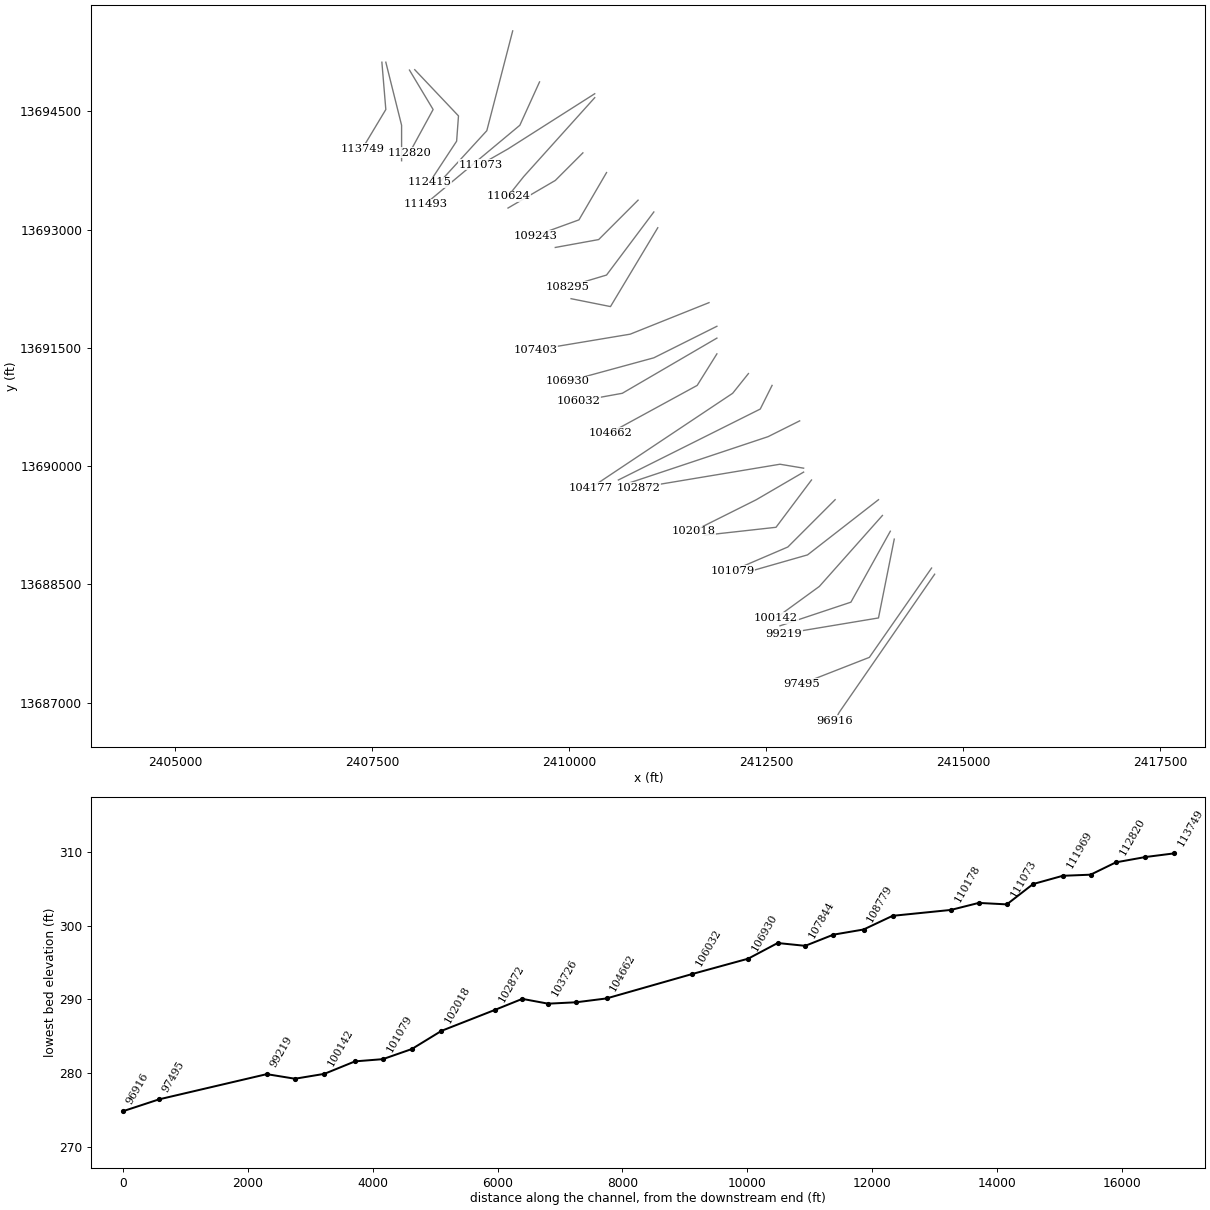
HEC-RAS study SALTY CREEK_SUGAR CREEK.prj: SALTY CREEK_SUGAR CREEK Base Level Engineering

--- SALTY CREEK_SUGAR CREEK.g01 (geometry) --- (continued)

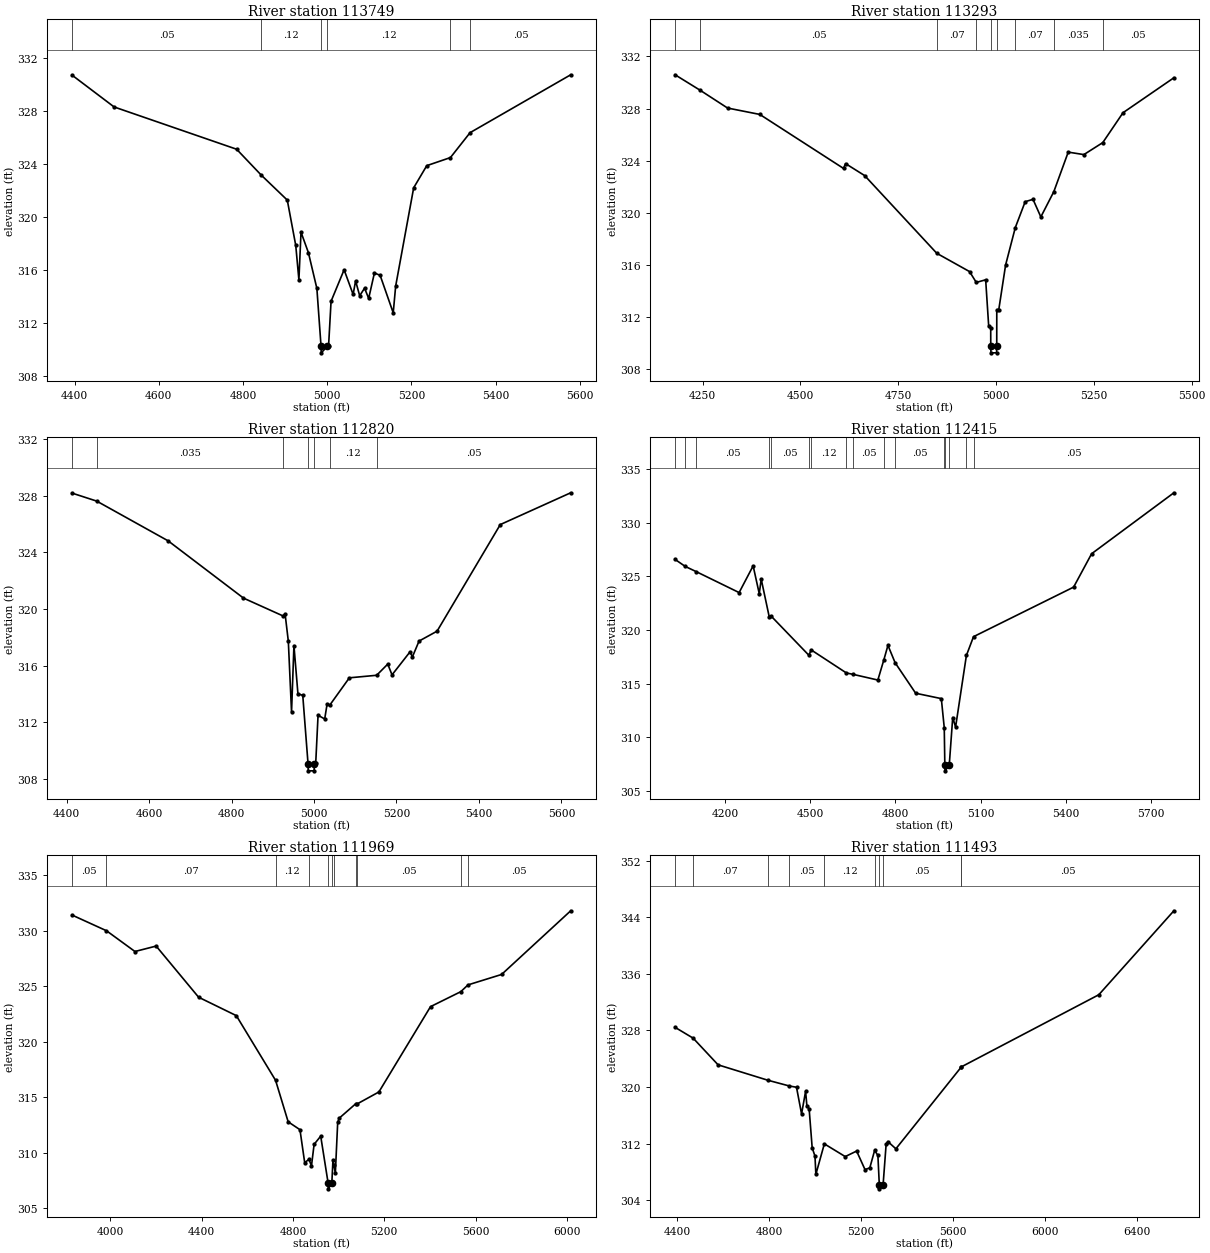
Type RM Length L Ch R = 1 ,113749  ,456,456,456
BEGIN DESCRIPTION:
SALTY CREEK_SUGAR CREEK 75.0
END DESCRIPTION:
XS GIS Cut Line= 3
        2407625.     13695124.97        2407675.       13694525.
      2407375.02     13694025.03
#Sta/Elev= 30
  4393.4  330.73  4493.7  328.32  4784.7  325.13  4843.1  323.18  4905.1  321.29
  4925.2  317.87  4932.7  315.27  4937.7  318.87  4955.3  317.32  4975.4  314.62
  4985.3  310.26  4985.8  309.76  5000.5  310.26  5003.2  310.28  5009.1  313.65
  5040.1  316.03  5061.5  314.17  5067.4  315.19  5077.1  314.07  5088.7  314.64
  5098.5  313.87  5112.1  315.79  5125.7  315.61  5156.8  312.78  5162.6   314.8
  5205.4  322.22  5236.5  323.89  5292.7   324.5  5339.4  326.38  5578.5  330.75
#Mann= 6 ,-1 , 0
  4393.4     .05       0  4843.1     .12       0  4985.3     .05       0
  5000.5     .12       0  5292.7    .035       0  5339.4     .05       0
Bank Sta=4985.3,5000.5
XS Rating Curve= 0 ,0
Exp/Cntr=0.3,0.1

Type RM Length L Ch R = 1 ,113293  ,473,473,473
BEGIN DESCRIPTION:
SALTY CREEK_SUGAR CREEK 74.0
END DESCRIPTION:
XS GIS Cut Line= 3
      2407674.99     13695125.05        2407875.       13694325.
        2407875.     13693874.97
#Sta/Elev= 30
  4179.9  330.59  4244.1   329.4    4314  328.04  4396.4  327.55  4610.3  323.41
  4615.5  323.78  4664.4  322.86  4848.8   316.9  4932.4   315.5  4949.6  314.67
  4973.6  314.87  4981.4  311.29  4986.5  311.17  4986.6  309.77  4987.1  309.27
  5001.4  309.27  5001.9  309.77    5002  312.58  5007.1  312.58  5024.6  316.01
  5049.3  318.87  5074.6  320.86  5094.6  321.04  5114.6  319.69  5147.8  321.63
  5184.6  324.66  5224.6  324.47  5272.9  325.39  5324.6  327.68  5454.6  330.36
#Mann= 9 ,-1 , 0
  4179.9    .035       0  4244.1     .05       0  4848.8     .07       0
  4949.6     .12       0  4986.6     .05       0  5001.9     .12       0
  5049.3     .07       0  5147.8    .035       0  5272.9     .05       0
Bank Sta=4986.6,5001.9
XS Rating Curve= 0 ,0
Exp/Cntr=0.3,0.1

Type RM Length L Ch R = 1 ,112820  ,405,405,405
BEGIN DESCRIPTION:
SALTY CREEK_SUGAR CREEK 73.0
END DESCRIPTION:
XS GIS Cut Line= 3
      2407974.98     13695025.03        2408275.       13694525.
      2407975.01     13693975.02
#Sta/Elev= 30
    4413   328.2  4473.2  327.63  4646.3  324.82    4829  320.77  4924.8  319.51
    4930  319.64  4937.8  317.72  4945.6  312.71  4951.4  317.41  4961.1     314
  4972.8  313.89  4985.6  309.05  4986.1  308.55  5000.4  308.55  5000.9  309.05
  5004.2  309.07  5009.9  312.48    5026  312.22  5031.7  313.25  5038.1  313.19
  5085.8  315.13    5152  315.31  5178.9   316.1  5189.3  315.34    5233  316.97
  5238.7  316.61  5254.8  317.73  5298.5  318.43  5451.8  325.97  5622.6  328.22
#Mann= 7 ,-1 , 0
    4413     .05       0  4473.2    .035       0  4924.8     .05       0
  4985.6     .05       0  5000.9     .05       0  5038.1     .12       0
    5152     .05       0
Bank Sta=4985.6,5000.9
XS Rating Curve= 0 ,0
Exp/Cntr=0.3,0.1

Type RM Length L Ch R = 1 ,112415  ,446,446,446
BEGIN DESCRIPTION:
E20596
END DESCRIPTION:
XS GIS Cut Line= 4
      2408041.87     13695030.02      2408596.71     13694443.91
      2408573.27     13694123.51      2408229.71     13693600.37
#Sta/Elev= 30
    4025  326.58  4060.5  325.93  4099.5  325.44  4250.2  323.49  4299.5  325.98
    4321  323.39  4327.9  324.74  4355.9  321.25  4363.5  321.28  4495.5  317.65
  4503.5  318.15  4627.5     316  4651.2  315.87  4738.1  315.34  4759.5  317.25
  4773.6  318.57  4798.9  316.95  4871.1  314.11  4961.3  313.61  4971.6  310.91
  4973.7  307.38  4974.2  306.88  4989.1  307.38  5001.4  311.85  5011.5  310.96
  5049.5  317.63  5074.5  319.38  5426.6     324  5489.9  327.11  5779.2  332.79
#Mann= 16 ,-1 , 0
    4025     .05       0  4060.5    .033       0  4099.5     .05       0
  4355.9    .033       0  4363.5     .05       0  4495.5    .035       0
  4503.5     .12       0  4627.5    .035       0  4651.2     .05       0
  4759.5    .035       0  4798.9     .05       0  4971.6      .1       0
  4973.7     .05       0  4989.1      .1       0  5049.5    .035       0
  5074.5     .05       0
Bank Sta=4973.7,4989.1
XS Rating Curve= 0 ,0
Exp/Cntr=0.3,0.1

Type RM Length L Ch R = 1 ,111969  ,476,476,476
BEGIN DESCRIPTION:
E20595
END DESCRIPTION:
XS GIS Cut Line= 3
       2409284.4     13695522.32      2408956.19     13694256.36
      2408363.33      13693608.9
#Sta/Elev= 30
  3831.4  331.41  3982.9  329.99  4107.6  328.12  4200.5  328.61  4386.5     324
  4551.8  322.34  4723.8  316.51    4779  312.77  4830.7  312.06  4851.4  309.09
  4870.2  309.39  4881.1   308.8  4892.7  310.74  4921.6  311.48  4954.2  307.23
  4954.7  306.73  4970.3  307.23  4975.3  309.35  4979.4  308.87  4985.7  308.13
    4996  312.71  5002.8   313.1  5076.3  314.42  5082.8   314.4  5176.5  315.46
  5402.8  323.15  5535.5   324.5    5567  325.11  5714.2  326.05  6017.1  331.79
#Mann= 11 ,-1 , 0
  3831.4     .05       0  3982.9     .07       0  4723.8     .12       0
  4870.2     .05       0  4954.2     .05       0  4970.3     .05       0
  4979.4     .12       0  5076.3      .1       0  5082.8     .05       0
  5535.5     .07       0    5567     .05       0
Bank Sta=4954.2,4970.3
XS Rating Curve= 0 ,0
Exp/Cntr=0.3,0.1

Type RM Length L Ch R = 1 ,111493  ,420,420,420
BEGIN DESCRIPTION:
SALTY CREEK_SUGAR CREEK 72.0
END DESCRIPTION:
XS GIS Cut Line= 3
      2409625.02     13694875.04        2409375.       13694325.
      2408175.04     13693325.03
#Sta/Elev= 30
  4392.1  328.44  4470.6  326.91  4578.9  323.14  4794.3  320.97  4888.3  320.15
  4919.4  319.97  4941.4   316.2  4958.9   319.4  4964.4  317.38  4974.3  316.91
  4987.5   311.4  4999.6  310.24  5003.5  307.66  5040.3  311.97    5131  310.17
  5180.5  310.95  5216.9  308.33  5237.8  308.58  5258.7  311.05  5272.9  310.33
  5279.1  306.11  5279.6  305.61  5295.3  306.11  5308.7  311.94  5315.9   312.3
    5351  311.27  5634.2   322.8  5635.7  322.86  6232.3  333.05  6558.3  344.92
#Mann= 10 ,-1 , 0
  4392.1     .05       0  4470.6     .07       0  4794.3     .12       0
  4888.3     .05       0  5040.3     .12       0  5258.7     .05       0
  5279.1     .05       0  5295.3     .05       0  5634.2     .07       0
  5635.7     .05       0
Bank Sta=5279.1,5295.3
XS Rating Curve= 0 ,0
Exp/Cntr=0.3,0.1

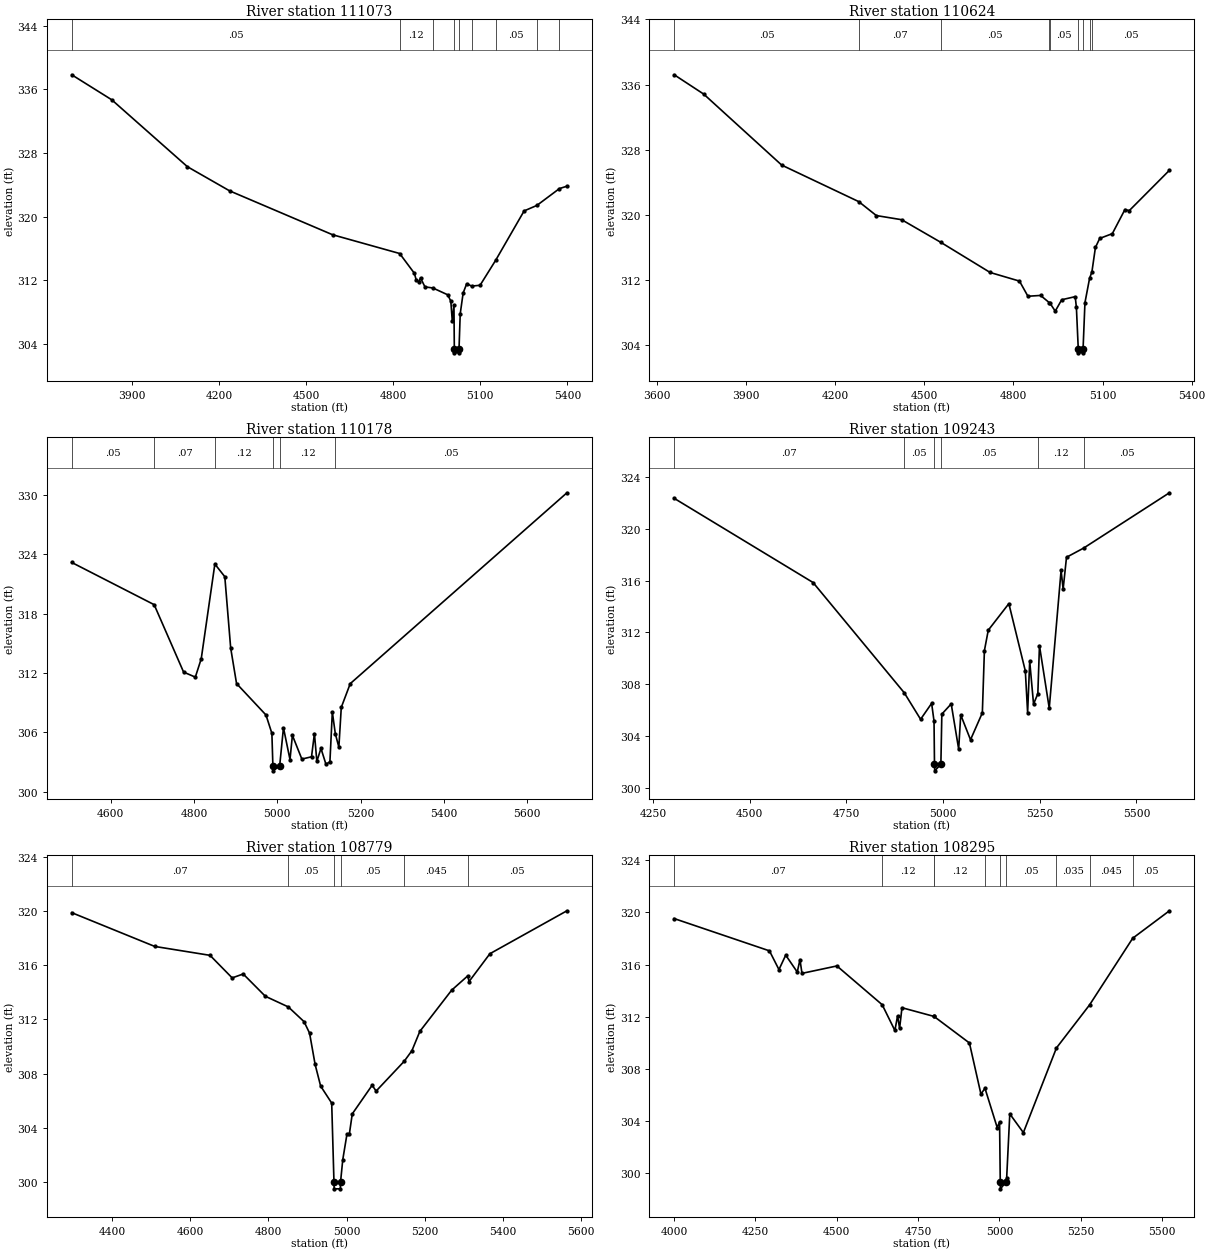
Type RM Length L Ch R = 1 ,111073  ,449,449,449
BEGIN DESCRIPTION:
SALTY CREEK_SUGAR CREEK 71.0
END DESCRIPTION:
XS GIS Cut Line= 3
      2410325.02     13694725.01        2409225.       13694025.
      2408874.98     13693824.99
#Sta/Elev= 30
  3691.5  337.85  3829.5   334.7  4090.3  326.28  4235.9  323.24  4590.7  317.72
  4821.8  315.36  4872.6  312.87  4878.5  312.08  4887.8  311.76  4893.8  312.29
    4909  311.16  4936.4  311.02  4987.7  310.16  4998.2  309.36  5003.3  306.84
    5009  308.89  5010.3  303.36  5010.8  302.86    5026  302.86  5026.5  303.36
  5030.6  307.77  5040.7  310.39    5053  311.56    5070  311.26    5099  311.36
  5152.7   314.5  5250.9  320.72  5294.9  321.41  5372.6  323.53  5398.5  323.83
#Mann= 9 ,-1 , 0
  3691.5     .05       0  4821.8     .12       0  4936.4     .05       0
  5010.3     .05       0  5026.5     .05       0    5070     .12       0
  5152.7     .05       0  5294.9     .07       0  5372.6     .05       0
Bank Sta=5010.3,5026.5
XS Rating Curve= 0 ,0
Exp/Cntr=0.3,0.1

Type RM Length L Ch R = 1 ,110624  ,446,446,446
BEGIN DESCRIPTION:
SALTY CREEK_SUGAR CREEK 70.0
END DESCRIPTION:
XS GIS Cut Line= 3
      2410325.02     13694675.02        2409425.       13693675.
      2409225.03     13693425.04
#Sta/Elev= 30
  3659.5  337.21  3758.6  334.84  4020.9  326.12  4280.2  321.63  4339.3  319.92
  4424.5  319.41  4555.7  316.64    4722  312.93  4820.7  311.87  4849.1  310.01
  4891.7  310.11  4921.4  309.21  4923.2  309.16    4941  308.18  4962.7  309.58
  5008.1  309.96  5012.1  308.66  5018.4  303.56  5018.9  303.06  5034.1  303.06
  5034.6  303.56  5040.9  309.22  5056.5  312.22  5064.3     313  5076.1     316
  5090.5  317.11    5133   317.7  5175.4  320.66  5189.8  320.52    5325  325.48
#Mann= 9 ,-1 , 0
  3659.5     .05       0  4280.2     .07       0  4555.7     .05       0
  4921.4     .12       0  4923.2     .05       0  5018.4     .05       0
  5034.6     .05       0  5056.5     .12       0  5064.3     .05       0
Bank Sta=5018.4,5034.6
XS Rating Curve= 0 ,0
Exp/Cntr=0.3,0.1

Type RM Length L Ch R = 1 ,110178  ,935,935,935
BEGIN DESCRIPTION:
SALTY CREEK_SUGAR CREEK 69.0
END DESCRIPTION:
XS GIS Cut Line= 3
      2410174.97     13693974.97        2409825.       13693625.
      2409224.96     13693274.98
#Sta/Elev= 30
  4506.2  323.19  4704.2  318.92  4774.9   312.1  4803.1  311.59  4817.3  313.45
    4850  323.03  4873.9  321.75    4888  314.54  4902.1  310.94  4972.8  307.76
    4987   305.9  4989.4  302.61  4989.9  302.11  5005.7  302.61  5014.8  306.47
  5030.5  303.25  5036.3   305.7    5059   303.3  5082.2  303.53  5089.2  305.88
    5095  303.07  5104.9  304.38  5116.9  302.77  5126.4  303.03  5132.2  308.06
  5139.4  305.86  5147.9  304.51  5153.7  308.53  5175.2  310.93  5695.8  330.24
#Mann= 6 ,-1 , 0
  4506.2     .05       0  4704.2     .07       0    4850     .12       0
  4989.4     .05       0  5005.7     .12       0  5139.4     .05       0
Bank Sta=4989.4,5005.7
XS Rating Curve= 0 ,0
Exp/Cntr=0.3,0.1

Type RM Length L Ch R = 1 ,109243  ,464,464,464
BEGIN DESCRIPTION:
SALTY CREEK_SUGAR CREEK 68.0
END DESCRIPTION:
XS GIS Cut Line= 3
      2410475.01     13693725.02        2410125.       13693125.
      2409574.98     13692924.99
#Sta/Elev= 30
  4305.3  322.35  4664.2  315.85  4899.8  307.34  4942.1  305.29  4970.6  306.52
  4976.8  305.15    4978  301.81  4978.5  301.31  4994.5  301.81    4997  305.69
  5021.2  306.48  5040.5  302.99  5045.8  305.63  5071.1  303.71  5101.7  305.79
    5107  310.59    5117  312.17  5170.2  314.22  5212.8  309.02  5218.7   305.8
  5224.1  309.77    5234  306.47  5245.1  307.26  5249.3  310.98  5274.6  306.15
  5305.2  316.78  5310.5  315.35  5319.2   317.8  5363.5  318.51  5585.2  322.78
#Mann= 6 ,-1 , 0
  4305.3     .07       0  4899.8     .05       0    4978     .05       0
  4994.5     .05       0  5245.1     .12       0  5363.5     .05       0
Bank Sta=4978,4994.5
XS Rating Curve= 0 ,0
Exp/Cntr=0.3,0.1

Type RM Length L Ch R = 1 ,108779  ,484,484,484
BEGIN DESCRIPTION:
SALTY CREEK_SUGAR CREEK 67.0
END DESCRIPTION:
XS GIS Cut Line= 3
      2410875.02     13693375.02        2410375.       13692875.
      2409824.96     13692774.99
#Sta/Elev= 30
  4297.4  319.91  4509.6  317.41    4651  316.75  4707.6  315.08  4735.8  315.37
  4792.4  313.72  4851.2  312.93  4891.4  311.84  4905.5  310.99  4919.7  308.67
  4933.8  307.07  4962.1  305.81  4967.9  299.96  4968.4  299.46  4984.2  299.46
  4984.7  299.96  4990.4  301.62    5001  303.49  5007.1  303.49  5014.7  305.01
  5065.5  307.13  5075.7   306.7  5147.6  308.91  5167.2  309.69  5187.5  311.12
  5268.8  314.17    5310  315.23  5313.3  314.81  5366.6  316.87  5563.6  320.05
#Mann= 6 ,-1 , 0
  4297.4     .07       0  4851.2     .05       0  4967.9     .05       0
  4984.7     .05       0  5147.6    .045       0    5310     .05       0
Bank Sta=4967.9,4984.7
XS Rating Curve= 0 ,0
Exp/Cntr=0.3,0.1

Type RM Length L Ch R = 1 ,108295  ,451,451,451
BEGIN DESCRIPTION:
SALTY CREEK_SUGAR CREEK 66.0
END DESCRIPTION:
XS GIS Cut Line= 3
      2411075.02     13693225.03        2410475.       13692425.
      2409975.05     13692275.01
#Sta/Elev= 30
  4000.6  319.53  4293.3  317.05  4322.5  315.61  4343.3  316.72  4378.8  315.42
  4387.1  316.38  4393.3  315.32  4500.6  315.89  4639.8  312.91  4678.8  310.93
  4687.1  312.06  4693.3  311.09  4700.6  312.68  4797.8  312.02  4799.1  312.01
  4907.9  309.97  4943.3  306.04  4955.7  306.49  4993.3  303.47  5000.6  303.91
  5002.7  299.26  5003.2  298.76  5019.5  299.26  5022.4  299.61    5032  304.52
  5073.7  303.08  5175.4  309.59  5277.3   312.9  5409.8  318.02  5522.6  320.13
#Mann= 10 ,-1 , 0
  4000.6     .07       0  4639.8     .12       0  4797.8     .05       0
  4799.1     .12       0  4955.7     .05       0  5002.7     .05       0
  5019.5     .05       0  5175.4    .035       0  5277.3    .045       0
  5409.8     .05       0
Bank Sta=5002.7,5019.5
XS Rating Curve= 0 ,0
Exp/Cntr=0.3,0.1

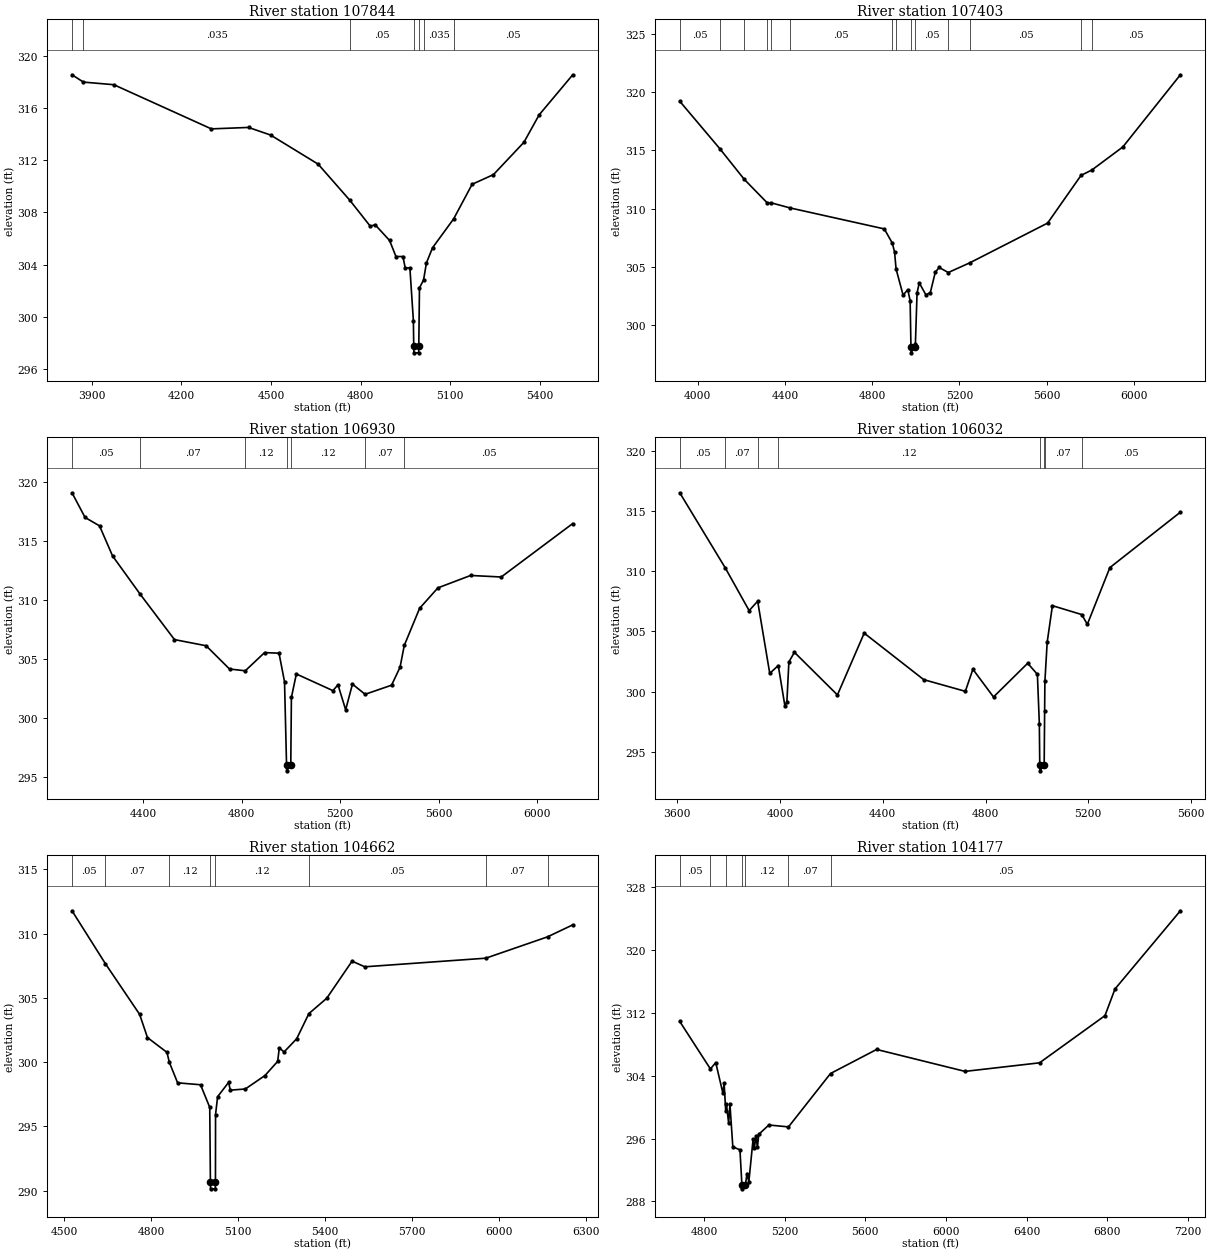
Type RM Length L Ch R = 1 ,107844  ,441,441,441
BEGIN DESCRIPTION:
SALTY CREEK_SUGAR CREEK 65.0
END DESCRIPTION:
XS GIS Cut Line= 3
        2411125.     13693025.01        2410525.       13692025.
        2410025.       13692125.
#Sta/Elev= 30
  3833.8  318.53    3872  317.97  3973.8  317.77  4300.3  314.39  4424.7   314.5
  4498.5  313.92  4657.9  311.69  4763.4  308.94  4832.8  306.93  4848.4  307.06
    4897  305.85  4918.4  304.62  4941.7  304.62  4949.5  303.74    4965  303.76
  4976.7  299.72  4977.9  297.75  4978.4  297.25  4994.3  297.25  4994.8  297.75
  4997.1  302.22  5010.8  302.83  5020.4  304.13  5040.8  305.29  5111.7  307.51
  5173.4  310.15  5244.8  310.89  5346.7  313.36  5397.7  315.46  5509.9  318.52
#Mann= 7 ,-1 , 0
  3833.8     .07       0    3872    .035       0  4763.4     .05       0
  4977.9     .05       0  4994.8     .05       0  5010.8    .035       0
  5111.7     .05       0
Bank Sta=4977.9,4994.8
XS Rating Curve= 0 ,0
Exp/Cntr=0.3,0.1

Type RM Length L Ch R = 1 ,107403  ,473,473,473
BEGIN DESCRIPTION:
SALTY CREEK_SUGAR CREEK 64.0
END DESCRIPTION:
XS GIS Cut Line= 3
        2411775.       13692075.        2410775.       13691675.
      2409574.98       13691475.
#Sta/Elev= 30
  3918.5  319.21    4102  315.14  4214.1  312.51  4318.9   310.5  4336.7   310.5
  4423.7  310.06  4855.5  308.26  4892.4  307.04  4902.6  306.28  4909.6  304.82
  4941.7  302.58  4963.2  303.05    4974   302.1  4977.7  298.13  4978.2  297.63
  4994.6  298.13  4998.1   298.4  5005.7  302.77  5015.8  303.63  5046.2   302.6
  5066.5   302.8  5089.3  304.55    5107  304.95  5148.9  304.52  5248.2  305.36
  5603.8  308.76  5756.9  312.85  5806.4  313.31  5948.5  315.29  6212.1  321.48
#Mann= 14 ,-1 , 0
  3918.5     .05       0    4102     .07       0  4214.1    .035       0
  4318.9     .05       0  4336.7    .035       0  4423.7     .05       0
  4892.4     .12       0  4909.6     .05       0  4977.7     .05       0
  4994.6     .05       0  5148.9    .035       0  5248.2     .05       0
  5756.9     .07       0  5806.4     .05       0
Bank Sta=4977.7,4994.6
XS Rating Curve= 0 ,0
Exp/Cntr=0.3,0.1

Type RM Length L Ch R = 1 ,106930  ,898,898,898
BEGIN DESCRIPTION:
SALTY CREEK_SUGAR CREEK 63.0
END DESCRIPTION:
XS GIS Cut Line= 3
        2411875.       13691775.        2411075.       13691375.
        2409975.       13691075.
#Sta/Elev= 30
  4110.2  319.05  4163.3  316.96    4222  316.25  4275.1   313.7    4387  310.47
  4526.7  306.62  4655.2   306.1  4750.3  304.13  4814.3  303.98  4892.8  305.52
  4951.5  305.47  4973.9  303.05  4982.1  296.01  4982.6  295.51  4999.3  296.01
  5001.8  301.72  5021.9  303.71  5170.5   302.3  5191.2  302.79  5222.3  300.68
  5249.9  302.85  5301.5  301.99  5408.9  302.76  5443.4  304.28  5460.6  306.13
  5522.9  309.27  5597.2     311  5730.2  312.05  5854.6  311.92  6144.8  316.44
#Mann= 7 ,-1 , 0
  4110.2     .05       0    4387     .07       0  4814.3     .12       0
  4982.1     .05       0  4999.3     .12       0  5301.5     .07       0
  5460.6     .05       0
Bank Sta=4982.1,4999.3
XS Rating Curve= 0 ,0
Exp/Cntr=0.3,0.1

Type RM Length L Ch R = 1 ,106032  ,1370,1370,1370
BEGIN DESCRIPTION:
SALTY CREEK_SUGAR CREEK 62.0
END DESCRIPTION:
XS GIS Cut Line= 3
      2411875.03     13691625.02        2410675.       13690925.
        2410125.       13690825.
#Sta/Elev= 30
  3610.1  316.51  3787.9  310.25  3880.1  306.73  3913.3  307.51  3960.3  301.52
  3993.5  302.17  4019.1  298.84  4026.9  299.11  4034.8  302.47  4056.3  303.27
  4223.7  299.73  4327.9  304.86  4559.5     301  4721.5  300.03  4750.9  301.86
  4831.1  299.56  4964.2  302.36  5001.9  301.44  5009.5  297.35  5011.1  293.93
  5011.6  293.43  5028.3  293.93  5030.1  298.38  5031.1  300.85    5040   304.1
  5060.4  307.14  5174.6   306.4  5196.3  305.59    5284   310.3  5558.4   314.9
#Mann= 8 ,-1 , 0
  3610.1     .05       0  3787.9     .07       0  3913.3     .05       0
  3993.5     .12       0  5011.1     .05       0  5028.3     .12       0
  5030.1     .07       0  5174.6     .05       0
Bank Sta=5011.1,5028.3
XS Rating Curve= 0 ,0
Exp/Cntr=0.3,0.1

Type RM Length L Ch R = 1 ,104662  ,485,485,485
BEGIN DESCRIPTION:
SALTY CREEK_SUGAR CREEK 61.0
END DESCRIPTION:
XS GIS Cut Line= 3
      2411874.99     13691424.99        2411625.       13691025.
      2410524.99     13690424.99
#Sta/Elev= 30
  4527.8  311.77  4642.6  307.66  4760.7  303.71  4787.8   301.9    4855  300.75
  4862.9  299.99  4891.6  298.38  4970.6  298.23  5002.3  296.47  5004.6  290.63
  5005.1  290.13  5021.5  290.13    5022  290.63  5022.3  295.91  5029.4   297.3
  5067.4  298.42  5073.1  297.81  5124.8   297.9  5192.7  298.95  5236.3  300.05
    5242  301.11  5258.2  300.78  5301.8  301.81  5343.9  303.77  5405.3  304.96
  5492.6  307.85  5536.3  307.41  5953.2  308.08  6165.9  309.74  6252.5  310.67
#Mann= 8 ,-1 , 0
  4527.8     .05       0  4642.6     .07       0  4862.9     .12       0
  5004.6     .05       0    5022     .12       0  5343.9     .05       0
  5953.2     .07       0  6165.9     .05       0
Bank Sta=5004.6,5022
XS Rating Curve= 0 ,0
Exp/Cntr=0.3,0.1

Type RM Length L Ch R = 1 ,104177  ,451,451,451
BEGIN DESCRIPTION:
SALTY CREEK_SUGAR CREEK 60.0
END DESCRIPTION:
XS GIS Cut Line= 3
        2412275.     13691175.01        2412075.       13690925.
        2410275.       13689725.
#Sta/Elev= 30
  4679.7   310.9  4831.8  304.86  4858.2  305.67  4893.4  301.81  4899.8  303.02
  4907.8  299.49  4911.5  300.35  4922.2  297.96  4928.6  300.37    4943  294.94
  4978.3  294.58    4988  290.11  4988.5  289.61  5005.4  290.11  5013.4  291.56
  5022.4  290.49  5043.4  295.91  5049.4  294.78  5058.5  296.39  5064.5  294.87
    5072  296.55  5121.6  297.73  5219.1  297.49  5427.6  304.28  5656.4  307.34
    6095  304.55  6464.6  305.64  6789.1  311.64  6838.7  315.03  7163.2  324.98
#Mann= 7 ,-1 , 0
  4679.7     .05       0  4831.8     .07       0  4911.5     .12       0
    4988     .05       0  5005.4     .12       0  5219.1     .07       0
  5427.6     .05       0
Bank Sta=4988,5005.4
XS Rating Curve= 0 ,0
Exp/Cntr=0.3,0.1

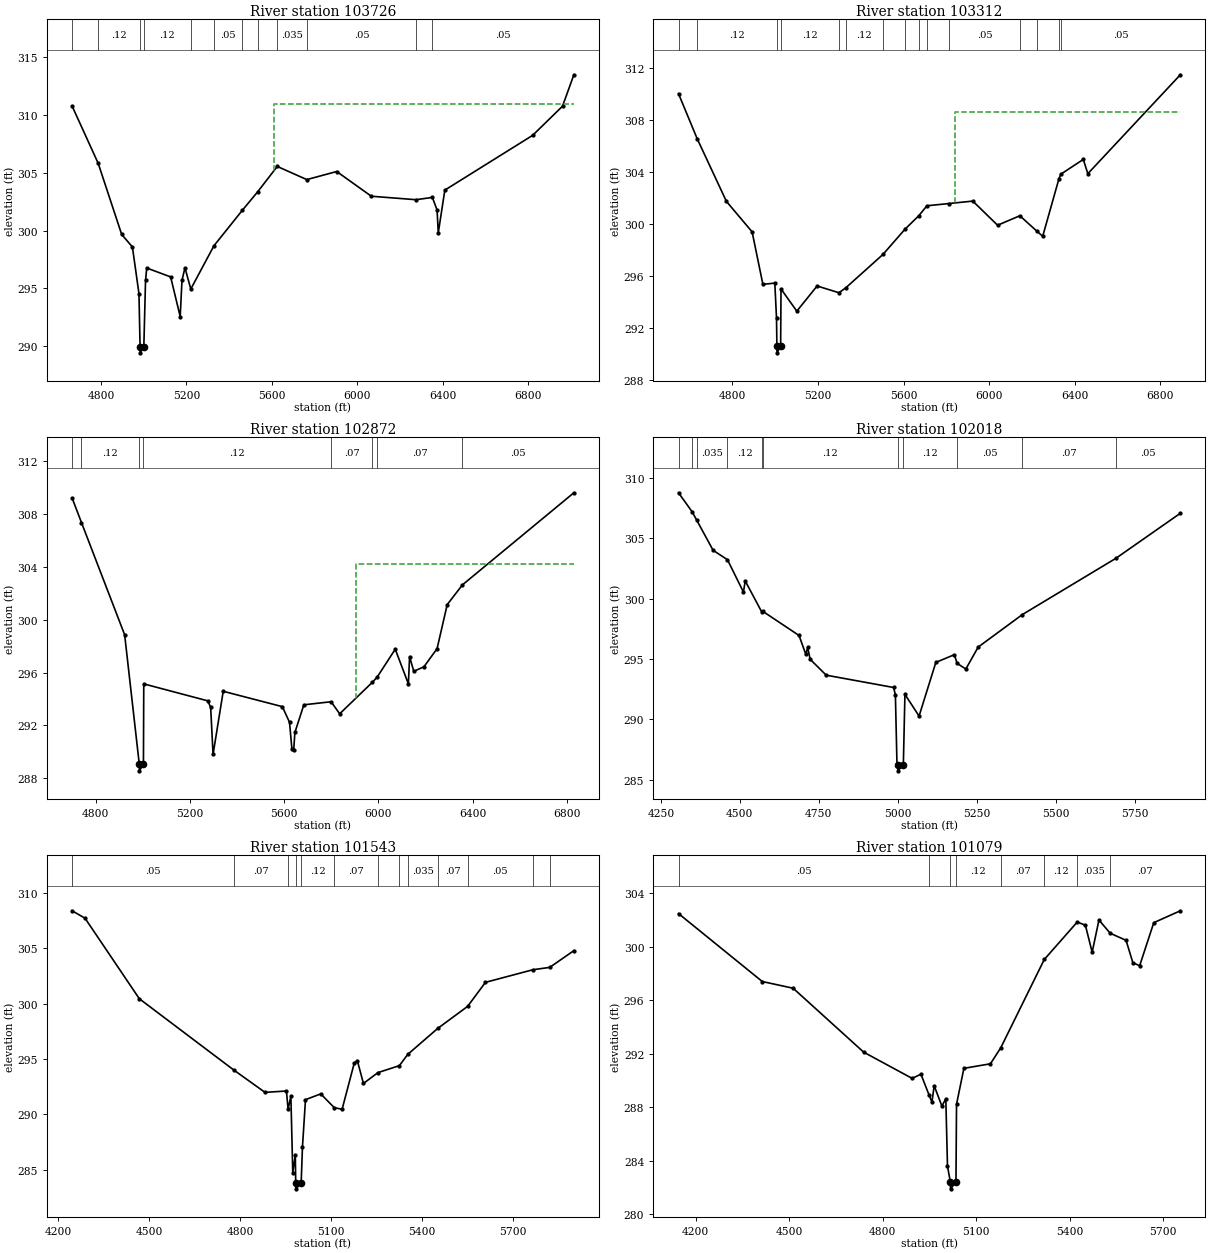
Type RM Length L Ch R = 1 ,103726  ,414,414,414
BEGIN DESCRIPTION:
SALTY CREEK_SUGAR CREEK 59.0
END DESCRIPTION:
XS GIS Cut Line= 3
      2412574.99     13691024.98        2412425.       13690725.
      2410625.04     13689825.02
#Sta/Elev= 30
  4665.2  310.78  4787.6  305.81  4897.2  299.67  4947.5  298.58  4978.2  294.54
  4983.4  289.92  4983.9  289.42  5000.9  289.92    5009  295.71  5014.6  296.76
  5126.4  295.99  5171.1  292.56  5179.5  295.69  5193.4  296.78  5220.7  294.94
  5329.2  298.69  5462.6  301.77  5534.3  303.37  5625.3  305.55  5763.5  304.41
  5903.4  305.11  6065.5  302.97  6274.4  302.67    6351  302.87    6373  301.78
  6378.6   299.8  6409.3   303.5  6820.2  308.24  6959.9  310.76    7013  313.48
#Mann= 12 ,-1 , 0
  4665.2     .05       0  4787.6     .12       0  4983.4     .05       0
  5000.9     .12       0  5220.7     .07       0  5329.2     .05       0
  5462.6    .035       0  5534.3     .05       0  5625.3    .035       0
  5763.5     .05       0  6274.4     .07       0    6351     .05       0
#XS Ineff= 2 , 0
       0                  5610.5       0  310.99
Permanent Ineff=
       F       F
Bank Sta=4983.4,5000.9
XS Rating Curve= 0 ,0
Exp/Cntr=0.3,0.1

Type RM Length L Ch R = 1 ,103312  ,440,440,440
BEGIN DESCRIPTION:
SALTY CREEK_SUGAR CREEK 58.0
END DESCRIPTION:
XS GIS Cut Line= 3
      2412925.01       13690575.        2412525.       13690375.
      2410724.99       13689775.
#Sta/Elev= 30
  4548.6  310.03  4635.3  306.58  4772.2  301.74  4892.4  299.39  4942.7  295.35
  4998.5  295.44  5006.4  292.74  5008.2  290.57  5008.7  290.07  5025.7  290.57
  5027.4  294.99  5101.2  293.28  5196.1  295.22  5298.2   294.7  5330.2  295.08
  5503.8  297.65  5606.5  299.59  5671.1  300.63  5709.3   301.4  5812.1  301.57
  5923.4  301.76  6039.4   299.9  6143.4  300.63  6223.1  299.44  6250.2  299.05
  6325.9  303.47  6334.6  303.83  6439.9  304.97    6461  303.87  6893.2  311.49
#Mann= 15 ,-1 , 0
  4548.6     .07       0  4635.3     .12       0  5008.2     .05       0
  5025.7     .12       0  5298.2     .07       0  5330.2     .12       0
  5503.8     .07       0  5606.5    .035       0  5671.1     .07       0
  5709.3    .035       0  5812.1     .05       0  6143.4     .07       0
  6223.1     .05       0  6325.9     .07       0  6334.6     .05       0
#XS Ineff= 2 , 0
       0                  5840.7       0  308.63
Permanent Ineff=
       F       F
Bank Sta=5008.2,5025.7
XS Rating Curve= 0 ,0
Exp/Cntr=0.3,0.1

Type RM Length L Ch R = 1 ,102872  ,854,854,854
BEGIN DESCRIPTION:
SALTY CREEK_SUGAR CREEK 57.0
END DESCRIPTION:
XS GIS Cut Line= 3
      2412975.03     13689974.99        2412675.       13690025.
        2410875.       13689725.
#Sta/Elev= 30
  4700.3  309.19  4740.2  307.33  4923.4  298.85  4985.5  289.07    4986  288.57
  5003.1  289.07  5004.5  295.14  5275.7  293.86  5288.3  293.37  5298.5  289.81
  5341.6  294.58  5592.5  293.42  5622.9  292.24    5633  290.22  5640.6  290.15
  5645.7  291.47  5683.7  293.56  5799.3  293.79  5835.8  292.88  5974.9  295.27
  5994.3  295.64  6071.5  297.76  6127.2  295.14  6132.3   297.2  6150.1  296.09
  6193.1  296.43  6248.9   297.8    6292  301.13  6356.4  302.62  6829.3  309.58
#Mann= 8 ,-1 , 0
  4700.3    .035       0  4740.2     .12       0  4985.5     .05       0
  5003.1     .12       0  5799.3     .07       0  5974.9     .05       0
  5994.3     .07       0  6356.4     .05       0
#XS Ineff= 2 , 0
       0                    5903       0  304.18
Permanent Ineff=
       F       F
Bank Sta=4985.5,5003.1
XS Rating Curve= 0 ,0
Exp/Cntr=0.3,0.1

Type RM Length L Ch R = 1 ,102018  ,475,475,475
BEGIN DESCRIPTION:
SALTY CREEK_SUGAR CREEK 56.0
END DESCRIPTION:
XS GIS Cut Line= 3
      2412974.97     13689924.98        2412375.       13689575.
      2411575.01       13689175.
#Sta/Elev= 30
  4305.8  308.79  4348.7  307.22  4363.2  306.53  4415.3  304.02  4460.8  303.24
  4511.3  300.56    4517  301.48  4568.9  298.93  4572.8  298.96  4687.4  296.96
  4708.9  295.39  4714.7  295.98  4722.5  294.99  4773.4  293.67  4986.7  292.65
  4992.5  292.05  4997.5  286.31  4999.9  286.24  5000.4  285.74  5017.7  286.24
  5022.7  292.08  5067.5  290.28  5120.6  294.73  5179.3  295.37  5187.9  294.65
  5215.6  294.18  5254.7     296  5394.4  298.69  5690.3  303.35  5894.8  307.09
#Mann= 11 ,-1 , 0
  4305.8    .035       0  4348.7     .12       0  4363.2    .035       0
  4460.8     .12       0  4568.9    .035       0  4572.8     .12       0
  4999.9     .05       0  5017.7     .12       0  5187.9     .05       0
  5394.4     .07       0  5690.3     .05       0
Bank Sta=4999.9,5017.7
XS Rating Curve= 0 ,0
Exp/Cntr=0.3,0.1

Type RM Length L Ch R = 1 ,101543  ,464,464,464
BEGIN DESCRIPTION:
SALTY CREEK_SUGAR CREEK 55.0
END DESCRIPTION:
XS GIS Cut Line= 3
        2413075.       13689825.        2412625.       13689225.
      2411725.04       13689125.
#Sta/Elev= 30
  4245.8  308.38  4288.5  307.71  4467.7  300.44  4778.6  294.02  4882.3  291.99
  4953.1  292.11  4958.5  290.46  4967.7  291.63  4973.9  284.75  4982.3  286.31
  4983.7  283.78  4984.2  283.28  5001.6  283.78  5005.9  287.06  5015.9  291.33
  5066.2  291.85  5110.8  290.61  5136.7  290.46  5176.9  294.64    5187  294.85
  5207.1  292.79  5254.7  293.77  5325.6   294.4  5353.4  295.42  5452.1  297.76
  5550.8  299.75  5609.6  301.92  5766.5  303.06  5821.7  303.27  5901.3  304.78
#Mann= 13 ,-1 , 0
  4245.8     .05       0  4778.6     .07       0  4958.5     .12       0
  4983.7     .05       0  5001.6     .12       0  5110.8     .07       0
  5254.7    .035       0  5325.6     .07       0  5353.4    .035       0
  5452.1     .07       0  5550.8     .05       0  5766.5     .07       0
  5821.7     .05       0
Bank Sta=4983.7,5001.6
XS Rating Curve= 0 ,0
Exp/Cntr=0.3,0.1

Type RM Length L Ch R = 1 ,101079  ,446,446,446
BEGIN DESCRIPTION:
SALTY CREEK_SUGAR CREEK 54.0
END DESCRIPTION:
XS GIS Cut Line= 3
        2413375.       13689575.        2412775.       13688975.
      2412075.01       13688675.
#Sta/Elev= 30
    4145  302.49  4413.7  297.41  4512.7  296.91    4739  292.13  4894.5  290.17
  4922.8  290.48  4949.3   288.9  4958.2  288.39  4965.2  289.62    4990   288.1
  5002.6  288.64    5008  283.61  5017.2  282.41  5017.7  281.91  5035.2  282.41
    5037  288.23  5060.6  290.92  5145.8  291.26  5178.8  292.45  5318.6  299.06
  5424.4  301.86  5450.5  301.62  5472.2   299.6    5494  302.01  5530.1  301.02
    5581  300.49  5602.8  298.82  5624.6  298.59  5669.9  301.81  5755.1   302.7
#Mann= 8 ,-1 , 0
    4145     .05       0  4949.3     .12       0  5017.2     .05       0
  5035.2     .12       0  5178.8     .07       0  5318.6     .12       0
  5424.4    .035       0  5530.1     .07       0
Bank Sta=5017.2,5035.2
XS Rating Curve= 0 ,0
Exp/Cntr=0.3,0.1

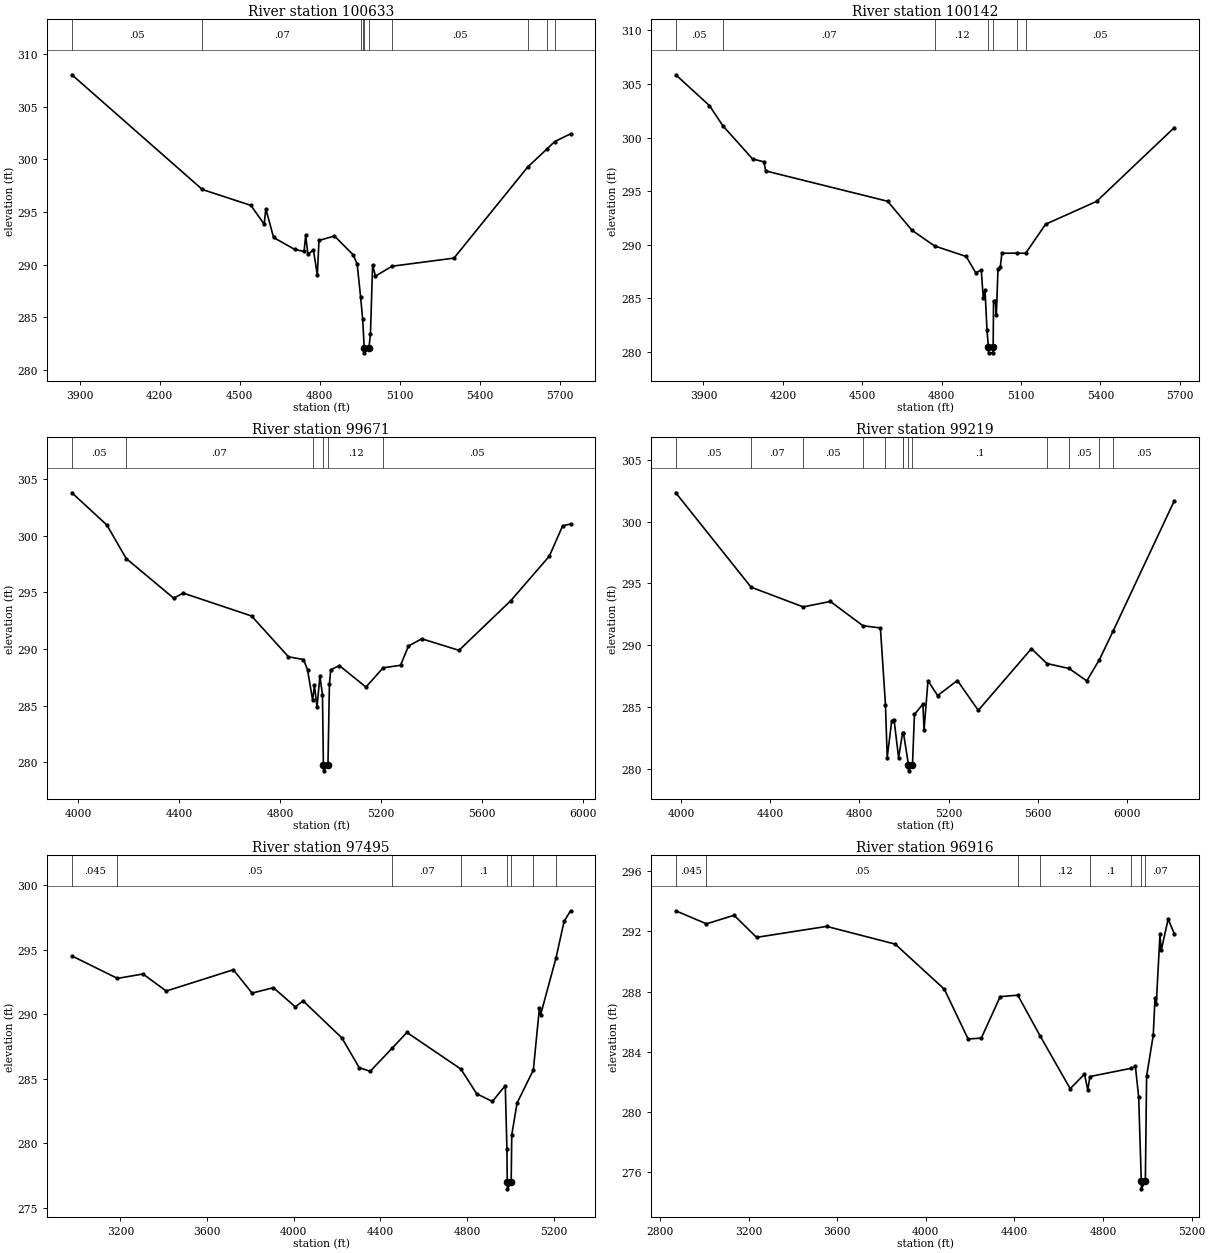
Type RM Length L Ch R = 1 ,100633  ,491,491,491
BEGIN DESCRIPTION:
SALTY CREEK_SUGAR CREEK 53.0
END DESCRIPTION:
XS GIS Cut Line= 3
        2413925.       13689575.        2413025.       13688875.
      2412324.99       13688675.
#Sta/Elev= 30
  3871.5  308.03  4360.1  297.13    4542  295.62  4591.8  293.83  4598.1  295.29
  4627.1  292.57  4705.8  291.44  4741.1  291.24  4747.4  292.77  4755.6  290.98
  4776.4  291.38  4790.9     289  4797.2  292.29  4855.1  292.71  4925.7  290.91
  4940.2  290.04    4953  286.94  4960.9  284.79  4966.5  282.11    4967  281.61
  4984.5  282.11    4990   283.4  4998.1  289.98  5008.5   288.9  5070.9  289.84
  5302.9  290.61  5578.6  299.25  5650.7  300.97  5680.1  301.68  5739.7  302.42
#Mann= 10 ,-1 , 0
  3871.5     .05       0  4360.1     .07       0    4953     .12       0
  4960.9     .07       0  4966.5     .05       0  4984.5     .07       0
  5070.9     .05       0  5578.6     .07       0  5650.7     .05       0
  5680.1    .035       0
Bank Sta=4966.5,4984.5
XS Rating Curve= 0 ,0
Exp/Cntr=0.3,0.1

Type RM Length L Ch R = 1 ,100142  ,471,471,471
BEGIN DESCRIPTION:
SALTY CREEK_SUGAR CREEK 52.0
END DESCRIPTION:
XS GIS Cut Line= 3
        2413975.       13689375.        2413175.       13688475.
      2412625.02     13688075.02
#Sta/Elev= 30
  3795.2  305.86  3922.7  302.98    3973  301.11  4085.8     298  4128.4  297.74
  4135.1  296.89  4595.9  294.06  4687.9  291.35  4773.4  289.89  4892.7  288.91
  4928.7  287.39  4949.6  287.65  4957.1  285.06  4963.8  285.79  4971.3  282.03
  4976.6  280.42  4977.1  279.92  4994.1  279.92  4994.6  280.42    4996  284.76
  5002.4  284.76  5006.7  283.47  5012.9  287.78  5021.4   287.9  5027.6  289.21
    5086  289.22  5117.4  289.21  5192.9  291.92  5385.4  294.05  5679.4  300.94
#Mann= 7 ,-1 , 0
  3795.2     .05       0    3973     .07       0  4773.4     .12       0
  4976.6     .05       0  4994.6     .12       0    5086     .07       0
  5117.4     .05       0
Bank Sta=4976.6,4994.6
XS Rating Curve= 0 ,0
Exp/Cntr=0.3,0.1

Type RM Length L Ch R = 1 ,99671   ,452,452,452
BEGIN DESCRIPTION:
SALTY CREEK_SUGAR CREEK 51.0
END DESCRIPTION:
XS GIS Cut Line= 3
      2414075.02     13689175.03        2413575.       13688275.
      2412674.99       13687975.
#Sta/Elev= 30
  3974.3  303.79  4112.8  300.95  4189.7  297.99  4378.2  294.49  4415.9  294.94
    4687  292.92  4833.5  289.32  4892.9  289.08    4909  288.19  4929.4  285.48
  4936.4  286.81  4946.7  284.88  4958.1   287.6  4968.4  285.98    4972  279.76
  4972.5  279.26  4990.1  279.76  4995.9   286.9    5001  288.18  5035.5  288.54
  5140.9  286.65    5209  288.35    5278  288.57  5309.6  290.27  5362.3  290.91
  5509.9  289.89  5715.4  294.27  5868.3   298.2    5921  300.86  5952.6  301.04
#Mann= 6 ,-1 , 0
  3974.3     .05       0  4189.7     .07       0  4929.4     .12       0
    4972     .05       0  4990.1     .12       0    5209     .05       0
Bank Sta=4972,4990.1
XS Rating Curve= 0 ,0
Exp/Cntr=0.3,0.1

Type RM Length L Ch R = 1 ,99219   ,1724,1724,1724
BEGIN DESCRIPTION:
SALTY CREEK_SUGAR CREEK 50.0
END DESCRIPTION:
XS GIS Cut Line= 3
      2414125.01     13689075.03        2413925.       13688075.
      2412724.98       13687875.
#Sta/Elev= 30
  3976.1  302.32  4314.1   294.7  4547.8  293.11  4669.6  293.55  4815.7  291.59
    4894  291.41  4916.7  285.22  4924.5  280.95  4944.9  283.93  4955.1  284.02
  4975.5  280.94  4993.2  282.92  4997.2  282.96  5019.8  280.38  5020.3  279.88
  5037.9  280.38  5046.6  284.43  5084.6  285.27  5089.7  283.16  5107.4  287.16
  5150.5  285.95  5239.2  287.17    5333  284.76  5571.3  289.74  5640.8  288.54
  5740.1  288.14  5819.6  287.14  5876.4  288.86  5938.7   291.2  6212.5  301.69
#Mann= 13 ,-1 , 0
  3976.1     .05       0  4314.1     .07       0  4547.8     .05       0
  4815.7     .07       0  4916.7      .1       0  4993.2     .07       0
  4997.2      .1       0  5019.8     .05       0  5037.9      .1       0
  5640.8     .07       0  5740.1     .05       0  5876.4     .07       0
  5938.7     .05       0
Bank Sta=5019.8,5037.9
XS Rating Curve= 0 ,0
Exp/Cntr=0.3,0.1

Type RM Length L Ch R = 1 ,97495   ,579,579,579
BEGIN DESCRIPTION:
E20594
END DESCRIPTION:
XS GIS Cut Line= 3
      2414598.37     13688707.94       2413809.1     13687574.82
      2412951.32      13687239.5
#Sta/Elev= 30
  2975.9  294.52    3186  292.78    3304  293.12  3411.3   291.8  3721.1  293.45
  3807.5  291.64  3906.1  292.06  4007.3  290.57  4043.1  291.04  4222.5  288.16
  4302.2  285.86  4352.9  285.58  4454.8  287.38  4522.3  288.59  4771.7  285.75
  4844.4  283.84  4916.8  283.24  4976.4  284.47    4984  279.58  4985.6  276.97
  4986.1  276.47  5003.7  276.97  5006.3  280.64  5030.8  283.12    5106  285.68
    5134   290.5  5139.4  289.95  5210.5  294.36    5248   297.2  5277.8  298.02
#Mann= 8 ,-1 , 0
  2975.9    .045       0    3186     .05       0  4454.8     .07       0
  4771.7      .1       0  4985.6     .05       0  5003.7      .1       0
    5106     .07       0  5210.5    .035       0
Bank Sta=4985.6,5003.7
XS Rating Curve= 0 ,0
Exp/Cntr=0.3,0.1

Type RM Length L Ch R = 1 ,96916   ,728,728,728
BEGIN DESCRIPTION:
SALTY CREEK_SUGAR CREEK 49.0
END DESCRIPTION:
XS GIS Cut Line= 3
      2414637.48     13688629.84        2413425.       13686875.
      2413371.48     13686769.92
#Sta/Elev= 30
    2871  293.38  3009.8  292.51  3134.3  293.08  3235.7  291.61  3552.1  292.34
  3861.4  291.16  4083.3  288.16  4190.8  284.84  4250.3   284.9  4335.5  287.66
  4414.9  287.76  4515.6  285.05  4651.5  281.53    4716   282.5  4730.9  281.45
  4740.7  282.34    4927  282.89  4945.8  283.02  4960.7  280.96  4972.5  275.36
    4973  274.86  4990.8  275.36  4996.5  282.37  5026.4  285.09  5034.5  287.57
  5040.1  287.15  5056.8  291.81  5062.4  290.74  5093.7  292.82  5121.9  291.84
#Mann= 8 ,-1 , 0
    2871    .045       0  3009.8     .05       0  4414.9     .07       0
  4515.6     .12       0  4740.7      .1       0    4927     .07       0
  4972.5     .05       0  4990.8     .07       0
Bank Sta=4972.5,4990.8
XS Rating Curve= 0 ,0
Exp/Cntr=0.3,0.1