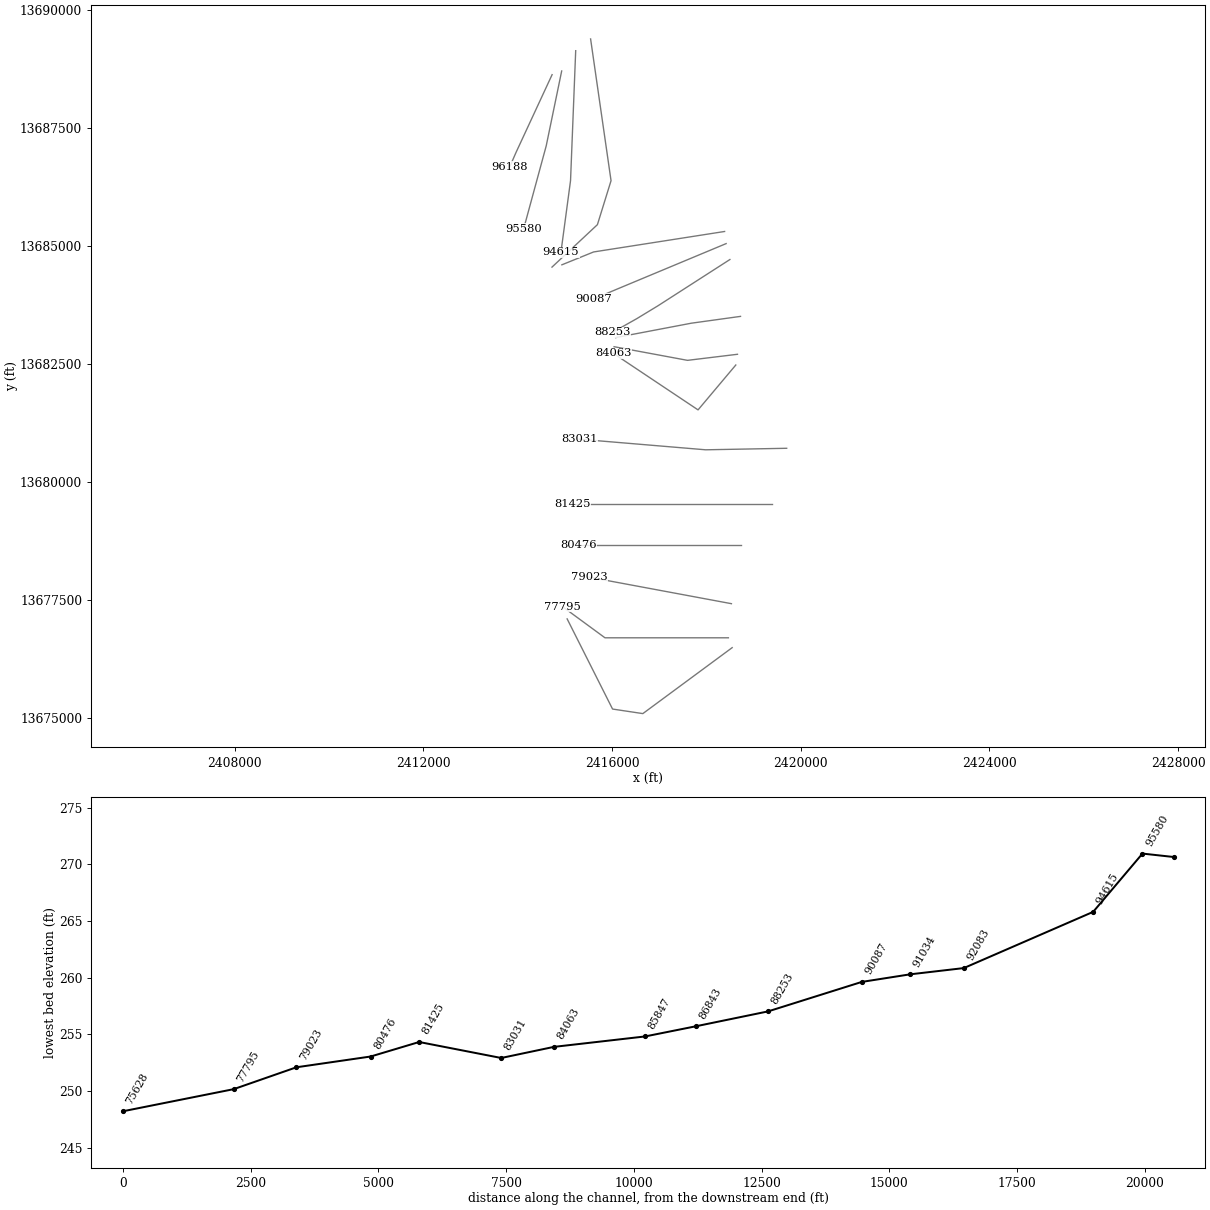
HEC-RAS study SALTY CREEK_SUGAR CREEK.prj: SALTY CREEK_SUGAR CREEK Base Level Engineering

--- SALTY CREEK_SUGAR CREEK.g01 (geometry) --- (continued)

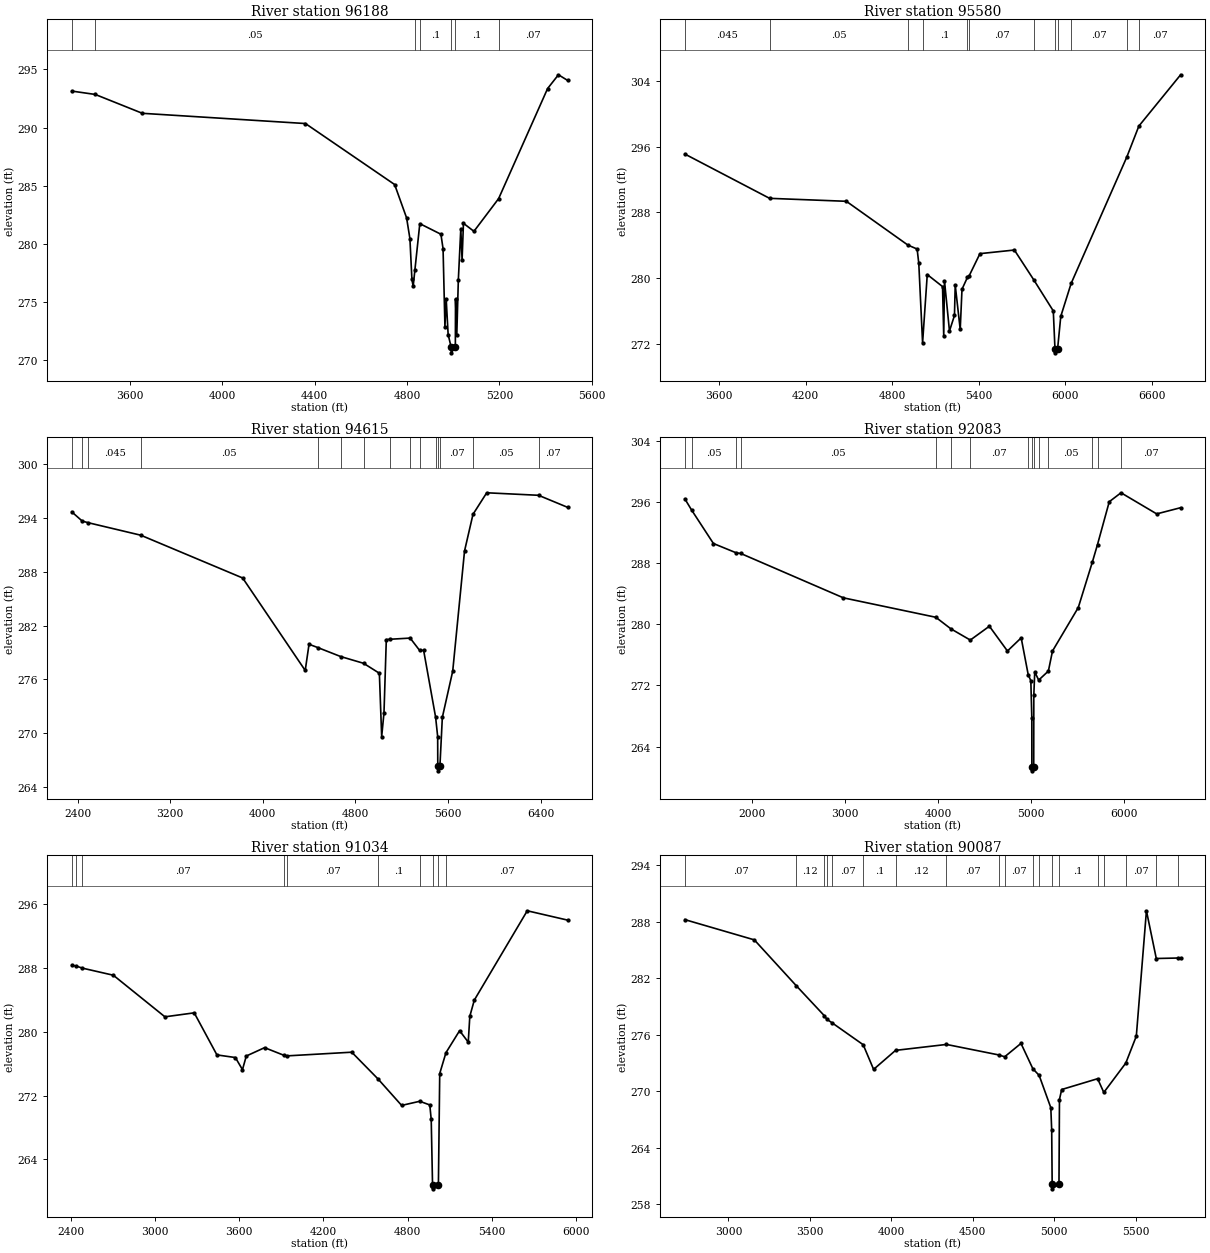
Type RM Length L Ch R = 1 ,96188   ,608,608,608
BEGIN DESCRIPTION:
SALTY CREEK_SUGAR CREEK 48.0
END DESCRIPTION:
XS GIS Cut Line= 3
      2414731.24       13688622.      2413965.39     13686973.09
      2413834.42     13686673.44
#Sta/Elev= 30
  3349.3  293.13  3450.9  292.84  3654.7  291.22  4360.4  290.34  4746.3   285.1
  4798.1  282.23  4812.4  280.45    4821  276.96  4826.5  276.35  4834.1  277.79
  4855.2  281.74  4946.5  280.83  4955.8  279.59  4963.9  272.89  4969.4  275.24
  4977.8  272.21  4990.7  271.14  4991.2  270.64    5009  271.14  5009.7  275.27
  5015.2  272.18  5021.9   276.9  5032.6  281.31  5038.1  278.61    5044  281.77
  5089.4  281.08  5196.2  283.89  5408.2  293.35    5455  294.53  5494.4  294.05
#Mann= 7 ,-1 , 0
  3349.3    .045       0  3450.9     .05       0  4834.1     .12       0
  4855.2      .1       0  4990.7     .05       0    5009      .1       0
  5196.2     .07       0
Bank Sta=4990.7,5009
XS Rating Curve= 0 ,0
Exp/Cntr=0.3,0.1

Type RM Length L Ch R = 1 ,95580   ,965,965,965
BEGIN DESCRIPTION:
SALTY CREEK_SUGAR CREEK 47.0
END DESCRIPTION:
XS GIS Cut Line= 3
      2414934.42     13688700.16      2414606.19     13687113.75
      2414129.75     13685364.17
#Sta/Elev= 30
  3364.4  295.09  3951.1  289.71  4482.8  289.35  4909.1  284.03  4972.9  283.55
  4984.4  281.81  5010.7  272.15  5043.1  280.45  5148.9  278.99  5157.2  272.95
  5162.3   279.7  5196.9  273.59  5231.5  275.48  5236.7  279.18  5271.3  273.78
  5283.7  278.67  5321.7  280.12  5334.2  280.33    5408  282.99  5646.4  283.43
    5781   279.8  5915.9  276.03  5927.5  271.44    5928  270.94  5945.8  271.44
  5967.7  275.37  6039.4  279.37  6425.3  294.74  6508.5  298.49  6797.7  304.72
#Mann= 12 ,-1 , 0
  3364.4    .045       0  3951.1     .05       0  4909.1     .12       0
  5010.7      .1       0  5321.7     .12       0  5334.2     .07       0
    5781     .12       0  5927.5     .05       0  5945.8     .12       0
  6039.4     .07       0  6425.3     .12       0  6508.5     .07       0
Bank Sta=5927.5,5945.8
XS Rating Curve= 0 ,0
Exp/Cntr=0.3,0.1

Type RM Length L Ch R = 1 ,94615   ,2532,2532,2532
BEGIN DESCRIPTION:
SALTY CREEK_SUGAR CREEK 46.0
END DESCRIPTION:
XS GIS Cut Line= 3
      2415231.37     13689129.89      2415121.96     13686379.17
      2414918.78     13684863.12
#Sta/Elev= 30
  2350.2  294.67  2441.2  293.64  2493.1  293.46  2946.1  292.07  3826.3   287.3
  4366.7  276.99  4399.7  279.91  4476.1  279.54  4673.4  278.54  4870.7  277.79
  5007.2  276.68  5027.2  269.62  5047.2  272.28  5067.2  280.43  5099.9  280.47
  5273.3   280.6  5354.1  279.24  5389.8  279.22    5493  271.79  5510.9  269.62
  5511.8   266.3  5512.3   265.8  5530.2   266.3  5551.2  271.76  5640.9  276.92
  5742.9  290.31    5816   294.4  5934.6   296.8    6382  296.52  6632.7  295.18
#Mann= 15 ,-1 , 0
  2350.2    .045       0  2441.2     .05       0  2493.1    .045       0
  2946.1     .05       0  4476.1     .07       0  4673.4     .12       0
  4870.7      .1       0  5099.9     .12       0  5273.3      .1       0
  5354.1     .12       0    5493     .07       0  5511.8     .05       0
  5530.2     .07       0    5816     .05       0    6382     .07       0
Bank Sta=5511.8,5530.2
XS Rating Curve= 0 ,0
Exp/Cntr=0.3,0.1

Type RM Length L Ch R = 1 ,92083   ,1049,1049,1049
BEGIN DESCRIPTION:
E20593
END DESCRIPTION:
XS GIS Cut Line= 4
      2415547.24     13689378.68      2415980.57     13686377.51
      2415691.68     13685446.67      2414728.76     13684547.94
#Sta/Elev= 30
  1279.2  296.38  1350.9  294.94    1586  290.55  1829.1  289.34  1879.1  289.25
  2981.7  283.45  3974.2  280.91  4134.8  279.41  4344.6  277.93  4549.6  279.74
  4743.4   276.5  4891.1  278.22  4966.4  273.41  4994.7  272.61  5005.2  267.76
  5005.6  261.34  5006.1  260.84  5025.7  261.34  5026.6   270.7  5036.6  273.77
    5079   272.7  5183.1  273.88  5227.3   276.5  5504.2  282.18    5656  288.15
  5710.7  290.42  5836.9  296.01    5963  297.18  6346.4  294.42  6603.3  295.23
#Mann= 15 ,-1 , 0
  1279.2    .045       0  1350.9     .05       0  1829.1    .045       0
  1879.1     .05       0  3974.2     .07       0  4134.8     .05       0
  4344.6     .07       0  4966.4      .1       0  5005.6     .05       0
  5025.7      .1       0    5079     .07       0  5183.1     .05       0
    5656     .07       0  5710.7     .05       0    5963     .07       0
Bank Sta=5005.6,5025.7
XS Rating Curve= 0 ,0
Exp/Cntr=0.3,0.1

Type RM Length L Ch R = 1 ,91034   ,947,947,947
BEGIN DESCRIPTION:
E20592
END DESCRIPTION:
XS GIS Cut Line= 3
      2418387.93     13685302.23      2415611.44      13684868.9
      2414938.66     13684596.59
#Sta/Elev= 30
  2405.5  288.35  2435.7  288.26  2481.8  287.99    2702   287.1  3069.9  281.88
  3278.9  282.38  3440.8   277.1  3572.4  276.77    3623  275.25  3650.2  276.96
  3780.8  278.01  3920.1  277.04  3942.5  276.98  4402.3  277.44  4589.8  274.08
  4758.1  270.76  4887.3  271.28    4959  270.82  4969.1     269  4978.6  260.79
  4979.6  260.29  5020.4  260.79  5029.8  274.76  5074.3  277.38  5171.5  280.14
  5233.3   278.7  5244.4  281.95  5276.5  283.98  5654.1  295.19  5941.4  294.02
#Mann= 10 ,-1 , 0
  2405.5     .07       0  2435.7     .12       0  2481.8     .07       0
  3920.1     .12       0  3942.5     .07       0  4589.8      .1       0
  4887.3     .12       0  4978.6     .05       0  5020.4     .12       0
  5074.3     .07       0
Bank Sta=4978.6,5020.4
XS Rating Curve= 0 ,0
Exp/Cntr=0.3,0.1

Type RM Length L Ch R = 1 ,90087   ,1834,1834,1834
BEGIN DESCRIPTION:
E20591
END DESCRIPTION:
XS GIS Cut Line= 3
      2418419.98     13685045.42      2416108.96      13684082.5
      2415611.44     13683873.86
#Sta/Elev= 30
  2732.6  288.22  3158.9  286.07  3415.9  281.21  3587.7  278.03  3604.6  277.63
  3634.4  277.28  3827.2  274.93  3891.2  272.31    4026  274.33  4338.5  274.96
  4658.2  273.85  4695.8  273.65  4795.8  275.07  4868.9  272.37  4907.1  271.68
  4978.9  268.24  4984.3  265.86  4987.2  260.12  4988.2  259.62    5029  260.12
    5032  269.11  5045.5  270.17  5266.2  271.32  5304.2  269.86  5439.1  272.98
  5503.7  275.84  5565.8  289.16  5626.3  284.09  5756.9  284.14  5775.7  284.15
#Mann= 19 ,-1 , 0
  2732.6     .07       0  3415.9     .12       0  3587.7     .07       0
  3604.6     .12       0  3634.4     .07       0  3827.2      .1       0
    4026     .12       0  4338.5     .07       0  4658.2     .12       0
  4695.8     .07       0  4868.9     .12       0  4907.1      .1       0
  4987.2     .05       0    5029      .1       0  5266.2     .07       0
  5304.2      .1       0  5439.1     .07       0  5626.3    .033       0
  5756.9     .07       0
Bank Sta=4987.2,5029
XS Rating Curve= 0 ,0
Exp/Cntr=0.3,0.1

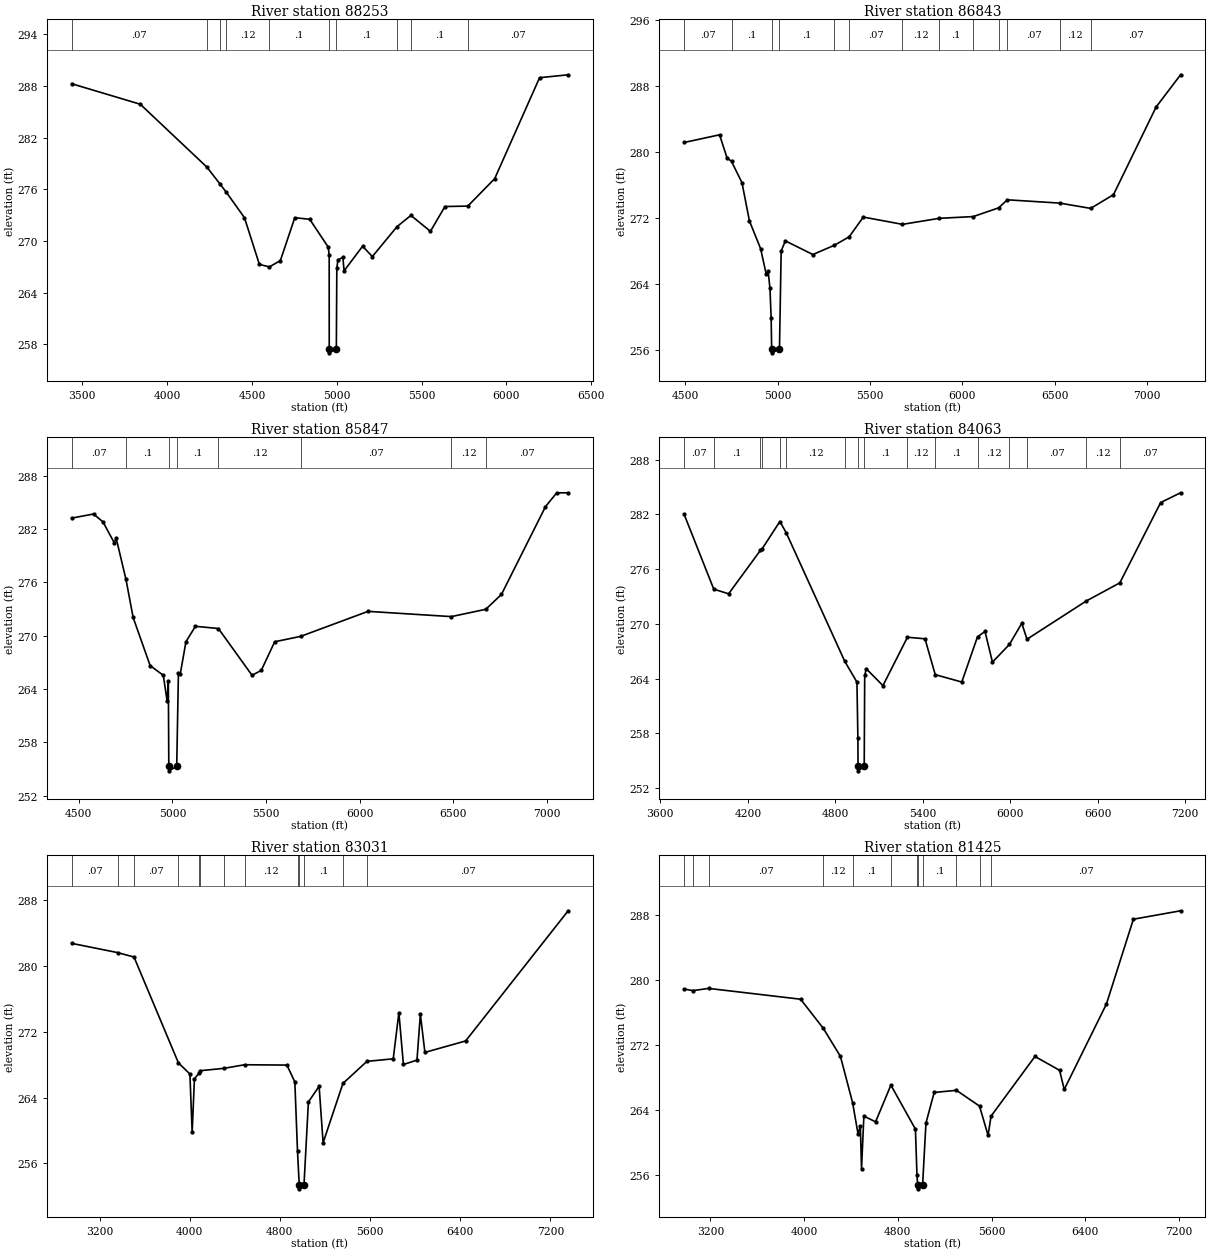
Type RM Length L Ch R = 1 ,88253   ,1410,1410,1410
BEGIN DESCRIPTION:
E20590
END DESCRIPTION:
XS GIS Cut Line= 4
      2418500.29     13684708.42      2416975.61     13683729.42
      2416526.24     13683456.59      2416012.66      13683167.7
#Sta/Elev= 30
  3437.4  288.27  3841.7  285.89  4234.9  278.58  4312.8   276.6  4349.3  275.66
  4456.1  272.71    4544  267.29  4602.9     267  4667.7  267.73  4752.7  272.71
  4840.6  272.53  4949.6  269.31  4955.5  268.38  4955.8  257.52  4956.8  257.02
  4997.7  257.52  5000.5  266.85    5007  267.81  5036.1  268.11  5043.4  266.54
  5152.4   269.4  5209.9   268.2  5355.7  271.68  5437.3  272.98  5552.4  271.13
  5637.8  274.01  5772.7  274.06  5931.3  277.25  6195.8  288.97  6364.3  289.31
#Mann= 10 ,-1 , 0
  3437.4     .07       0  4234.9     .12       0  4312.8     .07       0
  4349.3     .12       0  4602.9      .1       0  4955.8     .05       0
  4997.7      .1       0  5355.7     .07       0  5437.3      .1       0
  5772.7     .07       0
Bank Sta=4955.8,4997.7
XS Rating Curve= 0 ,0
Exp/Cntr=0.3,0.1

Type RM Length L Ch R = 1 ,86843   ,996,996,996
BEGIN DESCRIPTION:
E20589
END DESCRIPTION:
XS GIS Cut Line= 3
      2418724.96     13683504.73      2417681.77     13683360.29
      2416078.39     13683055.65
#Sta/Elev= 30
  4494.5  281.15  4686.3  282.08  4726.6  279.29  4750.9  278.86  4807.4  276.29
  4847.8  271.66  4908.4   268.3  4938.7   265.2  4948.7  265.62  4958.8  263.53
  4965.2  259.92    4968  256.21    4969  255.71  5010.2  256.21  5019.4  268.02
    5042  269.25    5191   267.6    5307  268.72  5387.2  269.74  5463.6  272.13
  5675.5  271.25  5874.8  271.98  6058.2  272.19  6196.1  273.25  6242.1  274.22
  6526.3  273.82  6693.3  273.18  6816.7  274.84  7047.5  285.45  7179.7  289.34
#Mann= 13 ,-1 , 0
  4494.5     .07       0  4750.9      .1       0    4968     .05       0
  5010.2      .1       0    5307     .12       0  5387.2     .07       0
  5675.5     .12       0  5874.8      .1       0  6058.2     .07       0
  6196.1      .1       0  6242.1     .07       0  6526.3     .12       0
  6693.3     .07       0
Bank Sta=4968,5010.2
XS Rating Curve= 0 ,0
Exp/Cntr=0.3,0.1

Type RM Length L Ch R = 1 ,85847   ,1784,1784,1784
BEGIN DESCRIPTION:
E20588
END DESCRIPTION:
XS GIS Cut Line= 3
      2418660.72     13682702.27      2417601.52     13682573.89
      2416044.75     13682862.77
#Sta/Elev= 30
  4461.8  283.24  4578.4   283.7  4628.7  282.82  4689.2  280.46  4699.2  280.99
  4751.7  276.34  4789.9  272.06  4880.6  266.65  4951.1  265.55  4971.2  262.66
  4977.8  264.88  4980.3  255.31  4981.3  254.81  5022.5  255.31  5031.7  265.86
  5041.7  265.74  5071.9  269.34  5122.3  271.07    5245  270.82  5424.5  265.56
  5473.9  266.11  5545.6  269.33  5684.6  269.94  6043.9  272.75  6488.4  272.16
    6672  272.98  6755.9  274.65  6991.1  284.53  7050.8  286.08  7112.1  286.09
#Mann= 8 ,-1 , 0
  4461.8     .07       0  4751.7      .1       0  4980.3     .05       0
  5022.5      .1       0    5245     .12       0  5684.6     .07       0
  6488.4     .12       0    6672     .07       0
Bank Sta=4980.3,5022.5
XS Rating Curve= 0 ,0
Exp/Cntr=0.3,0.1

Type RM Length L Ch R = 1 ,84063   ,1032,1032,1032
BEGIN DESCRIPTION:
SALTY CREEK_SUGAR CREEK 39.0
END DESCRIPTION:
XS GIS Cut Line= 3
      2418625.01     13682475.01        2417825.       13681525.
      2416025.02     13682724.99
#Sta/Elev= 30
  3762.9     282  3966.2   273.8  4067.9  273.29  4286.2  278.05  4295.9  278.17
  4419.6  281.21  4462.6     280  4865.1  265.88  4948.3  263.61  4954.8  257.47
  4955.8  254.39  4956.8  253.89  4998.1  254.39  5001.6  264.36  5012.4  265.07
  5126.6  263.23  5294.7  268.53    5415  268.36  5485.4  264.43  5667.4  263.62
  5775.2  268.58  5826.7  269.16  5877.7   265.8    5994  267.74    6079  270.06
  6114.6  268.31    6520  272.49  6751.5  274.49  7031.5  283.29  7168.2  284.36
#Mann= 16 ,-1 , 0
  3762.9     .07       0  3966.2      .1       0  4286.2     .07       0
  4295.9     .12       0  4419.6     .07       0  4462.6     .12       0
  4865.1      .1       0  4955.8     .05       0  4998.1      .1       0
  5294.7     .12       0  5485.4      .1       0  5775.2     .12       0
    5994      .1       0  6114.6     .07       0    6520     .12       0
  6751.5     .07       0
Bank Sta=4955.8,4998.1
XS Rating Curve= 0 ,0
Exp/Cntr=0.3,0.1

Type RM Length L Ch R = 1 ,83031   ,1606,1606,1606
BEGIN DESCRIPTION:
SALTY CREEK_SUGAR CREEK 38.0
END DESCRIPTION:
XS GIS Cut Line= 3
      2419703.94      13680712.2       2417986.7      13680680.1
      2415308.24     13680904.64
#Sta/Elev= 30
  2952.8  282.74  3359.8  281.62  3505.8  281.08  3899.5  268.23  4001.9  266.86
  4021.9  259.76  4041.9  266.26  4083.5  267.01  4095.7  267.27  4302.6  267.55
  4487.4  267.99  4862.7  267.95    4933   265.9  4956.7  257.46    4972  253.41
    4973  252.91  5014.3  253.41  5053.4  263.47  5148.4  265.37  5183.8  258.51
  5359.7  265.72  5572.4   268.4    5806  268.71  5856.2  274.31  5896.3  268.02
  6016.7  268.55  6046.9  274.12    6087  269.49  6448.3  270.88  7358.2   286.7
#Mann= 13 ,-1 , 0
  2952.8     .07       0  3359.8     .12       0  3505.8     .07       0
  3899.5      .1       0  4083.5     .12       0  4095.7      .1       0
  4302.6     .07       0  4487.4     .12       0  4956.7      .1       0
    4972     .05       0  5014.3      .1       0  5359.7     .12       0
  5572.4     .07       0
Bank Sta=4972,5014.3
XS Rating Curve= 0 ,0
Exp/Cntr=0.3,0.1

Type RM Length L Ch R = 1 ,81425   ,949,949,949
BEGIN DESCRIPTION:
SALTY CREEK_SUGAR CREEK 37.0
END DESCRIPTION:
XS GIS Cut Line= 3
      2419398.99     13679540.61      2417745.96     13679540.61
      2415162.09     13679540.61
#Sta/Elev= 30
  2975.8  278.92  3050.9  278.73  3185.3     279  3969.8  277.67  4163.7  274.08
  4309.8  270.63  4414.1   264.9  4459.8   261.1  4479.8  262.04  4489.8  256.81
  4509.8  263.28  4609.8  262.57  4740.4  267.09  4949.8  261.67  4962.9  256.04
  4968.6  254.82  4969.6  254.32    5011  254.82  5039.8  262.43  5109.8  266.19
  5299.9  266.45  5496.7  264.51  5569.8   260.9  5595.1  263.27  5969.8  270.62
  6179.8  268.92  6219.8  266.56  6579.8  277.08  6809.8  287.52  7212.7  288.56
#Mann= 12 ,-1 , 0
  2975.8     .07       0  3050.9     .12       0  3185.3     .07       0
  4163.7     .12       0  4414.1      .1       0  4740.4     .12       0
  4962.9      .1       0  4968.6     .05       0    5011      .1       0
  5299.9     .07       0  5496.7     .12       0  5595.1     .07       0
Bank Sta=4968.6,5011
XS Rating Curve= 0 ,0
Exp/Cntr=0.3,0.1

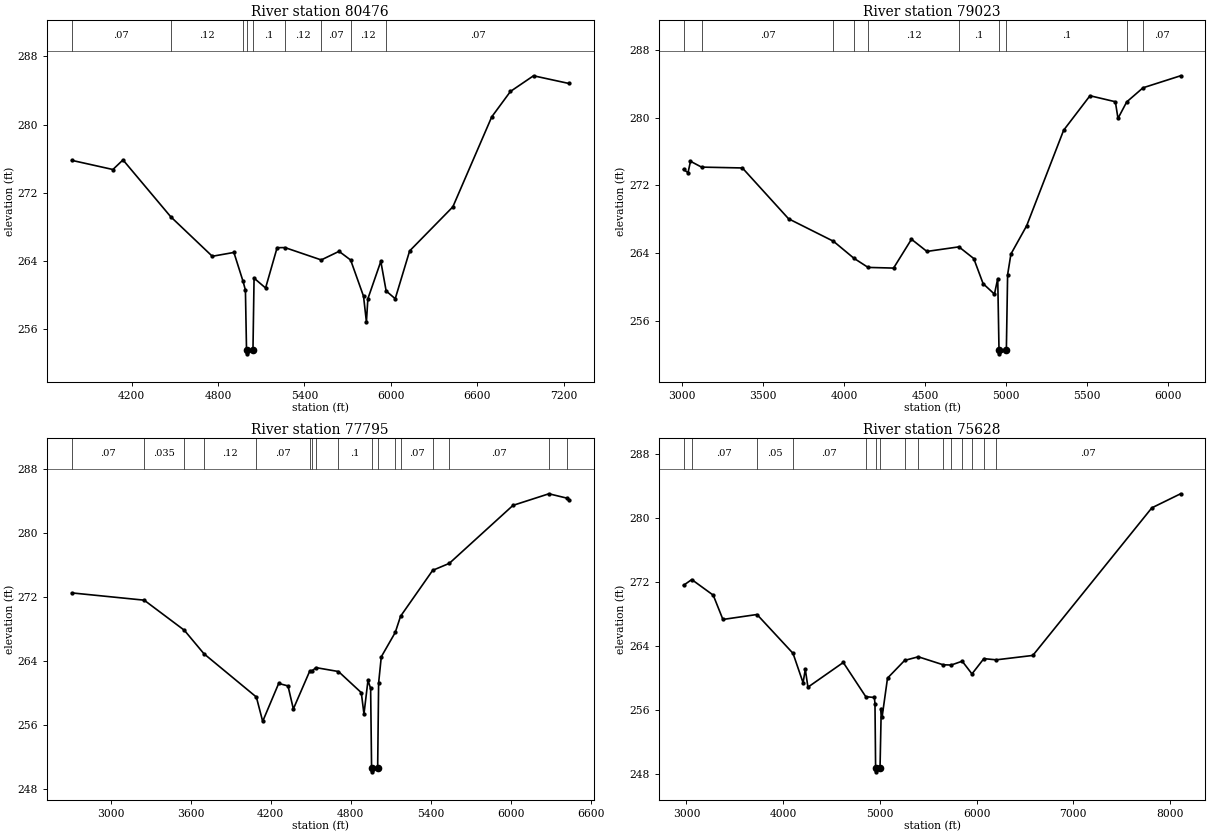
Type RM Length L Ch R = 1 ,80476   ,1453,1453,1453
BEGIN DESCRIPTION:
E20587
END DESCRIPTION:
XS GIS Cut Line= 3
      2418741.03     13678673.97      2416927.46     13678673.97
      2415290.43     13678673.97
#Sta/Elev= 30
  3784.4  275.79  4070.4  274.71  4140.4  275.84  4471.7  269.16  4760.4  264.51
  4910.4  264.96  4974.2  261.55  4990.4  260.53    4998  253.54    4999  253.04
  5042.8  253.54  5050.4  261.94  5130.4  260.78  5210.4  265.52  5265.3  265.53
  5516.8  264.08  5640.4  265.09  5720.8  264.07  5810.4  259.81  5830.4   256.8
  5840.4  259.51  5930.4  263.91  5967.4  260.43  6030.4  259.52  6130.4  265.14
  6430.4  270.32  6700.4   280.9  6830.4  283.89  6990.4  285.73    7235  284.83
#Mann= 9 ,-1 , 0
  3784.4     .07       0  4471.7     .12       0  4974.2      .1       0
    4998     .05       0  5042.8      .1       0  5265.3     .12       0
  5516.8     .07       0  5720.8     .12       0  5967.4     .07       0
Bank Sta=4998,5042.8
XS Rating Curve= 0 ,0
Exp/Cntr=0.3,0.1

Type RM Length L Ch R = 1 ,79023   ,1228,1228,1228
BEGIN DESCRIPTION:
E20586
END DESCRIPTION:
XS GIS Cut Line= 2
      2418532.32     13677422.15      2415515.16     13677983.85
#Sta/Elev= 30
  3008.6  273.89  3036.4  273.51  3051.6  274.86  3119.8  274.17  3372.1  274.07
  3657.2  268.06  3934.4   265.4  4060.8  263.39  4148.2  262.31  4305.5  262.23
  4416.1  265.64  4511.3   264.2  4709.1  264.74  4800.6  263.36  4858.4  260.39
  4928.4  259.15  4948.7  260.99  4956.5  252.59  4957.5  252.09    5002  252.59
  5009.7  261.45  5030.1  263.89  5127.2  267.23  5355.6  278.53  5518.3  282.61
    5675   281.9  5691.2  279.93  5745.1  281.88  5845.8  283.55  6077.6  284.97
#Mann= 10 ,-1 , 0
  3008.6    .035       0  3119.8     .07       0  3934.4     .12       0
  4060.8     .07       0  4148.2     .12       0  4709.1      .1       0
  4956.5     .05       0    5002      .1       0  5745.1    .035       0
  5845.8     .07       0
Bank Sta=4956.5,5002
XS Rating Curve= 0 ,0
Exp/Cntr=0.3,0.1

Type RM Length L Ch R = 1 ,77795   ,2167,2167,2167
BEGIN DESCRIPTION:
E20585
END DESCRIPTION:
XS GIS Cut Line= 3
       2418468.2     13676699.93      2415852.17     13676699.93
      2414953.43     13677357.94
#Sta/Elev= 30
  2706.4  272.53  3250.3  271.62  3551.5  267.86  3698.9  264.92  4092.1  259.51
  4139.6  256.47  4259.6  261.21  4329.6   260.9  4369.6  258.02  4491.5  262.71
  4512.5  262.81  4538.6  263.19  4708.4   262.7  4879.6  260.06  4899.6  257.39
  4929.6  261.58  4949.6   260.6  4956.8  250.66  4957.8  250.16  5002.4  250.66
  5009.6  261.27  5029.6  264.54  5134.5  267.59  5174.2  269.61  5415.3  275.35
  5539.9  276.22  6017.9  283.47  6287.5  284.92  6421.5  284.38  6436.3  284.12
#Mann= 17 ,-1 , 0
  2706.4     .07       0  3250.3    .035       0  3551.5     .07       0
  3698.9     .12       0  4092.1     .07       0  4491.5     .12       0
  4512.5     .07       0  4538.6     .12       0  4708.4      .1       0
  4956.8     .05       0  5002.4      .1       0  5134.5      .1       0
  5174.2     .07       0  5415.3    .035       0  5539.9     .07       0
  6287.5    .035       0  6421.5     .07       0
Bank Sta=4956.8,5002.4
XS Rating Curve= 0 ,0
Exp/Cntr=0.3,0.1

Type RM Length L Ch R = 1 ,75628   ,1757,1757,1757
BEGIN DESCRIPTION:
E20584
END DESCRIPTION:
XS GIS Cut Line= 4
      2418548.42      13676491.3      2416654.63     13675095.03
      2416012.67     13675191.32      2415050.17     13677100.28
#Sta/Elev= 30
  2969.6  271.54  3054.6  272.26  3276.7  270.31  3376.9  267.27  3729.4  267.89
  4101.9  263.03    4206  259.35  4228.7  261.04  4256.1   258.8  4621.6  261.89
  4854.2  257.61  4943.2  257.51  4949.4  256.73  4955.9  248.71  4956.9  248.21
  5001.6  248.71  5014.2  256.13  5022.6  255.03    5079  259.93  5256.4  262.15
  5397.5   262.6  5654.6   261.6  5738.5  261.57  5851.4  262.05  5952.4  260.46
  6075.4  262.37  6203.1  262.22  6581.7  262.77  7812.4  281.23  8109.5  282.99
#Mann= 15 ,-1 , 0
  2969.6     .05       0  3054.6     .07       0  3729.4     .05       0
  4101.9     .07       0  4854.2     .12       0  4955.9     .05       0
  5001.6     .12       0  5256.4     .07       0  5397.5    .035       0
  5654.6     .12       0  5738.5     .07       0  5851.4     .12       0
  5952.4     .07       0  6075.4     .12       0  6203.1     .07       0
Bank Sta=4955.9,5001.6
XS Rating Curve= 0 ,0
Exp/Cntr=0.3,0.1