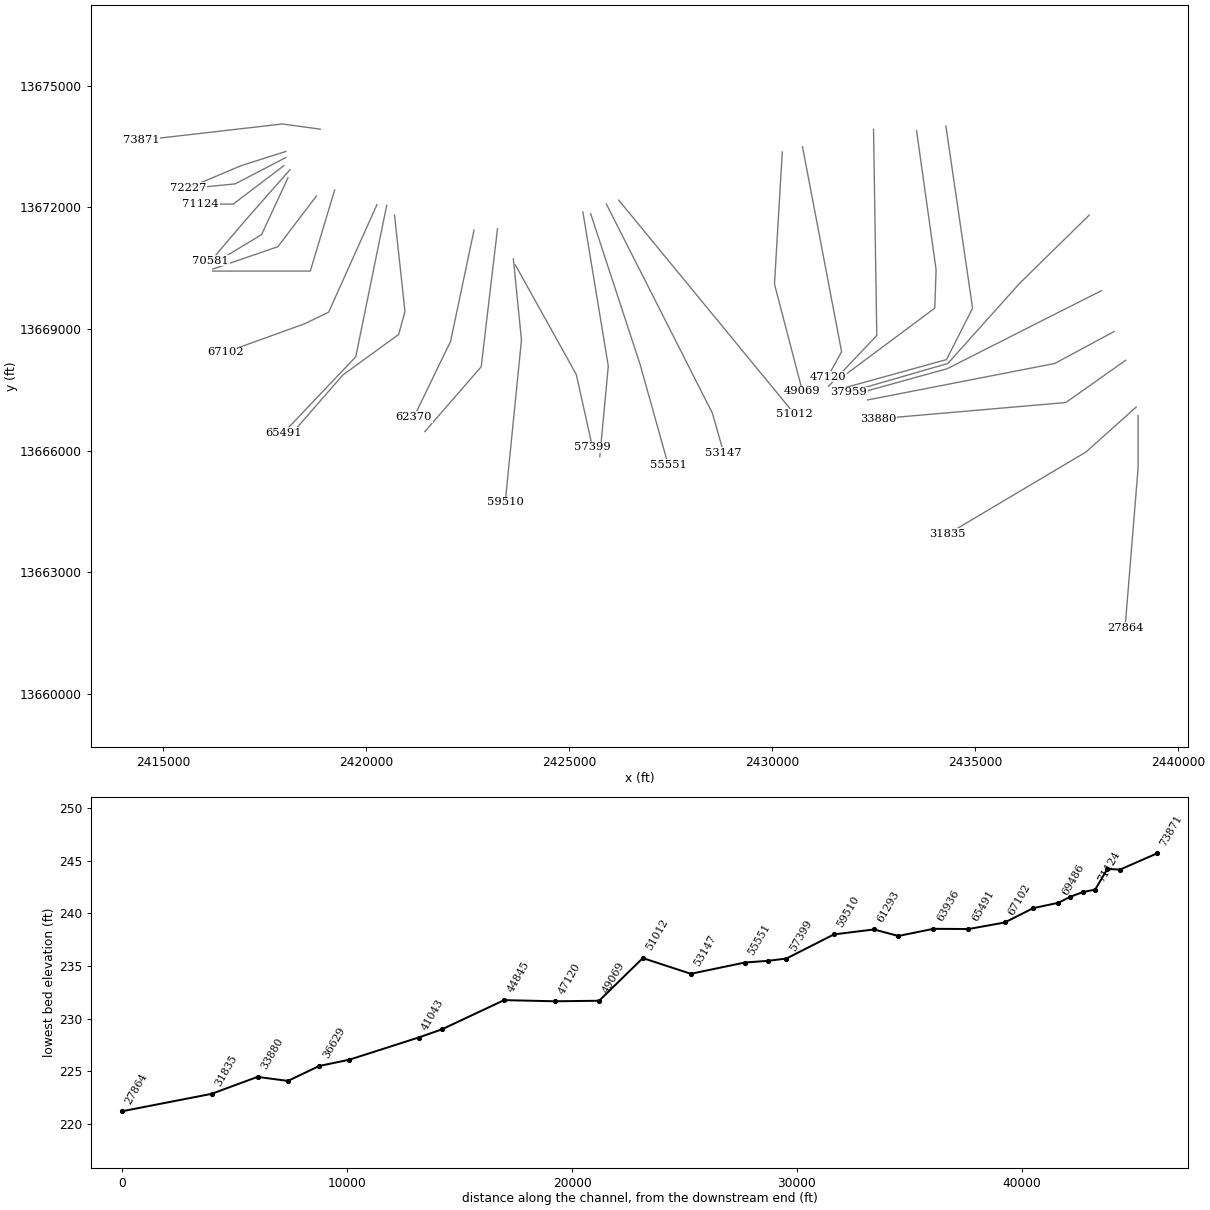
HEC-RAS study SALTY CREEK_SUGAR CREEK.prj: SALTY CREEK_SUGAR CREEK Base Level Engineering

--- SALTY CREEK_SUGAR CREEK.g01 (geometry) --- (continued)

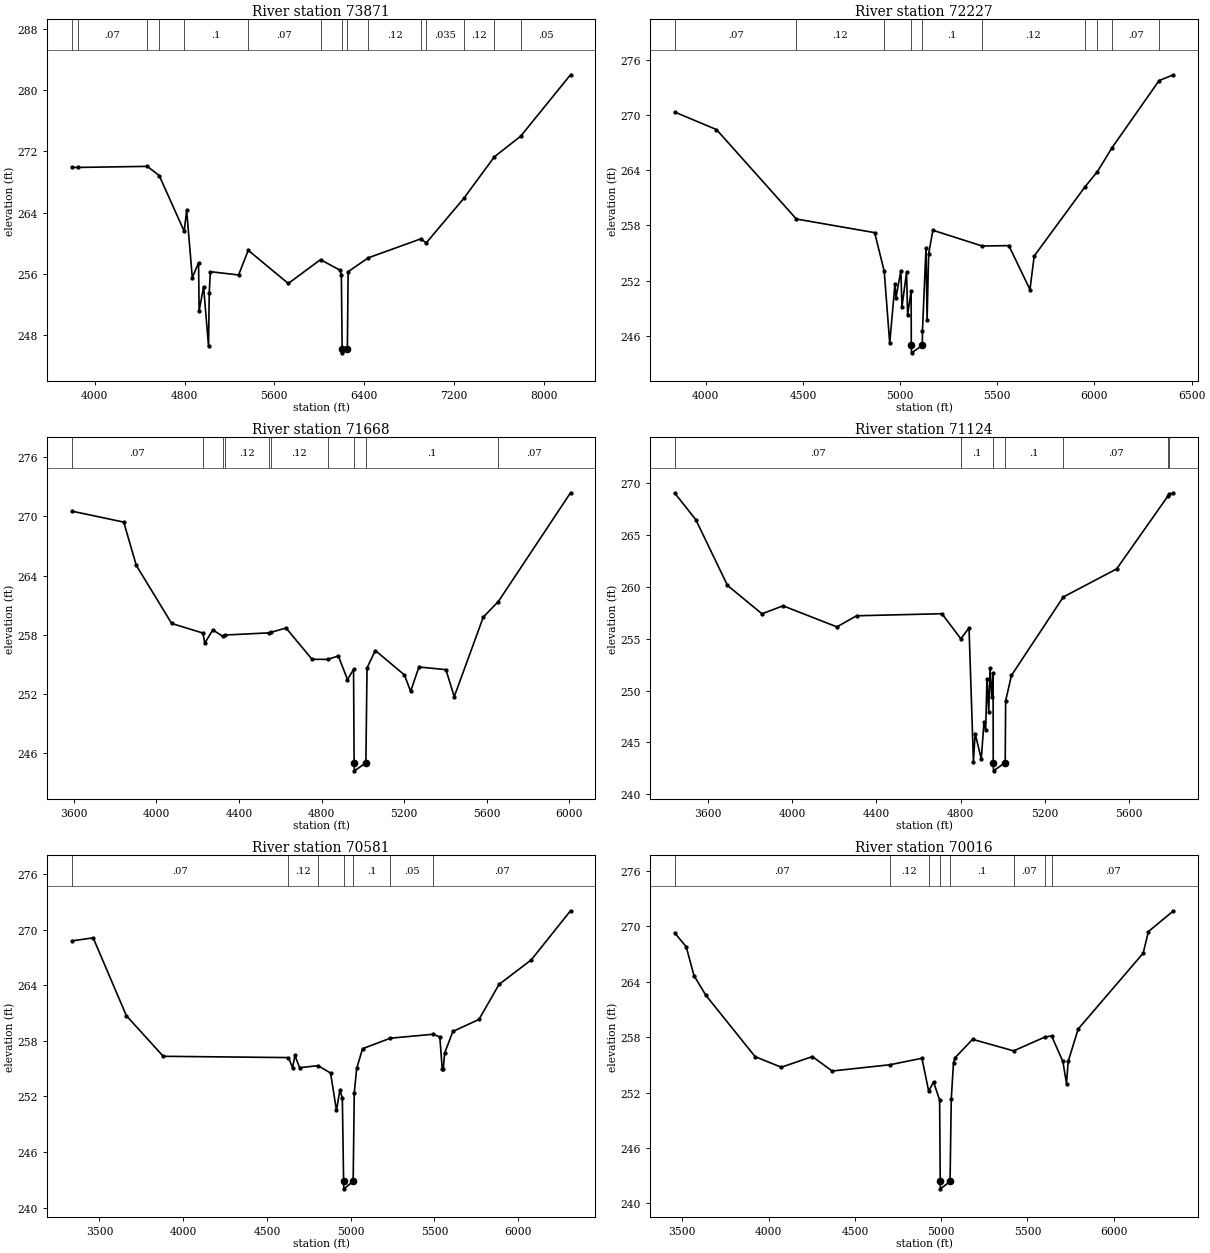
Type RM Length L Ch R = 1 ,73871   ,1644,1644,1644
BEGIN DESCRIPTION:
SALTY CREEK_SUGAR CREEK 36.0
END DESCRIPTION:
XS GIS Cut Line= 3
      2418869.39     13673923.45      2417938.55     13674051.84
      2414455.94     13673650.61
#Sta/Elev= 30
  3795.1   269.9    3846  269.89  4468.5  270.03  4574.5  268.83  4796.9  261.56
  4818.9   264.3  4869.2  255.51    4925  257.46  4930.1  251.16  4969.8  254.33
    5014  246.57  5020.2  253.52  5030.2  256.29  5281.9  255.86  5367.8  259.08
  5724.8  254.75    6012  257.86  6187.8  256.47  6197.9  255.83  6204.9   246.2
  6205.9   245.7  6251.4   246.2  6258.3  256.29    6438   258.1  6904.1  260.56
  6955.2  260.06  7288.3  265.84    7562  271.28  7797.1  273.98  8240.4  281.98
#Mann= 15 ,-1 , 0
  3795.1    .035       0    3846     .07       0  4468.5    .035       0
  4574.5     .07       0  4796.9      .1       0  5367.8     .07       0
    6012      .1       0  6204.9     .05       0  6251.4      .1       0
    6438     .12       0  6904.1     .05       0  6955.2    .035       0
  7288.3     .12       0    7562     .07       0  7797.1     .05       0
Bank Sta=6204.9,6251.4
XS Rating Curve= 0 ,0
Exp/Cntr=0.3,0.1

Type RM Length L Ch R = 1 ,72227   ,559,559,559
BEGIN DESCRIPTION:
SALTY CREEK_SUGAR CREEK 35.0
END DESCRIPTION:
XS GIS Cut Line= 3
      2418024.96     13673374.99        2416925.       13673025.
      2415624.96     13672474.98
#Sta/Elev= 30
  3840.6   270.3  4055.3   268.4  4466.3  258.69    4869  257.21  4918.3  253.02
  4946.6  245.18  4973.5  251.68  4978.8  250.15    5004  253.09  5009.5  249.13
  5033.2  252.92  5038.6  248.27  5056.8   250.9  5057.5  244.96  5058.8  244.16
  5114.4  244.96  5115.1  246.58  5133.3  255.58  5138.8  247.75  5146.9  254.91
  5168.6  257.47  5421.9  255.76  5559.5   255.8  5668.1  251.03  5689.8  254.67
  5949.7  262.14  6015.3  263.84  6089.7  266.41  6332.4  273.72  6406.5  274.35
#Mann= 10 ,-1 , 0
  3840.6     .07       0  4466.3     .12       0  4918.3      .1       0
  5057.5     .05       0  5114.4      .1       0  5421.9     .12       0
  5949.7     .07       0  6015.3     .12       0  6089.7     .07       0
  6332.4     .05       0
Bank Sta=5057.5,5114.4
XS Rating Curve= 0 ,0
Exp/Cntr=0.3,0.1

Type RM Length L Ch R = 1 ,71668   ,544,544,544
BEGIN DESCRIPTION:
SALTY CREEK_SUGAR CREEK 34.0
END DESCRIPTION:
XS GIS Cut Line= 3
      2418024.97     13673224.98        2416775.       13672575.
      2415774.95       13672475.
#Sta/Elev= 30
  3591.1  270.54  3842.5  269.43  3903.2  265.05  4074.4  259.16  4225.6  258.19
  4234.8  257.16  4273.4  258.51  4320.8  257.87  4334.9  257.99  4546.8  258.21
  4553.5  258.25    4628   258.7  4754.2  255.53  4829.9  255.52  4881.2  255.87
  4925.4  253.48  4954.9   254.5  4957.6  245.03  4958.9  244.23  5014.5  245.03
  5020.1  254.66  5060.3  256.42    5201  253.95  5231.1  252.28  5271.3  254.75
    5402  254.48  5442.2  251.74  5582.9  259.81  5655.7  261.38    6005   272.4
#Mann= 10 ,-1 , 0
  3591.1     .07       0  4225.6     .12       0  4320.8     .07       0
  4334.9     .12       0  4546.8     .07       0  4553.5     .12       0
  4829.9      .1       0  4957.6     .05       0  5014.5      .1       0
  5655.7     .07       0
Bank Sta=4957.6,5014.5
XS Rating Curve= 0 ,0
Exp/Cntr=0.3,0.1

Type RM Length L Ch R = 1 ,71124   ,543,543,543
BEGIN DESCRIPTION:
SALTY CREEK_SUGAR CREEK 33.0
END DESCRIPTION:
XS GIS Cut Line= 3
      2417974.97     13673024.97        2416725.       13672075.
      2415924.99       13672075.
#Sta/Elev= 30
  3441.8  269.04  3542.2  266.46  3692.3  260.14  3856.2   257.4  3956.4  258.17
  4212.2  256.14  4305.8  257.21  4711.3  257.41  4801.4  254.99  4840.2  256.04
  4861.1  243.15  4869.3  245.86  4898.4  243.41  4911.3  246.94  4919.2  246.23
  4925.5  251.12  4933.8  247.93  4940.1   252.2  4948.3  249.38  4954.6  251.67
  4955.2  243.06  4956.5  242.26  5012.1  243.06  5014.3  249.02  5041.8  251.46
  5288.1  259.02  5541.8  261.73  5785.2  268.75  5792.7  268.92  5811.8  269.07
#Mann= 7 ,-1 , 0
  3441.8     .07       0  4801.4      .1       0  4955.2     .05       0
  5012.1      .1       0  5288.1     .07       0  5785.2     .05       0
  5792.7     .07       0
Bank Sta=4955.2,5012.1
XS Rating Curve= 0 ,0
Exp/Cntr=0.3,0.1

Type RM Length L Ch R = 1 ,70581   ,565,565,565
BEGIN DESCRIPTION:
SALTY CREEK_SUGAR CREEK 32.0
END DESCRIPTION:
XS GIS Cut Line= 3
      2418125.01     13672925.01        2417025.       13671675.
      2416175.02     13670675.02
#Sta/Elev= 30
  3334.9  268.78  3462.5  269.11  3660.8  260.71  3880.9  256.33  4628.5  256.19
  4653.2  255.09    4667  256.42    4695   255.1  4805.1  255.32    4880  254.52
  4915.1  250.49    4936  252.73  4950.2  251.78  4957.7  242.83  4959.1  242.03
  5014.7  242.83  5021.4  252.41  5035.7  255.02  5070.8  257.15  5236.3  258.28
  5491.6  258.71  5532.1  258.42  5546.4     255    5553  254.98  5560.7  256.67
  5610.1  259.01    5766  260.31  5885.9  264.09  6077.9  266.73  6312.4  272.03
#Mann= 7 ,-1 , 0
  3334.9     .07       0  4628.5     .12       0  4805.1      .1       0
  4957.7     .05       0  5014.7      .1       0  5236.3     .05       0
  5491.6     .07       0
Bank Sta=4957.7,5014.7
XS Rating Curve= 0 ,0
Exp/Cntr=0.3,0.1

Type RM Length L Ch R = 1 ,70016   ,530,530,530
BEGIN DESCRIPTION:
SALTY CREEK_SUGAR CREEK 31.0
END DESCRIPTION:
XS GIS Cut Line= 3
        2418075.     13672725.01        2417425.       13671325.
      2416275.03     13670625.02
#Sta/Elev= 30
  3456.2  269.27  3522.4  267.78  3567.5  264.66  3636.2  262.53    3922  255.88
  4073.6  254.74  4253.6  255.89  4368.1  254.33  4703.5  255.01  4888.4  255.71
  4927.6  252.15  4955.6  253.14    4991  251.19  4994.4  242.38  4995.8  241.58
  5051.4  242.38  5058.3  251.26  5071.4  255.24  5081.1  255.78  5181.8  257.76
  5419.8  256.51  5601.3  258.01  5639.6  258.13  5704.9  255.37  5726.2  252.97
  5735.8  255.36  5793.9  258.88  6170.4  267.08  6200.7  269.42    6346  271.67
#Mann= 8 ,-1 , 0
  3456.2     .07       0  4703.5     .12       0  4927.6      .1       0
  4994.4     .05       0  5051.4      .1       0  5419.8     .07       0
  5601.3      .1       0  5639.6     .07       0
Bank Sta=4994.4,5051.4
XS Rating Curve= 0 ,0
Exp/Cntr=0.3,0.1

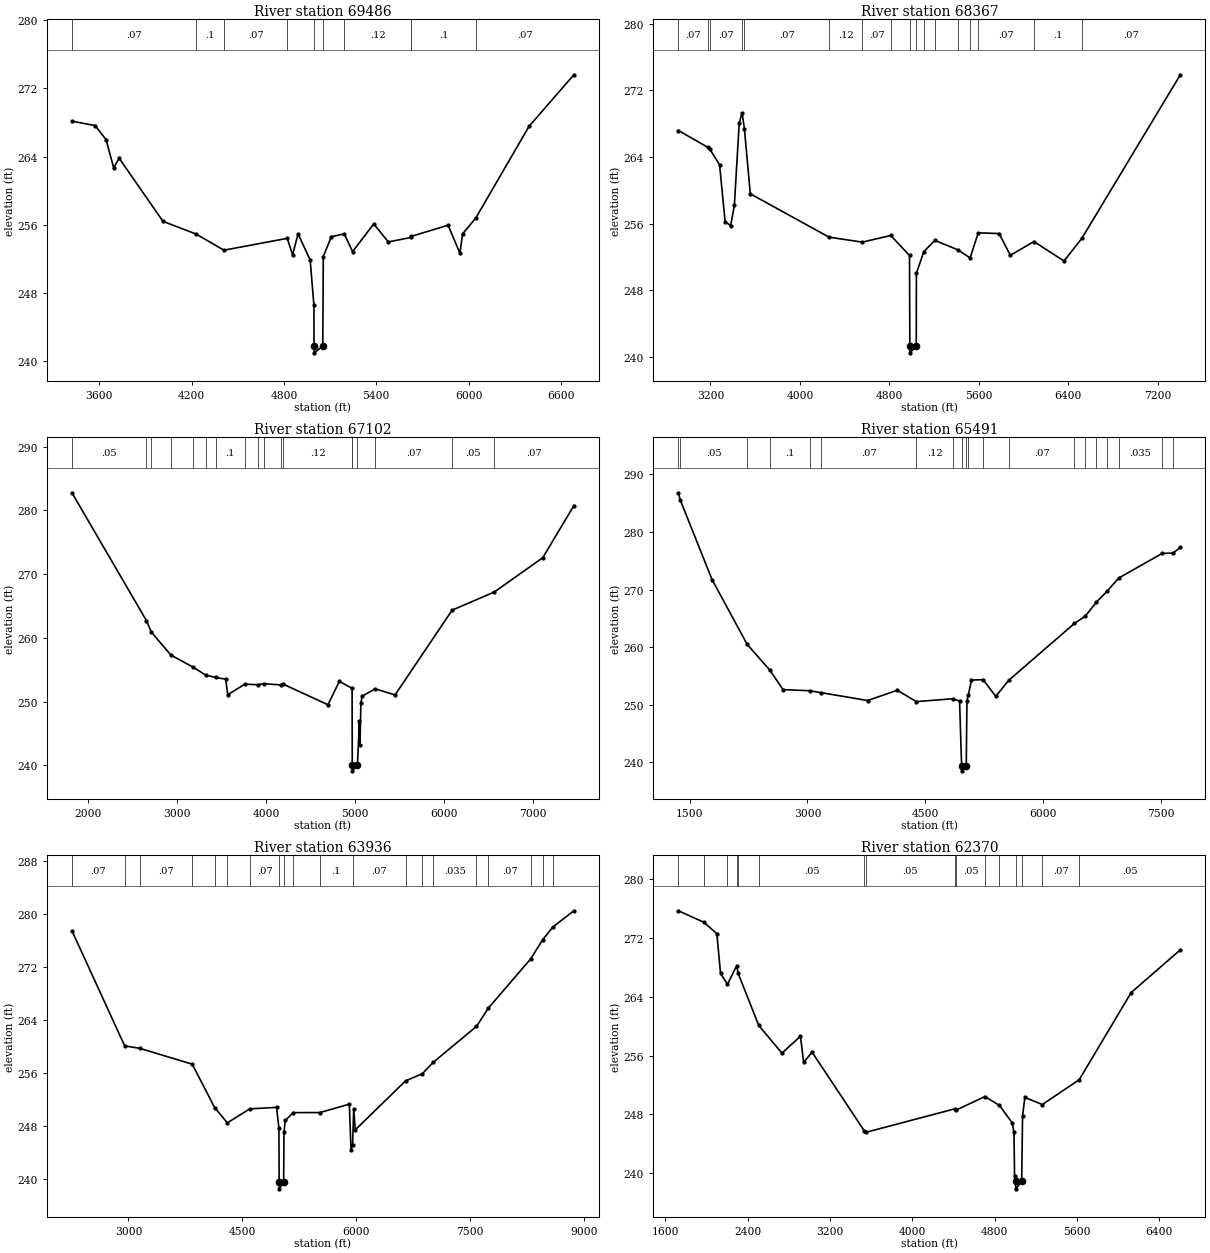
Type RM Length L Ch R = 1 ,69486   ,1119,1119,1119
BEGIN DESCRIPTION:
SALTY CREEK_SUGAR CREEK 30.0
END DESCRIPTION:
XS GIS Cut Line= 3
      2418774.97     13672274.96        2417825.       13671025.
      2416224.98     13670474.99
#Sta/Elev= 30
  3422.3  268.16    3573  267.65  3643.7  266.01  3693.6  262.69    3729  263.82
  4013.9  256.42  4228.2  254.94    4410  253.04  4821.6  254.43  4856.1  252.51
  4891.8  254.95  4970.5  251.89  4994.9  246.56  4995.5  241.81  4996.8  241.01
  5052.5  241.81  5055.7   252.3  5108.6  254.63  5192.2  254.95  5246.1  252.87
  5383.5  256.12  5478.7  254.01    5624  254.53  5628.2  254.66  5866.8  255.97
    5944  252.68  5960.6  254.94  6046.8  256.81  6392.7  267.55  6684.2   273.6
#Mann= 10 ,-1 , 0
  3422.3     .07       0  4228.2      .1       0    4410     .07       0
  4821.6      .1       0  4995.5     .05       0  5052.5      .1       0
  5192.2     .12       0    5624     .07       0  5628.2      .1       0
  6046.8     .07       0
Bank Sta=4995.5,5052.5
XS Rating Curve= 0 ,0
Exp/Cntr=0.3,0.1

Type RM Length L Ch R = 1 ,68367   ,1265,1265,1265
BEGIN DESCRIPTION:
SALTY CREEK_SUGAR CREEK 29.0
END DESCRIPTION:
XS GIS Cut Line= 3
      2419225.01     13672425.04        2418625.       13670425.
        2416225.       13670425.
#Sta/Elev= 30
  2913.3  267.17  3173.9  265.18  3195.1  264.92  3281.4  263.06    3331  256.23
  3380.5  255.77  3413.6   258.2  3457.1   268.1  3482.9  269.31  3503.3  267.38
  3556.3  259.58  4260.2  254.38  4558.1  253.78  4811.8  254.58  4979.7  252.18
  4982.9   241.3  4984.2   240.5    5040   241.3  5041.4  250.05  5108.1  252.65
  5206.5  253.99  5413.8  252.85  5521.6  251.89  5594.6   254.9  5781.4  254.81
  5881.4   252.2  6092.2  253.85  6361.4  251.52    6521  254.24  7401.4  273.86
#Mann= 17 ,-1 , 0
  2913.3     .07       0  3173.9     .05       0  3195.1     .07       0
  3482.9     .05       0  3503.3     .07       0  4260.2     .12       0
  4558.1     .07       0  4811.8      .1       0  4982.9     .05       0
    5040      .1       0  5108.1     .07       0  5206.5     .12       0
  5413.8     .07       0  5521.6     .12       0  5594.6     .07       0
  6092.2      .1       0    6521     .07       0
Bank Sta=4982.9,5040
XS Rating Curve= 0 ,0
Exp/Cntr=0.3,0.1

Type RM Length L Ch R = 1 ,67102   ,1611,1611,1611
BEGIN DESCRIPTION:
E20583
END DESCRIPTION:
XS GIS Cut Line= 4
      2420265.68     13672061.78      2419078.04     13669413.66
      2418484.22     13669124.78      2416526.27     13668418.63
#Sta/Elev= 30
  1816.1  282.77  2653.3  262.72  2708.8  260.91  2929.1   257.3  3177.1  255.42
  3321.1  254.15  3430.5   253.8  3545.1  253.52  3568.3  251.08  3758.5  252.73
  3908.6  252.66  3973.7  252.81  4164.4  252.62  4188.5  252.76    4695  249.51
  4822.8  253.18  4966.4  252.09  4968.3  240.04  4969.7  239.14  5026.8  240.04
  5048.3  246.99  5055.3  243.19  5065.2  249.72  5077.6  250.84  5225.1  252.01
  5449.4  251.05  6091.2  264.35  6566.7  267.21  7110.6  272.58  7460.1  280.75
#Mann= 18 ,-1 , 0
  1816.1     .05       0  2653.3     .07       0  2708.8     .05       0
  2929.1     .07       0  3177.1     .05       0  3321.1     .07       0
  3430.5      .1       0  3758.5     .12       0  3908.6     .07       0
  3973.7     .12       0  4164.4     .07       0  4188.5     .12       0
  4966.4      .1       0  4968.3     .05       0  5026.8      .1       0
  5225.1     .07       0  6091.2     .05       0  6566.7     .07       0
Bank Sta=4968.3,5026.8
XS Rating Curve= 0 ,0
Exp/Cntr=0.3,0.1

Type RM Length L Ch R = 1 ,65491   ,1555,1555,1555
BEGIN DESCRIPTION:
E20582
END DESCRIPTION:
XS GIS Cut Line= 3
       2420506.4     13672045.72      2419744.54     13668311.06
      2417967.85     13666438.74
#Sta/Elev= 30
  1356.1   286.8  1379.9  285.54  1784.4  271.73  2231.7  260.48  2521.9  255.98
  2688.8  252.62  3027.4  252.43  3166.3  252.11  3765.4  250.73    4144  252.51
  4387.1  250.54  4847.4  251.03  4937.1  250.63  4963.2  239.42  4964.6  238.52
  5022.3  239.42    5031  250.69  5049.7  251.74  5088.7  254.28    5238  254.35
  5397.8  251.45    5562  254.22  6400.7  264.12  6540.3   265.4  6679.9  267.82
  6819.5  269.75  6962.3  271.98  7517.4  276.27    7657  276.33  7748.8  277.33
#Mann= 20 ,-1 , 0
  1356.1     .07       0  1379.9     .05       0  2231.7     .07       0
  2521.9      .1       0  3027.4     .12       0  3166.3     .07       0
  4387.1     .12       0  4847.4      .1       0  4963.2     .05       0
  5022.3      .1       0  5049.7     .12       0    5238     .12       0
    5562     .07       0  6400.7    .035       0  6540.3    .035       0
  6679.9    .035       0  6819.5    .035       0  6962.3    .035       0
  7517.4     .07       0    7657     .07       0
Bank Sta=4963.2,5022.3
XS Rating Curve= 0 ,0
Exp/Cntr=0.3,0.1

Type RM Length L Ch R = 1 ,63936   ,1566,1566,1566
BEGIN DESCRIPTION:
E20581
END DESCRIPTION:
XS GIS Cut Line= 5
      2420698.99       13671805.      2420955.78     13669429.71
       2420801.5     13668861.99        2419425.     13667861.11
      2418158.85     13666404.17
#Sta/Elev= 30
  2256.9  277.51  2951.1  260.13  3148.6  259.76  3839.9  257.37  4136.1  250.82
  4303.3   248.5  4598.8  250.62  4951.4  250.84  4982.5  247.72  4985.4  239.54
  4986.8  238.54  5044.7  239.54  5049.6  247.05  5065.4  248.86  5171.9  250.05
  5523.4  250.06    5910  251.33  5931.7  244.43  5952.4  245.15  5967.3  250.65
  5988.2  247.45  6649.9  254.84  6872.3  255.93  7012.9  257.63  7584.4  263.07
  7737.7  265.79  8298.8  273.28  8456.4  276.17  8590.2  278.08  8866.5  280.53
#Mann= 20 ,-1 , 0
  2256.9     .07       0  2951.1    .035       0  3148.6     .07       0
  3839.9     .12       0  4136.1     .12       0  4303.3     .12       0
  4598.8     .07       0  4985.4     .05       0  5044.7      .1       0
  5171.9     .07       0  5523.4      .1       0  5952.4     .07       0
  6649.9     .07       0  6872.3     .07       0  7012.9    .035       0
  7584.4    .035       0  7737.7     .07       0  8298.8     .05       0
  8456.4     .05       0  8590.2    .045       0
Bank Sta=4985.4,5044.7
XS Rating Curve= 0 ,0
Exp/Cntr=0.3,0.1

Type RM Length L Ch R = 1 ,62370   ,1077,1077,1077
BEGIN DESCRIPTION:
SALTY CREEK_SUGAR CREEK 24.0
END DESCRIPTION:
XS GIS Cut Line= 3
      2422656.97     13671435.82      2422079.21     13668691.45
      2421174.98     13666824.97
#Sta/Elev= 30
  1726.9  275.73  1975.9  274.15  2100.6  272.61  2136.5  267.19  2203.7  265.72
  2293.7  268.26  2306.5  267.24  2507.5  260.12  2732.9  256.34  2913.2  258.64
  2943.8  255.11  3026.7  256.47  3531.3   245.8  3547.2  245.55  4414.7  248.76
  4429.2  248.61  4706.5  250.43  4847.3  249.22  4971.9  246.84  4988.5  245.57
  4994.2   239.6  5003.9  238.86  5005.4  237.86  5063.3  238.86    5072  247.76
  5094.2  250.31  5264.2  249.34  5623.2  252.73  6127.6  264.59  6605.4  270.41
#Mann= 16 ,-1 , 0
  1726.9     .05       0  1975.9    .035       0  2203.7     .07       0
  2293.7    .035       0  2306.5     .07       0  2507.5     .05       0
  3531.3     .07       0  3547.2     .05       0  4414.7     .07       0
  4429.2     .05       0  4706.5     .07       0  4847.3      .1       0
  5003.9     .05       0  5063.3      .1       0  5264.2     .07       0
  5623.2     .05       0
Bank Sta=5003.9,5063.3
XS Rating Curve= 0 ,0
Exp/Cntr=0.3,0.1

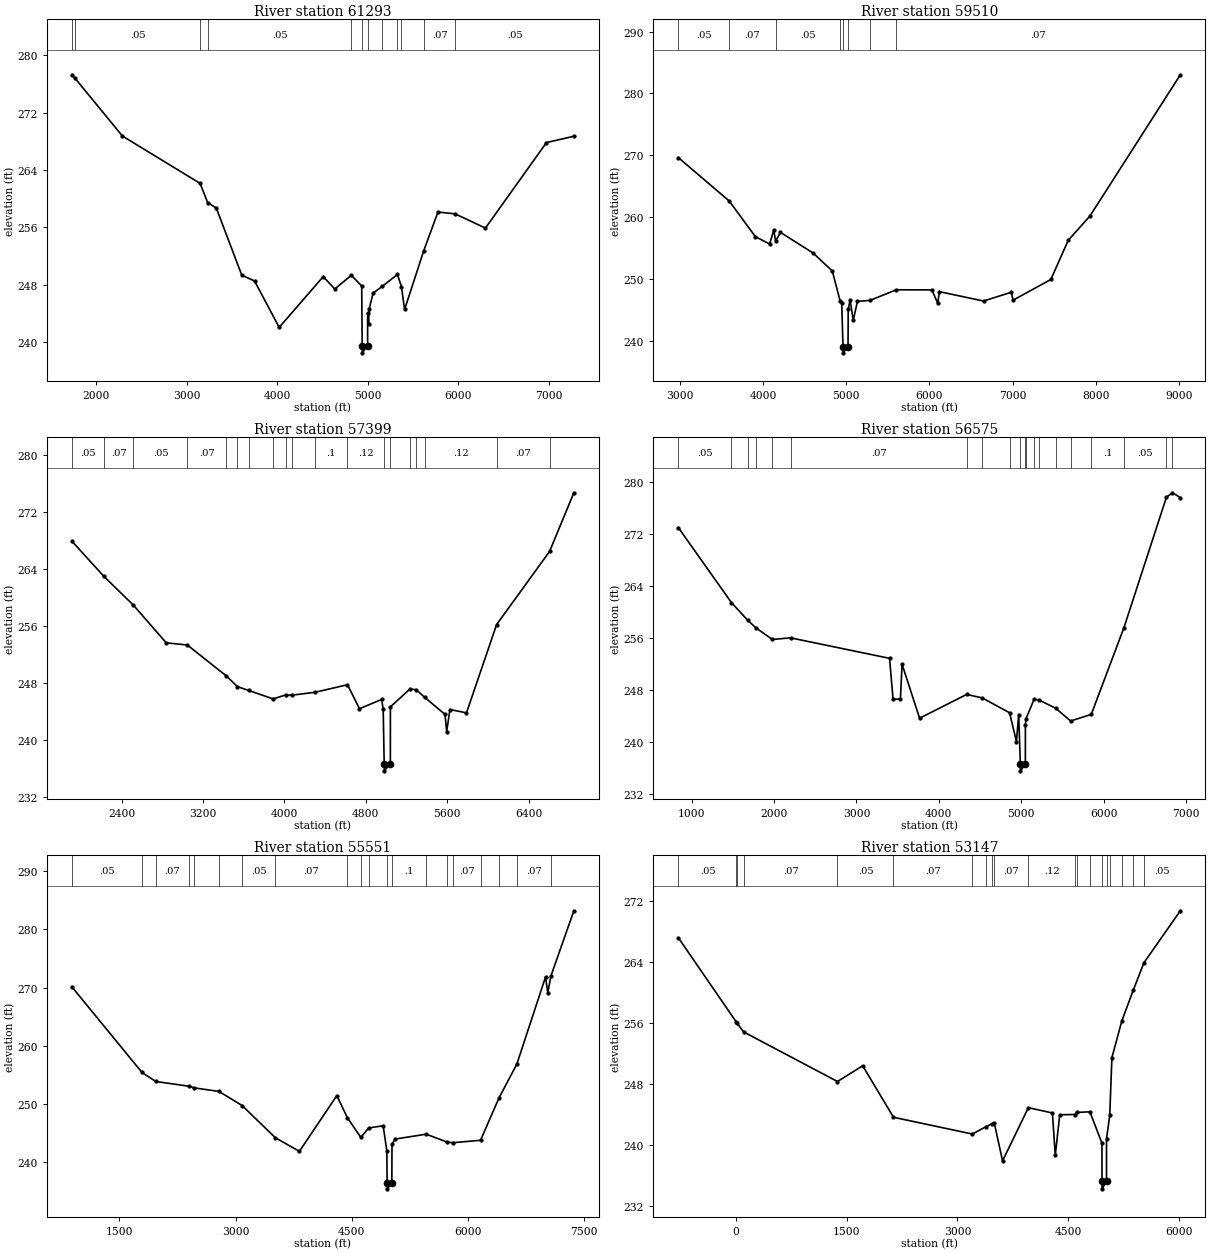
Type RM Length L Ch R = 1 ,61293   ,1783,1783,1783
BEGIN DESCRIPTION:
SALTY CREEK_SUGAR CREEK 23.0
END DESCRIPTION:
XS GIS Cut Line= 3
      2423234.74     13671467.95      2422833.52     13668065.54
      2421445.88     13666466.99
#Sta/Elev= 30
  1734.6  277.29  1767.5  276.82  2291.9  268.74  3149.8  262.13  3233.6  259.44
  3328.5   258.7  3610.5  249.31  3751.4  248.51  4023.3  242.03  4509.6  249.12
  4637.5  247.39  4819.2   249.3  4934.5  247.82  4939.8  239.48  4941.3  238.48
  4999.9  239.48    5000  244.01  5010.1  242.47  5017.5  244.65  5060.4  246.82
  5161.8  247.76  5328.8  249.42  5373.3  247.72  5408.2  244.53  5620.4  252.76
  5776.6  258.13  5966.4  257.88  6300.8  255.89  6975.1  267.83  7277.4  268.71
#Mann= 12 ,-1 , 0
  1734.6     .07       0  1767.5     .05       0  3149.8     .07       0
  3233.6     .05       0  4819.2      .1       0  4939.8     .05       0
  4999.9      .1       0  5161.8     .12       0  5328.8     .07       0
  5373.3     .12       0  5620.4     .07       0  5966.4     .05       0
Bank Sta=4939.8,4999.9
XS Rating Curve= 0 ,0
Exp/Cntr=0.3,0.1

Type RM Length L Ch R = 1 ,59510   ,2111,2111,2111
BEGIN DESCRIPTION:
SALTY CREEK_SUGAR CREEK 22.0
END DESCRIPTION:
XS GIS Cut Line= 3
        2423625.     13670725.03        2423825.       13668725.
        2423425.     13664724.96
#Sta/Elev= 30
  2985.2  269.61  3595.7  262.59  3909.8  256.82  4080.7  255.63  4130.9  257.88
  4152.7  256.11  4211.3  257.51  4603.3  254.17  4834.4  251.25  4929.3  246.35
  4947.5  246.05  4962.4  239.01  4963.9  238.01  5022.9  239.01  5025.4  245.07
    5048  246.55  5085.7  243.27  5135.9  246.34  5286.4   246.5  5603.8  248.22
  6030.3   248.2  6100.7  246.02  6120.8  247.91  6650.9   246.4  6985.1  247.82
  7005.2  246.53  7459.9  249.89  7668.5  256.23  7929.8  260.17  9015.2  283.03
#Mann= 8 ,-1 , 0
  2985.2     .05       0  3595.7     .07       0  4152.7     .05       0
  4929.3      .1       0  4962.4     .05       0  5022.9      .1       0
  5286.4     .12       0  5603.8     .07       0
Bank Sta=4962.4,5022.9
XS Rating Curve= 0 ,0
Exp/Cntr=0.3,0.1

Type RM Length L Ch R = 1 ,57399   ,824,824,824
BEGIN DESCRIPTION:
SALTY CREEK_SUGAR CREEK 21.0
END DESCRIPTION:
XS GIS Cut Line= 3
        2423675.       13670575.        2425175.       13667875.
        2425575.       13666075.
#Sta/Elev= 30
  1911.8  267.96  2222.5  263.07  2516.6  258.97  2838.4  253.69  3045.1  253.39
  3427.8  249.06  3538.7  247.54  3649.6     247  3889.1  245.82  4010.6  246.37
  4076.8  246.35  4301.1  246.75  4619.8  247.81  4737.4  244.44  4954.7  245.74
  4970.7  244.37  4980.4  236.72  4981.9  235.72  5041.1  236.72  5041.5  244.71
  5233.5  247.21  5296.1   247.1  5377.6  246.05    5578  243.65  5594.6  241.23
  5626.6  244.33  5789.3  243.86  6085.1  256.25    6606  266.53  6844.4  274.76
#Mann= 19 ,-1 , 0
  1911.8     .05       0  2222.5     .07       0  2516.6     .05       0
  3045.1     .07       0  3427.8     .12       0  3538.7     .07       0
  3649.6     .12       0  3889.1     .07       0  4010.6     .12       0
  4076.8     .07       0  4301.1      .1       0  4619.8     .12       0
  4980.4     .05       0  5041.1     .12       0  5233.5     .12       0
  5296.1      .1       0  5377.6     .12       0  6085.1     .07       0
    6606     .05       0
Bank Sta=4980.4,5041.1
XS Rating Curve= 0 ,0
Exp/Cntr=0.3,0.1

Type RM Length L Ch R = 1 ,56575   ,1024,1024,1024
BEGIN DESCRIPTION:
SALTY CREEK_SUGAR CREEK 20.0
END DESCRIPTION:
XS GIS Cut Line= 3
      2425337.17     13671885.19      2425963.08     13668081.59
      2425754.44     13665850.78
#Sta/Elev= 30
   837.5  272.98  1482.1  261.42  1680.7  258.69  1782.5   257.5  1978.8  255.75
  2199.2     256  3401.7  252.84  3444.4  246.53  3533.5  246.56  3553.7  251.93
  3766.6  243.61  4336.8  247.27  4524.7  246.75  4859.5  244.45  4942.5  240.01
    4970  244.17  4989.9   236.5  4991.4   235.5  5050.7   236.5  5051.5  242.59
  5057.9  243.51  5157.1  246.53  5218.8   246.4  5417.6  245.16    5601  243.18
  5851.4   244.2  6248.1  257.57  6763.6  277.65    6836  278.36  6932.8  277.63
#Mann= 20 ,-1 , 0
   837.5     .05       0  1482.1    .035       0  1680.7     .05       0
  1782.5    .035       0  1978.8     .05       0  2199.2     .07       0
  4336.8     .12       0  4524.7     .12       0  4859.5     .12       0
  4989.9     .05       0  5050.7      .1       0  5057.9     .12       0
  5157.1     .07       0  5218.8     .12       0  5417.6     .12       0
    5601     .07       0  5851.4      .1       0  6248.1     .05       0
  6763.6     .07       0    6836     .05       0
Bank Sta=4989.9,5050.7
XS Rating Curve= 0 ,0
Exp/Cntr=0.3,0.1

Type RM Length L Ch R = 1 ,55551   ,2404,2404,2404
BEGIN DESCRIPTION:
SALTY CREEK_SUGAR CREEK 19.0
END DESCRIPTION:
XS GIS Cut Line= 3
      2425529.74     13671837.11      2426749.49     13668113.69
      2427439.59     13665642.14
#Sta/Elev= 30
   886.2   270.1  1790.7  255.38  1969.7  253.82  2396.5  253.01  2462.9  252.73
  2785.6  252.11  3084.7  249.68  3512.3  244.16  3824.3  241.79  4308.4  251.39
  4443.7   247.6  4618.5   244.2  4720.1  245.82  4906.8   246.2  4954.2  241.89
    4958  236.34  4959.5  235.34  5018.8  236.34    5021  243.04  5061.9  243.91
  5462.7  244.75  5735.5  243.38  5807.8  243.28  6164.8   243.7  6405.4  251.05
  6633.5   256.8  7004.7  271.82  7033.6  269.09    7074  271.98  7370.4  283.21
#Mann= 20 ,-1 , 0
   886.2     .05       0  1790.7     .07       0  1969.7     .07       0
  2396.5     .12       0  2462.9     .07       0  2785.6     .07       0
  3084.7     .05       0  3512.3     .07       0  4443.7     .12       0
  4618.5     .07       0  4720.1     .12       0    4958     .05       0
  5018.8      .1       0  5462.7     .07       0  5735.5     .12       0
  5807.8     .07       0  6164.8     .07       0  6405.4    .035       0
  6633.5     .07       0    7074     .05       0
Bank Sta=4958,5018.8
XS Rating Curve= 0 ,0
Exp/Cntr=0.3,0.1

Type RM Length L Ch R = 1 ,53147   ,2135,2135,2135
BEGIN DESCRIPTION:
SALTY CREEK_SUGAR CREEK 18.0
END DESCRIPTION:
XS GIS Cut Line= 3
      2425914.95     13672077.77        2428525.       13666925.
      2428803.35      13665948.5
#Sta/Elev= 30
  -776.2   267.2     9.6  256.12      19  255.99   104.9  254.86  1376.3  248.35
  1717.3  250.42  2133.8  243.66  3200.5  241.46  3381.1   242.4  3462.9  242.78
  3497.7   242.9  3609.9  237.94  3959.3  244.92  4284.4  244.22  4323.3  238.66
  4383.4  243.99  4585.9  244.02  4617.3  244.29  4791.5  244.38  4955.1  240.25
  4955.5  235.27    4957  234.27  5016.5  235.27  5016.8  240.84  5060.3  243.91
  5089.7  251.49  5222.9  256.27  5377.2   260.3  5522.2  263.92  6015.3  270.75
#Mann= 20 ,-1 , 0
  -776.2     .05       0     9.6     .07       0      19     .12       0
   104.9     .07       0  1376.3     .05       0  2133.8     .07       0
  3200.5     .12       0  3381.1     .07       0  3462.9     .12       0
  3497.7     .07       0  3959.3     .12       0  4585.9    .035       0
  4617.3     .12       0  4791.5      .1       0  4955.5     .05       0
  5016.5      .1       0  5060.3     .12       0  5222.9     .05       0
  5377.2     .07       0  5522.2     .05       0
Bank Sta=4955.5,5016.5
XS Rating Curve= 0 ,0
Exp/Cntr=0.3,0.1

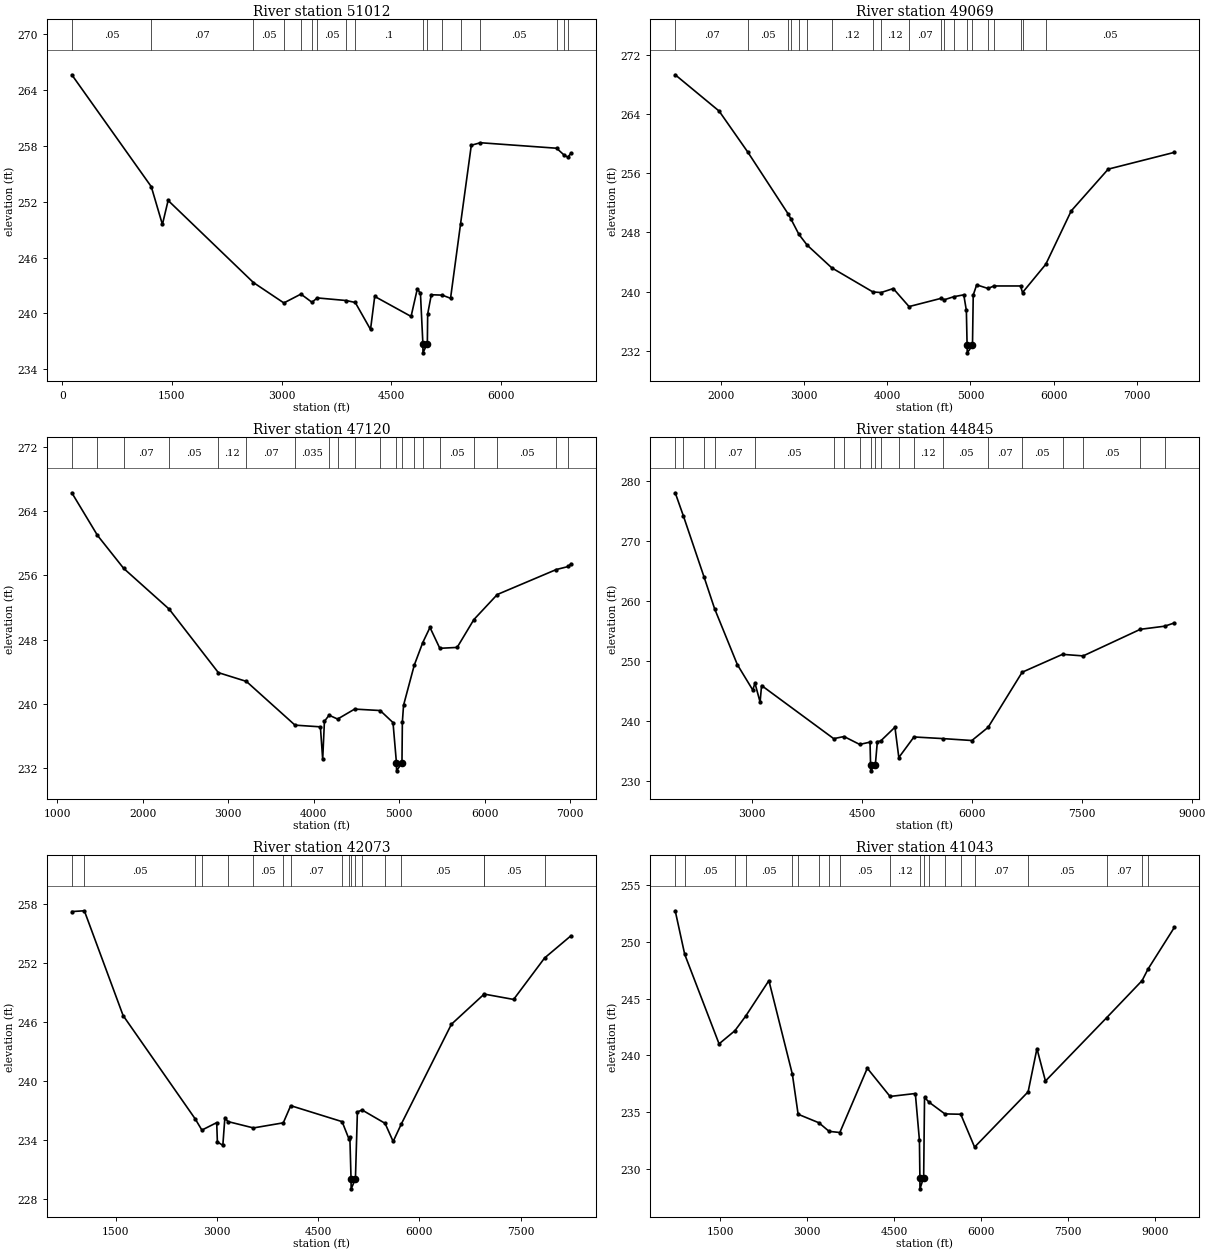
Type RM Length L Ch R = 1 ,51012   ,1943,1943,1943
BEGIN DESCRIPTION:
E20580
END DESCRIPTION:
XS GIS Cut Line= 2
      2426219.87     13672174.09      2430553.13     13666893.94
#Sta/Elev= 30
   129.9  265.63  1217.5  253.61  1369.8  249.55    1448  252.13  2615.5  243.31
  3031.9  241.12  3265.3  242.07  3416.8  241.19  3488.1  241.66  3884.5  241.38
  4008.9  241.17  4217.9  238.27  4275.3  241.82  4772.9  239.67    4858  242.63
  4901.1  242.15  4934.4  236.76  4935.9  235.76  4995.4  236.76  5000.1  239.93
  5049.6     242  5199.4  241.96    5313  241.62    5450  249.61  5597.1  258.06
  5721.5  258.33  6764.8  257.74  6871.9  256.97  6919.3  256.78  6960.5   257.2
#Mann= 17 ,-1 , 0
   129.9     .05       0  1217.5     .07       0  2615.5     .05       0
  3031.9     .07       0  3265.3     .05       0  3416.8     .07       0
  3488.1     .05       0  3884.5     .07       0  4008.9      .1       0
  4934.4     .05       0  4995.4      .1       0  5199.4     .12       0
    5450     .07       0  5721.5     .05       0  6764.8    .035       0
  6871.9     .05       0  6919.3     .07       0
Bank Sta=4934.4,4995.4
XS Rating Curve= 0 ,0
Exp/Cntr=0.3,0.1

Type RM Length L Ch R = 1 ,49069   ,1949,1949,1949
BEGIN DESCRIPTION:
E20579
END DESCRIPTION:
XS GIS Cut Line= 3
      2430248.18     13673361.74      2430055.59     13670103.77
       2430745.7     13667455.67
#Sta/Elev= 30
  1450.3  269.34    1978  264.43  2322.7  258.88  2806.1  250.54  2838.5  249.89
  2937.4  247.74  3036.2  246.29  3332.7  243.21  3826.8  239.95  3925.6  239.87
  4071.6  240.41  4261.4  237.97  4648.5  239.09    4684  238.89  4800.2  239.31
  4919.4  239.56  4950.4  237.44  4959.3  232.71  4960.8  231.71    5024  232.71
    5033  239.54  5074.4  240.91  5210.6  240.42  5281.6  240.76  5601.2  240.76
  5625.5  239.87  5904.9  243.69  6211.1  250.92  6655.5  256.57  7450.5  258.84
#Mann= 20 ,-1 , 0
  1450.3     .07       0  2322.7     .05       0  2806.1     .07       0
  2838.5    .035       0  2937.4     .07       0  3036.2     .05       0
  3332.7     .12       0  3826.8     .07       0  3925.6     .12       0
  4261.4     .07       0  4648.5      .1       0    4684     .07       0
  4800.2      .1       0  4959.3     .05       0    5024      .1       0
  5210.6     .12       0  5281.6      .1       0  5601.2     .12       0
  5625.5     .07       0  5904.9     .05       0
Bank Sta=4959.3,5024
XS Rating Curve= 0 ,0
Exp/Cntr=0.3,0.1

Type RM Length L Ch R = 1 ,47120   ,2275,2275,2275
BEGIN DESCRIPTION:
E20578
END DESCRIPTION:
XS GIS Cut Line= 3
      2430745.71     13673490.09      2431708.64     13668434.67
      2431371.62     13667824.81
#Sta/Elev= 30
  1167.9  266.29  1468.6  260.98  1775.3  256.87  2307.6   251.8  2883.5  243.89
  3211.2   242.8  3780.9  237.35  4078.1  237.14  4104.9  233.09  4125.2  237.82
  4179.4  238.59  4279.5  238.11  4478.9  239.35    4778  239.17  4928.1  237.67
  4968.3  232.66  4969.8  231.66    5033  232.66  5037.6  237.74  5051.6  239.83
  5176.9  244.82  5276.6  247.64  5360.8  249.52  5476.1  246.92  5678.9  247.03
  5874.9   250.5  6148.9  253.62  6839.6  256.73    6981  257.11    7011  257.45
#Mann= 20 ,-1 , 0
  1167.9     .07       0  1468.6     .12       0  1775.3     .07       0
  2307.6     .05       0  2883.5     .12       0  3211.2     .07       0
  3780.9    .035       0  4179.4      .1       0  4279.5    .035       0
  4478.9     .12       0    4778    .035       0  4968.3     .05       0
    5033     .12       0  5176.9    .035       0  5276.6     .05       0
  5476.1     .05       0  5874.9     .05       0  6148.9     .05       0
  6839.6    .035       0    6981     .07       0
Bank Sta=4968.3,5033
XS Rating Curve= 0 ,0
Exp/Cntr=0.3,0.1

Type RM Length L Ch R = 1 ,44845   ,2772,2772,2772
BEGIN DESCRIPTION:
E20577
END DESCRIPTION:
XS GIS Cut Line= 3
      2432495.05      13673923.4      2432575.29     13668835.89
      2431388.83     13667585.29
#Sta/Elev= 30
  1951.6  277.98  2062.7  274.15  2345.4  263.98    2489  258.72  2800.1  249.41
  3010.1   245.2  3039.9  246.35  3110.1  243.19  3130.1  245.95  4114.8  237.12
  4255.7  237.47  4469.3  236.16  4610.3  236.54  4617.9  232.77  4619.4  231.77
  4682.8  232.77  4710.3  236.62  4754.5  236.72  4950.4  239.02  5003.4  233.98
    5210   237.4  5603.8  237.13  6000.5  236.81  6222.1     239  6686.8  248.16
  7237.3  251.13  7519.3  250.87  8299.4  255.29  8632.9  255.81  8763.6  256.35
#Mann= 20 ,-1 , 0
  1951.6     .05       0  2062.7     .07       0  2345.4    .035       0
    2489     .07       0  3039.9     .05       0  4114.8     .07       0
  4255.7     .12       0  4469.3      .1       0  4617.9     .05       0
  4682.8      .1       0  4754.5     .12       0  5003.4      .1       0
    5210     .12       0  5603.8     .05       0  6222.1     .07       0
  6686.8     .05       0  7237.3     .07       0  7519.3     .05       0
  8299.4     .07       0  8632.9     .07       0
Bank Sta=4617.9,4682.8
XS Rating Curve= 0 ,0
Exp/Cntr=0.3,0.1

Type RM Length L Ch R = 1 ,42073   ,1030,1030,1030
BEGIN DESCRIPTION:
E20576
END DESCRIPTION:
XS GIS Cut Line= 4
      2433554.29     13673891.34      2434035.76     13670456.85
      2434003.66     13669509.95      2431613.35     13667729.25
#Sta/Elev= 30
     850  257.26  1035.7  257.34  1610.1  246.66  2678.5  236.12  2777.6  234.98
  2997.1  235.74  3007.2  233.77    3088  233.43  3118.3  236.25  3162.6  235.85
  3541.4   235.2  3983.8  235.72  4093.8  237.47  4855.5  235.84  4954.1  234.12
  4970.3  234.25  4987.9  229.99  4989.4  228.99  5052.8  229.99  5081.9  236.83
  5151.4  237.03  5491.6  235.67  5611.9  233.82  5734.2  235.62  6475.1  245.77
  6953.3   248.8  6957.4  248.85  7396.8   248.3  7856.4  252.53  8246.2  254.79
#Mann= 18 ,-1 , 0
     850    .035       0  1035.7     .05       0  2678.5    .035       0
  2777.6      .1       0  3162.6     .07       0  3541.4     .05       0
  3983.8    .035       0  4093.8     .07       0  4855.5     .12       0
  4954.1      .1       0  4987.9     .05       0  5052.8     .07       0
  5151.4     .05       0  5491.6     .07       0  5734.2     .05       0
  6953.3    .035       0  6957.4     .05       0  7856.4     .07       0
Bank Sta=4987.9,5052.8
XS Rating Curve= 0 ,0
Exp/Cntr=0.3,0.1

Type RM Length L Ch R = 1 ,41043   ,3084,3084,3084
BEGIN DESCRIPTION:
E20575
END DESCRIPTION:
XS GIS Cut Line= 4
       2434276.5     13674003.65      2434934.51     13669509.95
      2434292.54     13668242.08      2431740.71     13667535.91
#Sta/Elev= 30
     726  252.75   889.7  248.91  1482.6  241.01  1755.6  242.17    1942  243.46
  2342.2  246.59  2747.1  238.33  2846.2   234.8  3204.1  234.05    3381  233.29
  3565.9  233.19  4039.6  238.86  4432.2  236.37  4868.4  236.63  4939.1   232.5
  4947.1  229.22  4948.6  228.22    5012  229.22  5027.2  236.28  5108.5  235.85
  5378.8  234.83  5651.6   234.8  5890.7   231.9  6814.4  236.78  6966.4  240.59
  7112.9  237.73  8167.4  243.31  8780.4  246.59  8881.7   247.6  9336.5  251.28
#Mann= 20 ,-1 , 0
     726     .07       0   889.7     .05       0  1755.6     .07       0
    1942     .05       0  2747.1    .035       0  2846.2     .07       0
  3204.1    .035       0    3381     .07       0  3565.9     .05       0
  4432.2     .12       0  4947.1     .05       0    5012      .1       0
  5108.5     .07       0  5378.8    .035       0  5651.6     .05       0
  5890.7     .07       0  6814.4     .05       0  8167.4     .07       0
  8780.4    .035       0  8881.7     .07       0
Bank Sta=4947.1,5012
XS Rating Curve= 0 ,0
Exp/Cntr=0.3,0.1

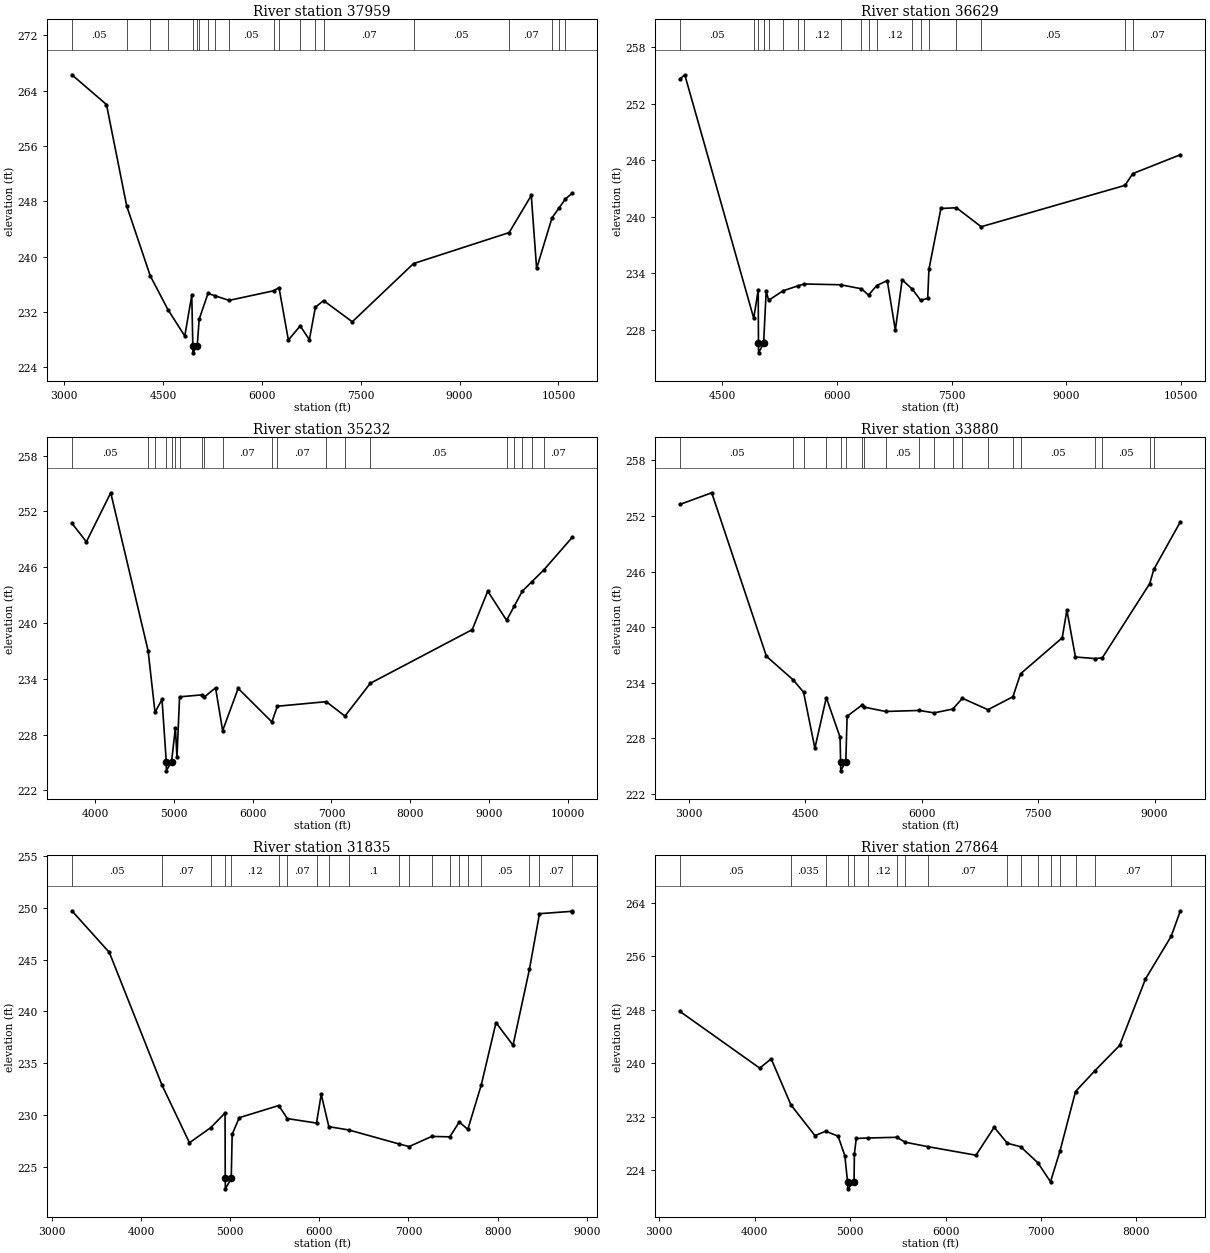
Type RM Length L Ch R = 1 ,37959   ,1330,1330,1330
BEGIN DESCRIPTION:
E20574
END DESCRIPTION:
XS GIS Cut Line= 4
       2437807.3     13671804.99      2436090.04     13670119.82
      2434324.64     13668145.78      2431885.85     13667439.82
#Sta/Elev= 30
  3118.4   266.3  3643.3     262    3950  247.34  4307.5  237.24  4575.2  232.36
  4831.2  228.54  4937.4  234.44  4953.2  227.11  4954.7  226.11  5020.4  227.11
  5049.4  230.97  5183.5   234.7  5296.6  234.34  5502.5  233.69  6179.4  235.08
  6260.4  235.54  6402.8  227.96  6582.2     230  6721.3  228.01  6812.5  232.71
    6937  233.66  7372.5   230.6  8301.2  239.01  9751.8  243.49 10087.8  248.86
 10168.7  238.31 10402.5  245.63 10504.1  246.99 10605.7  248.35 10711.6  249.21
#Mann= 20 ,-1 , 0
  3118.4     .05       0    3950     .05       0  4307.5     .05       0
  4575.2     .07       0  4953.2     .05       0  5020.4     .07       0
  5049.4     .07       0  5183.5     .07       0  5296.6     .12       0
  5502.5     .05       0  6179.4    .035       0  6260.4     .07       0
  6582.2     .07       0  6812.5     .05       0    6937     .07       0
  8301.2     .05       0  9751.8     .07       0 10402.5    .035       0
 10504.1    .035       0 10605.7     .07       0
Bank Sta=4953.2,5020.4
XS Rating Curve= 0 ,0
Exp/Cntr=0.3,0.1

Type RM Length L Ch R = 1 ,36629   ,1397,1397,1397
BEGIN DESCRIPTION:
E20573
END DESCRIPTION:
XS GIS Cut Line= 4
      2438112.19     13669943.26      2436683.85     13669221.07
      2434308.59     13668017.39      2432109.97     13667407.55
#Sta/Elev= 30
  3947.9  254.63    4012  255.09  4913.7   229.2  4972.3  232.21  4975.7  226.52
  4977.2  225.52  5042.9  226.52  5044.1  226.77  5076.5  232.07    5109  231.11
  5295.3  232.11  5486.6  232.63  5573.7  232.84  6049.7  232.76  6322.8  232.33
    6415  231.66  6521.9  232.68  6659.8   233.2  6765.5  227.93  6854.6  233.29
  6987.2  232.29    7096  231.11  7188.7  231.31  7204.7  234.41  7361.3  240.87
  7563.9  240.95  7887.9  238.93  9768.3  243.33  9870.7  244.58 10492.9  246.59
#Mann= 20 ,-1 , 0
  3947.9     .05       0  4913.7     .07       0  4975.7     .05       0
  5042.9     .07       0  5044.1     .12       0    5109     .07       0
  5295.3     .12       0  5486.6     .07       0  5573.7     .12       0
  6049.7     .07       0  6322.8     .12       0    6415     .07       0
  6521.9     .12       0  6987.2     .12       0    7096     .07       0
  7204.7     .07       0  7563.9     .12       0  7887.9     .05       0
  9768.3    .035       0  9870.7     .07       0
Bank Sta=4975.7,5042.9
XS Rating Curve= 0 ,0
Exp/Cntr=0.3,0.1

Type RM Length L Ch R = 1 ,35232   ,1352,1352,1352
BEGIN DESCRIPTION:
E20572
END DESCRIPTION:
XS GIS Cut Line= 3
      2438417.16     13668932.19      2436956.69     13668145.78
      2432350.59     13667247.03
#Sta/Elev= 30
  3706.1  250.73  3890.3  248.74  4199.2  254.01  4673.1  237.03  4761.1   230.4
  4849.9  231.78  4903.8   225.1  4905.3   224.1  4971.1   225.1  5019.7  228.74
  5039.6  225.57  5072.8  232.06  5354.3  232.27  5386.9  232.04  5529.6  233.03
  5619.3  228.42  5816.4  232.97    6244  229.36  6313.8  231.05  6933.8  231.54
  7171.5  229.99  7493.8  233.52    8787  239.29  8983.5  243.43  9222.6  240.29
  9322.3  241.85    9422  243.43  9542.1  244.43  9697.2  245.73 10057.8  249.24
#Mann= 20 ,-1 , 0
  3706.1     .05       0  4673.1     .07       0  4761.1     .12       0
  4903.8     .05       0  4971.1     .12       0  5019.7     .07       0
  5072.8     .12       0  5354.3     .07       0  5386.9     .12       0
  5619.3     .07       0    6244     .12       0  6313.8     .07       0
  6933.8      .1       0  7171.5     .05       0  7493.8     .05       0
  9222.6     .07       0  9322.3    .035       0    9422     .07       0
  9542.1    .035       0  9697.2     .07       0
Bank Sta=4903.8,4971.1
XS Rating Curve= 0 ,0
Exp/Cntr=0.3,0.1

Type RM Length L Ch R = 1 ,33880   ,2045,2045,2045
BEGIN DESCRIPTION:
E20571
END DESCRIPTION:
XS GIS Cut Line= 3
      2438706.05     13668226.04      2437229.52     13667182.84
      2432608.67     13666781.72
#Sta/Elev= 30
  2885.9  253.24  3296.2   254.5  4000.4  236.85  4347.7  234.28    4479  232.97
  4624.5  226.92  4771.9  232.38  4949.2  228.11  4955.7  225.48  4957.2  224.48
    5023  225.48  5039.6  230.38  5233.1  231.59  5254.3  231.37  5534.2  230.89
  5969.4     231    6161  230.74  6400.4  231.15  6524.5  232.31  6853.7  231.08
  7175.1  232.48  7273.6  234.96    7810  238.84  7870.2  241.83  7980.6  236.77
  8235.8   236.6    8326  236.68  8937.4   244.7  8990.3  246.24    9332  251.37
#Mann= 20 ,-1 , 0
  2885.9     .05       0  4347.7     .07       0    4479     .12       0
  4771.9     .07       0  4955.7     .05       0    5023     .07       0
  5233.1     .05       0  5254.3     .07       0  5534.2     .05       0
  5969.4      .1       0    6161     .07       0  6400.4     .12       0
  6524.5    .033       0  6853.7     .05       0  7175.1    .035       0
  7273.6     .05       0  8235.8    .035       0    8326     .05       0
  8937.4     .07       0  8990.3     .05       0
Bank Sta=4955.7,5023
XS Rating Curve= 0 ,0
Exp/Cntr=0.3,0.1

Type RM Length L Ch R = 1 ,31835   ,3971,3971,3971
BEGIN DESCRIPTION:
SALTY CREEK_SUGAR CREEK 10.0
END DESCRIPTION:
XS GIS Cut Line= 3
      2438962.81     13667070.49      2437727.04     13665963.11
      2434324.65     13663940.94
#Sta/Elev= 30
  3222.2  249.71  3642.4  245.69    4233  232.89  4541.7  227.32  4778.4  228.76
  4941.3  230.19  4943.3  223.87  4944.8  222.87  5010.6  223.87  5021.2  228.14
    5101  229.74  5543.6  230.91  5640.4  229.65  5967.6  229.22  6020.5  231.99
  6106.4  228.87  6331.5  228.55  6894.4   227.2  7006.9  226.95  7260.8  227.93
  7463.4  227.89  7569.7  229.32  7665.9  228.61    7816  232.88  7982.1  238.91
    8173  236.73  8357.7  244.08  8470.2  249.43  8837.3  249.66  8839.5  249.64
#Mann= 20 ,-1 , 0
  3222.2     .05       0    4233     .07       0  4778.4     .12       0
  4943.3     .05       0  5010.6     .12       0  5543.6      .1       0
  5640.4     .07       0  5967.6     .12       0  6106.4      .1       0
  6331.5      .1       0  6894.4    .033       0  7006.9     .12       0
  7260.8    .033       0  7463.4     .07       0  7569.7    .033       0
  7665.9     .05       0    7816     .05       0  8357.7    .035       0
  8470.2     .07       0  8837.3     .05       0
Bank Sta=4943.3,5010.6
XS Rating Curve= 0 ,0
Exp/Cntr=0.3,0.1

Type RM Length L Ch R = 1 ,27864   ,4462,4462,4462
BEGIN DESCRIPTION:
SALTY CREEK_SUGAR CREEK 9.0
END DESCRIPTION:
XS GIS Cut Line= 3
      2439010.97     13666861.87      2439010.97     13665577.93
        2438690.       13661630.
#Sta/Elev= 30
    3216  247.77  4052.9  239.28  4172.9  240.67  4379.7  233.78  4631.8  229.18
  4743.8  229.84  4874.1   229.1  4944.3  226.19  4973.8  222.22  4975.3  221.22
  5041.2  222.22  5044.7  226.47  5064.7  228.76  5192.3  228.83  5488.4  228.93
  5578.8  228.19  5815.7  227.53  6318.9  226.25  6509.5  230.43  6646.8  228.05
  6787.2  227.51  6968.4  225.11  7099.8  222.27  7198.7  226.85  7362.2  235.78
  7562.6  238.86  7823.8  242.67  8095.2  252.62  8364.6  259.01  8460.9  262.82
#Mann= 17 ,-1 , 0
    3216     .05       0  4379.7    .035       0  4743.8      .1       0
  4973.8     .05       0  5041.2      .1       0  5192.3     .12       0
  5488.4     .07       0  5578.8     .12       0  5815.7     .07       0
  6646.8     .12       0  6787.2    .035       0  6968.4     .07       0
  7099.8      .1       0  7198.7     .07       0  7362.2     .05       0
  7562.6     .07       0  8364.6     .05       0
Bank Sta=4973.8,5041.2
XS Rating Curve= 0 ,0
Exp/Cntr=0.3,0.1