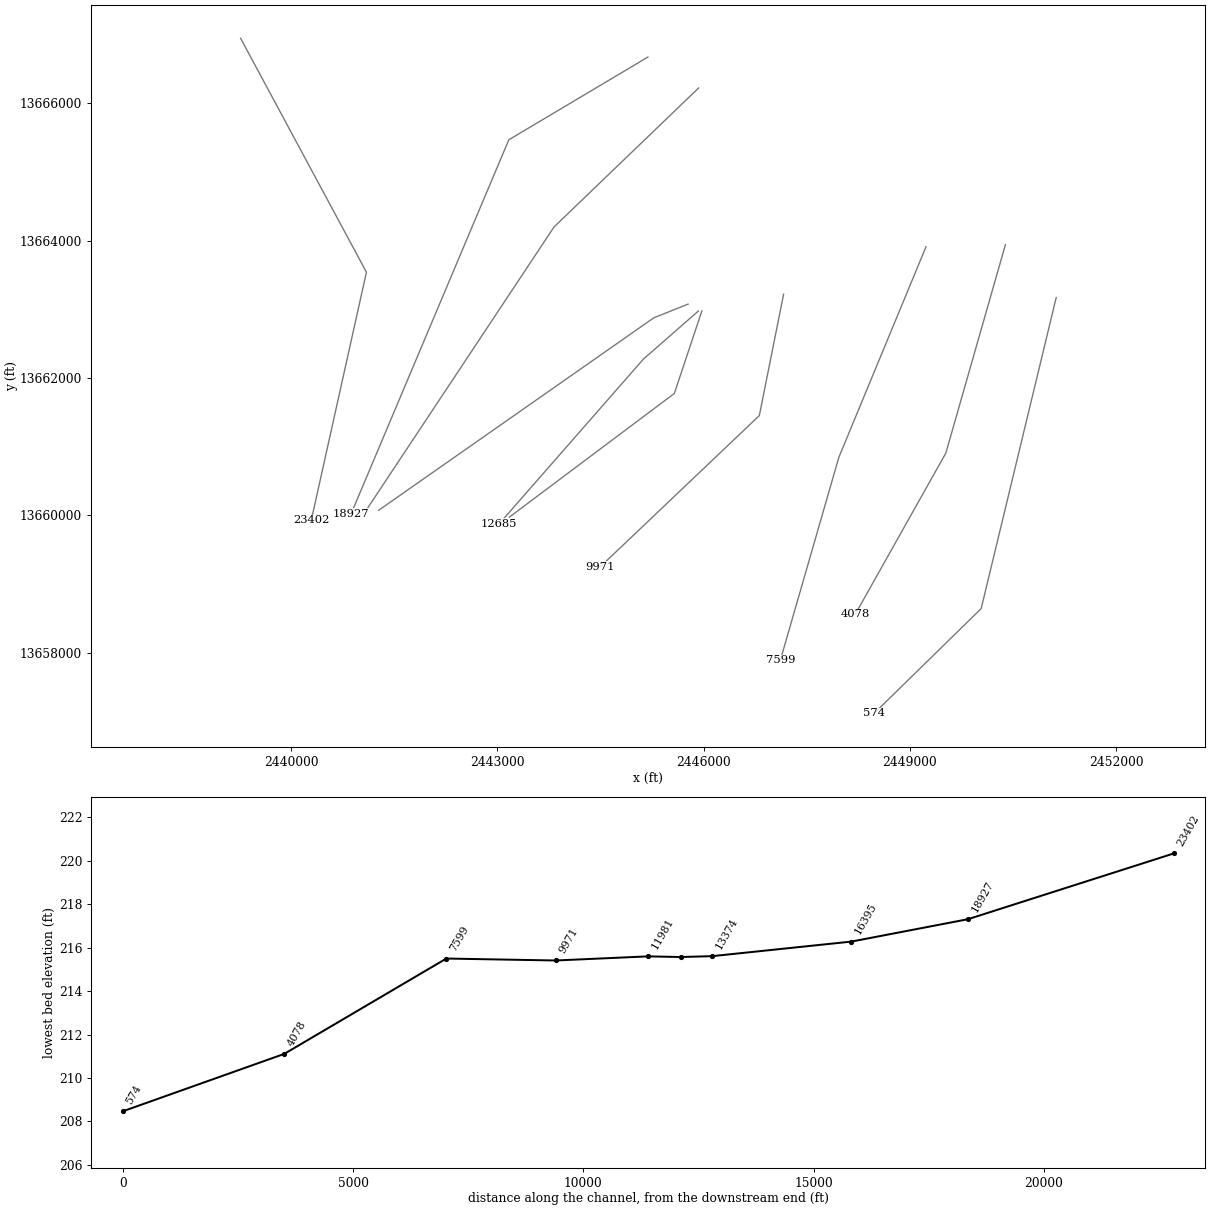
HEC-RAS study SALTY CREEK_SUGAR CREEK.prj: SALTY CREEK_SUGAR CREEK Base Level Engineering

--- SALTY CREEK_SUGAR CREEK.g01 (geometry) --- (continued)

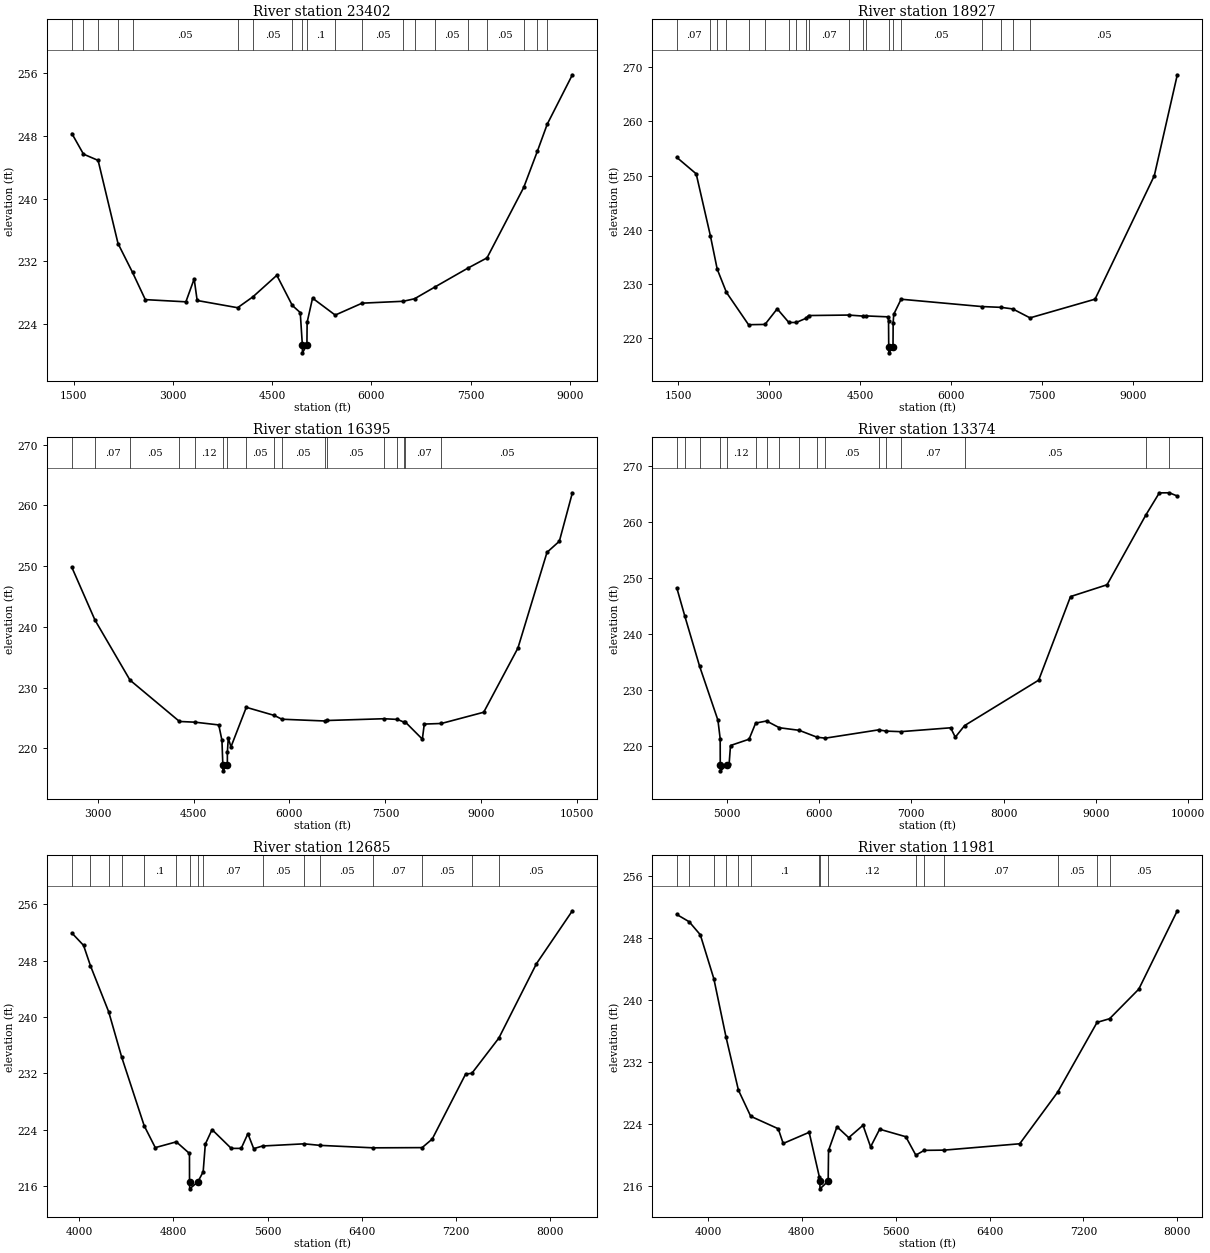
Type RM Length L Ch R = 1 ,23402   ,4475,4475,4475
BEGIN DESCRIPTION:
E20569
END DESCRIPTION:
XS GIS Cut Line= 3
      2439267.77     13666942.07      2441097.34      13663539.7
      2440295.05     13659929.36
#Sta/Elev= 30
  1475.3  248.28  1650.5  245.66  1871.6  244.86  2172.7  234.26  2392.2  230.58
  2584.7  227.12  3197.8  226.84  3322.7  229.76  3368.1  227.01  3979.1  226.09
  4210.8  227.48  4571.6  230.22  4805.4  226.38  4925.5  225.47  4957.3  221.34
  4958.8  220.34  5026.2  221.34  5029.4  224.23  5111.4  227.31  5453.6  225.15
  5860.3  226.67  6481.5  226.91  6652.4  227.23  6962.1  228.74  7461.7  231.15
  7747.2  232.44  8301.5  241.41  8508.4  246.04  8656.6  249.47  9036.8  255.77
#Mann= 20 ,-1 , 0
  1475.3     .05       0  1650.5     .07       0  1871.6     .05       0
  2172.7    .035       0  2392.2     .05       0  3979.1     .07       0
  4210.8     .05       0  4805.4     .07       0  4957.3     .05       0
  5026.2      .1       0  5453.6     .12       0  5860.3     .05       0
  6481.5     .07       0  6652.4     .05       0  6962.1     .05       0
  7461.7     .05       0  7747.2     .05       0  8301.5     .05       0
  8508.4     .07       0  8656.6     .05       0
Bank Sta=4957.3,5026.2
XS Rating Curve= 0 ,0
Exp/Cntr=0.3,0.1

Type RM Length L Ch R = 1 ,18927   ,2532,2532,2532
BEGIN DESCRIPTION:
SALTY CREEK_SUGAR CREEK 7.0
END DESCRIPTION:
XS GIS Cut Line= 3
      2445189.89     13666669.29      2443167.67     13665465.59
      2440874.99     13660024.98
#Sta/Elev= 30
  1476.3  253.36  1796.2  250.33  2030.3  238.91  2142.9  232.75  2295.2  228.46
  2659.9   222.5  2931.2  222.55  3132.7  225.43  3325.1  222.91  3447.6  222.91
  3606.8  223.68  3649.9  224.19  4311.9  224.28  4546.6  224.09    4599  224.12
  4960.5  223.95  4969.7  223.18  4972.7  218.31  4974.2  217.31  5043.2  218.31
  5045.7  222.87  5055.4  224.42  5176.7   227.2  6504.8  225.85  6825.8   225.7
  7018.5  225.41  7303.7  223.76  8376.7  227.21  9353.8  249.97  9733.6   268.6
#Mann= 20 ,-1 , 0
  1476.3     .07       0  2030.3    .035       0  2142.9     .05       0
  2295.2     .07       0  2659.9      .1       0  2931.2     .07       0
  3325.1      .1       0  3447.6     .07       0  3606.8    .035       0
  3649.9     .07       0  4311.9     .12       0  4546.6     .07       0
    4599      .1       0  4972.7     .05       0  5043.2      .1       0
  5176.7     .05       0  6504.8     .07       0  6825.8     .05       0
  7018.5    .035       0  7303.7     .05       0
Bank Sta=4972.7,5043.2
XS Rating Curve= 0 ,0
Exp/Cntr=0.3,0.1

Type RM Length L Ch R = 1 ,16395   ,3021,3021,3021
BEGIN DESCRIPTION:
E20570
END DESCRIPTION:
XS GIS Cut Line= 3
       2445928.1     13666219.89      2443825.68     13664197.71
      2441113.38     13660105.18
#Sta/Elev= 30
  2597.1  249.78  2958.1  241.11    3506  231.22  4279.8  224.41  4524.8  224.29
  4894.1  223.84  4943.8  221.31  4957.7  217.28  4959.2  216.28  5028.6  217.28
  5028.7  219.31  5042.9  221.68    5085  220.23  5324.7  226.74  5760.8  225.41
  5881.2  224.78  6551.6  224.49  6589.6  224.57  7474.2  224.86  7687.9  224.75
    7792  224.29  7813.8  224.29  8077.8   221.5  8107.9  223.98  8375.8  224.08
  9037.3  225.93  9572.3   236.5   10027  252.26 10220.2  254.09 10423.9  262.07
#Mann= 17 ,-1 , 0
  2597.1    .035       0  2958.1     .07       0    3506     .05       0
  4279.8     .07       0  4524.8     .12       0  4957.7     .05       0
  5028.6     .12       0  5324.7     .05       0  5760.8    .035       0
  5881.2     .05       0  6551.6     .07       0  6589.6     .05       0
  7474.2     .07       0  7687.9     .05       0    7792     .12       0
  7813.8     .07       0  8375.8     .05       0
Bank Sta=4957.7,5028.6
XS Rating Curve= 0 ,0
Exp/Cntr=0.3,0.1

Type RM Length L Ch R = 1 ,13374   ,689,689,689
BEGIN DESCRIPTION:
SALTY CREEK_SUGAR CREEK 6.0
END DESCRIPTION:
XS GIS Cut Line= 3
      2445775.02     13663075.01        2445275.       13662875.
      2441274.97     13660074.98
#Sta/Elev= 30
  4461.1  248.25  4547.1  243.26  4707.9  234.28  4906.7  224.64    4931  221.33
  4931.8  216.61  4933.3  215.61  5002.8  216.61    5028  216.88  5042.8  220.13
  5243.8  221.25  5315.4  224.13  5433.2   224.5    5572   223.3  5786.5  222.84
  5980.2  221.61  6069.6  221.44  6646.5  222.92  6728.6   222.7  6885.8   222.6
  7427.4  223.29  7477.6  221.61  7578.1  223.68  8380.9  231.79  8725.7   246.7
  9121.5  248.81  9539.3  261.19  9687.4   265.2    9796  265.22  9882.3  264.64
#Mann= 17 ,-1 , 0
  4461.1     .05       0  4547.1     .07       0  4707.9     .12       0
  4931.8     .05       0  5002.8     .12       0  5315.4    .035       0
  5433.2     .05       0    5572     .07       0  5786.5     .05       0
  5980.2     .07       0  6069.6     .05       0  6646.5     .07       0
  6728.6     .05       0  6885.8     .07       0  7578.1     .05       0
  9539.3     .07       0    9796     .05       0
Bank Sta=4931.8,5002.8
XS Rating Curve= 0 ,0
Exp/Cntr=0.3,0.1

Type RM Length L Ch R = 1 ,12685   ,704,704,704
BEGIN DESCRIPTION:
SALTY CREEK_SUGAR CREEK 5.0
END DESCRIPTION:
XS GIS Cut Line= 3
      2445924.98     13662974.99        2445125.       13662275.
      2443025.02     13659875.03
#Sta/Elev= 30
    3937  251.94  4036.2  250.18  4095.1  247.27  4249.7  240.74  4359.9  234.31
  4551.3  224.54  4645.5  221.43  4824.2  222.25  4935.9   220.6  4936.5  216.57
    4938  215.57  5007.5  216.57  5052.3  217.99  5070.7  221.93  5127.7  223.99
  5290.9  221.32  5375.4  221.32  5432.3  223.41  5481.7  221.28  5556.8  221.66
  5910.4  221.97  6045.1  221.75  6496.5   221.4  6912.6  221.43  6998.4  222.65
  7282.2  231.89  7334.8  231.99  7564.2     237  7883.9  247.58    8189   255.1
#Mann= 16 ,-1 , 0
    3937     .05       0  4095.1     .07       0  4249.7     .05       0
  4359.9     .12       0  4551.3      .1       0  4824.2     .12       0
  4936.5     .05       0  5007.5     .12       0  5052.3     .07       0
  5556.8     .05       0  5910.4    .035       0  6045.1     .05       0
  6496.5     .07       0  6912.6     .05       0  7334.8     .07       0
  7564.2     .05       0
Bank Sta=4936.5,5007.5
XS Rating Curve= 0 ,0
Exp/Cntr=0.3,0.1

Type RM Length L Ch R = 1 ,11981   ,2010,2010,2010
BEGIN DESCRIPTION:
SALTY CREEK_SUGAR CREEK 4.0
END DESCRIPTION:
XS GIS Cut Line= 3
      2445975.01     13662975.04        2445575.       13661775.
      2443174.97     13659974.97
#Sta/Elev= 30
  3734.7  251.03  3840.4  250.09    3935  248.41  4050.1  242.75  4154.9  235.15
  4259.7  228.35  4364.5  224.97  4599.1  223.36  4641.3  221.46  4862.6   222.9
  4948.7  217.19  4953.6   216.6  4955.1   215.6  5024.6   216.6  5027.8  220.56
  5099.7  223.62  5199.7  222.21  5321.5  223.81  5386.1  221.02  5463.2   223.3
  5686.1  222.33  5771.6  219.95  5842.9  220.57  6013.6   220.6  6656.9  221.42
  6979.1  228.06  7316.1   237.1  7422.8  237.57  7671.5  241.39  7999.7  251.51
#Mann= 15 ,-1 , 0
  3734.7     .05       0  3840.4     .07       0  4050.1     .05       0
  4154.9     .07       0  4259.7     .12       0  4364.5      .1       0
  4948.7     .12       0  4953.6     .05       0  5024.6     .12       0
  5771.6     .07       0  5842.9     .05       0  6013.6     .07       0
  6979.1     .05       0  7316.1     .07       0  7422.8     .05       0
Bank Sta=4953.6,5024.6
XS Rating Curve= 0 ,0
Exp/Cntr=0.3,0.1

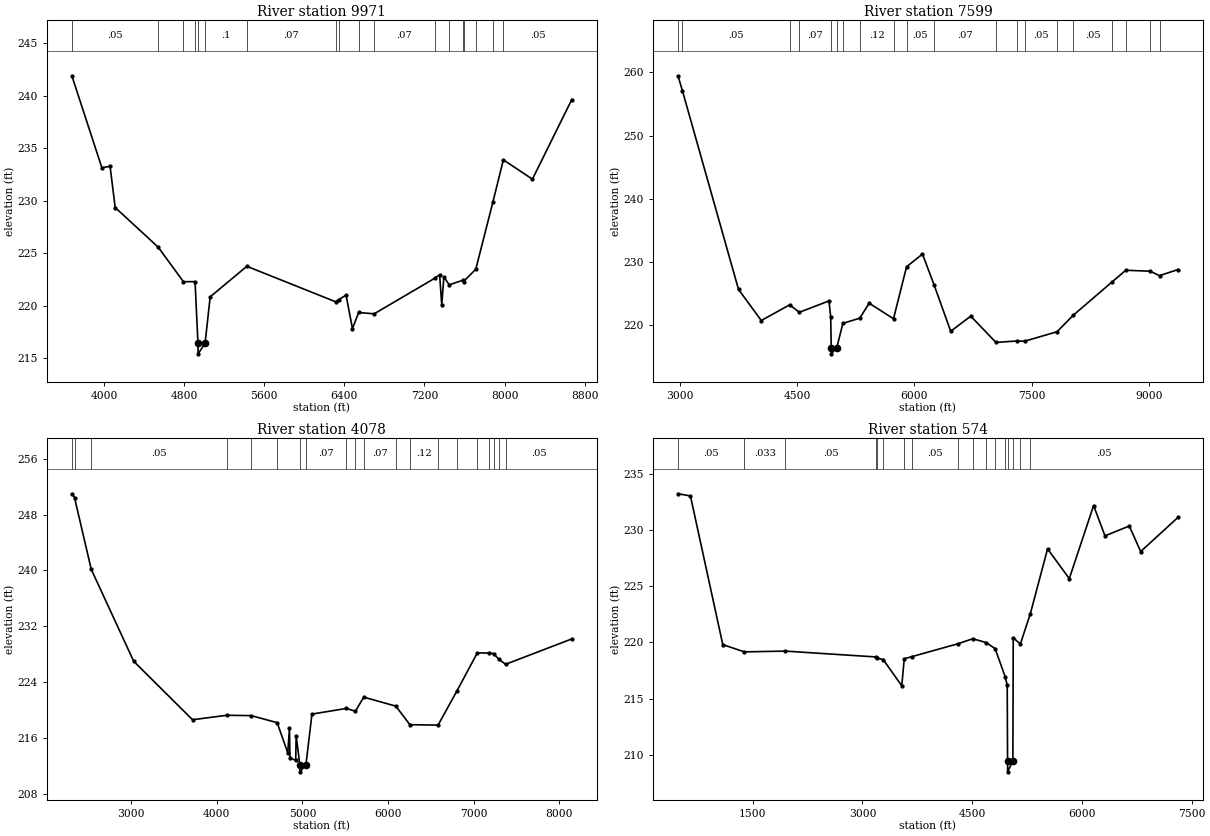
Type RM Length L Ch R = 1 ,9971    ,2372,2372,2372
BEGIN DESCRIPTION:
E20568
END DESCRIPTION:
XS GIS Cut Line= 3
      2447163.89     13663218.75      2446810.81     13661453.33
      2444499.87     13659254.72
#Sta/Elev= 30
  3680.3   241.9  3979.9  233.14  4061.8  233.28  4112.8  229.35  4541.3  225.58
  4794.4  222.28    4910  222.29    4939  216.41  4940.5  215.41  5010.1  216.41
  5060.9  220.84    5427  223.75  6313.1  220.37  6342.7  220.57  6417.2     221
  6481.1  217.82  6543.2  219.35  6697.2  219.22  7302.4  222.61  7351.1  222.95
  7372.2  220.07  7393.5  222.73  7447.6  221.99  7579.8  222.41  7589.8   222.3
    7712  223.47    7882  229.84  7987.1  233.89  8277.4  232.05  8670.4  239.64
#Mann= 18 ,-1 , 0
  3680.3     .05       0  4541.3     .07       0  4794.4     .05       0
    4910      .1       0    4939     .05       0  5010.1      .1       0
    5427     .07       0  6313.1    .035       0  6342.7     .07       0
  6543.2    .035       0  6697.2     .07       0  7302.4     .12       0
  7447.6     .07       0  7579.8     .05       0  7589.8     .07       0
    7712     .05       0    7882     .07       0  7987.1     .05       0
Bank Sta=4939,5010.1
XS Rating Curve= 0 ,0
Exp/Cntr=0.3,0.1

Type RM Length L Ch R = 1 ,7599    ,3521,3521,3521
BEGIN DESCRIPTION:
SALTY CREEK_SUGAR CREEK 3.0
END DESCRIPTION:
XS GIS Cut Line= 3
      2449234.22     13663908.83      2447966.34     13660843.46
      2447115.75     13657890.46
#Sta/Elev= 30
  2976.7  259.48  3034.6  257.07  3750.5  225.69  4041.4  220.77  4404.3  223.25
  4528.2  222.07  4907.1  223.87    4929  221.32  4935.7   216.5  4937.2   215.5
    5007   216.5  5084.6  220.32  5300.3  221.14    5421  223.51  5731.7  221.05
  5898.6  229.27  6102.1  231.28  6250.3  226.41  6462.7  219.07  6719.2  221.46
  7040.4  217.31  7305.5  217.53  7408.9   217.5  7822.3     219    8029   221.6
  8523.3  226.85  8700.7  228.72  9012.1  228.57  9131.6  227.86    9367  228.83
#Mann= 20 ,-1 , 0
  2976.7     .05       0  3034.6     .05       0  4404.3     .05       0
  4528.2     .07       0  4935.7     .05       0    5007      .1       0
  5084.6      .1       0  5300.3     .12       0  5731.7     .07       0
  5898.6     .05       0  6250.3     .07       0  7040.4     .12       0
  7305.5      .1       0  7408.9     .05       0  7822.3     .07       0
    8029     .05       0  8523.3     .07       0  8700.7     .05       0
  9012.1     .07       0  9131.6     .05       0
Bank Sta=4935.7,5007
XS Rating Curve= 0 ,0
Exp/Cntr=0.3,0.1

Type RM Length L Ch R = 1 ,4078    ,3504,3504,3504
BEGIN DESCRIPTION:
SALTY CREEK_SUGAR CREEK 2.0
END DESCRIPTION:
XS GIS Cut Line= 3
      2450389.76     13663940.96       2449523.1     13660907.66
      2448207.09     13658564.51
#Sta/Elev= 30
  2305.5  250.98  2336.8  250.42  2532.3  240.14  3028.4  226.96  3715.7  218.58
  4116.2  219.22  4401.7  219.17  4704.7  218.16  4828.5  213.83  4848.4  217.44
  4853.6  213.09  4921.2  212.76  4926.4  216.29  4969.6  212.11  4971.1  211.11
    5041  212.11    5111  219.39  5513.2   220.2  5619.1   219.8  5715.9  221.82
  6091.6  220.53  6255.5  217.87  6584.7  217.81  6802.1  222.64    7043  228.16
  7180.9  228.15  7234.2  228.06  7295.7  227.24  7374.4  226.53  8147.6  230.17
#Mann= 20 ,-1 , 0
  2305.5     .05       0  2336.8     .07       0  2532.3     .05       0
  4116.2      .1       0  4401.7    .035       0  4704.7     .07       0
  4969.6     .05       0    5041     .07       0  5513.2     .07       0
  5619.1     .12       0  5715.9     .07       0  6091.6      .1       0
  6255.5     .12       0  6584.7     .07       0  6802.1    .035       0
    7043     .05       0  7180.9    .035       0  7234.2     .05       0
  7295.7    .035       0  7374.4     .05       0
Bank Sta=4969.6,5041
XS Rating Curve= 0 ,0
Exp/Cntr=0.3,0.1

Type RM Length L Ch R = 1 ,574     ,0,0,0
BEGIN DESCRIPTION:
SALTY CREEK_SUGAR CREEK 1.0
END DESCRIPTION:
XS GIS Cut Line= 3
        2451128.     13663170.54      2450036.67     13658644.74
      2448479.93      13657120.1
#Sta/Elev= 30
   478.3  233.25   648.6  233.06  1090.9  219.81  1386.4  219.16  1943.6  219.23
  3181.5  218.71  3196.8  218.61  3283.5  218.48  3537.6  216.14  3572.1  218.55
  3677.1  218.74  4303.7  219.88  4507.7  220.33  4691.6  219.99  4813.8  219.45
  4950.6  216.96  4979.3   216.2    4984  209.47  4985.5  208.47  5056.7  209.47
  5061.5  220.42  5158.9  219.86  5296.1  222.58  5530.8  228.34  5827.8  225.69
  6160.1   232.2  6315.7   229.5    6648  230.38  6803.6   228.1  7312.8  231.14
#Mann= 17 ,-1 , 0
   478.3     .05       0  1386.4    .033       0  1943.6     .05       0
  3181.5     .07       0  3196.8      .1       0  3283.5     .07       0
  3572.1      .1       0  3677.1     .05       0  4303.7     .12       0
  4507.7     .12       0  4691.6     .07       0  4813.8     .12       0
  4950.6      .1       0    4984     .05       0  5056.7      .1       0
  5158.9     .12       0  5296.1     .05       0
Bank Sta=4984,5056.7
XS Rating Curve= 0 ,0
Exp/Cntr=0.3,0.1

Chan Stop Cuts=-1
Use User Specified Reach Order=0
Composite Channel Slope=5