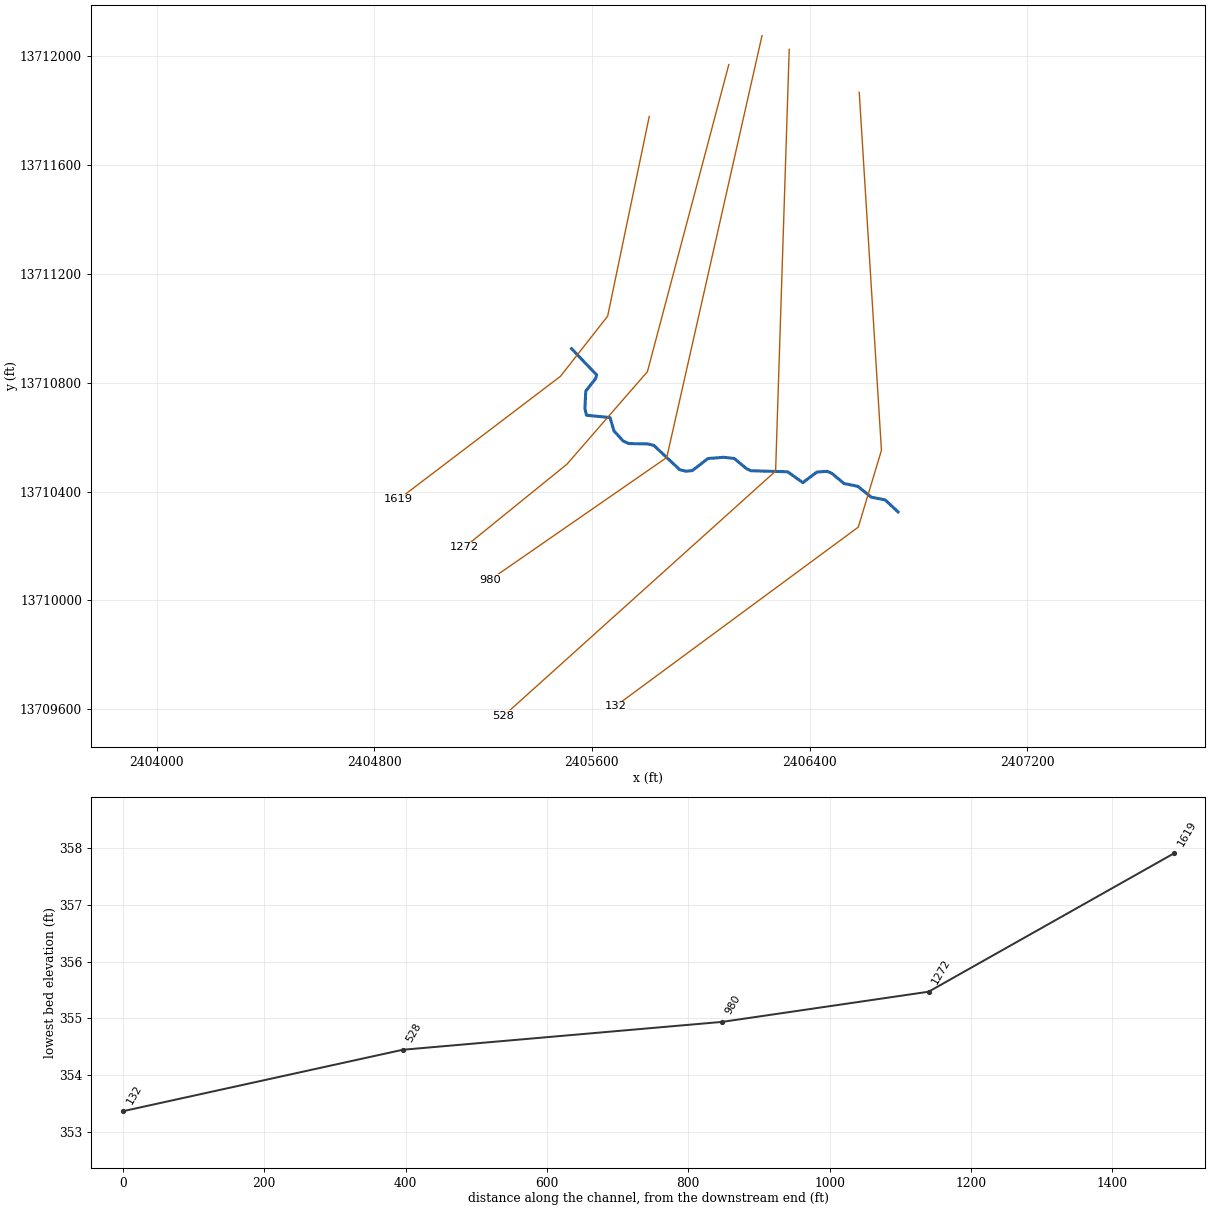
--- Stream0689.prj (project) ---

Proj Title=Stream0689 Base Level Engineering
Current Plan=p01
Default Exp/Contr=0.3,0.1
English Units
Geom File=g01
Flow File=f01
Plan File=p01
BEGIN DESCRIPTION:
Stream0689
END DESCRIPTION:

--- Stream0689.p01 (plan) ---

Plan Title=Multiple Run
Short Identifier=Multiple
Geom File=g01
Flow File=f01
Subcritical Flow
K Sum by GR= 0
Std Step Tol= 0.01
Critical Tol= 0.01
Num of Std Step Trials= 20
Max Error Tol= 0.3
Flow Tol Ratio= 0.001
Split Flow NTrial= 30
Split Flow Tol= 0.02
Split Flow Ratio= 0.02
Log Output Level= 0
Friction Slope Method= 1
Unsteady Friction Slope Method= 2
Unsteady Bridges Friction Slope Method= 1
Parabolic Critical Depth
Global Vel Dist=  1 , 1 , 1
Global Log Level= 0
CheckData=True
Encroach Param= -1, 0, 0, 0
BEGIN DESCRIPTION:
Multiple Run
END DESCRIPTION:

--- Stream0689.f01 (steady flow) ---

Flow Title=Multiple
Number of Profiles=7
Profile Names=10-year,25-year,50-year,1pct_min,100-year,1pct_plu,500-year
River Rch & RM= Stream0689,Reach-1,1619
     708    1146    1542    1004    2004    3999    3354
Boundary for River Rch & Prof#=Stream0689,Reach-1,1
Up Type=0
Dn Type=3
Dn Slope=0.005
Boundary for River Rch & Prof#=Stream0689,Reach-1,2
Up Type=0
Dn Type=3
Dn Slope=0.005
Boundary for River Rch & Prof#=Stream0689,Reach-1,3
Up Type=0
Dn Type=3
Dn Slope=0.005
Boundary for River Rch & Prof#=Stream0689,Reach-1,4
Up Type=0
Dn Type=3
Dn Slope=0.005
Boundary for River Rch & Prof#=Stream0689,Reach-1,5
Up Type=0
Dn Type=3
Dn Slope=0.005
Boundary for River Rch & Prof#=Stream0689,Reach-1,6
Up Type=0
Dn Type=3
Dn Slope=0.005
Boundary for River Rch & Prof#=Stream0689,Reach-1,7
Up Type=0
Dn Type=3
Dn Slope=0.005

--- Stream0689.g01 (geometry) ---

Geom Title=Existing Conditions

River Reach=Stream0689,Reach-1
Reach XY= 30
      2405525.00     13710925.00      2405617.32     13710828.42
      2405613.69     13710815.15      2405577.32     13710769.01
      2405574.19     13710704.52      2405580.03     13710680.14
      2405666.55     13710671.77      2405680.89     13710622.82
      2405714.92     13710585.45      2405735.34     13710576.12
      2405804.94     13710574.86      2405827.42     13710569.46
      2405922.71     13710480.10      2405945.13     13710474.61
      2405968.87     13710476.79      2406026.58     13710521.26
      2406085.05     13710525.77      2406123.40     13710521.30
      2406168.94     13710483.15      2406185.51     13710476.23
      2406319.14     13710472.53      2406375.01     13710432.59
      2406426.64     13710471.40      2406464.30     13710474.20
      2406480.93     13710467.21      2406526.72     13710429.22
      2406577.20     13710418.93      2406626.67     13710379.04
      2406677.36     13710369.33      2406725.00     13710325.00

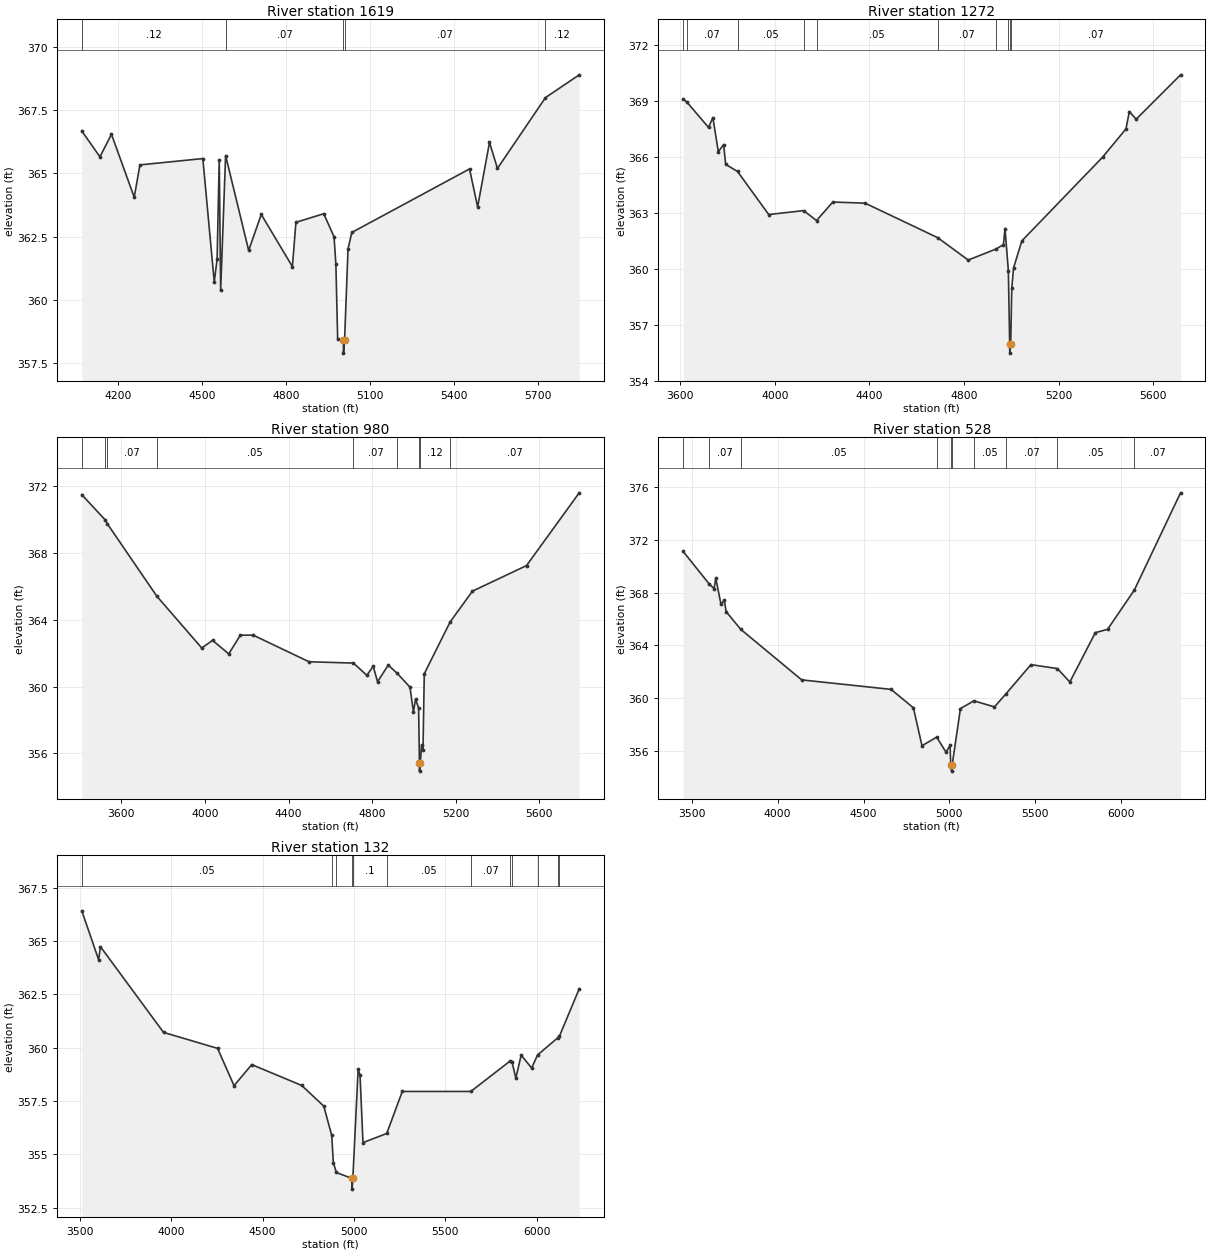
Type RM Length L Ch R = 1,1619,347,347,347
BEGIN DESCRIPTION:
XS7479
END DESCRIPTION:
XS GIS Cut Line= 4
      2405810.69     13711778.46      2405657.73     13711044.25
      2405484.36     13710823.30      2404889.72     13710371.37
#Sta/Elev= 30
  4070.7  366.68  4135.5  365.66  4176.8  366.55  4258.1  364.06  4278.5  365.34
  4503.3  365.59  4544.1  360.71  4554.3  361.61  4561.9  365.55  4567.0  360.38
  4584.7  365.71  4667.1  361.96  4712.1  363.38  4823.4  361.32  4836.0  363.07
  4935.4  363.41  4972.2  362.50  4978.8  361.41  4985.2  358.45  5005.7  358.40
  5006.0  357.90  5009.8  358.40  5022.2  362.02  5035.8  362.67  5456.4  365.18
  5485.4  363.68  5527.8  366.23  5556.2  365.20  5727.9  368.00  5848.4  368.90
#Mann=5,-1,0
  4070.7    0.12       0  4584.7    0.07       0  5005.7    0.05       0
  5009.8    0.07       0  5727.9    0.12       0
Bank Sta=5005.7,5009.8
Exp/Cntr=0.3,0.1

Type RM Length L Ch R = 1,1272,292,292,292
BEGIN DESCRIPTION:
XS7478
END DESCRIPTION:
XS GIS Cut Line= 4
      2406103.03     13711968.87      2405803.89     13710840.30
      2405508.16     13710500.37      2405130.81     13710194.42
#Sta/Elev= 30
  3612.1  369.09  3627.9  368.93  3719.6  367.57  3738.0  368.10  3760.9  366.27
  3783.4  366.65  3792.0  365.59  3842.2  365.21  3974.1  362.90  4121.8  363.11
  4176.4  362.58  4245.2  363.57  4381.7  363.51  4688.8  361.66  4817.9  360.46
  4937.2  361.06  4967.0  361.29  4973.6  362.15  4987.7  359.89  4993.3  355.97
  4993.6  355.47  4997.6  355.97  5002.1  358.95  5009.7  360.04  5044.9  361.49
  5385.9  365.97  5485.1  367.49  5499.5  368.42  5528.2  368.01  5716.0  370.39
#Mann=10,-1,0
  3612.1   0.045       0  3627.9    0.07       0  3842.2    0.05       0
  4121.8    0.12       0  4176.4    0.05       0  4688.8    0.07       0
  4937.2    0.12       0  4987.7    0.07       0  4993.3    0.05       0
  4997.6    0.07       0
Bank Sta=4993.3,4997.6
Exp/Cntr=0.3,0.1

Type RM Length L Ch R = 1,980,452,452,452
BEGIN DESCRIPTION:
Stream0689 2.0
END DESCRIPTION:
XS GIS Cut Line= 3
      2406225.01     13712075.04      2405875.00     13710525.00
      2405225.03     13710075.02
#Sta/Elev= 30
  3410.9  371.47  3523.7  369.95  3532.5  369.74  3769.8  365.40  3985.0  362.30
  4036.3  362.76  4113.9  361.95  4169.6  363.07  4231.1  363.07  4497.6  361.48
  4710.6  361.40  4774.4  360.67  4805.2  361.21  4825.7  360.28  4876.9  361.28
  4920.6  360.78  4980.9  359.96  4997.4  358.48  5007.4  359.24  5022.3  358.72
  5026.2  355.44  5026.5  354.94  5030.5  355.44  5036.4  356.52  5043.2  356.20
  5049.3  360.76  5173.0  363.86  5279.7  365.70  5538.5  367.23  5790.5  371.58
#Mann=9,-1,0
  3410.9   0.035       0  3523.7   0.045       0  3532.5    0.07       0
  3769.8    0.05       0  4710.6    0.07       0  4920.6    0.12       0
  5026.2    0.05       0  5030.5    0.12       0  5173.0    0.07       0
Bank Sta=5026.2,5030.5
Exp/Cntr=0.3,0.1

Type RM Length L Ch R = 1,528,396,396,396
BEGIN DESCRIPTION:
Stream0689 1.0
END DESCRIPTION:
XS GIS Cut Line= 3
      2406325.00     13712024.99      2406275.00     13710475.00
      2405274.97     13709574.97
#Sta/Elev= 30
  3449.5  371.14  3599.2  368.70  3629.6  368.31  3639.6  369.11  3669.6  367.14
  3689.6  367.43  3699.6  366.57  3785.1  365.22  4139.9  361.38  4660.1  360.66
  4790.2  359.26  4840.2  356.38  4925.6  357.03  4980.3  355.89  5003.7  356.40
  5007.4  355.00  5012.0  354.95  5012.2  354.45  5016.3  354.95  5064.2  359.20
  5142.0  359.79  5262.3  359.33  5327.2  360.29  5474.5  362.54  5628.9  362.24
  5701.0  361.22  5849.7  364.97  5920.8  365.22  6076.5  368.20  6345.7  375.59
#Mann=10,-1,0
  3449.5   0.035       0  3599.2    0.07       0  3785.1    0.05       0
  4925.6     0.1       0  5012.0    0.05       0  5016.3     0.1       0
  5142.0    0.05       0  5327.2    0.07       0  5628.9    0.05       0
  6076.5    0.07       0
Bank Sta=5012,5016.3
Exp/Cntr=0.3,0.1

Type RM Length L Ch R = 1,132,0,0,0
BEGIN DESCRIPTION:
XS7477
END DESCRIPTION:
XS GIS Cut Line= 4
      2406582.32     13711866.89      2406663.91     13710551.36
      2406578.92     13710269.22      2405685.56     13709610.47
#Sta/Elev= 30
  3510.2  366.42  3602.3  364.13  3612.3  364.74  3957.6  360.72  4253.5  359.97
  4343.7  358.22  4440.4  359.21  4714.4  358.23  4834.9  357.26  4878.3  355.89
  4887.1  354.61  4903.9  354.15  4989.4  353.87  4989.7  353.37  4993.8  353.87
  5022.9  358.99  5033.3  358.71  5049.4  355.55  5179.5  355.98  5264.5  357.95
  5639.6  357.95  5855.2  359.38  5864.9  359.35  5885.9  358.57  5915.2  359.65
  5972.7  359.05  6004.8  359.66  6116.3  360.47  6124.6  360.54  6232.9  362.76
#Mann=12,-1,0
  3510.2    0.05       0  4878.3    0.07       0  4903.9     0.1       0
  4989.4    0.05       0  4993.8     0.1       0  5179.5    0.05       0
  5639.6    0.07       0  5855.2    0.05       0  5864.9    0.07       0
  6004.8    0.05       0  6116.3    0.07       0  6124.6    0.05       0
Bank Sta=4989.4,4993.8
Exp/Cntr=0.3,0.1

Chan Stop Cuts=-1