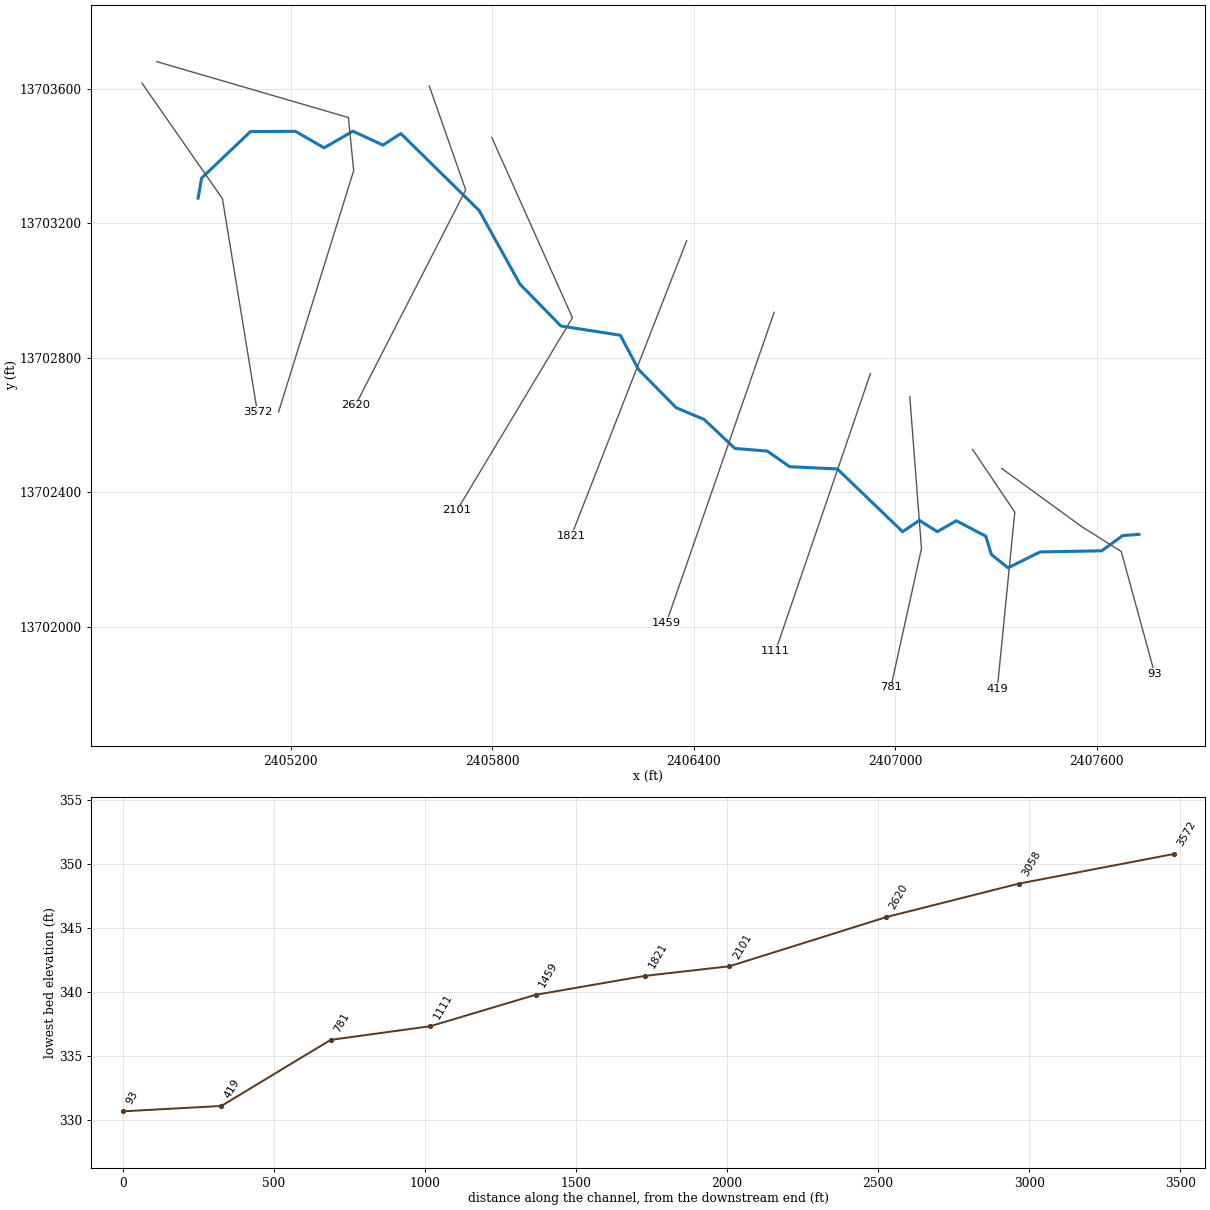
--- Stream0691.prj (project) ---

Proj Title=Stream0691 Base Level Engineering
Current Plan=p01
Default Exp/Contr=0.3,0.1
English Units
Geom File=g01
Flow File=f01
Plan File=p01
Y Axis Title=Elevation
X Axis Title(PF)=Main Channel Distance
X Axis Title(XS)=Station
BEGIN DESCRIPTION:
Stream0691
END DESCRIPTION:
DSS Export Rating Curves= 0
DSS Export Rating Curve Sorted= 0
DSS Export Volume Flow Curves= 0
DXF OffsetX= 0
DXF OffsetY= 0
DXF ScaleX= 1
DXF ScaleY= 10

--- Stream0691.p01 (plan) ---

Plan Title=Multiple Run
Short Identifier=Multiple
Geom File=g01
Flow File=f01
Subcritical Flow
K Sum by GR= 0
Std Step Tol= 0.01
Critical Tol= 0.01
Num of Std Step Trials= 20
Max Error Tol= 0.3
Flow Tol Ratio= 0.001
Split Flow NTrial= 30
Split Flow Tol= 0.02
Split Flow Ratio= 0.02
Log Output Level= 0
Friction Slope Method= 1
Unsteady Friction Slope Method= 2
Unsteady Bridges Friction Slope Method= 1
Parabolic Critical Depth
Global Vel Dist=  1 , 1 , 1
Global Log Level= 0
CheckData=True
Encroach Param= -1, 0, 0, 0
BEGIN DESCRIPTION:
Multiple Run
END DESCRIPTION:

--- Stream0691.f01 (steady flow) ---

Flow Title=Multiple
Number of Profiles=7
Profile Names=10-year,25-year,50-year,1pct_min,100-year,1pct_plu,500-year
River Rch & RM= Stream0691,Reach-1,3572
     306     471     612     387     772    1541    1213
Boundary for River Rch & Prof#=Stream0691,Reach-1,1
Up Type=0
Dn Type=3
Dn Slope=0.005
Boundary for River Rch & Prof#=Stream0691,Reach-1,2
Up Type=0
Dn Type=3
Dn Slope=0.005
Boundary for River Rch & Prof#=Stream0691,Reach-1,3
Up Type=0
Dn Type=3
Dn Slope=0.005
Boundary for River Rch & Prof#=Stream0691,Reach-1,4
Up Type=0
Dn Type=3
Dn Slope=0.005
Boundary for River Rch & Prof#=Stream0691,Reach-1,5
Up Type=0
Dn Type=3
Dn Slope=0.005
Boundary for River Rch & Prof#=Stream0691,Reach-1,6
Up Type=0
Dn Type=3
Dn Slope=0.005
Boundary for River Rch & Prof#=Stream0691,Reach-1,7
Up Type=0
Dn Type=3
Dn Slope=0.005

--- Stream0691.g01 (geometry) ---

Geom Title=Existing Conditions

River Reach=Stream0691,Reach-1
Reach XY= 30
      2404925.00     13703275.00      2404935.51     13703334.79
      2405080.86     13703472.95      2405214.50     13703473.77
      2405300.00     13703424.61      2405385.70     13703474.17
      2405475.09     13703432.84      2405528.34     13703467.01
      2405761.37     13703238.21      2405883.16     13703018.95
      2406004.84     13702894.61      2406181.47     13702867.30
      2406235.79     13702765.34      2406348.18     13702651.30
      2406431.04     13702616.82      2406522.58     13702530.54
      2406619.02     13702522.64      2406685.51     13702476.23
      2406827.45     13702469.53      2407021.67     13702282.98
      2407071.67     13702316.44      2407125.00     13702283.02
      2407181.59     13702315.45      2407269.37     13702269.40
      2407285.76     13702215.15      2407335.48     13702175.55
      2407430.93     13702222.71      2407614.54     13702226.12
      2407676.51     13702271.35      2407725.00     13702275.00

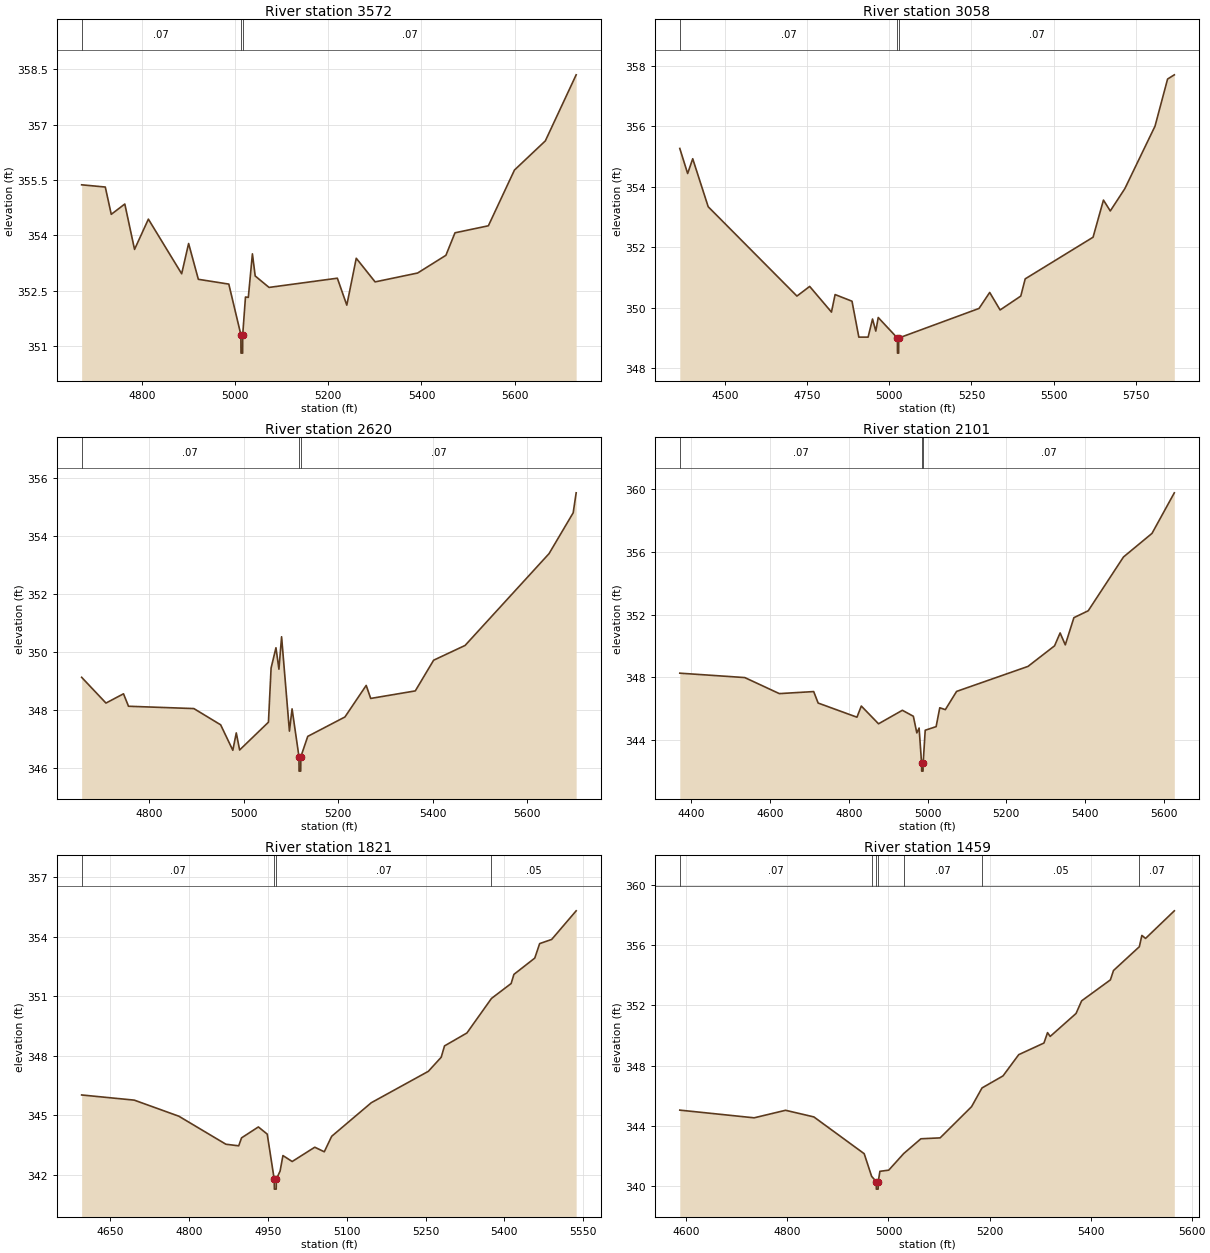
Type RM Length L Ch R = 1,3572,514,514,514
BEGIN DESCRIPTION:
XS7482
END DESCRIPTION:
XS GIS Cut Line= 3
      2404757.82     13703617.18      2404997.40     13703273.44
      2405101.40     13702639.00
#Sta/Elev= 30
  4670.3  355.37  4721.1  355.31  4733.9  354.57  4763.0  354.85  4783.9  353.62
  4813.6  354.44  4885.1  352.96  4900.0  353.78  4920.9  352.81  4986.3  352.68
  5012.2  351.31  5012.5  350.81  5016.0  350.81  5016.2  351.31  5022.1  352.33
  5028.2  352.32  5037.0  353.50  5043.0  352.90  5072.7  352.59  5219.4  352.84
  5239.7  352.11  5260.0  353.38  5300.5  352.74  5391.7  352.98  5452.5  353.46
  5472.0  354.07  5543.7  354.26  5599.7  355.77  5666.0  356.56  5732.2  358.35
#Mann=3,-1,0
  4670.3    0.07       0  5012.2    0.05       0  5016.2    0.07       0
Bank Sta=5012.2,5016.2
Exp/Cntr=0.3,0.1

Type RM Length L Ch R = 1,3058,438,438,438
BEGIN DESCRIPTION:
XS7481
END DESCRIPTION:
XS GIS Cut Line= 4
      2404802.07     13703680.97      2405372.29     13703514.72
      2405388.02     13703356.77      2405164.37     13702639.00
#Sta/Elev= 30
  4362.6  355.27  4386.5  354.44  4401.9  354.93  4449.0  353.34  4719.0  350.38
  4757.7  350.70  4824.0  349.85  4835.1  350.43  4886.5  350.21  4907.3  349.02
  4935.5  349.02  4949.0  349.62  4958.9  349.22  4966.3  349.67  5024.6  348.99
  5024.9  348.49  5028.4  348.49  5028.6  348.99  5272.9  349.97  5305.4  350.50
  5337.1  349.92  5400.0  350.38  5413.4  350.95  5619.9  352.33  5651.5  353.56
  5672.3  353.20  5716.6  353.94  5808.4  356.01  5846.6  357.57  5867.1  357.71
#Mann=3,-1,0
  4362.6    0.07       0  5024.6    0.05       0  5028.6    0.07       0
Bank Sta=5024.6,5028.6
Exp/Cntr=0.3,0.1

Type RM Length L Ch R = 1,2620,519,519,519
BEGIN DESCRIPTION:
XS7480
END DESCRIPTION:
XS GIS Cut Line= 3
      2405612.99     13703608.62      2405721.35     13703299.48
      2405393.52     13702659.43
#Sta/Elev= 30
  4657.1  349.12  4708.6  348.23  4745.7  348.55  4756.3  348.12  4894.6  348.04
  4951.3  347.48  4977.1  346.60  4984.4  347.20  4991.5  346.61  5052.5  347.57
  5058.1  349.44  5068.4  350.14  5074.7  349.40  5080.3  350.52  5096.9  347.26
  5102.5  348.03  5117.1  346.38  5117.3  345.88  5120.8  345.88  5121.1  346.38
  5135.7  347.08  5214.4  347.75  5259.4  348.84  5268.9  348.39  5363.3  348.65
  5402.1  349.71  5468.7  350.22  5646.4  353.39  5697.5  354.80  5703.8  355.49
#Mann=3,-1,0
  4657.1    0.07       0  5117.1    0.05       0  5121.1    0.07       0
Bank Sta=5117.1,5121.1
Exp/Cntr=0.3,0.1

Type RM Length L Ch R = 1,2101,280,280,280
BEGIN DESCRIPTION:
Stream0691 1.0
END DESCRIPTION:
XS GIS Cut Line= 3
      2405798.92     13703455.62      2406039.06     13702919.27
      2405695.30     13702346.34
#Sta/Elev= 30
  4370.8  348.27  4535.8  347.99  4623.6  346.97  4710.8  347.10  4722.1  346.37
  4820.7  345.47  4831.7  346.18  4875.5  345.05  4936.0  345.91  4963.9  345.53
  4972.7  344.47  4978.5  344.78  4984.8  342.54  4985.0  342.04  4988.5  342.04
  4988.8  342.54  4994.0  344.64  5021.7  344.87  5031.0  346.07  5045.1  345.95
  5073.7  347.11  5255.0  348.70  5322.5  350.01  5336.6  350.83  5349.7  350.07
  5371.6  351.80  5408.0  352.24  5497.5  355.66  5569.9  357.16  5626.6  359.74
#Mann=3,-1,0
  4370.8    0.07       0  4984.8    0.05       0  4988.8    0.07       0
Bank Sta=4984.8,4988.8
Exp/Cntr=0.3,0.1

Type RM Length L Ch R = 1,1821,362,362,362
BEGIN DESCRIPTION:
E21264
END DESCRIPTION:
XS GIS Cut Line= 2
      2406378.99     13703148.31      2406036.10     13702271.57
#Sta/Elev= 30
  4595.4  346.03  4695.6  345.77  4780.5  344.96  4870.0  343.55  4894.4  343.47
  4899.8  343.87  4931.8  344.42  4948.7  344.06  4962.0  341.79  4962.3  341.29
  4965.8  341.29  4966.0  341.79  4973.2  342.20  4978.6  342.98  4996.2  342.68
  5039.2  343.40  5057.3  343.17  5071.4  343.95  5146.8  345.64  5255.4  347.22
  5279.9  347.93  5286.2  348.50  5328.8  349.15  5375.6  350.89  5413.0  351.64
  5418.3  352.10  5458.0  352.92  5467.3  353.65  5490.2  353.86  5536.8  355.30
#Mann=4,-1,0
  4595.4    0.07       0  4962.0    0.05       0  4966.0    0.07       0
  5375.6    0.05       0
Bank Sta=4962,4966
Exp/Cntr=0.3,0.1

Type RM Length L Ch R = 1,1459,348,348,348
BEGIN DESCRIPTION:
E21263
END DESCRIPTION:
XS GIS Cut Line= 2
      2406639.41     13702935.65      2406318.25     13702011.24
#Sta/Elev= 30
  4587.1  345.05  4734.2  344.54  4796.4  345.04  4852.4  344.60  4952.0  342.16
  4966.7  340.66  4975.8  340.31  4976.1  339.81  4979.6  339.81  4979.8  340.31
  4983.1  340.99  5000.6  341.07  5030.2  342.17  5064.2  343.15  5102.3  343.21
  5164.5  345.28  5185.1  346.52  5226.7  347.32  5257.8  348.73  5307.7  349.50
  5314.8  350.19  5320.1  349.94  5371.2  351.46  5382.3  352.30  5439.2  353.69
  5445.3  354.31  5496.5  355.89  5501.5  356.64  5508.8  356.44  5565.7  358.27
#Mann=7,-1,0
  4587.1    0.07       0  4966.7    0.12       0  4975.8    0.05       0
  4979.8    0.12       0  5030.2    0.07       0  5185.1    0.05       0
  5496.5    0.07       0
Bank Sta=4975.8,4979.8
Exp/Cntr=0.3,0.1

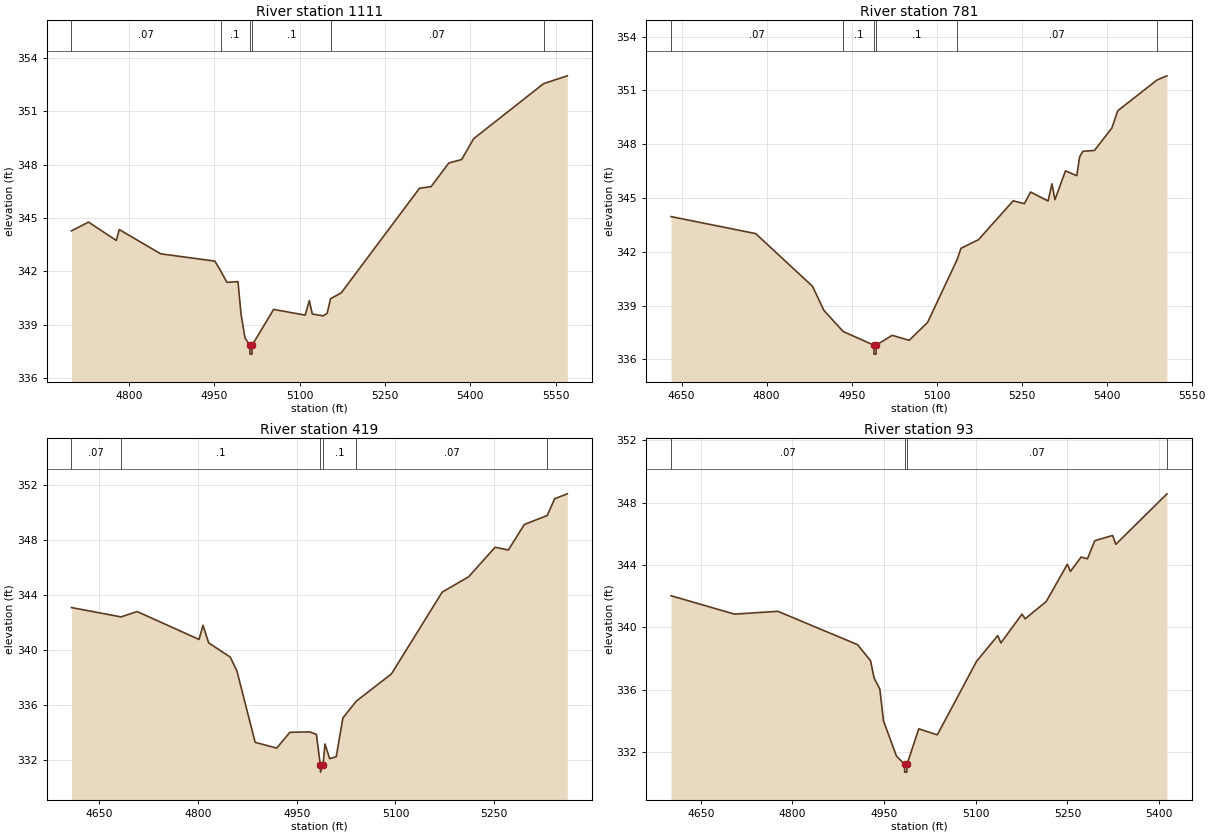
Type RM Length L Ch R = 1,1111,330,330,330
BEGIN DESCRIPTION:
E21262
END DESCRIPTION:
XS GIS Cut Line= 2
      2406925.87     13702753.36      2406643.97     13701929.35
#Sta/Elev= 30
  4699.3  344.28  4729.3  344.77  4778.0  343.74  4783.3  344.35  4856.1  342.99
  4951.2  342.58  4961.1  342.05  4972.4  341.39  4991.8  341.43  4997.1  339.62
  5004.1  338.27  5012.6  337.86  5012.9  337.36  5016.4  337.36  5016.6  337.86
  5054.4  339.87  5109.8  339.55  5117.1  340.36  5122.3  339.61  5141.5  339.51
  5148.4  339.65  5154.4  340.47  5173.2  340.80  5310.6  346.67  5330.9  346.76
  5362.2  348.09  5384.6  348.28  5405.7  349.45  5528.5  352.54  5570.2  352.98
#Mann=6,-1,0
  4699.3    0.07       0  4961.1     0.1       0  5012.6    0.05       0
  5016.6     0.1       0  5154.4    0.07       0  5528.5    0.05       0
Bank Sta=5012.6,5016.6
Exp/Cntr=0.3,0.1

Type RM Length L Ch R = 1,781,362,362,362
BEGIN DESCRIPTION:
E21261
END DESCRIPTION:
XS GIS Cut Line= 3
      2407043.07     13702683.92      2407077.79     13702232.56
      2406986.64     13701820.21
#Sta/Elev= 30
  4631.3  343.96  4780.7  343.01  4881.0  340.07  4901.0  338.73  4935.1  337.55
  4989.3  336.79  4989.5  336.29  4993.0  336.29  4993.3  336.79  5021.4  337.34
  5051.5  337.06  5084.0  338.06  5136.4  341.58  5142.9  342.19  5173.7  342.67
  5235.1  344.84  5254.8  344.68  5265.8  345.33  5296.6  344.83  5303.5  345.79
  5308.7  344.90  5327.3  346.51  5347.2  346.24  5352.3  347.29  5358.0  347.60
  5378.5  347.65  5409.2  348.90  5419.5  349.86  5489.0  351.58  5506.3  351.81
#Mann=6,-1,0
  4631.3    0.07       0  4935.1     0.1       0  4989.3    0.05       0
  4993.3     0.1       0  5136.4    0.07       0  5489.0   0.035       0
Bank Sta=4989.3,4993.3
Exp/Cntr=0.3,0.1

Type RM Length L Ch R = 1,419,326,326,326
BEGIN DESCRIPTION:
E21260
END DESCRIPTION:
XS GIS Cut Line= 3
      2407229.71     13702527.68      2407355.57     13702341.06
      2407303.49     13701815.93
#Sta/Elev= 30
  4608.1  343.11  4683.3  342.43  4707.8  342.82  4801.8  340.79  4807.8  341.82
  4816.4  340.54  4849.3  339.50  4859.4  338.48  4887.0  333.30  4919.7  332.88
  4939.8  334.03  4969.9  334.06  4980.0  333.88  4986.0  331.63  4986.2  331.13
  4990.0  331.63  4993.0  333.18  5000.1  332.11  5010.1  332.25  5020.2  335.07
  5040.6  336.30  5093.9  338.28  5170.9  344.23  5211.1  345.35  5251.3  347.50
  5271.4  347.30  5295.7  349.16  5330.4  349.81  5341.7  351.03  5360.9  351.39
#Mann=6,-1,0
  4608.1    0.07       0  4683.3     0.1       0  4986.0    0.05       0
  4990.0     0.1       0  5040.6    0.07       0  5330.4   0.063       0
Bank Sta=4986,4990
Exp/Cntr=0.3,0.1

Type RM Length L Ch R = 1,93,0,0,0
BEGIN DESCRIPTION:
E21259
END DESCRIPTION:
XS GIS Cut Line= 4
      2407316.53     13702471.25      2407555.22     13702297.66
      2407672.41     13702223.88      2407772.15     13701859.61
#Sta/Elev= 30
  4601.4  342.03  4705.1  340.85  4776.2  341.03  4906.6  338.89  4927.8  337.86
  4933.7  336.74  4943.0  336.04  4949.0  334.00  4970.2  331.74  4983.5  331.21
  4983.7  330.71  4987.2  330.71  4987.5  331.21  5006.7  333.49  5037.0  333.10
  5101.4  337.83  5135.9  339.47  5141.1  339.00  5175.6  340.85  5180.8  340.55
  5215.3  341.66  5249.8  344.05  5254.9  343.59  5272.3  344.51  5282.7  344.40
  5294.6  345.56  5323.9  345.90  5329.1  345.33  5412.6  348.56  5412.7  348.57
#Mann=4,-1,0
  4601.4    0.07       0  4983.5    0.05       0  4987.5    0.07       0
  5412.6   0.035       0
Bank Sta=4983.5,4987.5
Exp/Cntr=0.3,0.1

Chan Stop Cuts=-1