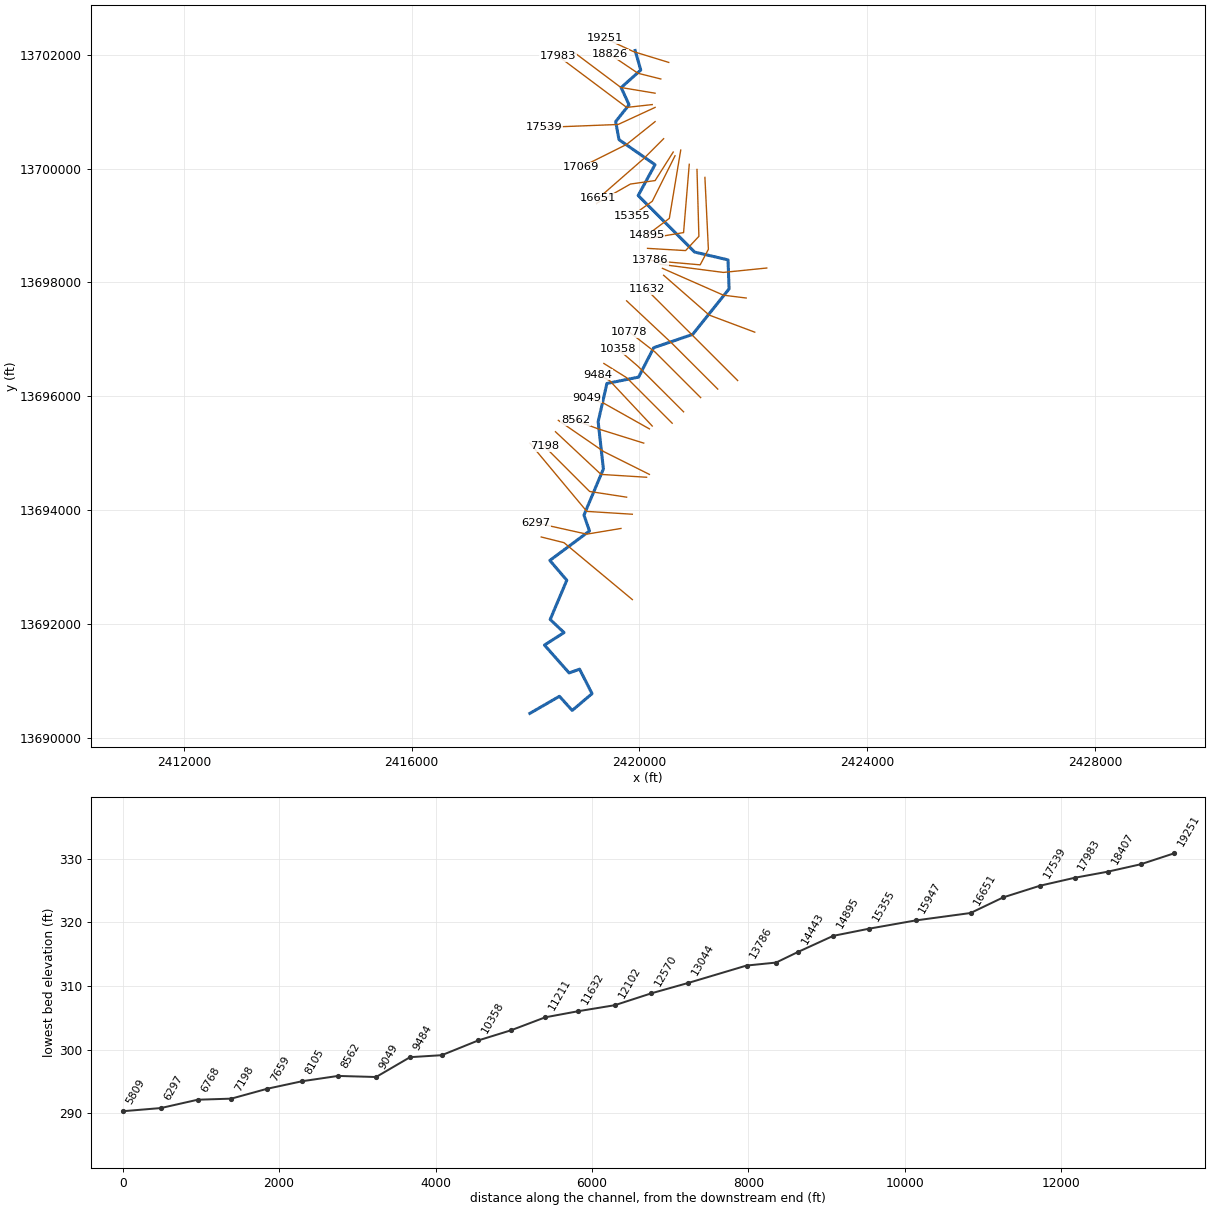
--- Stream0693.prj (project) ---

Proj Title=Stream0693 Base Level Engineering
Current Plan=p01
Default Exp/Contr=0.3,0.1
English Units
Geom File=g01
Flow File=f01
Plan File=p01
Y Axis Title=Elevation
X Axis Title(PF)=Main Channel Distance
X Axis Title(XS)=Station
BEGIN DESCRIPTION:
Stream0693
END DESCRIPTION:
DSS Export Rating Curves= 0
DSS Export Rating Curve Sorted= 0
DSS Export Volume Flow Curves= 0
DXF OffsetX= 0
DXF OffsetY= 0
DXF ScaleX= 1
DXF ScaleY= 10

--- Stream0693.p01 (plan) ---

Plan Title=Multiple Run
Short Identifier=Multiple
Geom File=g01
Flow File=f01
Subcritical Flow
K Sum by GR= 0
Std Step Tol= 0.01
Critical Tol= 0.01
Num of Std Step Trials= 20
Max Error Tol= 0.3
Flow Tol Ratio= 0.001
Split Flow NTrial= 30
Split Flow Tol= 0.02
Split Flow Ratio= 0.02
Log Output Level= 0
Friction Slope Method= 1
Unsteady Friction Slope Method= 2
Unsteady Bridges Friction Slope Method= 1
Parabolic Critical Depth
Global Vel Dist=  1 , 1 , 1
Global Log Level= 0
CheckData=True
Encroach Param= -1, 0, 0, 0
BEGIN DESCRIPTION:
Multiple Run
END DESCRIPTION:

--- Stream0693.f01 (steady flow) ---

Flow Title=Multiple
Number of Profiles=7
Profile Names=10-year,25-year,50-year,1pct_min,100-year,1pct_plu,500-year
River Rch & RM= Stream0693,Reach-1,19251
     641    1031    1382     897    1789    3570    2972
River Rch & RM= Stream0693,Reach-1,18407
     806    1307    1762    1149    2293    4574    3844
River Rch & RM= Stream0693,Reach-1,13044
    1489    2481    3404    2253    4495    8968    7772
Boundary for River Rch & Prof#=Stream0693,Reach-1,1
Up Type=0
Dn Type=3
Dn Slope=0.005
Boundary for River Rch & Prof#=Stream0693,Reach-1,2
Up Type=0
Dn Type=3
Dn Slope=0.005
Boundary for River Rch & Prof#=Stream0693,Reach-1,3
Up Type=0
Dn Type=3
Dn Slope=0.005
Boundary for River Rch & Prof#=Stream0693,Reach-1,4
Up Type=0
Dn Type=3
Dn Slope=0.005
Boundary for River Rch & Prof#=Stream0693,Reach-1,5
Up Type=0
Dn Type=3
Dn Slope=0.005
Boundary for River Rch & Prof#=Stream0693,Reach-1,6
Up Type=0
Dn Type=3
Dn Slope=0.005
Boundary for River Rch & Prof#=Stream0693,Reach-1,7
Up Type=0
Dn Type=3
Dn Slope=0.005

--- Stream0693.g01 (geometry) ---

Geom Title=Existing Conditions
Program Version=4.10

River Reach=Stream0693      ,Reach-1
Reach XY= 30
        2419925.       13702075.      2420022.86     13701730.97
      2419678.52     13701423.54      2419817.51     13701121.42
      2419582.08     13700825.01      2419641.06     13700507.95
      2420273.43     13700068.93      2419977.85     13699526.76
      2420968.81     13698532.75      2421555.77     13698395.57
       2421574.4     13697885.62      2420934.68     13697085.76
      2420250.64     13696851.99      2419985.12     13696335.06
      2419428.54     13696223.54      2419274.71     13695550.12
      2419366.92      13694721.7      2419025.36     13693909.73
      2419122.86     13693630.97       2418426.5     13693113.14
      2418723.96     13692764.56      2418432.28      13692074.9
      2418675.39     13691845.37      2418331.98     13691625.25
      2418764.81     13691135.77      2418948.71     13691201.96
      2419167.49     13690771.85      2418818.91     13690476.57
      2418595.05     13690725.22        2418075.       13690425.

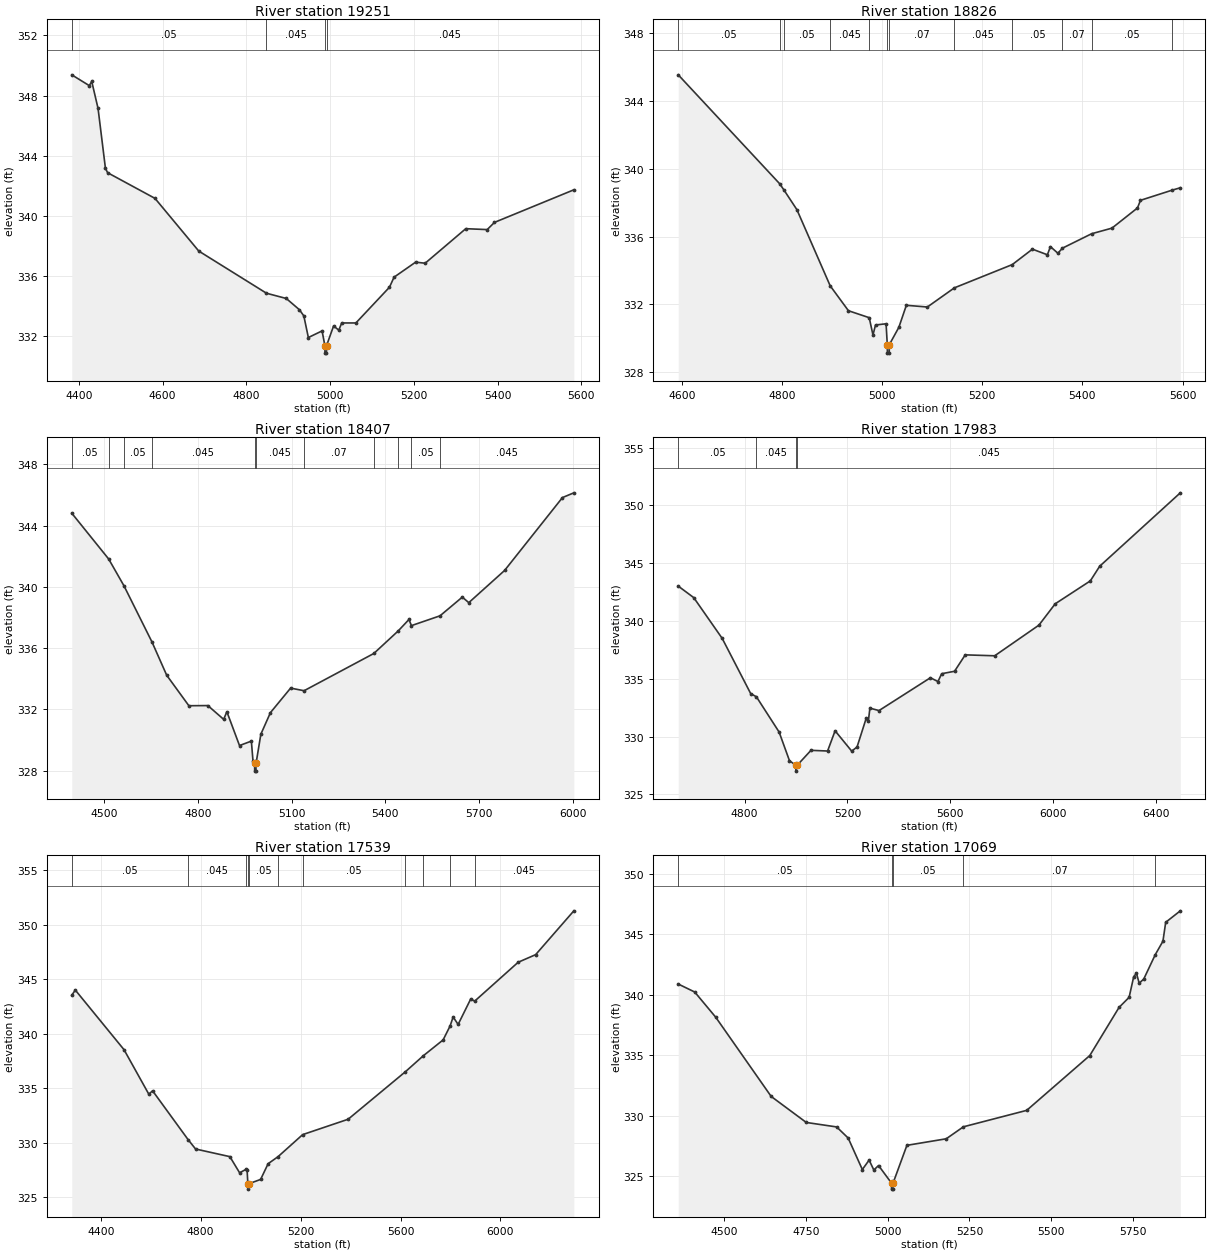
Type RM Length L Ch R = 1 ,19251   ,425,425,425
BEGIN DESCRIPTION:
XS7486
END DESCRIPTION:
XS GIS Cut Line= 3
      2420515.06     13701865.89      2419896.96     13702055.22
      2419395.79      13702289.1
#Sta/Elev= 30
  4382.8  349.38  4424.7  348.66  4430.5  348.94  4445.6  347.14  4463.2  343.16
  4468.4  342.86  4581.6  341.15  4686.2  337.64    4848  334.83  4895.3  334.48
  4926.7  333.73  4937.2  333.32    4948  331.88  4980.8  332.32  4987.5  331.34
  4987.7  330.84  4991.2  330.84  4991.5  331.34  5008.3  332.65  5020.8  332.37
  5027.7  332.85  5061.6  332.85  5141.8  335.23  5152.8   335.9  5204.3   336.9
  5227.1  336.83  5324.1  339.13  5375.3  339.07  5392.7  339.55  5582.3  341.72
#Mann= 4 ,-1 , 0
  4382.8     .05       0    4848    .045       0  4987.5    .045       0
  4991.5    .045       0
Bank Sta=4987.5,4991.5
XS Rating Curve= 0 ,0
Exp/Cntr=0.3,0.1

Type RM Length L Ch R = 1 ,18826   ,419,419,419
BEGIN DESCRIPTION:
Stream0693 33.0
END DESCRIPTION:
XS GIS Cut Line= 3
      2420374.98     13701575.01        2419975.       13701675.
      2419484.89      13702005.1
#Sta/Elev= 30
  4592.4  345.54    4795  339.12  4803.6  338.75  4829.5  337.59    4896   333.1
  4932.5  331.63    4974  331.22  4981.5   330.2  4986.6  330.79  5007.7  330.86
  5010.1  329.63  5010.4  329.13  5013.9  329.13  5014.2  329.63  5033.2  330.65
  5048.2  331.95  5090.2  331.85  5144.2  332.98  5259.8  334.35  5300.1  335.26
    5330  334.93  5336.1  335.41    5351  335.02  5360.1  335.32  5418.4  336.17
    5459   336.5    5510  337.69    5516  338.14  5579.3  338.74  5595.6  338.88
#Mann= 12 ,-1 , 0
  4592.4     .05       0    4795    .045       0  4803.6     .05       0
    4896    .045       0    4974     .07       0  5010.1     .05       0
  5014.2     .07       0  5144.2    .045       0  5259.8     .05       0
  5360.1     .07       0  5418.4     .05       0  5579.3    .045       0
Bank Sta=5010.1,5014.2
XS Rating Curve= 0 ,0
Exp/Cntr=0.3,0.1

Type RM Length L Ch R = 1 ,18407   ,424,424,424
BEGIN DESCRIPTION:
Stream0693 32.0
END DESCRIPTION:
XS GIS Cut Line= 3
        2420275.       13701325.        2419675.       13701425.
      2418874.98     13702025.02
#Sta/Elev= 30
  4395.7  344.81  4513.9  341.82  4562.9  340.07  4652.7   336.4  4699.8  334.23
  4770.8  332.24  4831.6  332.25  4882.3  331.35  4892.5  331.85    4933  329.64
    4971  329.93  4976.1  328.66  4981.4  328.47  4981.7  327.97  4985.6  327.97
    4986  328.47  5001.4  330.38  5032.1  331.79  5096.7  333.39  5139.9  333.22
  5363.2  335.65  5441.2  337.12  5475.8  337.87  5483.8  337.47  5575.3  338.11
  5646.7  339.33  5667.5  338.97  5782.1  341.07  5967.5  345.83    6004  346.14
#Mann= 11 ,-1 , 0
  4395.7     .05       0  4513.9    .045       0  4562.9     .05       0
  4652.7    .045       0  4981.4    .045       0    4986    .045       0
  5139.9     .07       0  5363.2     .05       0  5441.2     .07       0
  5483.8     .05       0  5575.3    .045       0
Bank Sta=4981.4,4986
XS Rating Curve= 0 ,0
Exp/Cntr=0.3,0.1

Type RM Length L Ch R = 1 ,17983   ,444,444,444
BEGIN DESCRIPTION:
Stream0693 31.0
END DESCRIPTION:
XS GIS Cut Line= 3
      2420225.03       13701125.        2419775.       13701075.
        2418575.       13701975.
#Sta/Elev= 30
  4542.1  343.02  4602.5  342.02  4713.2  338.49  4823.9  333.72  4846.2  333.44
  4934.5  330.39  4974.8  327.91  4999.9  327.51  5000.2  327.01  5004.5  327.51
  5058.4  328.81    5123  328.75  5152.2   330.5  5216.8  328.74  5237.6   329.1
    5273  331.57  5281.4  331.31  5287.6  332.46    5323  332.25    5523  335.09
  5552.2  334.76  5566.8  335.44  5616.8  335.65  5658.4  337.07    5773  336.99
  5944.9  339.64  6008.4  341.49  6144.9  343.47  6181.4  344.74  6494.9  351.09
#Mann= 4 ,-1 , 0
  4542.1     .05       0  4846.2    .045       0  4999.9    .045       0
  5004.5    .045       0
Bank Sta=4999.9,5004.5
XS Rating Curve= 0 ,0
Exp/Cntr=0.3,0.1

Type RM Length L Ch R = 1 ,17539   ,470,470,470
BEGIN DESCRIPTION:
Stream0693 30.0
END DESCRIPTION:
XS GIS Cut Line= 3
      2420274.99     13701074.99        2419625.       13700775.
      2418332.17     13700724.33
#Sta/Elev= 30
    4284  343.55  4298.2  344.02  4493.2  338.55  4592.4  334.47  4607.5  334.78
  4749.7   330.3  4779.6  329.44  4916.8  328.74  4955.8  327.26  4981.1  327.57
  4985.7  327.55  4988.8  326.26  4989.1  325.76  4993.6  326.26  5039.9  326.65
  5069.9  328.09  5109.8  328.74  5208.2  330.76  5390.2  332.17  5619.5  336.53
  5690.9  337.99  5770.5  339.45  5798.6  340.74  5810.5  341.55  5830.5  340.87
  5880.6  343.19    5897  343.01  6070.7  346.57  6140.8  347.27  6293.7  351.29
#Mann= 11 ,-1 , 0
    4284     .05       0  4749.7    .045       0  4981.1     .05       0
  4988.8     .05       0  4993.6     .05       0  5109.8    .045       0
  5208.2     .05       0  5619.5     .07       0  5690.9     .05       0
  5798.6     .07       0    5897    .045       0
Bank Sta=4988.8,4993.6
XS Rating Curve= 0 ,0
Exp/Cntr=0.3,0.1

Type RM Length L Ch R = 1 ,17069   ,418,418,418
BEGIN DESCRIPTION:
Stream0693 29.0
END DESCRIPTION:
XS GIS Cut Line= 3
        2420275.       13700825.        2419775.       13700425.
      2418975.04     13700025.02
#Sta/Elev= 30
  4359.7  340.88  4410.1  340.22  4474.2  338.14  4643.8  331.59  4751.1  329.44
  4843.9  329.07  4879.2  328.15  4922.4  325.55  4943.2  326.33  4957.6  325.51
    4972  325.88  5011.6  324.43  5011.9  323.93    5016  323.93  5016.4  324.43
  5058.7  327.55  5178.9  328.09  5231.3  329.08  5424.9  330.44  5617.7  334.97
  5707.2  338.95  5737.9  339.78  5751.9  341.48  5760.3  341.77  5768.7  340.95
  5782.6  341.29  5817.9  343.31  5841.3  344.42  5849.7  345.98  5894.4  346.93
#Mann= 5 ,-1 , 0
  4359.7     .05       0  5011.6     .05       0  5016.4     .05       0
  5231.3     .07       0  5817.9    .045       0
Bank Sta=5011.6,5016.4
XS Rating Curve= 0 ,0
Exp/Cntr=0.3,0.1

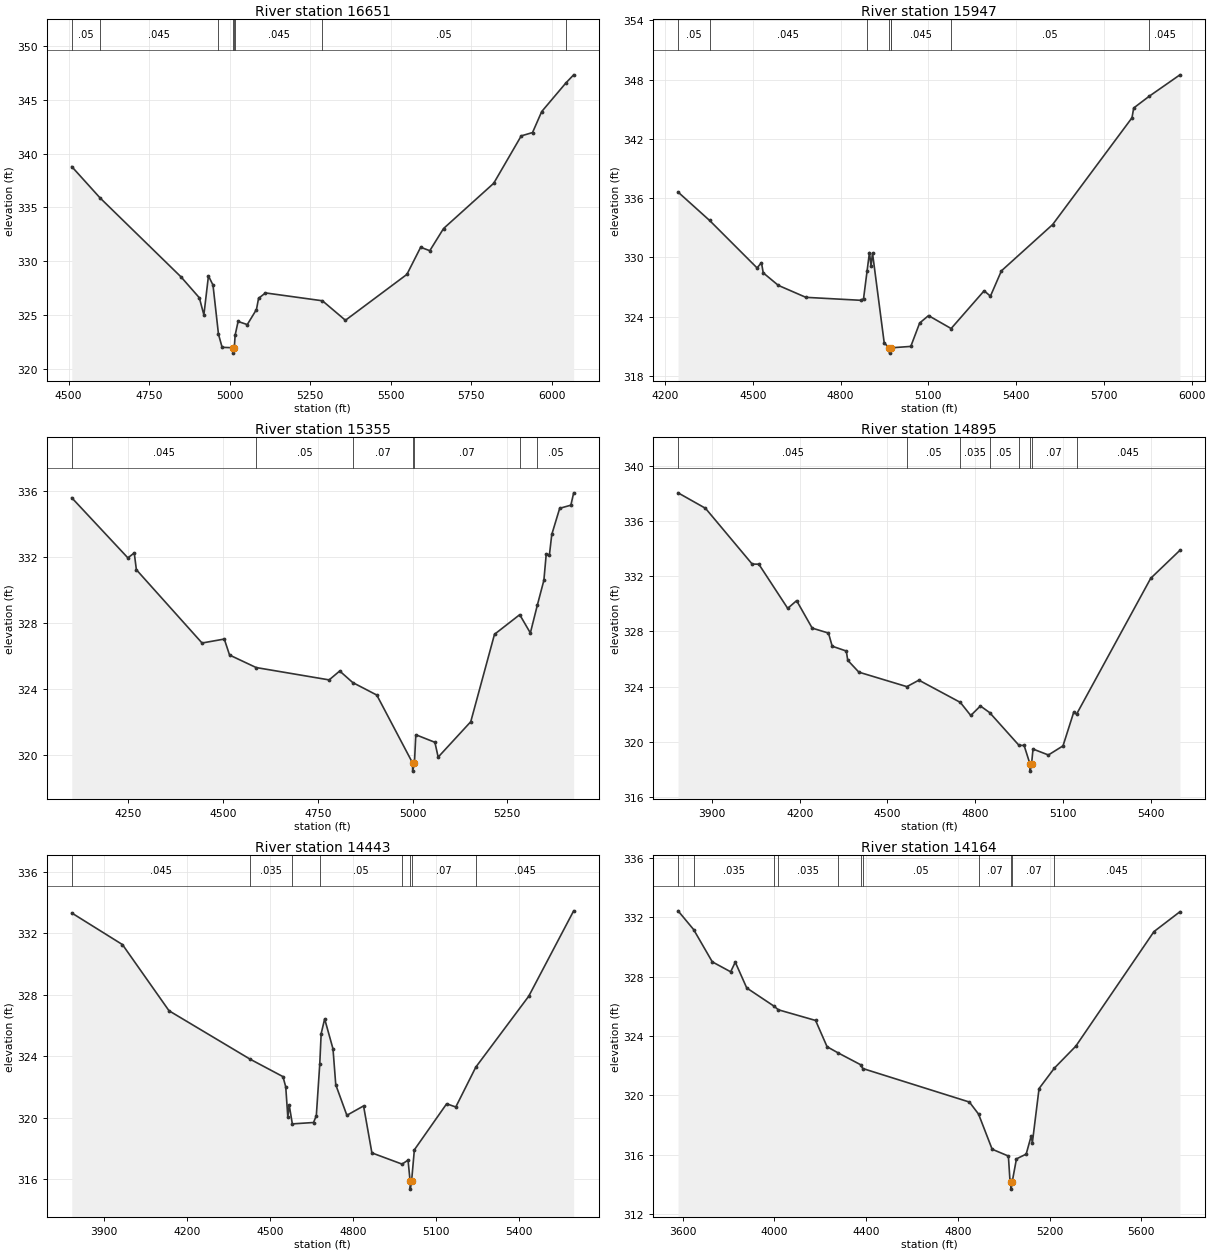
Type RM Length L Ch R = 1 ,16651   ,704,704,704
BEGIN DESCRIPTION:
Stream0693 28.0
END DESCRIPTION:
XS GIS Cut Line= 3
      2420425.01     13700525.01        2420075.       13700175.
        2419275.       13699475.
#Sta/Elev= 30
  4509.7  338.79  4597.6  335.88  4849.1  328.54  4905.7  326.61  4919.8  325.02
    4934  328.64  4948.1  327.79  4965.1  323.23  4976.4  322.01  5009.4  321.97
  5009.7  321.47  5014.3  321.97  5016.8  323.13    5026  324.41  5054.5  324.12
    5083  325.52  5089.6  326.56    5111  327.06  5287.8  326.33  5359.2  324.52
    5550  328.78  5592.7   331.3  5621.1  330.98  5663.8  333.04  5819.5  337.24
  5904.9  341.64    5940  341.95  5968.5   343.9  6043.7  346.56  6067.7  347.31
#Mann= 8 ,-1 , 0
  4509.7     .05       0  4597.6    .045       0  4965.1     .05       0
  5009.4     .05       0  5014.3     .05       0  5016.8    .045       0
  5287.8     .05       0  6043.7    .045       0
Bank Sta=5009.4,5014.3
XS Rating Curve= 0 ,0
Exp/Cntr=0.3,0.1

Type RM Length L Ch R = 1 ,15947   ,592,592,592
BEGIN DESCRIPTION:
XS7485
END DESCRIPTION:
XS GIS Cut Line= 4
        2420593.      13700290.5      2420275.62     13699789.37
      2419841.27     13699728.12      2419246.81     13699389.22
#Sta/Elev= 30
    4244  336.61    4352  333.73  4514.1  328.93  4529.3  329.46  4535.2  328.43
  4586.9  327.16    4681  325.95  4868.1  325.65  4878.2   325.8  4890.5  328.65
  4898.4  330.48  4903.9  329.13  4908.9  330.43  4948.9  321.34  4966.6   320.8
    4967   320.3  4971.5   320.8  4973.4  320.84  5039.8  320.98  5070.1  323.35
  5100.4   324.1  5177.7  322.79  5290.5  326.61  5312.1  326.07  5349.6  328.63
  5524.8  333.32  5796.1  344.13  5801.9  345.12  5854.9  346.31  5960.1  348.48
#Mann= 8 ,-1 , 0
    4244     .05       0    4352    .045       0  4890.5     .07       0
  4966.6    .045       0  4971.5     .07       0  4973.4    .045       0
  5177.7     .05       0  5854.9    .045       0
Bank Sta=4966.6,4971.5
XS Rating Curve= 0 ,0
Exp/Cntr=0.3,0.1

Type RM Length L Ch R = 1 ,15355   ,460,460,460
BEGIN DESCRIPTION:
Stream0693 27.0
END DESCRIPTION:
XS GIS Cut Line= 3
      2420624.98     13700224.97        2420225.       13699425.
      2419875.01       13699175.
#Sta/Elev= 30
  4100.5  335.61  4248.6  331.96  4265.4  332.26    4271  331.24  4444.3  326.79
    4503  327.03  4516.9  326.06  4587.1   325.3  4779.7  324.55  4807.6  325.09
  4841.9  324.39  4905.4  323.63  4999.8  319.51  5000.1  319.01  5004.8  319.51
  5008.4  321.22  5058.8  320.76  5067.4  319.86  5153.4  322.01  5216.1  327.32
  5282.6  328.51  5310.7   327.4    5329  329.08  5346.4   330.6  5352.5  332.17
  5361.1  332.16  5367.2  333.38  5388.1  334.97  5417.6  335.16    5425  335.91
#Mann= 7 ,-1 , 0
  4100.5    .045       0  4587.1     .05       0  4841.9     .07       0
  4999.8     .05       0  5004.8     .07       0  5282.6    .035       0
    5329     .05       0
Bank Sta=4999.8,5004.8
XS Rating Curve= 0 ,0
Exp/Cntr=0.3,0.1

Type RM Length L Ch R = 1 ,14895   ,452,452,452
BEGIN DESCRIPTION:
Stream0693 26.0
END DESCRIPTION:
XS GIS Cut Line= 3
        2420725.     13700325.03        2420525.       13699125.
      2420124.98     13698824.99
#Sta/Elev= 30
    3784  338.04  3877.8  336.92  4037.5  332.88  4060.3  332.87  4159.1  329.67
  4189.5  330.23  4242.8  328.24  4298.5  327.88  4311.2  326.93  4359.4  326.58
  4364.4  325.91  4402.4  325.05  4566.6     324  4607.7  324.47  4749.4  322.86
  4785.1  321.91  4818.1   322.6  4849.7  322.12    4950  319.75  4967.6  319.74
  4987.9  318.38  4988.3  317.88    4993  318.38    4998  319.48  5050.6  319.05
  5100.6  319.71    5137  322.13  5147.1  322.01  5400.6  331.85  5500.6  333.88
#Mann= 8 ,-1 , 0
    3784    .045       0  4566.6     .05       0  4749.4    .035       0
  4849.7     .05       0    4950     .07       0  4987.9     .05       0
    4993     .07       0  5147.1    .045       0
Bank Sta=4987.9,4993
XS Rating Curve= 0 ,0
Exp/Cntr=0.3,0.1

Type RM Length L Ch R = 1 ,14443   ,279,279,279
BEGIN DESCRIPTION:
Stream0693 25.0
END DESCRIPTION:
XS GIS Cut Line= 3
        2420875.     13700075.01        2420775.       13698875.
      2420175.05     13698775.01
#Sta/Elev= 30
  3783.5  333.33  3966.6  331.27  4134.7  326.96  4427.1  323.81  4546.1  322.67
  4556.2     322  4563.7  320.03  4568.7  320.81    4580  319.59  4656.5  319.68
  4666.6  320.12    4679  323.48  4684.1  325.47  4696.7  326.43  4726.8  324.48
  4736.8  322.14  4776.9  320.15  4837.2  320.76  4867.3   317.7  4976.2  316.97
  4997.8  317.23  5005.4  315.84  5005.8  315.34  5010.5  315.84  5020.6   317.9
  5137.2   320.9  5170.2  320.69  5242.6  323.29  5433.7  327.91  5595.9  333.47
#Mann= 8 ,-1 , 0
  3783.5    .045       0  4427.1    .035       0    4580     .07       0
    4679     .05       0  4976.2     .07       0  5005.4     .05       0
  5010.5     .07       0  5242.6    .045       0
Bank Sta=5005.4,5010.5
XS Rating Curve= 0 ,0
Exp/Cntr=0.3,0.1

Type RM Length L Ch R = 1 ,14164   ,378,378,378
BEGIN DESCRIPTION:
XS7484
END DESCRIPTION:
XS GIS Cut Line= 4
      2421010.67     13699984.25      2421044.08      13698809.3
       2420810.2     13698558.72      2420141.94      13698597.7
#Sta/Elev= 30
  3580.5  332.44  3648.3  331.18  3729.8     329  3809.8  328.33  3829.9  328.98
  3879.9  327.24  4000.1     326  4017.5  325.77    4180  325.05    4230  323.28
  4277.4  322.87  4375.8  322.07  4385.6  321.81  4850.3  319.55  4890.2  318.74
  4949.5  316.37  5020.3  315.91  5027.1  314.28  5031.9  314.18  5032.3  313.68
    5037  314.18  5055.5  315.72  5097.8  316.04  5119.8  317.27  5124.8  316.81
    5154  320.46  5220.9  321.84  5314.3  323.32  5654.8  331.04  5768.1  332.38
#Mann= 11 ,-1 , 0
  3580.5    .045       0  3648.3    .035       0  4000.1     .05       0
  4017.5    .035       0  4277.4     .05       0  4375.8     .07       0
  4385.6     .05       0  4890.2     .07       0  5031.9     .05       0
    5037     .07       0  5220.9    .045       0
Bank Sta=5031.9,5037
XS Rating Curve= 0 ,0
Exp/Cntr=0.3,0.1

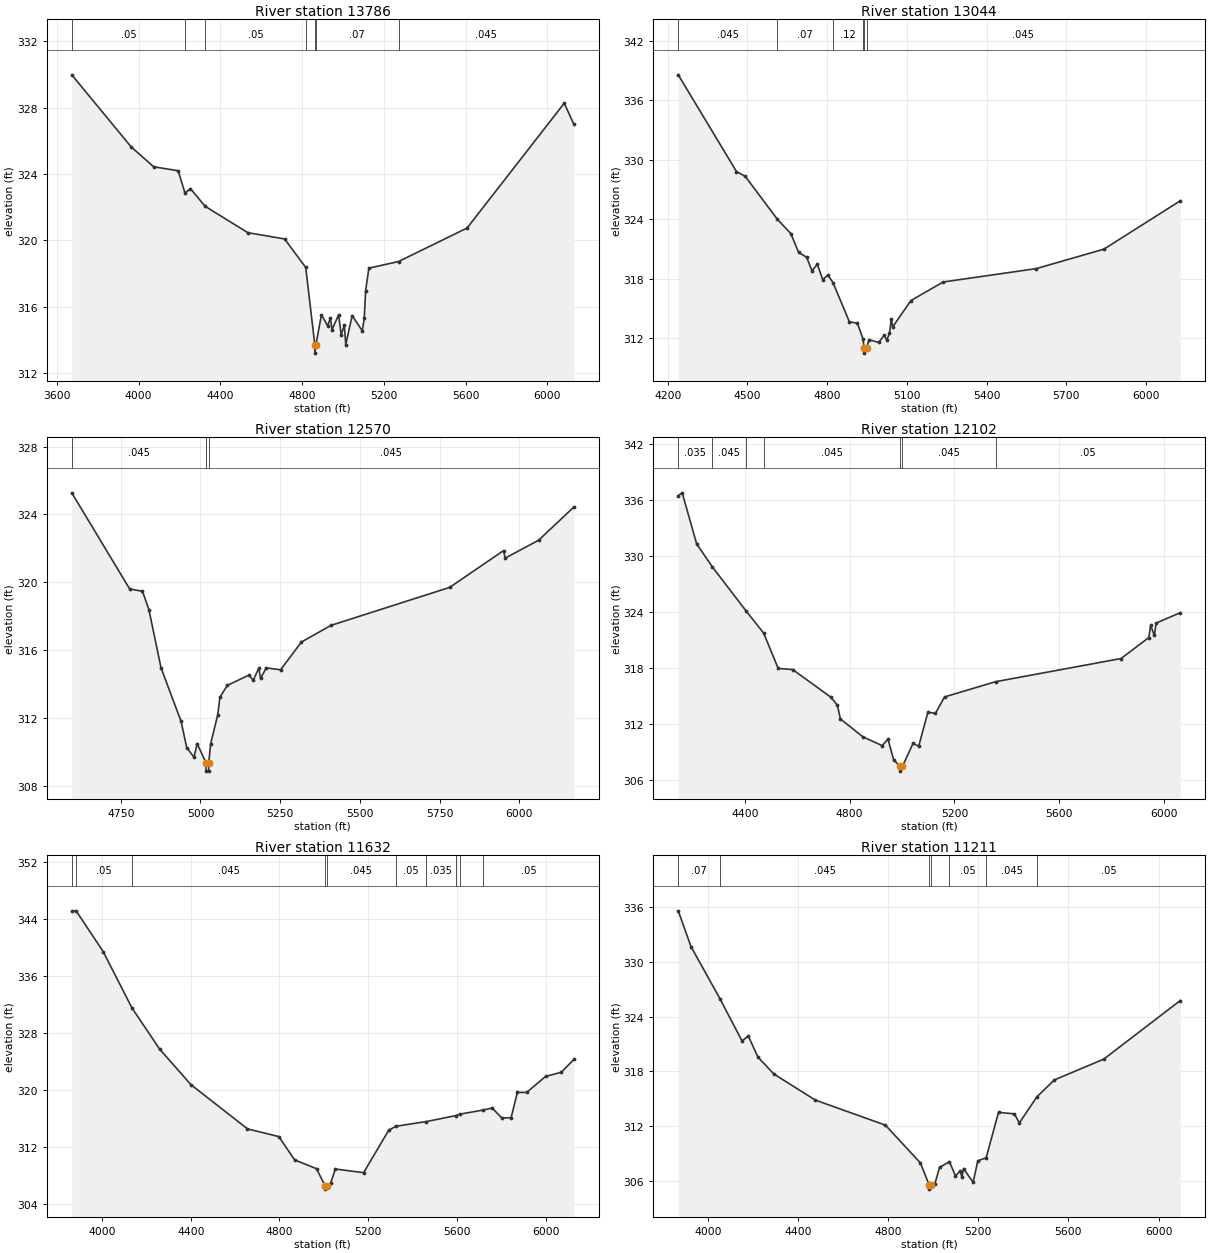
Type RM Length L Ch R = 1 ,13786   ,742,742,742
BEGIN DESCRIPTION:
XS7483
END DESCRIPTION:
XS GIS Cut Line= 4
      2421149.89     13699845.03      2421211.14     13698580.99
      2421066.36     13698308.13      2420188.21     13698385.94
#Sta/Elev= 30
    3673  329.98  3963.4  325.64  4073.5  324.44  4193.6   324.2  4226.8  322.85
  4253.7  323.12  4325.3  322.06    4534  320.47  4714.3  320.09  4817.5  318.37
  4861.9  313.71  4862.2  313.21    4867  313.71  4894.5  315.52  4924.5  314.86
  4938.5  315.33    4946  314.63  4978.6  315.52  4990.6  314.32  5006.3  314.89
  5013.2  313.72  5044.6  315.47  5094.2  314.55  5103.8  315.31  5110.5  316.98
  5126.4  318.33  5271.8  318.73  5606.8  320.75    6082  328.27    6129     327
#Mann= 7 ,-1 , 0
    3673     .05       0  4226.8    .035       0  4325.3     .05       0
  4817.5     .07       0  4861.9     .05       0    4867     .07       0
  5271.8    .045       0
Bank Sta=4861.9,4867
XS Rating Curve= 0 ,0
Exp/Cntr=0.3,0.1

Type RM Length L Ch R = 1 ,13044   ,474,474,474
BEGIN DESCRIPTION:
Stream0693 24.0
END DESCRIPTION:
XS GIS Cut Line= 3
      2422235.74     13698252.45        2421475.       13698175.
      2420359.56     13698319.22
#Sta/Elev= 30
  4239.8  338.55    4459   328.8  4491.8  328.32    4613  323.98  4663.3  322.55
  4692.9  320.64    4723  320.16  4743.1  318.79  4763.2  319.46  4783.3  317.91
  4803.4  318.35  4822.2   317.6  4883.9  313.65    4914  313.51  4934.9  311.94
  4939.8  310.99  4940.3  310.49  4948.5  310.99  4957.2  311.84  4994.4  311.57
  5014.6  312.29  5024.6  311.81  5034.7  312.48  5041.6  313.97  5046.7  313.13
  5115.4  315.79  5236.4  317.66  5586.8  319.01  5841.4  320.97  6129.2  325.85
#Mann= 6 ,-1 , 0
  4239.8    .045       0    4613     .07       0  4822.2     .12       0
  4934.9    .045       0  4939.8    .045       0  4948.5    .045       0
Bank Sta=4939.8,4948.5
XS Rating Curve= 0 ,0
Exp/Cntr=0.3,0.1

Type RM Length L Ch R = 1 ,12570   ,468,468,468
BEGIN DESCRIPTION:
Stream0693 23.0
END DESCRIPTION:
XS GIS Cut Line= 3
      2421875.03       13697725.        2421475.       13697775.
      2420403.67     13698246.89
#Sta/Elev= 30
  4596.6  325.27    4778   319.6  4818.3  319.46  4838.5  318.37  4876.3  314.95
  4939.3  311.78  4956.9  310.24  4979.6  309.67  4989.7  310.47  5017.2  309.35
  5017.7  308.85  5025.5  308.85    5026  309.35    5032  310.47  5054.4  312.19
  5060.8   313.2  5084.1  313.91  5152.7  314.52  5165.1   314.2  5182.9  314.93
  5188.4  314.32  5206.3  314.94  5251.1  314.83  5316.6  316.47  5409.3  317.45
  5781.1  319.69  5949.9  321.86  5955.4  321.42  6059.7  322.47  6170.4  324.43
#Mann= 3 ,-1 , 0
  4596.6    .045       0  5017.2    .045       0    5026    .045       0
Bank Sta=5017.2,5026
XS Rating Curve= 0 ,0
Exp/Cntr=0.3,0.1

Type RM Length L Ch R = 1 ,12102   ,470,470,470
BEGIN DESCRIPTION:
Stream0693 22.0
END DESCRIPTION:
XS GIS Cut Line= 3
      2422024.98     13697125.01        2421225.       13697425.
      2420424.99     13698125.01
#Sta/Elev= 30
  4145.4  336.49  4160.5  336.79  4215.7  331.33    4275  328.88  4403.9  324.16
  4471.7  321.76  4527.2  317.98  4582.4  317.86  4728.3   314.9  4753.2  314.04
  4764.8  312.57  4850.3  310.66  4924.1  309.71  4946.4  310.41  4967.7  308.22
  4992.7  307.48  4993.2  306.98  5001.5  307.48    5042  309.95  5063.8  309.66
    5099   313.3  5127.4  313.16  5162.6  314.93  5357.4  316.56  5836.4  319.04
  5942.7  321.29  5949.4  322.61  5963.6  321.51  5970.3  322.84  6062.8  323.95
#Mann= 7 ,-1 , 0
  4145.4    .035       0    4275    .045       0  4403.9    .035       0
  4471.7    .045       0  4992.7    .045       0  5001.5    .045       0
  5357.4     .05       0
Bank Sta=4992.7,5001.5
XS Rating Curve= 0 ,0
Exp/Cntr=0.3,0.1

Type RM Length L Ch R = 1 ,11632   ,421,421,421
BEGIN DESCRIPTION:
Stream0693 21.0
END DESCRIPTION:
XS GIS Cut Line= 3
      2421724.97     13696275.03        2420925.       13697075.
        2420125.       13697875.
#Sta/Elev= 30
  3863.9  345.14  3883.5  345.14  4005.3  339.42  4135.2  331.49  4259.8  325.71
  4401.3   320.7  4655.8   314.5  4797.2  313.41    4868  310.14  4966.9   308.9
  5004.9  306.53  5005.4  306.03  5013.9  306.53  5030.6  306.86  5051.8  308.86
  5179.1  308.34  5292.2   314.3  5323.8  314.86  5460.8  315.52  5596.1  316.37
  5611.7  316.56  5717.6  317.14  5758.9  317.43  5801.3  316.04  5843.8  316.06
    5872  319.61  5914.5  319.63  5999.3  321.87    6070  322.45  6126.6  324.25
#Mann= 10 ,-1 , 0
  3863.9    .035       0  3883.5     .05       0  4135.2    .045       0
  5004.9    .045       0  5013.9    .045       0  5323.8     .05       0
  5460.8    .035       0  5596.1     .05       0  5611.7    .035       0
  5717.6     .05       0
Bank Sta=5004.9,5013.9
XS Rating Curve= 0 ,0
Exp/Cntr=0.3,0.1

Type RM Length L Ch R = 1 ,11211   ,433,433,433
BEGIN DESCRIPTION:
Stream0693 20.0
END DESCRIPTION:
XS GIS Cut Line= 3
      2421375.03     13696124.97        2420575.       13696925.
        2419775.       13697675.
#Sta/Elev= 30
  3868.7   335.6  3925.3  331.68  4054.8  325.91  4151.6  321.33  4179.9  321.86
  4222.3  319.56    4293   317.7  4476.9  314.84    4788  312.09  4943.5  307.94
  4981.4  305.57  4981.9  305.07  4990.5  305.57  5007.2  305.62  5028.2  307.45
  5072.2  308.08    5099  306.52  5120.5  307.06  5127.4  306.37  5134.7  307.32
  5177.2  305.82  5198.2  308.18  5235.1  308.51    5290   313.5  5360.8  313.32
  5382.3  312.33  5460.8  315.21  5537.7  317.05    5757  319.33  6096.7  325.76
#Mann= 7 ,-1 , 0
  3868.7     .07       0  4054.8    .045       0  4981.4    .045       0
  4990.5    .045       0  5072.2     .05       0  5235.1    .045       0
  5460.8     .05       0
Bank Sta=4981.4,4990.5
XS Rating Curve= 0 ,0
Exp/Cntr=0.3,0.1

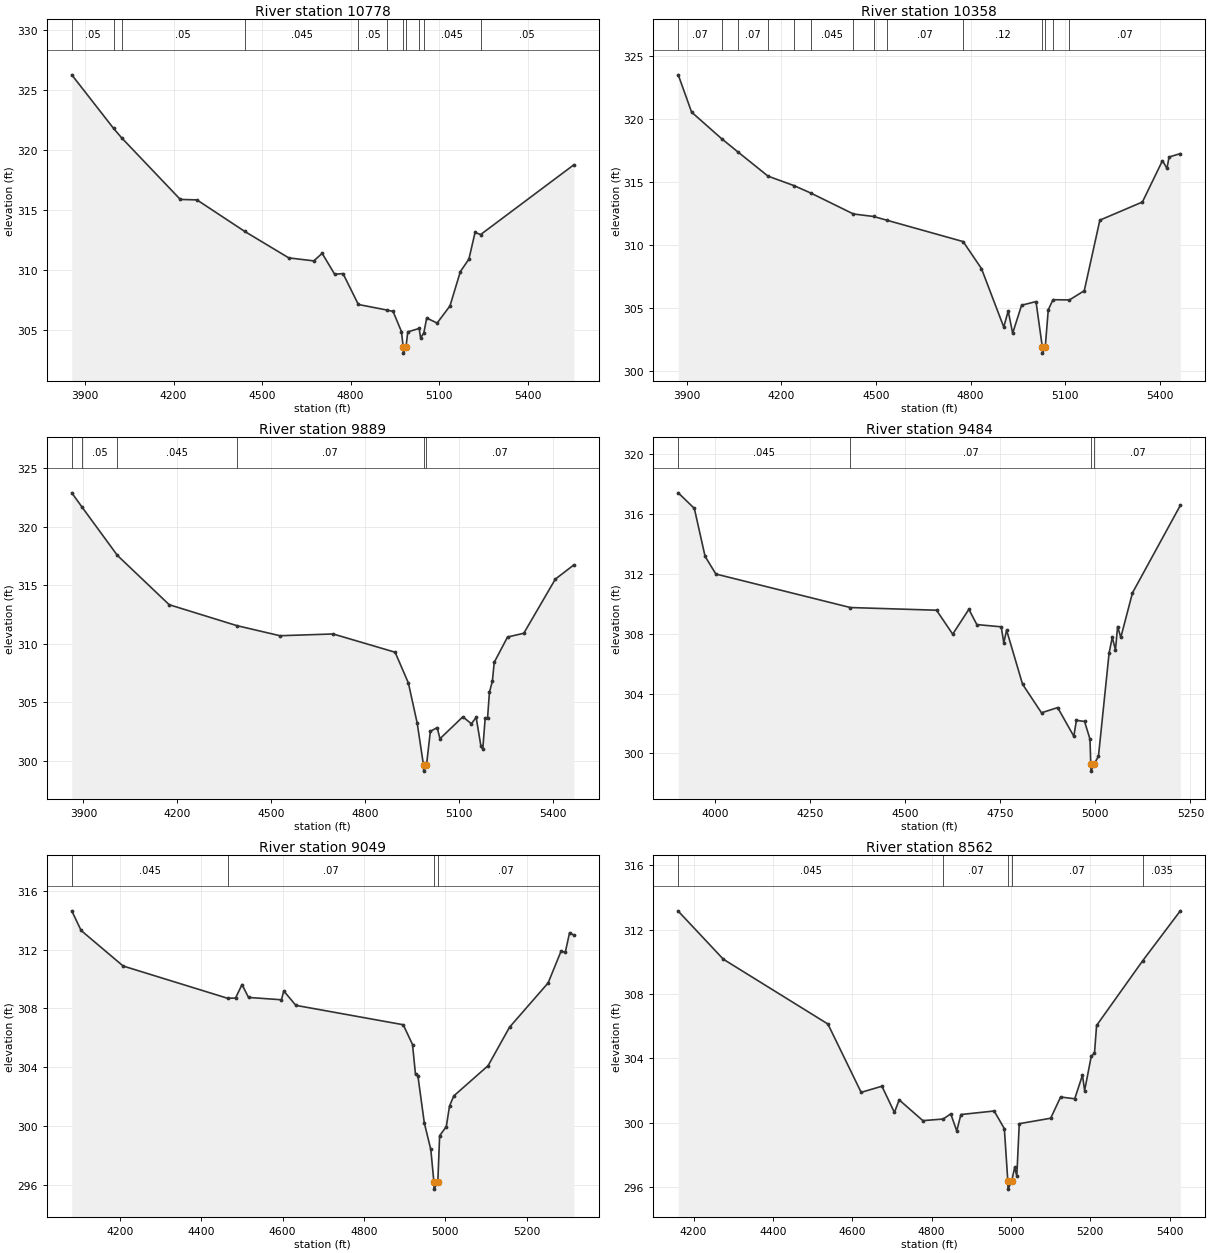
Type RM Length L Ch R = 1 ,10778   ,420,420,420
BEGIN DESCRIPTION:
Stream0693 19.0
END DESCRIPTION:
XS GIS Cut Line= 3
      2421074.99     13695975.01        2420275.       13696775.
      2419825.04     13697124.97
#Sta/Elev= 30
  3855.1  326.28  3996.7  321.81  4023.8  321.03  4222.8  315.88  4279.4  315.84
  4441.2  313.21  4590.5     311  4675.3  310.75  4703.6  311.38    4746  309.63
  4774.3  309.69  4826.3  307.11  4922.2  306.65    4944  306.53  4972.3  304.85
  4978.3  303.55  4978.8  303.05  4987.6  303.55  4993.7  304.82  5032.2  305.11
  5037.1  304.34  5047.9  304.71  5057.9  305.98  5093.2  305.56  5136.7  306.99
    5172  309.86  5200.9   310.9  5221.7  313.12  5240.8  312.95  5556.5  318.77
#Mann= 11 ,-1 , 0
  3855.1     .05       0  3996.7    .045       0  4023.8     .05       0
  4441.2    .045       0  4826.3     .05       0  4922.2    .045       0
  4978.3    .045       0  4987.6    .045       0  5032.2     .05       0
  5047.9    .045       0  5240.8     .05       0
Bank Sta=4978.3,4987.6
XS Rating Curve= 0 ,0
Exp/Cntr=0.3,0.1

Type RM Length L Ch R = 1 ,10358   ,469,469,469
BEGIN DESCRIPTION:
Stream0693 18.0
END DESCRIPTION:
XS GIS Cut Line= 3
      2420775.01     13695724.99        2419975.       13696525.
      2419624.97     13696825.03
#Sta/Elev= 30
  3872.5  323.53  3914.9  320.57  4009.8  318.47  4062.4   317.4  4157.4  315.49
  4239.7  314.74    4293  314.15  4428.1  312.49  4492.3  312.29  4534.8  311.99
  4776.1   310.3  4834.2  308.16  4904.9  303.52    4919  304.79  4933.2  303.03
  4961.5  305.25  5007.2  305.54  5027.2  301.95  5027.7  301.45  5036.6  301.95
  5046.1  304.89  5061.2  305.69  5113.2  305.67  5160.3   306.4  5209.7     312
  5344.7  313.44  5408.3  316.72  5422.6  316.11  5429.2  317.01  5464.9  317.28
#Mann= 14 ,-1 , 0
  3872.5     .07       0  4009.8     .05       0  4062.4     .07       0
  4157.4    .045       0  4239.7     .05       0    4293    .045       0
  4428.1     .07       0  4492.3     .12       0  4534.8     .07       0
  4776.1     .12       0  5027.2     .05       0  5036.6     .12       0
  5061.2    .045       0  5113.2     .07       0
Bank Sta=5027.2,5036.6
XS Rating Curve= 0 ,0
Exp/Cntr=0.3,0.1

Type RM Length L Ch R = 1 ,9889    ,405,405,405
BEGIN DESCRIPTION:
Stream0693 17.0
END DESCRIPTION:
XS GIS Cut Line= 3
        2420575.       13695525.        2419775.       13696325.
      2419374.97     13696575.02
#Sta/Elev= 30
  3862.8   322.9  3896.4  321.65  4008.6  317.55  4173.9  313.34  4390.2  311.55
  4527.5  310.69  4697.2  310.84  4895.2  309.28  4937.6  306.65  4965.9   303.2
  4985.9  299.62  4986.4  299.12  4995.4  299.62  5007.7  302.52  5029.5  302.84
  5038.4  301.89  5111.5  303.76  5138.6  303.17    5154  303.71  5169.3  301.24
  5175.2  301.02  5182.8  303.65  5190.5   303.7  5196.4  305.86  5205.8  306.81
  5211.7  308.42  5254.2  310.58  5306.1   310.9  5406.9  315.53  5465.9  316.74
#Mann= 6 ,-1 , 0
  3862.8     .07       0  3896.4     .05       0  4008.6    .045       0
  4390.2     .07       0  4985.9     .05       0  4995.4     .07       0
Bank Sta=4985.9,4995.4
XS Rating Curve= 0 ,0
Exp/Cntr=0.3,0.1

Type RM Length L Ch R = 1 ,9484    ,435,435,435
BEGIN DESCRIPTION:
Stream0693 16.0
END DESCRIPTION:
XS GIS Cut Line= 3
      2420225.02     13695474.98        2419475.       13696275.
      2419275.02     13696374.99
#Sta/Elev= 30
  3903.1  317.42  3945.4  316.38  3973.7  313.17  4002.1  311.99  4355.7  309.75
  4582.3  309.57  4624.8  307.97  4667.3  309.63  4688.3  308.61  4752.3  308.46
  4759.2  307.39  4766.5  308.24  4808.5  304.62  4858.3  302.71  4900.8  303.06
  4943.3  301.14  4950.1  302.21  4971.6  302.13  4985.8  300.95  4987.8  299.31
  4988.3  298.81  4997.4  299.31  5008.1  299.81  5036.1  306.72  5044.4  307.75
  5052.8  306.92  5058.4  308.48  5066.8  307.75  5097.5  310.73  5223.3  316.58
#Mann= 4 ,-1 , 0
  3903.1    .045       0  4355.7     .07       0  4987.8     .05       0
  4997.4     .07       0
Bank Sta=4987.8,4997.4
XS Rating Curve= 0 ,0
Exp/Cntr=0.3,0.1

Type RM Length L Ch R = 1 ,9049    ,487,487,487
BEGIN DESCRIPTION:
Stream0693 15.0
END DESCRIPTION:
XS GIS Cut Line= 3
      2420175.04     13695424.98        2419375.       13695875.
      2419075.05     13695974.98
#Sta/Elev= 30
    4082  314.65    4105  313.31  4208.3  310.89  4465.3  308.69  4484.6  308.71
  4500.5  309.63  4516.4  308.75  4597.4  308.59  4603.1  309.19  4632.8  308.21
  4896.7  306.89  4919.6  305.54  4926.9   303.5  4932.7  303.42  4948.6  300.19
  4964.5  298.39  4972.1  296.19  4972.6  295.69  4981.8  296.19  4986.2  299.33
  5002.6  299.95  5010.5  301.35    5021  302.04  5105.3   304.1    5158  306.72
  5252.9  309.74  5284.5  311.89  5295.1  311.83  5305.6  313.16  5316.1  312.99
#Mann= 4 ,-1 , 0
    4082    .045       0  4465.3     .07       0  4972.1     .05       0
  4981.8     .07       0
Bank Sta=4972.1,4981.8
XS Rating Curve= 0 ,0
Exp/Cntr=0.3,0.1

Type RM Length L Ch R = 1 ,8562    ,457,457,457
BEGIN DESCRIPTION:
Stream0693 14.0
END DESCRIPTION:
XS GIS Cut Line= 3
      2420075.01       13695175.        2419275.       13695425.
      2418874.96     13695575.01
#Sta/Elev= 30
  4161.4  313.15  4275.1  310.16  4538.6  306.13  4622.4  301.88  4674.8  302.26
  4706.2  300.63  4718.3  301.41    4778  300.12    4829  300.22  4848.2  300.54
  4863.4  299.48  4873.8   300.5  4957.7  300.72  4983.3  299.62  4992.1  296.36
  4992.6  295.86  5001.8  296.36  5009.4  297.22  5014.7  296.67  5020.9  299.93
  5100.1  300.27  5125.1  301.59  5160.7  301.48  5180.2  302.95  5185.6  301.99
  5202.5  304.14  5210.5  304.31  5215.8  306.04  5331.8  310.06  5426.8  313.17
#Mann= 5 ,-1 , 0
  4161.4    .045       0    4829     .07       0  4992.1     .05       0
  5001.8     .07       0  5331.8    .035       0
Bank Sta=4992.1,5001.8
XS Rating Curve= 0 ,0
Exp/Cntr=0.3,0.1

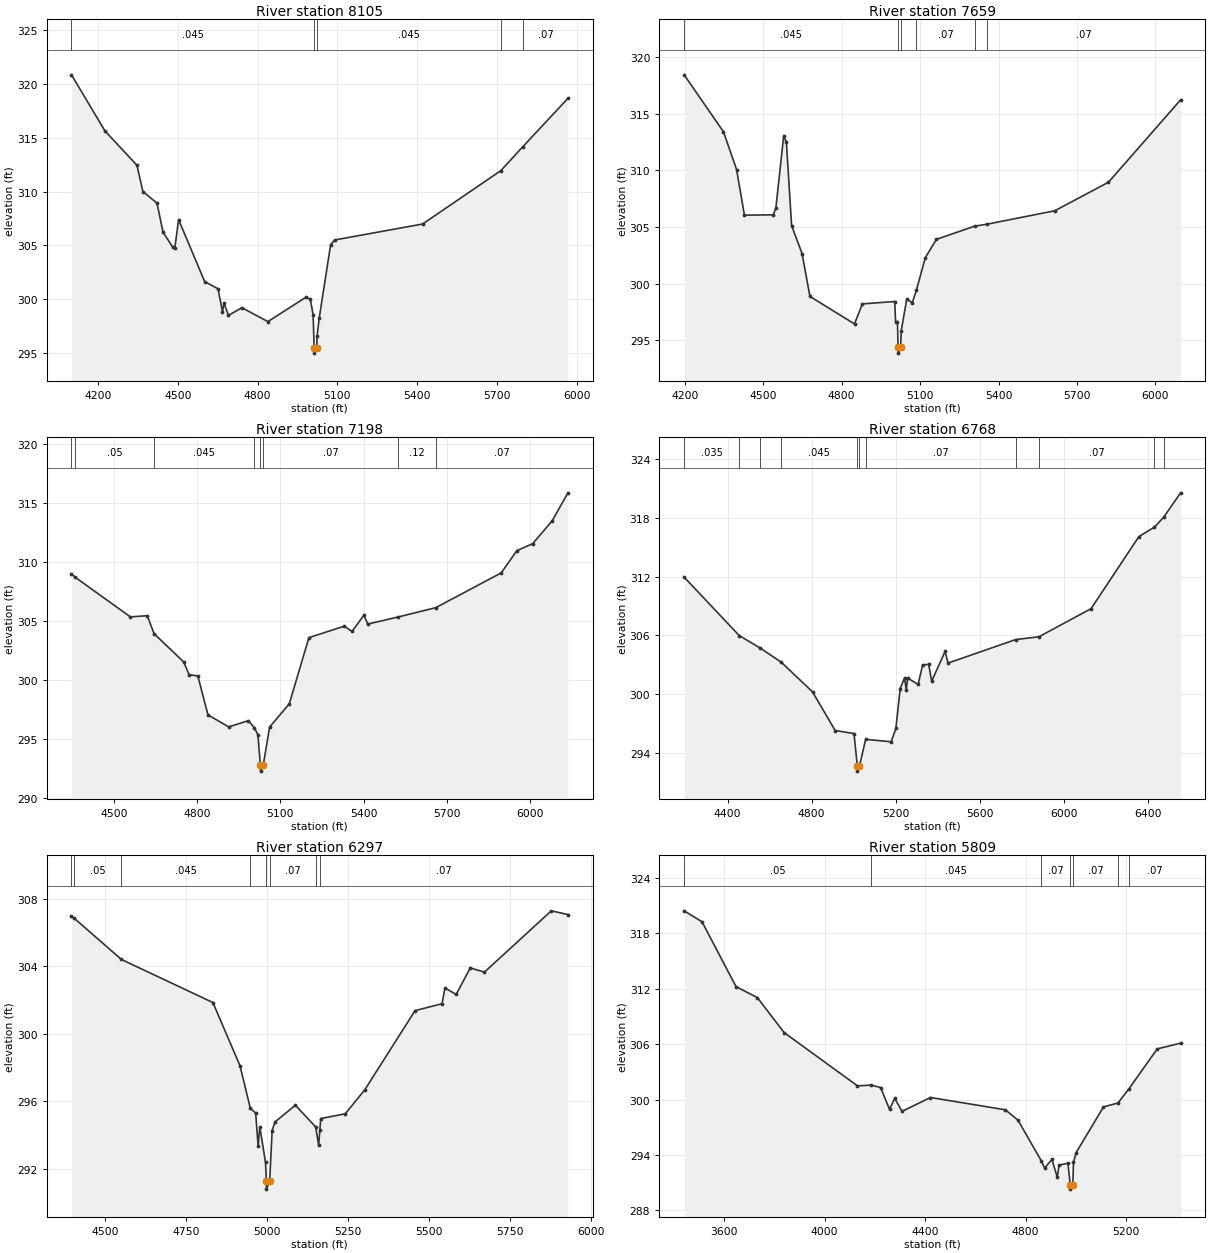
Type RM Length L Ch R = 1 ,8105    ,446,446,446
BEGIN DESCRIPTION:
Stream0693 13.0
END DESCRIPTION:
XS GIS Cut Line= 3
        2420175.       13694625.        2419375.       13695025.
      2418574.96     13695575.03
#Sta/Elev= 30
  4100.9  320.81  4226.7  315.61  4346.9  312.43  4369.2     310  4422.3  308.92
  4444.7  306.25    4481  304.85  4489.4   304.8  4503.4   307.4  4601.2  301.66
  4651.5  300.99  4668.3  298.86  4673.9  299.68  4690.7  298.52    4741  299.24
  4838.8  297.95  4981.4   300.2  4998.4  300.03  5008.8  298.58  5012.8  295.53
  5013.3  295.03  5022.6  295.53  5023.7  296.62  5031.7  298.27  5074.5  305.06
  5089.4  305.51  5420.1  306.99  5713.9  311.93  5796.7  314.15  5966.2  318.63
#Mann= 5 ,-1 , 0
  4100.9    .045       0  5012.8    .045       0  5022.6    .045       0
  5713.9    .035       0  5796.7     .07       0
Bank Sta=5012.8,5022.6
XS Rating Curve= 0 ,0
Exp/Cntr=0.3,0.1

Type RM Length L Ch R = 1 ,7659    ,461,461,461
BEGIN DESCRIPTION:
Stream0693 12.0
END DESCRIPTION:
XS GIS Cut Line= 3
        2420125.       13694575.        2419325.       13694625.
      2418525.03     13695374.97
#Sta/Elev= 30
    4198  318.44  4348.3  313.41  4398.4  310.07  4428.4  306.04  4538.7  306.07
  4548.7  306.69  4578.7  313.07  4588.8   312.5  4608.8  305.12  4648.9  302.64
  4678.9  298.86  4849.3  296.43  4879.3   298.2    5003  298.41  5006.6  296.56
  5013.5  296.63  5015.9  294.35  5016.4  293.85  5025.7  294.35  5027.7  295.79
  5049.1  298.63  5070.2   298.3  5086.1  299.42    5120  302.28  5162.4   303.9
  5308.5  305.07  5355.8  305.24  5615.2  306.43  5820.4  308.95  6096.1  316.23
#Mann= 6 ,-1 , 0
    4198    .045       0  5015.9    .045       0  5025.7    .045       0
  5086.1     .07       0  5308.5     .12       0  5355.8     .07       0
Bank Sta=5015.9,5025.7
XS Rating Curve= 0 ,0
Exp/Cntr=0.3,0.1

Type RM Length L Ch R = 1 ,7198    ,430,430,430
BEGIN DESCRIPTION:
Stream0693 11.0
END DESCRIPTION:
XS GIS Cut Line= 3
      2419774.96     13694225.01        2419125.       13694325.
      2418324.98     13695125.02
#Sta/Elev= 30
  4347.3  309.02  4359.5  308.75  4559.7  305.37  4620.4  305.47  4644.8  303.95
    4752  301.54  4770.9  300.47  4802.6  300.36  4839.2  297.06  4913.8  296.04
  4984.7  296.57  5006.3  295.97    5019  295.39  5028.1  292.79  5028.6  292.29
  5038.2  292.79  5061.5  296.03  5132.2     298  5202.9  303.61  5330.2  304.58
  5358.5  304.14  5400.9  305.51    5415  304.76  5524.6  305.36  5659.9  306.15
  5895.9   309.1  5952.4  310.99    6009  311.57  6079.7  313.52  6136.3  315.89
#Mann= 8 ,-1 , 0
  4347.3     .07       0  4359.5     .05       0  4644.8    .045       0
  5006.3     .07       0  5028.1    .045       0  5038.2     .07       0
  5524.6     .12       0  5659.9     .07       0
Bank Sta=5028.1,5038.2
XS Rating Curve= 0 ,0
Exp/Cntr=0.3,0.1

Type RM Length L Ch R = 1 ,6768    ,471,471,471
BEGIN DESCRIPTION:
Stream0693 10.0
END DESCRIPTION:
XS GIS Cut Line= 3
      2419874.99       13693925.        2419075.       13693975.
        2418075.       13695175.
#Sta/Elev= 30
  4193.1  311.94  4455.4  305.97  4554.2  304.71    4655  303.26  4804.3  300.22
    4912  296.27  5001.8  295.96  5017.6  292.62  5018.1  292.12  5027.7  292.62
  5057.1  295.37  5178.8  295.12    5201  296.48  5221.8  300.56  5242.6  301.66
  5250.4  300.39  5256.9  301.63  5307.1  300.98  5328.5  302.98  5357.2  303.03
  5371.5  301.31  5435.3  304.35  5449.6  303.16  5770.7  305.56  5882.1  305.85
  6130.4  308.72  6358.2  316.09  6432.1  317.05    6477  318.09  6556.7  320.56
#Mann= 11 ,-1 , 0
  4193.1    .035       0  4455.4     .07       0  4554.2     .05       0
    4655    .045       0  5017.6    .045       0  5027.7    .045       0
  5057.1     .07       0  5770.7     .12       0  5882.1     .07       0
  6432.1    .035       0    6477     .07       0
Bank Sta=5017.6,5027.7
XS Rating Curve= 0 ,0
Exp/Cntr=0.3,0.1

Type RM Length L Ch R = 1 ,6297    ,488,488,488
BEGIN DESCRIPTION:
Stream0693 9.0
END DESCRIPTION:
XS GIS Cut Line= 3
      2419674.96     13693674.99        2419075.       13693575.
      2418174.99       13693775.
#Sta/Elev= 30
  4397.4  306.98  4406.4  306.84  4551.3  304.41  4833.3  301.86  4916.9  298.11
  4948.5  295.61  4965.1  295.31  4972.7  293.36  4977.8  294.51  4995.5  292.39
    4998  291.31  4998.5  290.81  5008.3  291.31  5015.9  294.28  5024.8  294.79
  5087.6  295.78  5150.2  294.49  5159.3   293.4    5163  294.32  5165.7  294.99
  5241.2  295.27  5301.4  296.69  5456.4  301.38  5539.6  301.79  5548.6  302.72
  5583.1  302.34  5626.7  303.91  5670.2  303.66  5876.4  307.29  5927.6  307.07
#Mann= 8 ,-1 , 0
  4397.4    .035       0  4406.4     .05       0  4551.3    .045       0
  4948.5     .07       0    4998     .05       0  5008.3     .07       0
  5150.2    .045       0    5163     .07       0
Bank Sta=4998,5008.3
XS Rating Curve= 0 ,0
Exp/Cntr=0.3,0.1

Type RM Length L Ch R = 1 ,5809    ,465,465,465
BEGIN DESCRIPTION:
Stream0693 8.0
END DESCRIPTION:
XS GIS Cut Line= 3
        2419875.       13692425.        2418675.       13693425.
      2418274.96     13693525.01
#Sta/Elev= 30
  3441.8  320.41  3512.7  319.23  3648.1  312.21  3732.7  311.03  3839.5  307.24
  4131.1  301.48  4185.8  301.56  4222.8   301.3  4258.6  298.95  4279.4  300.13
  4308.1  298.72  4421.3  300.22  4719.4  298.89  4769.5  297.77  4862.2  293.37
  4875.6  292.59  4904.3  293.53  4925.7  291.61  4932.9  292.91  4968.1  293.11
  4977.2  290.81  4977.7  290.31  4987.6  290.81  4990.2  293.19  5000.6  294.25
  5109.5   299.2  5167.3  299.63  5209.1   301.1  5323.4  305.48  5416.2   306.1
#Mann= 7 ,-1 , 0
  3441.8     .05       0  4185.8    .045       0  4862.2     .07       0
  4977.2     .05       0  4987.6     .07       0  5167.3      .1       0
  5209.1     .07       0
Bank Sta=4977.2,4987.6
XS Rating Curve= 0 ,0
Exp/Cntr=0.3,0.1