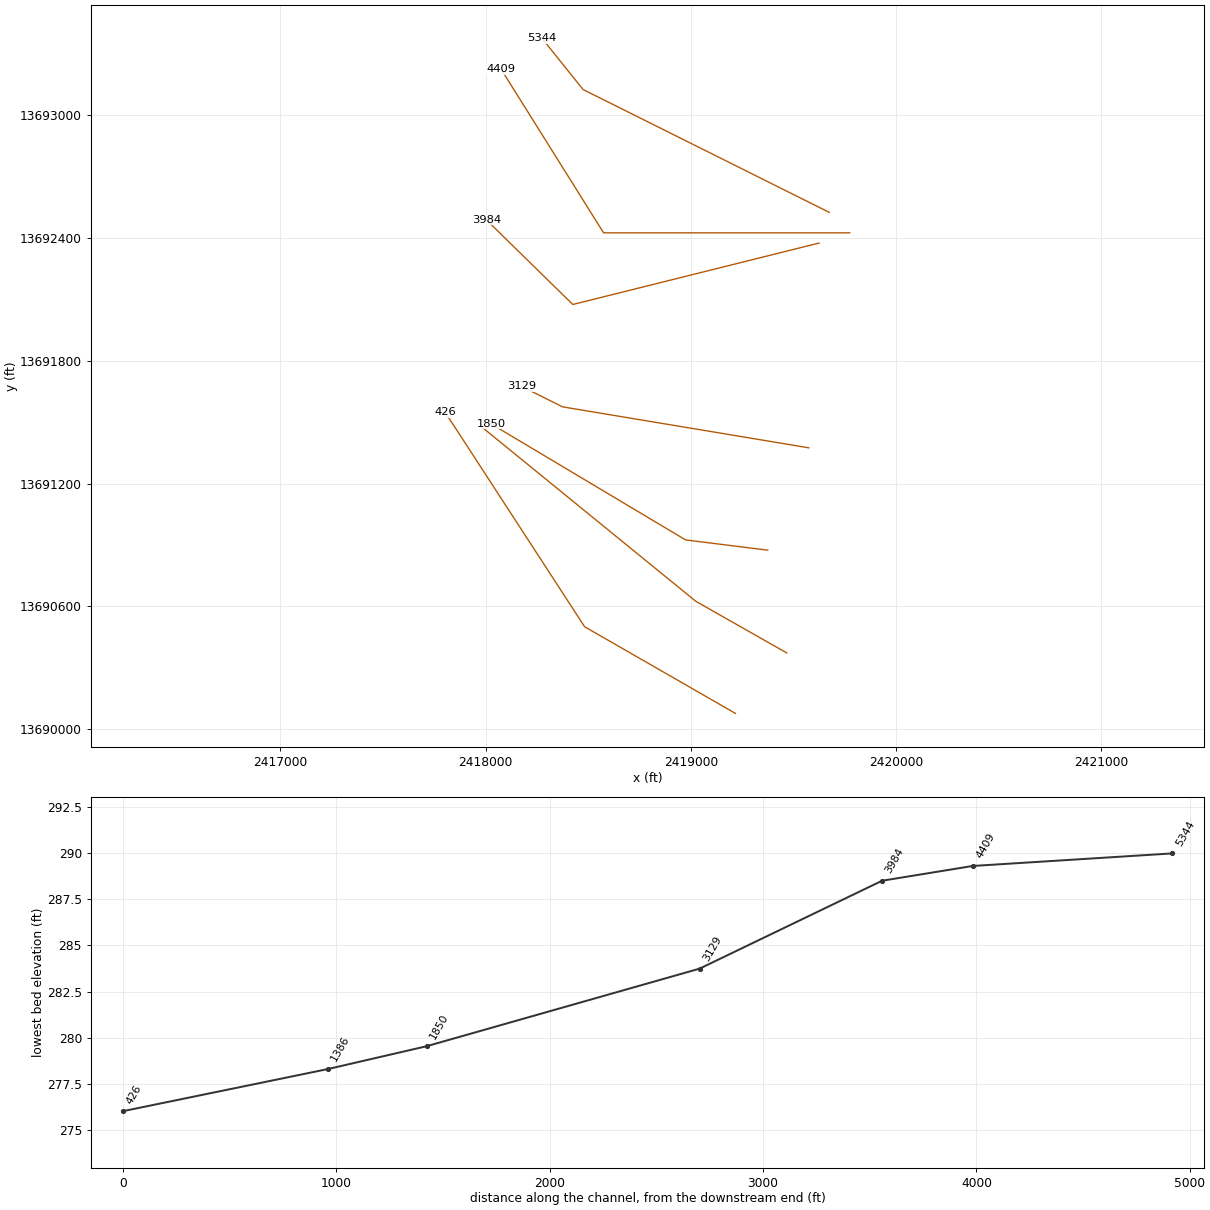
HEC-RAS study Stream0693.prj: Stream0693 Base Level Engineering

--- Stream0693.g01 (geometry) --- (continued)

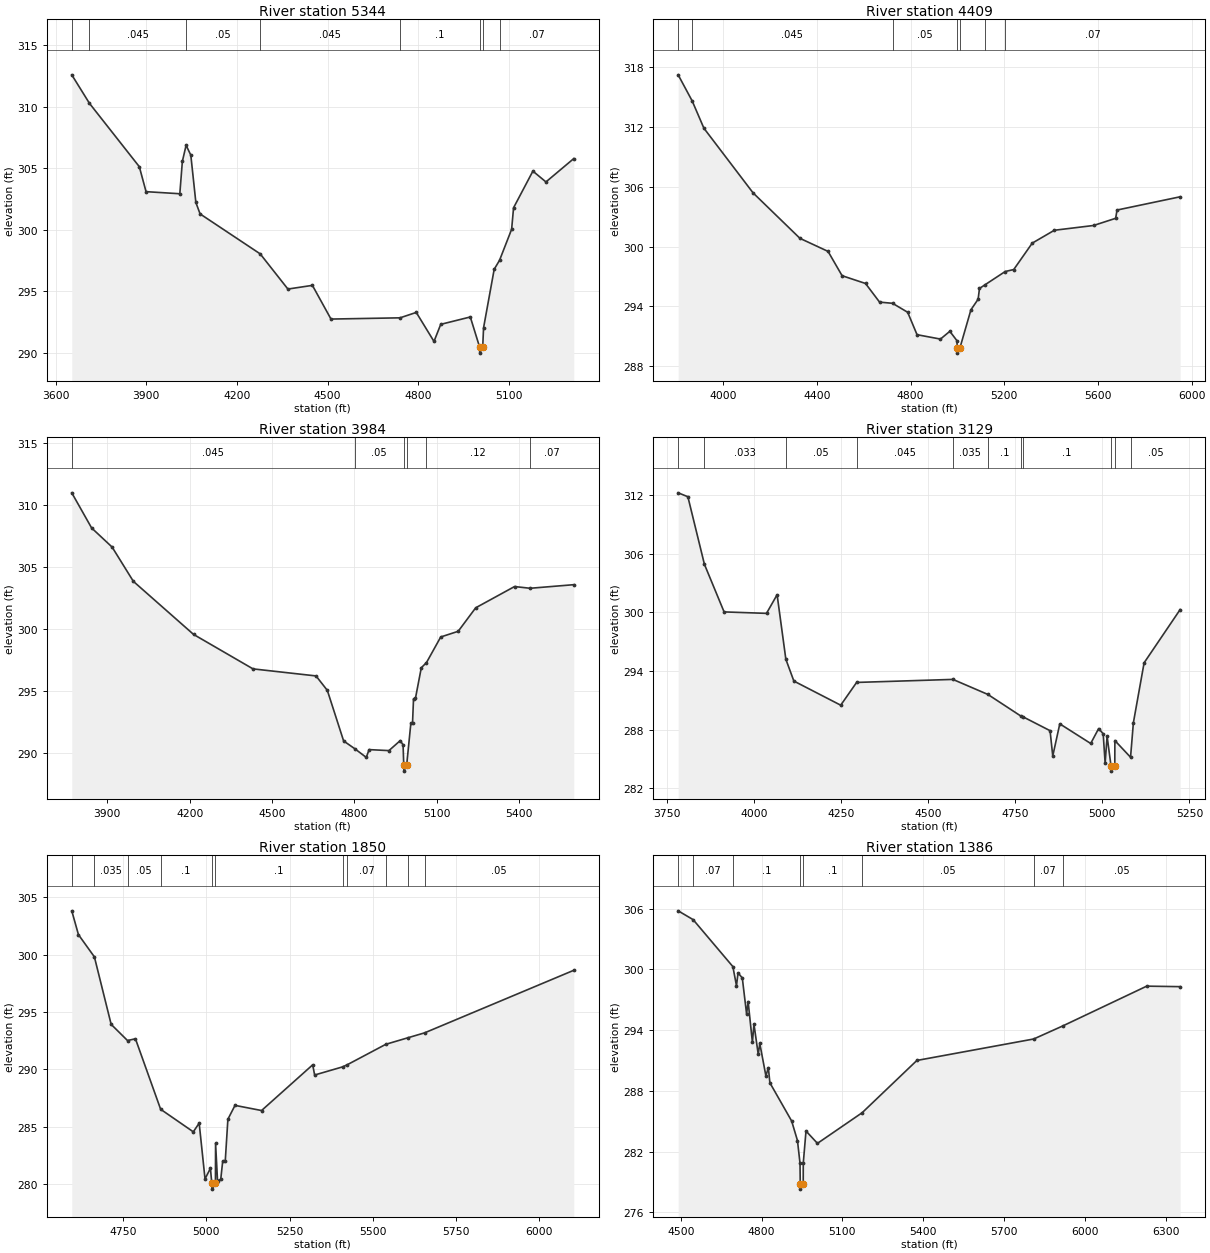
Type RM Length L Ch R = 1 ,5344    ,935,935,935
BEGIN DESCRIPTION:
Stream0693 7.0
END DESCRIPTION:
XS GIS Cut Line= 3
      2419674.97     13692525.01        2418475.       13693125.
      2418274.98     13693375.02
#Sta/Elev= 30
  3653.2  312.61  3711.8  310.29  3876.8  305.14  3899.1  303.11  4010.9  302.94
  4019.3  305.57  4031.7  306.88  4047.3  306.08    4064  302.23    4078   301.3
    4277  298.05  4368.7  295.19  4449.8  295.49  4511.3  292.75  4739.9  292.85
  4793.6  293.29  4852.3  290.93  4874.6  292.32  4972.5  292.92  5003.2  290.48
  5003.7  289.98  5013.6  290.48  5016.4  292.04  5051.6   296.8  5069.3  297.53
  5109.3  300.05  5115.7   301.8  5179.7  304.78  5222.9   303.9    5315   305.8
#Mann= 8 ,-1 , 0
  3653.2     .05       0  3711.8    .045       0  4031.7     .05       0
    4277    .045       0  4739.9      .1       0  5003.2     .05       0
  5013.6      .1       0  5069.3     .07       0
Bank Sta=5003.2,5013.6
XS Rating Curve= 0 ,0
Exp/Cntr=0.3,0.1

Type RM Length L Ch R = 1 ,4409    ,425,425,425
BEGIN DESCRIPTION:
Stream0693 6.0
END DESCRIPTION:
XS GIS Cut Line= 3
      2419774.97       13692425.        2418575.       13692425.
      2418074.98     13693225.02
#Sta/Elev= 30
  3807.6  317.23  3867.5  314.61  3917.6  311.87  4127.6  305.38  4327.6  300.82
  4447.6  299.51  4507.6  297.07  4607.6  296.29  4667.6  294.42  4723.1   294.3
  4787.6   293.4  4827.6  291.15  4927.6  290.71  4967.6  291.49  4997.6  290.56
  4999.8   289.8  5000.3   289.3  5010.4   289.8  5057.7  293.65  5088.4  294.71
  5094.2  295.79  5118.5  296.17    5204  297.49  5240.5  297.69  5319.5  300.34
  5413.8  301.63  5581.3  302.11  5675.6  302.83  5681.5  303.66    5951  304.99
#Mann= 7 ,-1 , 0
  3807.6     .05       0  3867.5    .045       0  4723.1     .05       0
  4999.8     .05       0  5010.4     .05       0  5118.5    .045       0
    5204     .07       0
Bank Sta=4999.8,5010.4
XS Rating Curve= 0 ,0
Exp/Cntr=0.3,0.1

Type RM Length L Ch R = 1 ,3984    ,855,855,855
BEGIN DESCRIPTION:
Stream0693 5.0
END DESCRIPTION:
XS GIS Cut Line= 3
      2419625.02       13692375.        2418425.       13692075.
      2418003.61     13692488.46
#Sta/Elev= 30
  3770.9  311.01  3843.1  308.17  3917.8  306.62  3995.1  303.85  4214.1  299.56
  4430.6  296.77    4660   296.2  4701.2  295.03  4760.5  290.94  4801.2  290.31
  4842.9  289.61  4853.2  290.24  4925.4  290.16  4966.6  290.97  4976.9  290.62
  4979.3     289  4979.8   288.5    4990     289  5005.3  292.39  5011.3  292.39
  5014.9  294.34  5021.9  294.39  5043.2  296.86  5062.1  297.28  5113.9  299.35
  5177.5  299.81  5241.2  301.71  5382.7  303.43  5439.3  303.29  5598.2  303.58
#Mann= 6 ,-1 , 0
  3770.9    .045       0  4801.2     .05       0  4979.3     .05       0
    4990     .05       0  5062.1     .12       0  5439.3     .07       0
Bank Sta=4979.3,4990
XS Rating Curve= 0 ,0
Exp/Cntr=0.3,0.1

Type RM Length L Ch R = 1 ,3129    ,1279,1279,1279
BEGIN DESCRIPTION:
Stream0693 4.0
END DESCRIPTION:
XS GIS Cut Line= 3
      2419575.03     13691374.99        2418375.       13691575.
      2418174.99       13691675.
#Sta/Elev= 30
  3783.1  312.23    3811  311.83  3858.5  304.91  3914.9  300.04  4036.6  299.89
    4067   301.8  4092.1  295.19  4115.1  292.96  4249.5  290.49  4295.1  292.82
  4571.4  293.13  4671.7  291.59  4767.5  289.35  4771.9  289.31  4850.1  287.88
  4857.8  285.29    4878  288.58  4966.7  286.57  4989.5   288.1  5002.5  287.56
  5008.1  284.55  5013.7  287.32  5025.1  284.24  5025.6  283.74  5035.8  284.24
    5036  286.87    5081  285.16  5089.1  288.69  5119.9  294.83  5223.3  300.28
#Mann= 11 ,-1 , 0
  3783.1     .05       0  3858.5    .033       0  4092.1     .05       0
  4295.1    .045       0  4571.4    .035       0  4671.7      .1       0
  4767.5    .035       0  4771.9      .1       0  5025.1     .05       0
  5035.8      .1       0    5081     .05       0
Bank Sta=5025.1,5035.8
XS Rating Curve= 0 ,0
Exp/Cntr=0.3,0.1

Type RM Length L Ch R = 1 ,1850    ,464,464,464
BEGIN DESCRIPTION:
Stream0693 3.0
END DESCRIPTION:
XS GIS Cut Line= 3
      2419374.95     13690875.01        2418975.       13690925.
      2418025.94      13691492.2
#Sta/Elev= 30
  4595.4  303.83  4615.5  301.75  4663.4  299.81  4713.8  293.92  4762.9  292.51
  4786.8  292.66  4862.5  286.51  4960.7  284.54  4978.3   285.3  4995.9  280.43
  5012.1  281.36  5016.3  280.04  5016.8  279.54  5027.2  280.04  5027.6  283.53
  5033.5  280.25  5043.2  280.41    5049  281.97  5056.7  281.99  5064.6  285.64
    5086  286.85  5165.8   286.4  5319.5  290.39  5325.3   289.5  5409.3  290.21
  5423.6   290.4  5539.2  292.18  5606.7  292.76  5655.8  293.18  6104.1  298.64
#Mann= 11 ,-1 , 0
  4595.4     .05       0  4663.4    .035       0  4762.9     .05       0
  4862.5      .1       0  5016.3     .05       0  5027.2      .1       0
  5409.3     .05       0  5423.6     .07       0  5539.2     .05       0
  5606.7     .07       0  5655.8     .05       0
Bank Sta=5016.3,5027.2
XS Rating Curve= 0 ,0
Exp/Cntr=0.3,0.1

Type RM Length L Ch R = 1 ,1386    ,960,960,960
BEGIN DESCRIPTION:
Stream0693 2.0
END DESCRIPTION:
XS GIS Cut Line= 3
      2419468.15     13690372.94        2419025.       13690625.
      2417976.46     13691480.53
#Sta/Elev= 30
  4490.4  305.79    4546  304.92  4693.5  300.28  4706.9  298.39  4712.6  299.66
  4728.5  299.16  4744.4   295.6  4750.1  296.83    4766   292.8  4771.7   294.6
  4787.6  291.62  4793.4  292.69  4816.1  289.48  4825.1   290.3  4830.9   288.8
  4911.6  285.03  4933.2   283.1  4942.7  280.85  4943.6   278.8  4944.1   278.3
  4954.6   278.8  4954.8  280.88  4964.9  284.04  5007.4  282.82  5173.4  285.85
  5376.4  291.01    5810  293.13  5917.9  294.42  6229.4  298.35  6353.5   298.3
#Mann= 8 ,-1 , 0
  4490.4     .05       0    4546     .07       0  4693.5      .1       0
  4943.6     .05       0  4954.6      .1       0  5173.4     .05       0
    5810     .07       0  5917.9     .05       0
Bank Sta=4943.6,4954.6
XS Rating Curve= 0 ,0
Exp/Cntr=0.3,0.1

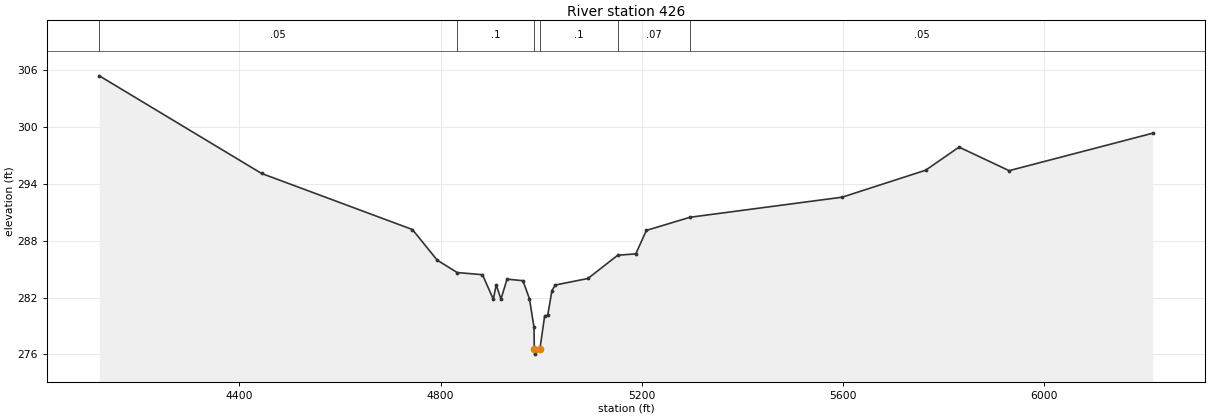
Type RM Length L Ch R = 1 ,426     ,0,0,0
BEGIN DESCRIPTION:
Stream0693 1.0
END DESCRIPTION:
XS GIS Cut Line= 3
      2419217.63     13690077.77      2418482.54     13690501.01
      2417803.19     13691547.88
#Sta/Elev= 30
  4121.1  305.42  4443.8  295.11  4744.2  289.18  4793.4  285.95  4833.2  284.64
  4883.5  284.41  4905.1  281.82  4910.9  283.34  4920.3  281.83  4932.4  283.94
    4964  283.78    4977  281.87    4986  278.88  4986.7  276.52  4987.2  276.02
  4997.7  276.52  5007.3  280.07  5013.3  280.11  5021.8  282.74  5028.4  283.32
  5093.3  284.01  5152.7  286.47  5188.6  286.61  5209.7  289.09  5296.6  290.48
  5599.3   292.6  5765.4  295.45  5831.9  297.89  5931.5   295.4  6217.3  299.36
#Mann= 6 ,-1 , 0
  4121.1     .05       0  4833.2      .1       0  4986.7     .05       0
  4997.7      .1       0  5152.7     .07       0  5296.6     .05       0
Bank Sta=4986.7,4997.7
XS Rating Curve= 0 ,0
Exp/Cntr=0.3,0.1

Chan Stop Cuts=-1
Use User Specified Reach Order=0
Composite Channel Slope=5