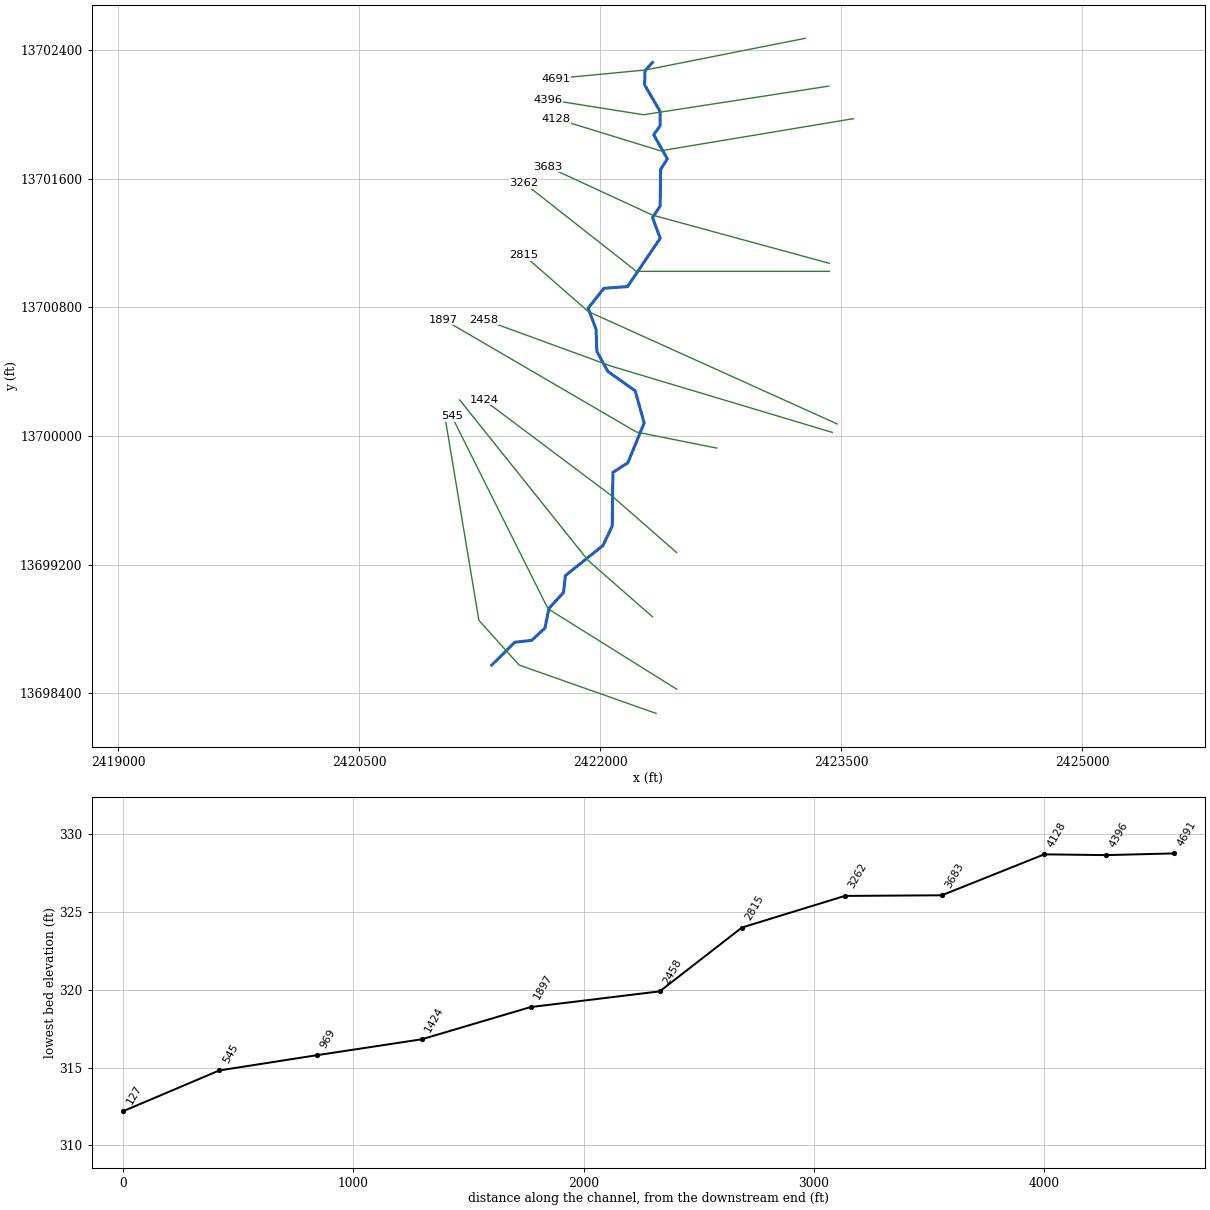
--- Stream0694.prj (project) ---

Proj Title=Stream0694 Base Level Engineering
Current Plan=p01
Default Exp/Contr=0.3,0.1
English Units
Geom File=g01
Flow File=f01
Plan File=p01
BEGIN DESCRIPTION:
Stream0694
END DESCRIPTION:

--- Stream0694.p01 (plan) ---

Plan Title=Multiple Run
Short Identifier=Multiple
Geom File=g01
Flow File=f01
Subcritical Flow
K Sum by GR= 0
Std Step Tol= 0.01
Critical Tol= 0.01
Num of Std Step Trials= 20
Max Error Tol= 0.3
Flow Tol Ratio= 0.001
Split Flow NTrial= 30
Split Flow Tol= 0.02
Split Flow Ratio= 0.02
Log Output Level= 0
Friction Slope Method= 1
Unsteady Friction Slope Method= 2
Unsteady Bridges Friction Slope Method= 1
Parabolic Critical Depth
Global Vel Dist=  1 , 1 , 1
Global Log Level= 0
CheckData=True
Encroach Param= -1, 0, 0, 0
BEGIN DESCRIPTION:
Multiple Run
END DESCRIPTION:

--- Stream0694.f01 (steady flow) ---

Flow Title=Multiple
Number of Profiles=7
Profile Names=10-year,25-year,50-year,1pct_min,100-year,1pct_plu,500-year
River Rch & RM= Stream0694,Reach-1,4691
     757    1224    1645    1070    2135    4260    3560
Boundary for River Rch & Prof#=Stream0694,Reach-1,1
Up Type=0
Dn Type=3
Dn Slope=0.005
Boundary for River Rch & Prof#=Stream0694,Reach-1,2
Up Type=0
Dn Type=3
Dn Slope=0.005
Boundary for River Rch & Prof#=Stream0694,Reach-1,3
Up Type=0
Dn Type=3
Dn Slope=0.005
Boundary for River Rch & Prof#=Stream0694,Reach-1,4
Up Type=0
Dn Type=3
Dn Slope=0.005
Boundary for River Rch & Prof#=Stream0694,Reach-1,5
Up Type=0
Dn Type=3
Dn Slope=0.005
Boundary for River Rch & Prof#=Stream0694,Reach-1,6
Up Type=0
Dn Type=3
Dn Slope=0.005
Boundary for River Rch & Prof#=Stream0694,Reach-1,7
Up Type=0
Dn Type=3
Dn Slope=0.005

--- Stream0694.g01 (geometry) ---

Geom Title=Existing Conditions

River Reach=Stream0694,Reach-1
Reach XY= 30
      2422325.00     13702325.00      2422278.19     13702273.60
      2422276.07     13702185.53      2422372.85     13702019.03
      2422372.63     13701930.89      2422332.53     13701874.99
      2422417.47     13701725.01      2422375.66     13701659.84
      2422372.71     13701430.93      2422325.10     13701359.60
      2422373.20     13701231.11      2422169.56     13700930.19
      2422022.54     13700919.54      2421924.33     13700795.08
      2421973.77     13700664.49      2421978.76     13700526.56
      2422047.99     13700401.48      2422217.26     13700281.45
      2422273.18     13700081.12      2422171.46     13699833.49
      2422078.48     13699773.74      2422074.49     13699440.21
      2422016.86     13699318.94      2421782.75     13699131.45
      2421771.37     13699026.50      2421680.54     13698927.42
      2421655.39     13698804.80      2421573.51     13698728.61
      2421468.83     13698717.14      2421325.00     13698575.00

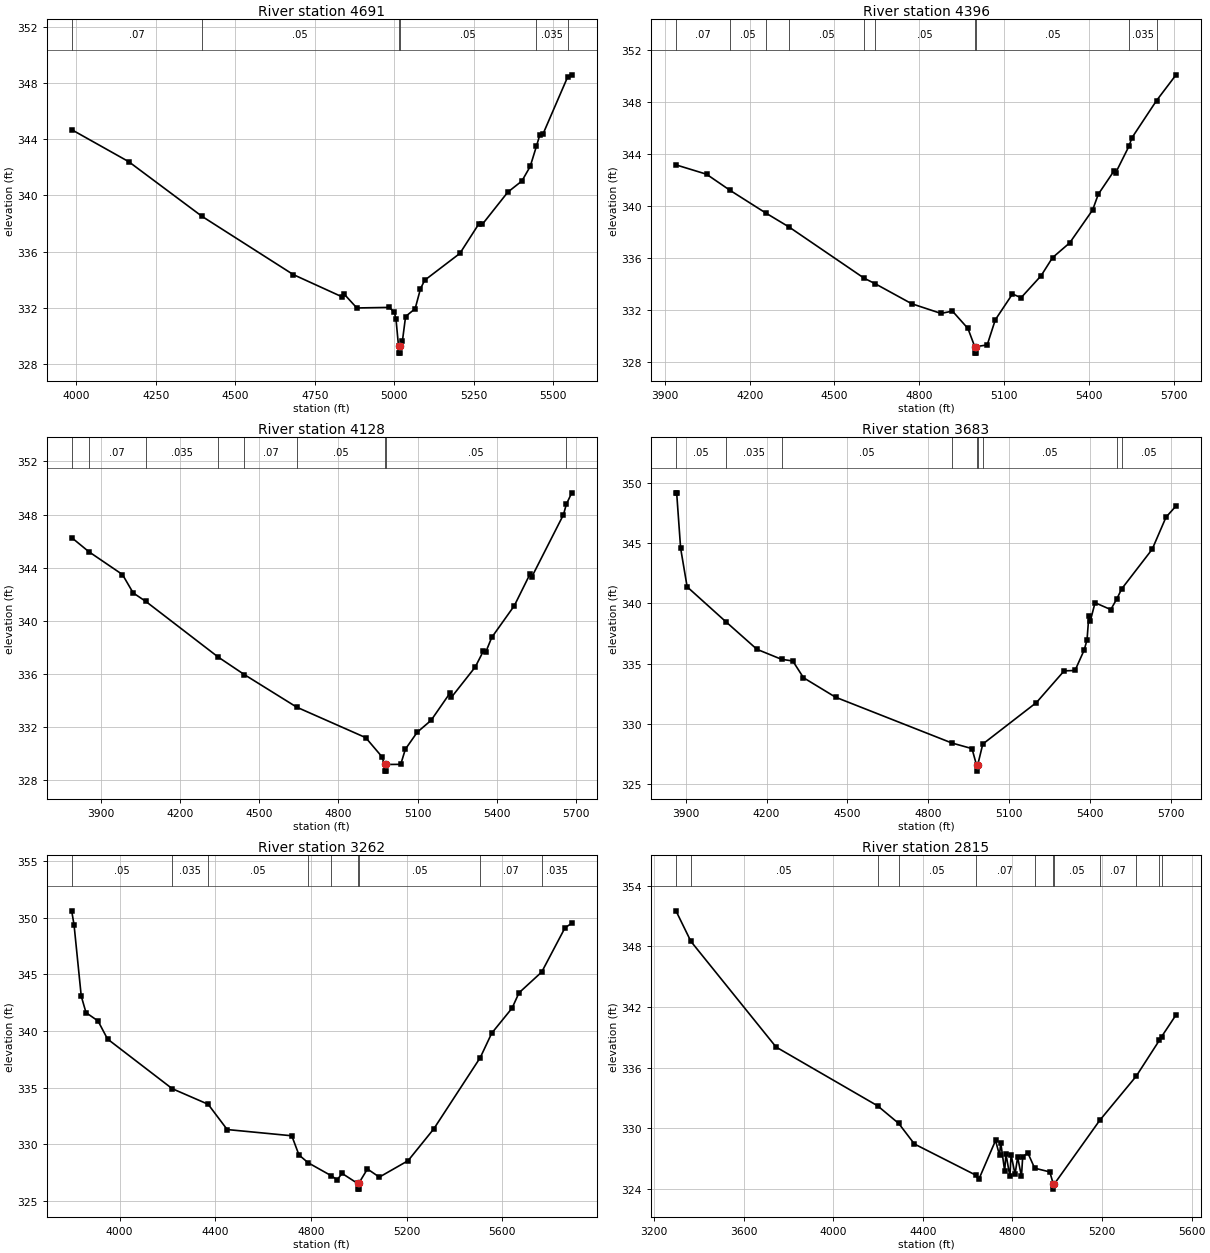
Type RM Length L Ch R = 1,4691,295,295,295
BEGIN DESCRIPTION:
Stream0694 10.0
END DESCRIPTION:
XS GIS Cut Line= 3
      2423274.98     13702475.00      2422280.30     13702277.96
      2421725.03     13702225.00
#Sta/Elev= 30
  3986.0  344.69  4165.2  342.41  4395.7  338.51  4682.5  334.36  4836.2  332.77
  4842.3  332.97  4882.3  331.98  4984.7  332.02  5000.0  331.67  5005.3  331.19
  5013.3  329.26  5013.6  328.76  5017.2  328.76  5017.4  329.26  5025.4  329.60
  5035.5  331.37  5065.6  331.93  5082.3  333.35  5095.7  333.96  5206.2  335.87
  5266.5  338.00  5276.6  337.94  5356.9  340.24  5401.0  341.03  5427.2  342.07
  5446.9  343.52  5457.4  344.32  5467.4  344.38  5545.5  348.48  5557.8  348.60
#Mann=6,-1,0
  3986.0    0.07       0  4395.7    0.05       0  5013.3    0.05       0
  5017.4    0.05       0  5446.9   0.035       0  5545.5    0.05       0
Bank Sta=5013.3,5017.4
Exp/Cntr=0.3,0.1

Type RM Length L Ch R = 1,4396,268,268,268
BEGIN DESCRIPTION:
XS7487
END DESCRIPTION:
XS GIS Cut Line= 3
      2423421.87     13702177.73      2422269.17     13701999.54
      2421673.34     13702094.20
#Sta/Elev= 30
  3939.3  343.16  4047.4  342.44  4130.5  341.20  4256.4  339.46  4340.3  338.36
  4605.5  334.42  4643.4  334.01  4773.2  332.46  4877.2  331.71  4917.7  331.89
  4972.5  330.55  4996.6  329.15  4996.8  328.65  5000.4  328.65  5000.7  329.15
  5040.7  329.28  5069.4  331.22  5130.2  333.21  5160.5  332.92  5231.2  334.61
  5271.9  336.01  5332.7  337.15  5413.7  339.68  5433.9  340.90  5490.3  342.72
  5495.4  342.55  5542.6  344.61  5552.6  345.24  5640.1  348.12  5709.0  350.10
#Mann=10,-1,0
  3939.3    0.07       0  4130.5    0.05       0  4256.4    0.07       0
  4340.3    0.05       0  4605.5    0.07       0  4643.4    0.05       0
  4996.6    0.05       0  5000.7    0.05       0  5542.6   0.035       0
  5640.1    0.05       0
Bank Sta=4996.6,5000.7
Exp/Cntr=0.3,0.1

Type RM Length L Ch R = 1,4128,445,445,445
BEGIN DESCRIPTION:
Stream0694 9.0
END DESCRIPTION:
XS GIS Cut Line= 3
      2423575.03     13701975.01      2422375.00     13701775.00
      2421724.96     13701975.01
#Sta/Elev= 30
  3788.3  346.27  3853.4  345.21  3981.0  343.49  4021.5  342.11  4069.4  341.47
  4344.2  337.28  4443.5  335.96  4642.1  333.51  4903.5  331.22  4964.3  329.80
  4974.9  329.20  4975.2  328.70  4978.8  328.70  4979.1  329.20  5036.3  329.21
  5053.9  330.35  5099.0  331.63  5151.4  332.52  5222.6  334.56  5227.9  334.24
  5318.8  336.53  5350.2  337.75  5358.7  337.65  5381.5  338.76  5467.2  341.15
  5527.4  343.56  5532.6  343.28  5653.6  348.00  5664.4  348.78  5685.0  349.64
#Mann=9,-1,0
  3788.3    0.05       0  3853.4    0.07       0  4069.4   0.035       0
  4344.2    0.05       0  4443.5    0.07       0  4642.1    0.05       0
  4974.9    0.05       0  4979.1    0.05       0  5664.4   0.035       0
Bank Sta=4974.9,4979.1
Exp/Cntr=0.3,0.1

Type RM Length L Ch R = 1,3683,421,421,421
BEGIN DESCRIPTION:
Stream0694 8.0
END DESCRIPTION:
XS GIS Cut Line= 3
      2423425.00     13701075.00      2422325.00     13701375.00
      2421674.97     13701675.01
#Sta/Elev= 30
  3863.7  349.19  3866.3  349.19  3881.0  344.59  3905.2  341.38  4049.5  338.47
  4164.3  336.19  4255.5  335.36  4297.3  335.22  4337.0  333.83  4456.2  332.21
  4887.3  328.41  4962.4  327.94  4979.3  326.57  4979.6  326.07  4983.5  326.57
  5002.5  328.32  5201.7  331.77  5304.5  334.40  5344.8  334.43  5378.8  336.13
  5389.4  336.98  5396.2  338.98  5401.7  338.56  5419.2  340.06  5477.5  339.49
  5499.5  340.36  5518.3  341.22  5631.2  344.50  5682.6  347.17  5719.8  348.10
#Mann=9,-1,0
  3863.7    0.05       0  4049.5   0.035       0  4255.5    0.05       0
  4887.3    0.07       0  4979.3    0.05       0  4983.5    0.07       0
  5002.5    0.05       0  5499.5    0.07       0  5518.3    0.05       0
Bank Sta=4979.3,4983.5
Exp/Cntr=0.3,0.1

Type RM Length L Ch R = 1,3262,447,447,447
BEGIN DESCRIPTION:
Stream0694 7.0
END DESCRIPTION:
XS GIS Cut Line= 3
      2423425.03     13701025.00      2422225.00     13701025.00
      2421524.96     13701575.03
#Sta/Elev= 30
  3799.8  350.60  3809.8  349.35  3839.8  343.07  3859.8  341.61  3909.8  340.88
  3949.8  339.28  4219.9  334.90  4370.3  333.52  4449.8  331.29  4719.8  330.74
  4749.8  329.05  4788.0  328.36  4884.2  327.22  4909.8  326.85  4929.8  327.42
  4995.1  326.53  4995.4  326.03  4999.2  326.03  4999.5  326.53  5036.0  327.81
  5085.7  327.09  5205.9  328.54  5313.4  331.35  5507.8  337.65  5555.6  339.80
  5640.6  342.01  5669.5  343.36  5764.5  345.20  5862.0  349.11  5890.1  349.50
#Mann=9,-1,0
  3799.8    0.05       0  4219.9   0.035       0  4370.3    0.05       0
  4788.0    0.07       0  4884.2    0.05       0  4995.1    0.05       0
  4999.5    0.05       0  5507.8    0.07       0  5764.5   0.035       0
Bank Sta=4995.1,4999.5
Exp/Cntr=0.3,0.1

Type RM Length L Ch R = 1,2815,357,357,357
BEGIN DESCRIPTION:
Stream0694 6.0
END DESCRIPTION:
XS GIS Cut Line= 3
      2423474.96     13700075.02      2421925.00     13700775.00
      2421525.00     13701125.00
#Sta/Elev= 30
  3298.2  351.50  3364.9  348.48  3745.1  338.04  4198.4  332.23  4292.5  330.49
  4362.5  328.46  4635.8  325.39  4649.9  324.96  4724.8  328.81  4742.4  327.34
  4747.9  328.60  4765.5  325.77  4771.0  327.49  4788.7  325.26  4794.1  327.39
  4811.8  325.47  4823.3  327.16  4840.4  325.25  4845.9  327.21  4869.0  327.57
  4899.3  326.07  4967.0  325.70  4982.4  324.50  4982.7  324.00  4986.8  324.50
  5189.5  330.79  5352.6  335.16  5456.0  338.71  5466.3  339.08  5530.4  341.22
#Mann=12,-1,0
  3298.2    0.07       0  3364.9    0.05       0  4198.4   0.035       0
  4292.5    0.05       0  4635.8    0.07       0  4899.3    0.05       0
  4982.4    0.05       0  4986.8    0.05       0  5189.5    0.07       0
  5352.6    0.05       0  5456.0    0.07       0  5466.3    0.05       0
Bank Sta=4982.4,4986.8
Exp/Cntr=0.3,0.1

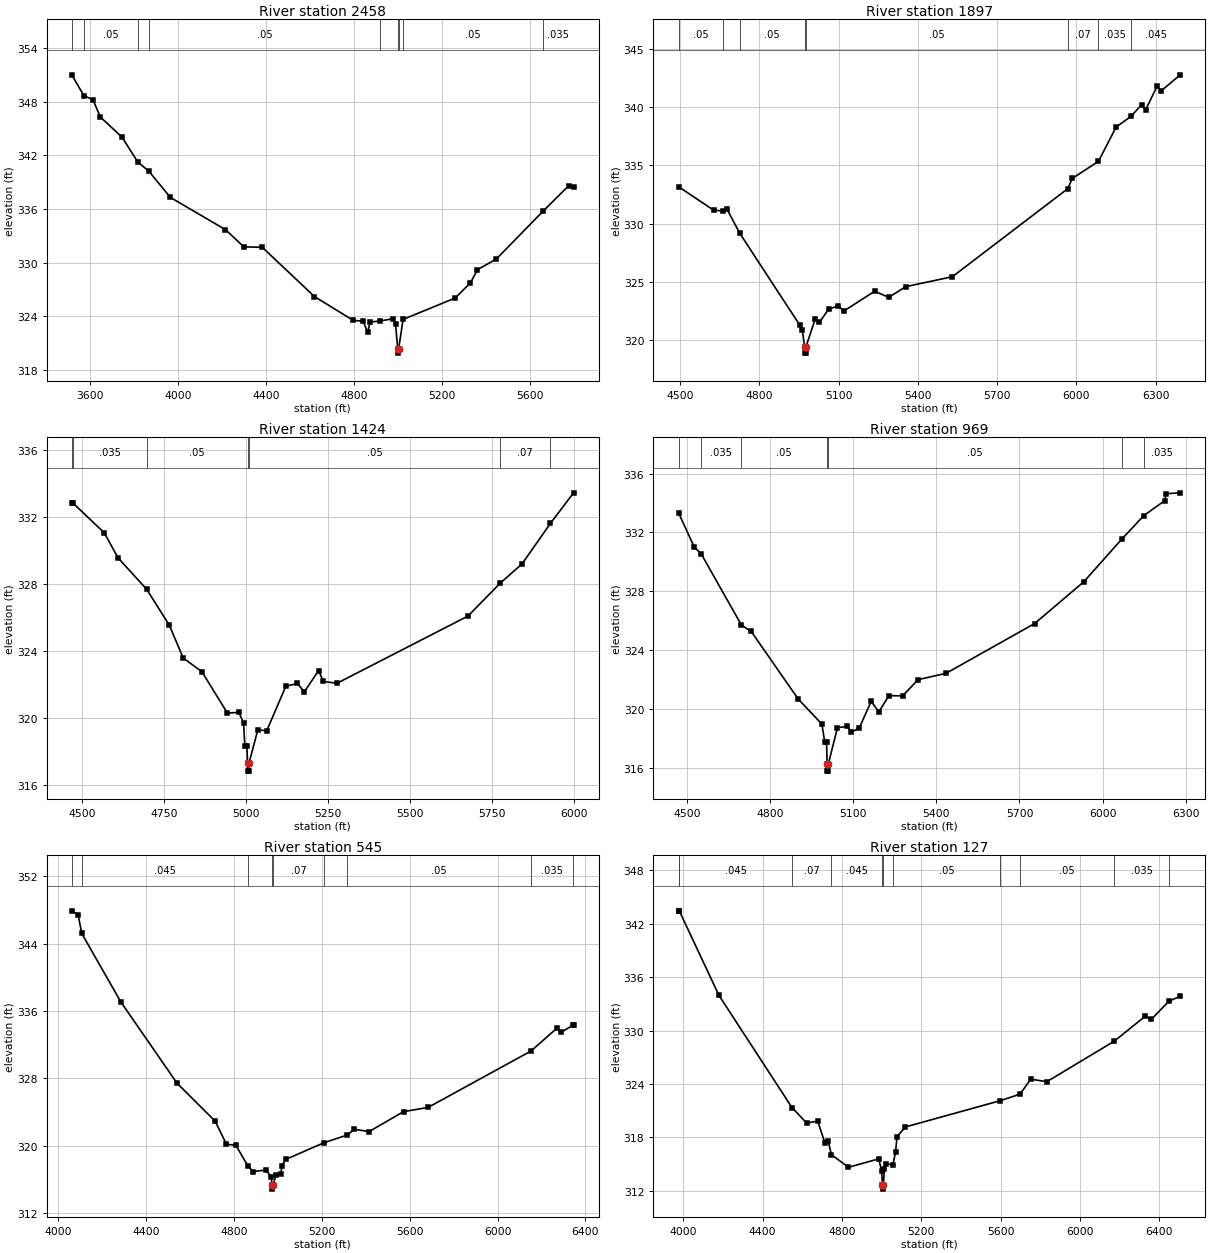
Type RM Length L Ch R = 1,2458,561,561,561
BEGIN DESCRIPTION:
Stream0694 5.0
END DESCRIPTION:
XS GIS Cut Line= 3
      2423444.09     13700022.71      2422068.70     13700434.77
      2421274.99     13700725.00
#Sta/Elev= 30
  3517.5  351.02  3572.3  348.70  3614.2  348.22  3647.2  346.31  3746.2  344.04
  3817.9  341.26  3867.8  340.25  3965.8  337.31  4216.0  333.71  4299.5  331.79
  4383.7  331.73  4620.5  326.23  4796.3  323.57  4842.3  323.47  4862.5  322.21
  4873.6  323.37  4920.0  323.50  4978.5  323.75  4989.2  323.19  4999.1  320.40
  4999.4  319.90  5003.6  320.40  5023.5  323.67  5260.2  326.06  5329.9  327.76
  5361.8  329.24  5447.0  330.41  5660.5  335.79  5777.1  338.64  5798.4  338.51
#Mann=9,-1,0
  3517.5    0.07       0  3572.3    0.05       0  3817.9    0.07       0
  3867.8    0.05       0  4920.0    0.07       0  4999.1    0.05       0
  5003.6    0.07       0  5023.5    0.05       0  5660.5   0.035       0
Bank Sta=4999.1,5003.6
Exp/Cntr=0.3,0.1

Type RM Length L Ch R = 1,1897,473,473,473
BEGIN DESCRIPTION:
Stream0694 4.0
END DESCRIPTION:
XS GIS Cut Line= 3
      2422725.04     13699924.99      2422225.00     13700025.00
      2421024.99     13700725.01
#Sta/Elev= 30
  4494.4  333.16  4627.0  331.15  4663.5  331.08  4678.0  331.22  4726.3  329.16
  4953.3  321.29  4963.5  320.83  4971.4  319.39  4971.7  318.89  4975.7  318.89
  4976.1  319.39  5012.2  321.85  5027.5  321.54  5062.2  322.64  5098.2  322.96
  5120.1  322.50  5237.1  324.20  5290.0  323.67  5354.5  324.59  5530.7  325.44
  5967.7  332.99  5984.7  333.87  6083.6  335.33  6150.9  338.28  6206.4  339.18
  6246.8  340.18  6262.5  339.76  6305.5  341.77  6321.2  341.38  6393.6  342.75
#Mann=8,-1,0
  4494.4    0.05       0  4663.5   0.035       0  4726.3    0.05       0
  4971.4    0.05       0  4976.1    0.05       0  5967.7    0.07       0
  6083.6   0.035       0  6206.4   0.045       0
Bank Sta=4971.4,4976.1
Exp/Cntr=0.3,0.1

Type RM Length L Ch R = 1,1424,455,455,455
BEGIN DESCRIPTION:
Stream0694 3.0
END DESCRIPTION:
XS GIS Cut Line= 3
      2422474.98     13699275.02      2422075.00     13699625.00
      2421274.98     13700225.01
#Sta/Elev= 30
  4468.5  332.86  4473.2  332.82  4567.7  331.06  4610.4  329.55  4696.9  327.69
  4766.0  325.55  4808.7  323.58  4865.7  322.76  4943.5  320.29  4978.6  320.33
  4992.9  319.69  4996.7  318.32  5003.1  318.32  5004.9  317.32  5005.2  316.82
  5009.3  316.82  5009.7  317.32  5036.4  319.29  5063.5  319.23  5121.9  321.89
  5157.3  322.06  5178.1  321.55  5221.9  322.83  5236.4  322.18  5278.1  322.07
  5678.1  326.09  5775.4  328.04  5842.7  329.20  5929.3  331.62  6000.0  333.45
#Mann=7,-1,0
  4468.5    0.05       0  4473.2   0.035       0  4696.9    0.05       0
  5004.9    0.05       0  5009.7    0.05       0  5775.4    0.07       0
  5929.3    0.05       0
Bank Sta=5004.9,5009.7
Exp/Cntr=0.3,0.1

Type RM Length L Ch R = 1,969,424,424,424
BEGIN DESCRIPTION:
Stream0694 2.0
END DESCRIPTION:
XS GIS Cut Line= 3
      2422325.03     13698874.97      2421925.00     13699225.00
      2421124.98     13700225.02
#Sta/Elev= 30
  4468.7  333.33  4525.2  331.02  4551.1  330.53  4695.9  325.71  4731.2  325.28
  4901.1  320.69  4986.5  318.99  4996.9  317.75  5003.4  317.75  5005.1  316.30
  5005.4  315.80  5009.5  315.80  5009.9  316.30  5042.7  318.75  5077.9  318.83
  5092.3  318.45  5121.1  318.71  5164.3  320.53  5192.3  319.83  5228.4  320.92
  5278.0  320.91  5334.0  322.01  5434.9  322.44  5755.0  325.82  5932.7  328.66
  6068.6  331.53  6149.4  333.15  6224.0  334.15  6230.4  334.63  6280.9  334.69
#Mann=7,-1,0
  4468.7   0.045       0  4551.1   0.035       0  4695.9    0.05       0
  5005.1    0.05       0  5009.9    0.05       0  6068.6    0.07       0
  6149.4   0.035       0
Bank Sta=5005.1,5009.9
Exp/Cntr=0.3,0.1

Type RM Length L Ch R = 1,545,418,418,418
BEGIN DESCRIPTION:
Stream0694 1.0
END DESCRIPTION:
XS GIS Cut Line= 3
      2422475.03     13698424.98      2421675.00     13698925.00
      2421074.99     13700125.03
#Sta/Elev= 30
  4060.6  347.90  4089.5  347.45  4106.1  345.21  4284.7  337.05  4540.0  327.41
  4713.3  322.91  4765.2  320.15  4807.7  320.04  4862.8  317.57  4886.7  316.91
  4945.1  317.09  4968.7  316.27  4972.7  315.32  4973.0  314.82  4977.6  315.32
  4990.5  316.48  5012.4  316.66  5018.0  317.60  5034.8  318.35  5207.1  320.31
  5315.7  321.26  5347.8  321.93  5414.9  321.66  5571.4  324.03  5683.2  324.53
  6151.5  331.23  6270.2  333.95  6287.0  333.44  6344.4  334.32  6345.7  334.32
#Mann=9,-1,0
  4060.6   0.035       0  4106.1   0.045       0  4862.8    0.07       0
  4972.7    0.05       0  4977.6    0.07       0  5207.1   0.035       0
  5315.7    0.05       0  6151.5   0.035       0  6344.4   0.045       0
Bank Sta=4972.7,4977.6
Exp/Cntr=0.3,0.1

Type RM Length L Ch R = 1,127,0,0,0
BEGIN DESCRIPTION:
XS7488
END DESCRIPTION:
XS GIS Cut Line= 4
      2422347.17     13698274.15      2421495.14     13698574.87
      2421244.55     13698853.30      2421038.51     13700089.51
#Sta/Elev= 30
  3975.7  343.44  3980.1  343.41  4179.5  333.95  4547.9  321.36  4621.9  319.62
  4677.9  319.83  4714.7  317.34  4730.9  317.59  4746.8  316.07  4833.1  314.65
  4985.9  315.60  5000.1  314.25  5004.4  312.70  5004.8  312.20  5009.3  312.70
  5014.0  314.47  5021.1  315.05  5056.7  314.95  5070.4  316.33  5077.9  318.09
  5120.5  319.18  5599.0  322.13  5698.3  322.86  5752.3  324.54  5833.7  324.26
  6174.1  328.81  6330.2  331.61  6360.6  331.25  6449.7  333.30  6507.1  333.85
#Mann=11,-1,0
  3975.7   0.035       0  3980.1   0.045       0  4547.9    0.07       0
  4746.8   0.045       0  5004.4   0.045       0  5009.3   0.045       0
  5056.7    0.05       0  5599.0   0.035       0  5698.3    0.05       0
  6174.1   0.035       0  6449.7   0.045       0
Bank Sta=5004.4,5009.3
Exp/Cntr=0.3,0.1

Chan Stop Cuts=-1