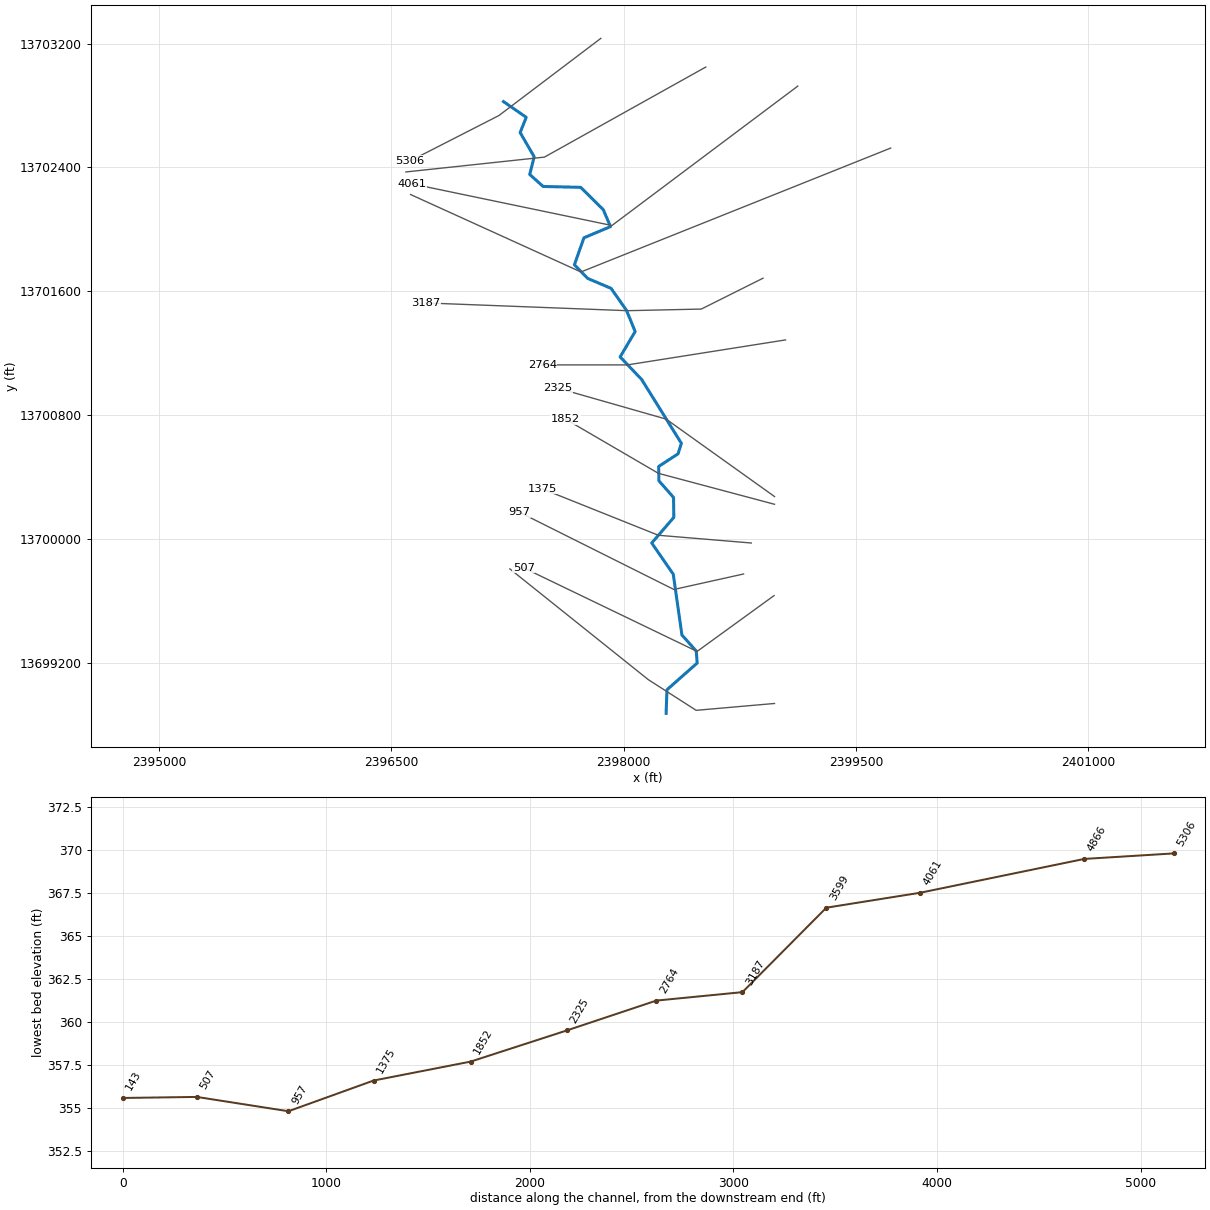
--- Stream0695.prj (project) ---

Proj Title=Stream0695 Base Level Engineering
Current Plan=p01
Default Exp/Contr=0.3,0.1
English Units
Geom File=g01
Flow File=f01
Plan File=p01
BEGIN DESCRIPTION:
Stream0695
END DESCRIPTION:

--- Stream0695.p01 (plan) ---

Plan Title=Multiple Run
Short Identifier=Multiple
Geom File=g01
Flow File=f01
Subcritical Flow
K Sum by GR= 0
Std Step Tol= 0.01
Critical Tol= 0.01
Num of Std Step Trials= 20
Max Error Tol= 0.3
Flow Tol Ratio= 0.001
Split Flow NTrial= 30
Split Flow Tol= 0.02
Split Flow Ratio= 0.02
Log Output Level= 0
Friction Slope Method= 1
Unsteady Friction Slope Method= 2
Unsteady Bridges Friction Slope Method= 1
Parabolic Critical Depth
Global Vel Dist=  1 , 1 , 1
Global Log Level= 0
CheckData=True
Encroach Param= -1, 0, 0, 0
BEGIN DESCRIPTION:
Multiple Run
END DESCRIPTION:

--- Stream0695.f01 (steady flow) ---

Flow Title=Multiple
Number of Profiles=7
Profile Names=10-year,25-year,50-year,1pct_min,100-year,1pct_plu,500-year
River Rch & RM= Stream0695,Reach-1,5306
     801    1312    1780    1168    2331    4650    3962
River Rch & RM= Stream0695,Reach-1,4061
    1021    1684    2296    1513    3020    6025    5177
Boundary for River Rch & Prof#=Stream0695,Reach-1,1
Up Type=0
Dn Type=3
Dn Slope=0.005
Boundary for River Rch & Prof#=Stream0695,Reach-1,2
Up Type=0
Dn Type=3
Dn Slope=0.005
Boundary for River Rch & Prof#=Stream0695,Reach-1,3
Up Type=0
Dn Type=3
Dn Slope=0.005
Boundary for River Rch & Prof#=Stream0695,Reach-1,4
Up Type=0
Dn Type=3
Dn Slope=0.005
Boundary for River Rch & Prof#=Stream0695,Reach-1,5
Up Type=0
Dn Type=3
Dn Slope=0.005
Boundary for River Rch & Prof#=Stream0695,Reach-1,6
Up Type=0
Dn Type=3
Dn Slope=0.005
Boundary for River Rch & Prof#=Stream0695,Reach-1,7
Up Type=0
Dn Type=3
Dn Slope=0.005

--- Stream0695.g01 (geometry) ---

Geom Title=Existing Conditions

River Reach=Stream0695,Reach-1
Reach XY= 30
      2397225.00     13702825.00      2397371.94     13702723.57
      2397332.56     13702625.00      2397423.16     13702468.88
      2397394.28     13702354.92      2397480.83     13702277.06
      2397723.54     13702271.46      2397869.20     13702127.29
      2397916.03     13702017.94      2397744.43     13701945.64
      2397682.79     13701771.57      2397768.91     13701683.14
      2397919.39     13701619.41      2398019.16     13701477.29
      2398075.05     13701340.34      2397978.10     13701176.65
      2398116.84     13701031.05      2398373.43     13700618.91
      2398352.45     13700551.17      2398226.89     13700469.29
      2398228.47     13700376.50      2398322.94     13700269.14
      2398324.64     13700140.16      2398182.08     13699975.00
      2398321.25     13699773.45      2398377.08     13699380.86
      2398469.59     13699277.42      2398475.54     13699199.88
      2398280.42     13699027.48      2398275.00     13698875.00

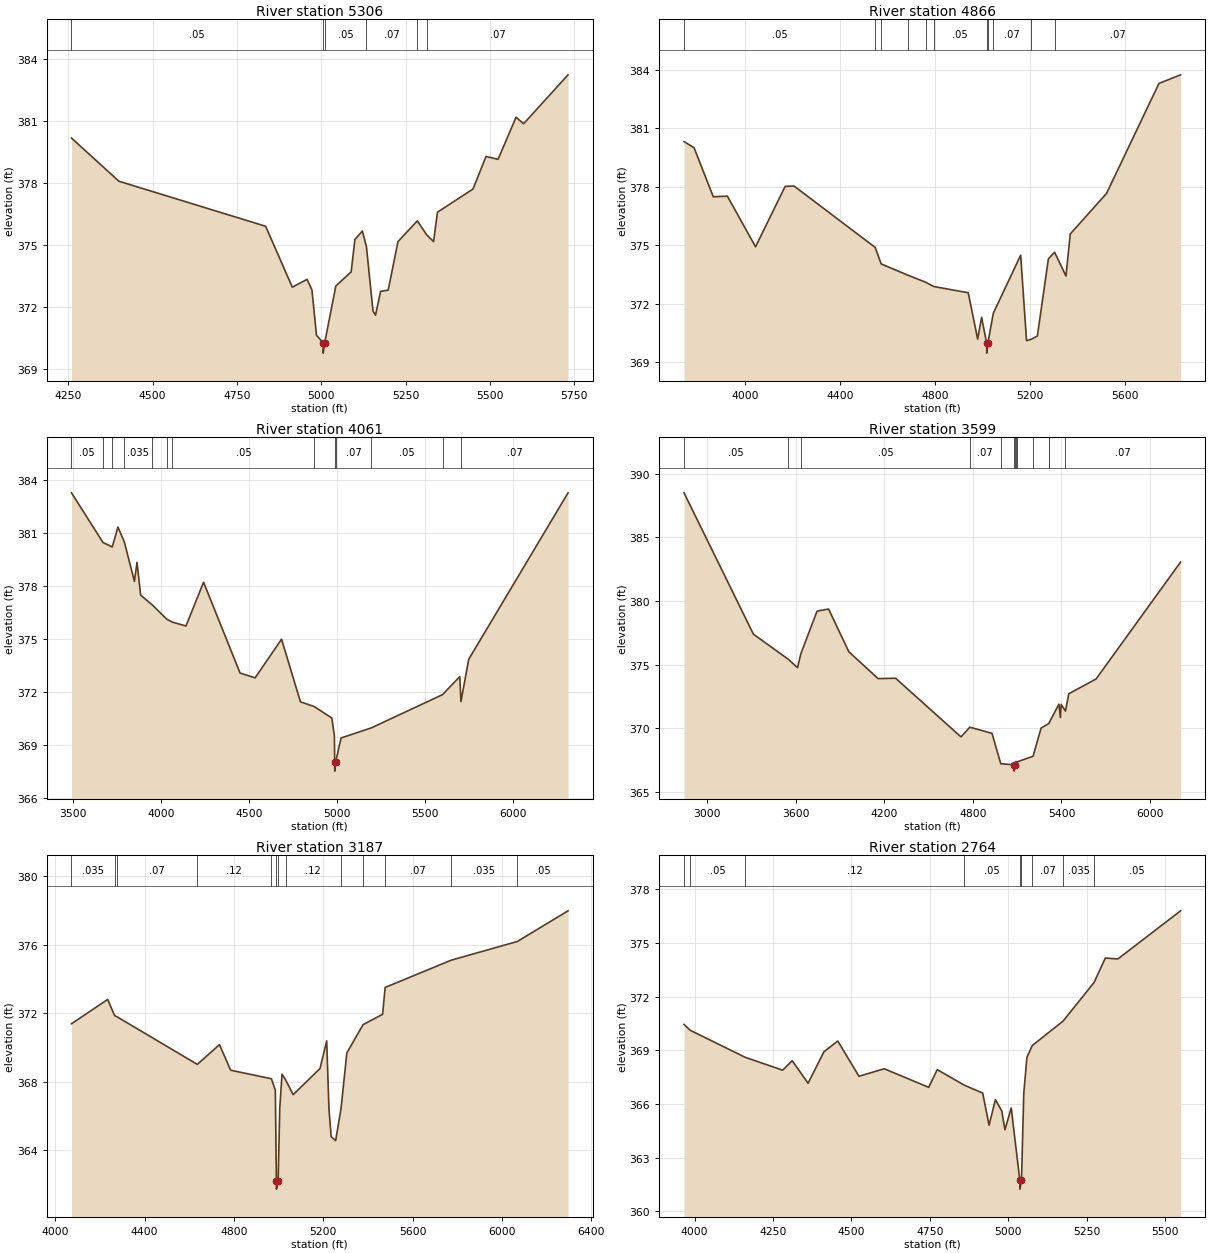
Type RM Length L Ch R = 1,5306,440,440,440
BEGIN DESCRIPTION:
XS7490
END DESCRIPTION:
XS GIS Cut Line= 3
      2397853.74     13703233.50      2397195.53     13702735.05
      2396620.35     13702441.07
#Sta/Elev= 30
  4259.9  380.19  4400.4  378.10  4835.3  375.92  4914.3  372.97  4958.0  373.35
  4972.5  372.84  4985.9  370.65  5005.5  370.28  5005.8  369.78  5010.3  370.28
  5043.3  373.03  5088.7  373.71  5099.8  375.28  5122.0  375.69  5134.0  374.93
  5153.5  371.81  5160.9  371.62  5176.0  372.77  5198.5  372.83  5227.5  375.18
  5284.9  376.18  5313.3  375.49  5333.0  375.18  5344.4  376.60  5449.7  377.72
  5488.5  379.30  5524.1  379.16  5577.4  381.20  5599.6  380.88  5731.5  383.25
#Mann=6,-1,0
  4259.9    0.05       0  5005.5    0.05       0  5010.3    0.05       0
  5134.0    0.07       0  5284.9   0.035       0  5313.3    0.07       0
Bank Sta=5005.5,5010.3
Exp/Cntr=0.3,0.1

Type RM Length L Ch R = 1,4866,805,805,805
BEGIN DESCRIPTION:
Stream0695 10.0
END DESCRIPTION:
XS GIS Cut Line= 3
      2398531.14     13703048.17      2397489.49     13702466.64
      2396594.79     13702370.78
#Sta/Elev= 30
  3742.0  380.32  3784.2  380.01  3865.3  377.49  3924.7  377.52  4043.5  374.92
  4168.1  378.02  4205.8  378.04  4547.4  374.89  4573.0  374.04  4684.0  373.47
  4760.4  373.10  4794.9  372.88  4939.8  372.56  4979.7  370.18  4996.1  371.30
  5017.6  369.96  5017.9  369.46  5022.4  369.96  5045.6  371.51  5160.8  374.49
  5185.5  370.10  5205.2  370.17  5231.2  370.34  5277.7  374.30  5303.8  374.64
  5351.8  373.42  5369.9  375.58  5522.8  377.66  5743.7  383.31  5834.8  383.75
#Mann=11,-1,0
  3742.0    0.05       0  4547.4    0.07       0  4573.0    0.05       0
  4684.0    0.07       0  4760.4   0.035       0  4794.9    0.05       0
  5017.6    0.05       0  5022.4    0.05       0  5045.6    0.07       0
  5205.2   0.035       0  5303.8    0.07       0
Bank Sta=5017.6,5022.4
Exp/Cntr=0.3,0.1

Type RM Length L Ch R = 1,4061,462,462,462
BEGIN DESCRIPTION:
Stream0695 9.0
END DESCRIPTION:
XS GIS Cut Line= 3
      2399125.03     13702925.02      2397925.00     13702025.00
      2396633.17     13702294.09
#Sta/Elev= 30
  3492.3  383.28  3671.4  380.46  3723.7  380.21  3755.9  381.34  3791.9  380.51
  3849.6  378.26  3864.2  379.34  3885.0  377.48  3951.8  376.92  4032.7  376.12
  4065.1  375.95  4142.3  375.73  4242.3  378.21  4449.6  373.06  4535.0  372.79
  4685.0  374.98  4792.3  371.43  4870.9  371.16  4970.5  370.51  4985.0  369.51
  4986.7  368.00  4987.1  367.50  4991.8  368.00  5023.0  369.38  5194.4  369.95
  5599.6  371.84  5697.1  372.86  5703.7  371.44  5747.8  373.84  6311.9  383.28
#Mann=13,-1,0
  3492.3    0.05       0  3671.4   0.035       0  3723.7    0.05       0
  3791.9   0.035       0  3951.8    0.05       0  4032.7   0.035       0
  4065.1    0.05       0  4870.9    0.07       0  4986.7    0.05       0
  4991.8    0.07       0  5194.4    0.05       0  5599.6   0.035       0
  5703.7    0.07       0
Bank Sta=4986.7,4991.8
Exp/Cntr=0.3,0.1

Type RM Length L Ch R = 1,3599,412,412,412
BEGIN DESCRIPTION:
Stream0695 8.0
END DESCRIPTION:
XS GIS Cut Line= 3
      2399725.02     13702525.01      2397725.00     13701725.00
      2396625.00     13702225.00
#Sta/Elev= 30
  2844.3  388.50  3314.2  377.39  3548.1  375.44  3613.1  374.76  3635.8  375.87
  3745.0  379.20  3823.1  379.37  3960.4  376.01  4158.3  373.90  4276.8  373.93
  4719.7  369.32  4779.6  370.08  4929.7  369.60  4989.2  367.21  5079.3  367.13
  5079.7  366.63  5084.5  367.13  5092.4  367.39  5098.3  367.35  5207.9  367.80
  5262.0  370.01  5316.1  370.38  5317.5  370.45  5382.9  371.89  5392.7  370.85
  5398.2  371.87  5427.0  371.35  5449.9  372.71  5634.4  373.87  6206.7  383.06
#Mann=13,-1,0
  2844.3    0.05       0  3548.1   0.035       0  3635.8    0.05       0
  4779.6    0.07       0  4989.2   0.035       0  5079.3   0.035       0
  5084.5   0.035       0  5092.4    0.07       0  5098.3    0.12       0
  5207.9   0.035       0  5316.1    0.07       0  5317.5   0.035       0
  5427.0    0.07       0
Bank Sta=5079.3,5084.5
Exp/Cntr=0.3,0.1

Type RM Length L Ch R = 1,3187,423,423,423
BEGIN DESCRIPTION:
Stream0695 7.0
END DESCRIPTION:
XS GIS Cut Line= 4
      2398900.62     13701684.73      2398502.19     13701485.51
      2398025.00     13701475.00      2396725.03     13701525.00
#Sta/Elev= 30
  4072.4  371.38  4234.6  372.80  4265.4  371.86  4274.6  371.80  4635.9  369.01
  4735.1  370.16  4785.1  368.67  4967.7  368.17  4985.2  367.50  4990.0  362.23
  4990.4  361.73  4995.4  362.23  4997.7  362.23  5005.2  366.47  5015.2  368.44
  5031.1  368.11  5065.2  367.24  5185.3  368.77  5215.3  370.38  5225.3  366.40
  5235.3  364.79  5255.4  364.56  5279.8  366.47  5305.4  369.68  5378.4  371.33
  5465.5  371.93  5477.1  373.50  5772.9  375.09  6068.8  376.18  6296.1  377.97
#Mann=13,-1,0
  4072.4   0.035       0  4265.4    0.12       0  4274.6    0.07       0
  4635.9    0.12       0  4967.7    0.05       0  4990.0    0.05       0
  4995.4    0.05       0  5031.1    0.12       0  5279.8    0.07       0
  5378.4   0.035       0  5477.1    0.07       0  5772.9   0.035       0
  6068.8    0.05       0
Bank Sta=4990,4995.4
Exp/Cntr=0.3,0.1

Type RM Length L Ch R = 1,2764,439,439,439
BEGIN DESCRIPTION:
Stream0695 6.0
END DESCRIPTION:
XS GIS Cut Line= 3
      2399045.76     13701286.29      2398025.00     13701125.00
      2397475.02     13701125.00
#Sta/Elev= 30
  3966.2  370.45  3986.1  370.12  4161.4  368.61  4280.8  367.89  4311.2  368.42
  4361.8  367.16  4412.4  368.92  4456.5  369.52  4524.0  367.55  4604.8  367.97
  4746.5  366.93  4773.6  367.92  4860.3  367.05  4918.6  366.61  4938.9  364.81
  4959.1  366.24  4979.4  365.61  4989.5  364.56  5009.6  365.78  5036.9  361.74
  5037.3  361.24  5042.3  361.74  5049.6  366.60  5059.6  368.61  5076.8  369.27
  5175.2  370.64  5273.6  372.79  5309.6  374.16  5349.6  374.11  5549.6  376.80
#Mann=9,-1,0
  3966.2    0.12       0  3986.1    0.05       0  4161.4    0.12       0
  4860.3    0.05       0  5036.9    0.05       0  5042.3    0.05       0
  5076.8    0.07       0  5175.2   0.035       0  5273.6    0.05       0
Bank Sta=5036.9,5042.3
Exp/Cntr=0.3,0.1

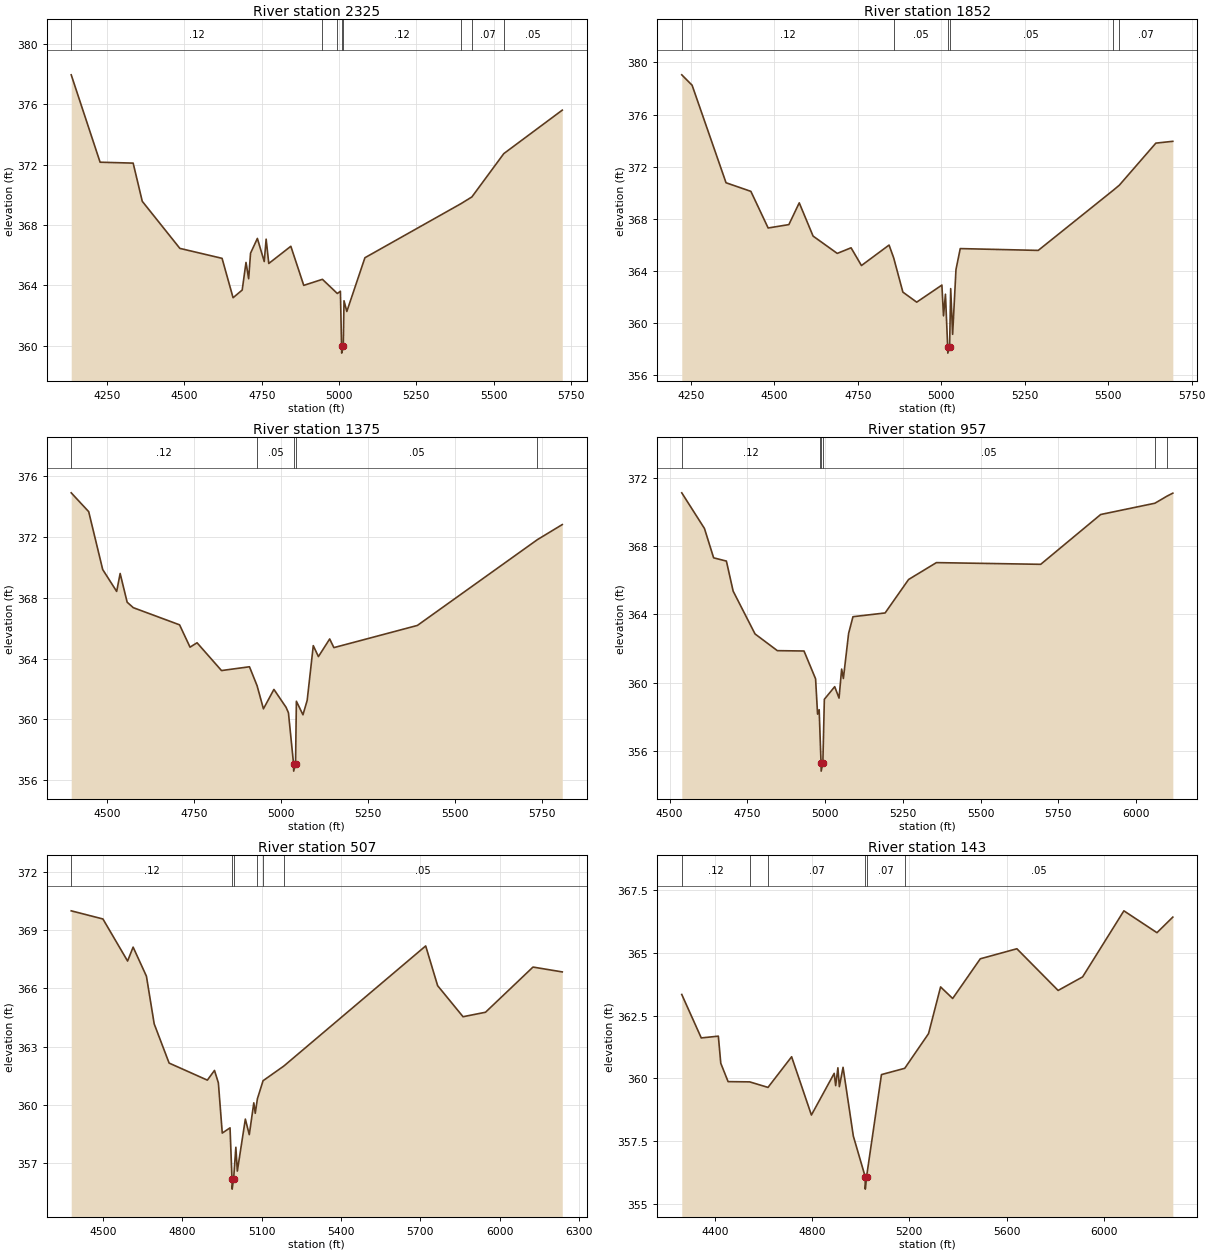
Type RM Length L Ch R = 1,2325,473,473,473
BEGIN DESCRIPTION:
Stream0695 5.0
END DESCRIPTION:
XS GIS Cut Line= 3
      2398974.99     13700275.01      2398275.00     13700775.00
      2397575.02     13700974.99
#Sta/Elev= 30
  4133.7  377.95  4227.1  372.16  4334.0  372.10  4363.5  369.57  4485.1  366.45
  4621.6  365.79  4657.2  363.18  4686.7  363.69  4699.0  365.52  4707.6  364.44
  4713.7  366.13  4735.8  367.11  4758.0  365.58  4764.1  367.06  4772.7  365.45
  4844.0  366.59  4885.8  364.00  4946.2  364.40  4994.4  363.46  5004.3  363.61
  5008.1  360.01  5008.5  359.51  5013.6  360.01  5016.0  362.98  5025.1  362.27
  5083.6  365.83  5394.0  369.41  5429.6  369.86  5532.8  372.73  5721.9  375.61
#Mann=8,-1,0
  4133.7    0.12       0  4946.2    0.05       0  4994.4    0.12       0
  5008.1    0.05       0  5013.6    0.12       0  5394.0   0.035       0
  5429.6    0.07       0  5532.8    0.05       0
Bank Sta=5008.1,5013.6
Exp/Cntr=0.3,0.1

Type RM Length L Ch R = 1,1852,477,477,477
BEGIN DESCRIPTION:
Stream0695 4.0
END DESCRIPTION:
XS GIS Cut Line= 3
      2398974.98     13700225.01      2398225.00     13700425.00
      2397625.01     13700774.99
#Sta/Elev= 30
  4222.8  379.05  4253.8  378.25  4355.4  370.77  4429.8  370.11  4481.5  367.30
  4543.6  367.56  4574.7  369.23  4616.1  366.68  4688.5  365.35  4729.9  365.78
  4761.0  364.42  4843.7  365.99  4857.5  365.01  4885.1  362.38  4926.5  361.61
  5001.9  362.92  5006.8  360.56  5012.6  362.22  5019.2  358.20  5019.7  357.70
  5025.0  358.20  5028.3  362.65  5034.1  359.14  5044.1  364.11  5056.9  365.72
  5290.5  365.58  5514.5  370.18  5533.3  370.58  5642.8  373.81  5693.6  373.95
#Mann=6,-1,0
  4222.8    0.12       0  4857.5    0.05       0  5019.2    0.05       0
  5025.0    0.05       0  5514.5   0.035       0  5533.3    0.07       0
Bank Sta=5019.2,5025
Exp/Cntr=0.3,0.1

Type RM Length L Ch R = 1,1375,418,418,418
BEGIN DESCRIPTION:
Stream0695 3.0
END DESCRIPTION:
XS GIS Cut Line= 3
      2398825.04     13699975.00      2398225.00     13700025.00
      2397474.99     13700325.00
#Sta/Elev= 30
  4397.5  374.92  4447.7  373.68  4487.9  369.87  4528.0  368.43  4538.0  369.61
  4558.1  367.72  4575.7  367.36  4708.6  366.23  4738.7  364.76  4758.8  365.05
  4829.0  363.22  4909.3  363.47  4931.2  362.22  4949.4  360.70  4979.5  361.98
  5014.4  360.80  5021.2  360.44  5035.8  357.10  5036.2  356.60  5041.6  357.10
  5044.0  361.20  5062.9  360.31  5075.0  361.26  5092.5  364.86  5107.3  364.14
  5139.6  365.30  5151.7  364.73  5391.4  366.19  5736.1  371.84  5807.4  372.83
#Mann=5,-1,0
  4397.5    0.12       0  4931.2    0.05       0  5035.8    0.05       0
  5041.6    0.05       0  5736.1   0.035       0
Bank Sta=5035.8,5041.6
Exp/Cntr=0.3,0.1

Type RM Length L Ch R = 1,957,450,450,450
BEGIN DESCRIPTION:
Stream0695 2.0
END DESCRIPTION:
XS GIS Cut Line= 3
      2398775.04     13699775.01      2398325.00     13699675.00
      2397325.04     13700174.98
#Sta/Elev= 30
  4539.0  371.13  4612.0  369.04  4641.5  367.32  4682.5  367.13  4704.2  365.37
  4774.6  362.86  4846.4  361.88  4932.1  361.86  4969.3  360.23  4975.7  358.16
  4980.8  358.42  4984.8  356.35  4986.8  355.32  4987.3  354.82  4992.7  355.32
  4997.5  359.03  5030.8  359.77  5044.7  359.10  5053.1  360.80  5058.7  360.25
  5075.5  362.89  5089.5  363.87  5192.9  364.09  5268.3  366.05  5357.8  367.04
  5693.2  366.94  5886.1  369.86  6060.3  370.52  6100.7  370.95  6118.0  371.11
#Mann=6,-1,0
  4539.0    0.12       0  4984.8    0.05       0  4986.8    0.05       0
  4992.7    0.05       0  6060.3   0.035       0  6100.7    0.05       0
Bank Sta=4986.8,4992.7
Exp/Cntr=0.3,0.1

Type RM Length L Ch R = 1,507,364,364,364
BEGIN DESCRIPTION:
Stream0695 1.0
END DESCRIPTION:
XS GIS Cut Line= 3
      2398972.09     13699635.59      2398475.00     13699275.00
      2397355.31     13699814.53
#Sta/Elev= 30
  4379.7  370.00  4499.6  369.58  4592.9  367.41  4613.8  368.13  4664.1  366.63
  4693.5  364.17  4749.9  362.15  4894.5  361.27  4921.5  361.77  4936.2  361.13
  4950.9  358.54  4980.3  358.81  4987.8  356.15  4988.3  355.65  4993.7  356.15
  5002.3  357.81  5007.9  356.58  5038.2  359.26  5053.1  358.46  5070.2  360.10
  5075.7  359.56  5083.8  360.31  5105.2  361.24  5184.1  362.00  5720.2  368.19
  5765.4  366.14  5861.4  364.54  5946.4  364.77  6126.0  367.10  6236.7  366.85
#Mann=6,-1,0
  4379.7    0.12       0  4987.8    0.05       0  4993.7    0.12       0
  5083.8    0.07       0  5105.2    0.12       0  5184.1    0.05       0
Bank Sta=4987.8,4993.7
Exp/Cntr=0.3,0.1

Type RM Length L Ch R = 1,143,0,0,0
BEGIN DESCRIPTION:
XS7489
END DESCRIPTION:
XS GIS Cut Line= 4
      2398974.90     13698938.94      2398468.99     13698894.71
      2398160.51     13699092.40      2397265.81     13699808.16
#Sta/Elev= 30
  4263.8  363.34  4344.0  361.61  4414.3  361.68  4424.3  360.60  4454.4  359.87
  4543.2  359.86  4618.5  359.64  4715.7  360.86  4797.1  358.54  4890.9  360.20
  4896.9  359.71  4906.1  360.42  4912.1  359.67  4927.3  360.44  4969.6  357.70
  5018.2  356.09  5018.7  355.59  5024.1  356.09  5085.2  360.15  5181.0  360.40
  5278.9  361.78  5328.5  363.64  5378.2  363.18  5491.8  364.76  5642.3  365.16
  5812.0  363.50  5912.8  364.04  6082.5  366.67  6218.6  365.80  6283.8  366.42
#Mann=6,-1,0
  4263.8    0.12       0  4543.2   0.035       0  4618.5    0.07       0
  5018.2    0.05       0  5024.1    0.07       0  5181.0    0.05       0
Bank Sta=5018.2,5024.1
Exp/Cntr=0.3,0.1

Chan Stop Cuts=-1