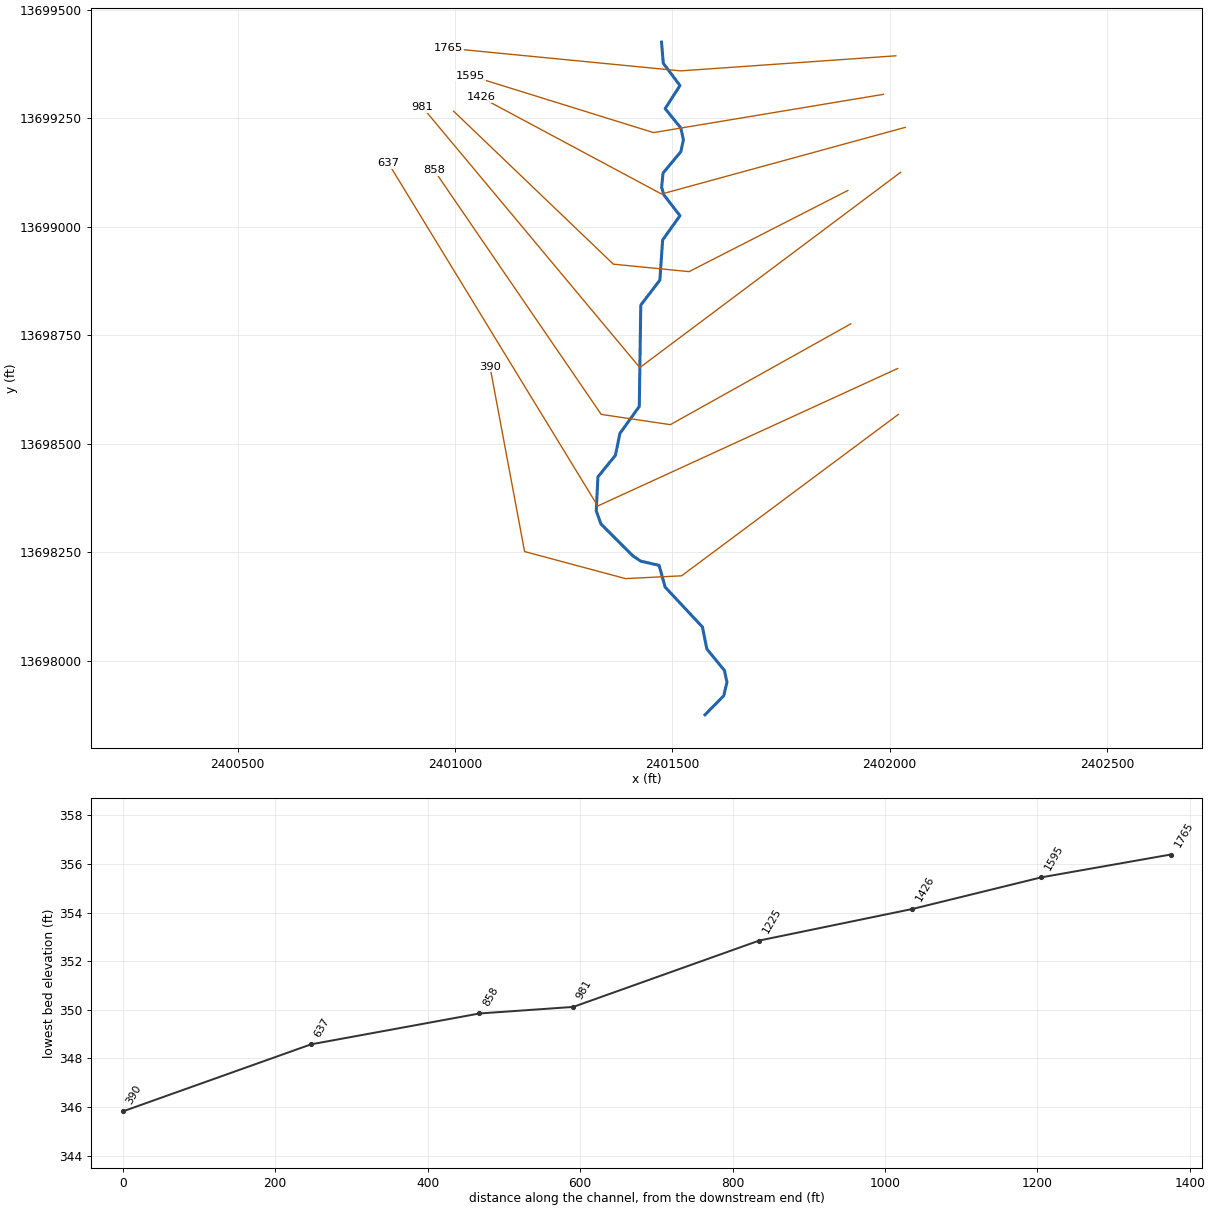
--- Stream0697.prj (project) ---

Proj Title=Stream0697 Base Level Engineering
Current Plan=p01
Default Exp/Contr=0.3,0.1
English Units
Geom File=g01
Flow File=f01
Plan File=p01
BEGIN DESCRIPTION:
Stream0697
END DESCRIPTION:

--- Stream0697.p01 (plan) ---

Plan Title=Multiple Run
Short Identifier=Multiple
Geom File=g01
Flow File=f01
Subcritical Flow
K Sum by GR= 0
Std Step Tol= 0.01
Critical Tol= 0.01
Num of Std Step Trials= 20
Max Error Tol= 0.3
Flow Tol Ratio= 0.001
Split Flow NTrial= 30
Split Flow Tol= 0.02
Split Flow Ratio= 0.02
Log Output Level= 0
Friction Slope Method= 1
Unsteady Friction Slope Method= 2
Unsteady Bridges Friction Slope Method= 1
Parabolic Critical Depth
Global Vel Dist=  1 , 1 , 1
Global Log Level= 0
CheckData=True
Encroach Param= -1, 0, 0, 0
BEGIN DESCRIPTION:
Multiple Run
END DESCRIPTION:

--- Stream0697.f01 (steady flow) ---

Flow Title=Multiple
Number of Profiles=7
Profile Names=10-year,25-year,50-year,1pct_min,100-year,1pct_plu,500-year
River Rch & RM= Stream0697,Reach-1,1765
     230     346     443     276     551    1099     841
Boundary for River Rch & Prof#=Stream0697,Reach-1,1
Up Type=0
Dn Type=3
Dn Slope=0.005
Boundary for River Rch & Prof#=Stream0697,Reach-1,2
Up Type=0
Dn Type=3
Dn Slope=0.005
Boundary for River Rch & Prof#=Stream0697,Reach-1,3
Up Type=0
Dn Type=3
Dn Slope=0.005
Boundary for River Rch & Prof#=Stream0697,Reach-1,4
Up Type=0
Dn Type=3
Dn Slope=0.005
Boundary for River Rch & Prof#=Stream0697,Reach-1,5
Up Type=0
Dn Type=3
Dn Slope=0.005
Boundary for River Rch & Prof#=Stream0697,Reach-1,6
Up Type=0
Dn Type=3
Dn Slope=0.005
Boundary for River Rch & Prof#=Stream0697,Reach-1,7
Up Type=0
Dn Type=3
Dn Slope=0.005

--- Stream0697.g01 (geometry) ---

Geom Title=Existing Conditions

River Reach=Stream0697,Reach-1
Reach XY= 30
      2401475.00     13699425.00      2401478.98     13699376.36
      2401517.43     13699324.94      2401483.30     13699271.77
      2401519.37     13699227.30      2401525.31     13699200.03
      2401519.56     13699172.81      2401478.43     13699123.27
      2401475.23     13699090.34      2401480.65     13699072.71
      2401517.41     13699025.01      2401477.55     13698969.11
      2401471.15     13698876.60      2401427.26     13698819.06
      2401423.80     13698585.50      2401379.19     13698523.26
      2401368.88     13698472.82      2401328.67     13698423.41
      2401324.79     13698345.05      2401335.43     13698315.19
      2401408.48     13698241.72      2401427.00     13698229.12
      2401469.38     13698219.38      2401483.30     13698169.26
      2401569.16     13698077.29      2401579.24     13698026.73
      2401619.67     13697977.23      2401625.62     13697950.06
      2401618.06     13697918.85      2401575.00     13697875.00

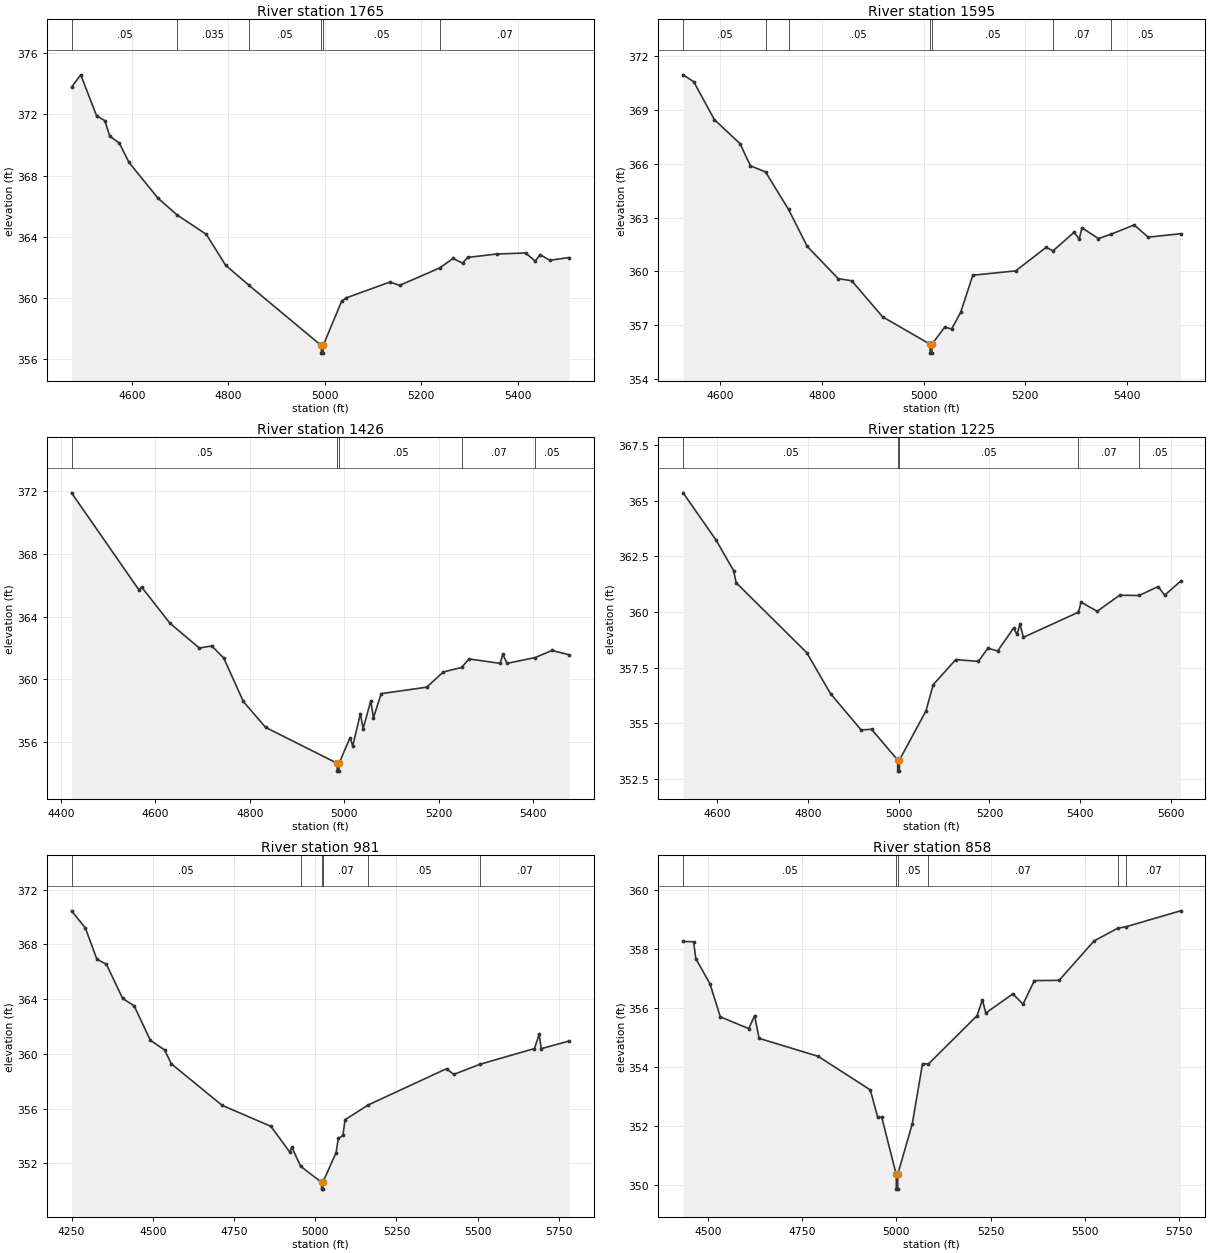
Type RM Length L Ch R = 1,1765,170,170,170
BEGIN DESCRIPTION:
XS7491
END DESCRIPTION:
XS GIS Cut Line= 3
      2402014.02     13699393.49      2401519.18     13699358.77
      2400985.37     13699410.85
#Sta/Elev= 30
  4474.3  373.78  4493.4  374.59  4526.3  371.91  4543.5  371.59  4553.5  370.59
  4573.6  370.12  4593.6  368.86  4653.8  366.52  4694.1  365.41  4754.0  364.16
  4794.1  362.14  4841.7  360.85  4992.6  356.89  4992.9  356.39  4996.4  356.39
  4996.6  356.89  5034.8  359.78  5044.9  360.01  5135.3  361.04  5155.4  360.82
  5239.0  361.97  5265.9  362.58  5286.0  362.28  5296.6  362.65  5356.4  362.87
  5416.6  362.94  5436.7  362.41  5446.8  362.83  5466.9  362.46  5506.7  362.64
#Mann=6,-1,0
  4474.3    0.05       0  4694.1   0.035       0  4841.7    0.05       0
  4992.6    0.05       0  4996.6    0.05       0  5239.0    0.07       0
Bank Sta=4992.6,4996.6
Exp/Cntr=0.3,0.1

Type RM Length L Ch R = 1,1595,169,169,169
BEGIN DESCRIPTION:
E21268
END DESCRIPTION:
XS GIS Cut Line= 3
      2401985.48     13699304.69      2401456.61     13699216.54
      2401035.21     13699347.69
#Sta/Elev= 30
  4527.6  370.95  4548.4  370.57  4588.9  368.46  4639.6  367.11  4659.9  365.88
  4689.6  365.54  4734.8  363.45  4771.4  361.40  4832.2  359.60  4858.9  359.48
  4919.7  357.47  5012.7  355.95  5013.0  355.45  5016.5  355.45  5016.7  355.95
  5041.4  356.89  5055.3  356.80  5073.0  357.72  5096.9  359.79  5181.1  360.03
  5241.0  361.34  5254.6  361.15  5295.9  362.18  5306.0  361.80  5311.3  362.43
  5343.8  361.83  5369.1  362.08  5414.1  362.59  5441.4  361.91  5505.1  362.10
#Mann=7,-1,0
  4527.6    0.05       0  4689.6   0.035       0  4734.8    0.05       0
  5012.7    0.05       0  5016.7    0.05       0  5254.6    0.07       0
  5369.1    0.05       0
Bank Sta=5012.7,5016.7
Exp/Cntr=0.3,0.1

Type RM Length L Ch R = 1,1426,201,201,201
BEGIN DESCRIPTION:
Stream0697 3.0
END DESCRIPTION:
XS GIS Cut Line= 3
      2402035.70     13699228.57      2401475.00     13699075.00
      2401059.60     13699297.74
#Sta/Elev= 30
  4422.7  371.89  4566.0  365.67  4571.2  365.88  4630.8  363.58  4693.0  362.00
  4719.5  362.13  4744.8  361.36  4786.3  358.59  4833.3  356.94  4984.8  354.65
  4985.1  354.15  4988.6  354.15  4988.8  354.65  5012.2  356.28  5017.8  355.76
  5034.1  357.81  5039.8  356.86  5056.0  358.63  5061.7  357.55  5078.0  359.09
  5174.3  359.50  5209.5  360.47  5248.2  360.76  5264.0  361.30  5329.7  361.02
  5335.4  361.59  5344.5  361.02  5403.9  361.39  5439.4  361.84  5475.4  361.57
#Mann=5,-1,0
  4422.7    0.05       0  4984.8    0.05       0  4988.8    0.05       0
  5248.2    0.07       0  5403.9    0.05       0
Bank Sta=4984.8,4988.8
Exp/Cntr=0.3,0.1

Type RM Length L Ch R = 1,1225,244,244,244
BEGIN DESCRIPTION:
E21267
END DESCRIPTION:
XS GIS Cut Line= 4
      2401903.85     13699083.25      2401538.31     13698896.18
      2401364.16     13698913.38      2400996.53     13699265.96
#Sta/Elev= 30
  4525.8  365.35  4598.2  363.23  4636.8  361.86  4642.6  361.31  4798.0  358.17
  4850.3  356.33  4917.7  354.70  4940.6  354.73  4998.0  353.35  4998.3  352.85
  5001.8  352.85  5002.0  353.35  5060.3  355.55  5076.2  356.73  5126.0  357.86
  5175.7  357.78  5196.8  358.37  5218.2  358.25  5253.4  359.28  5260.6  358.99
  5267.5  359.46  5274.8  358.86  5396.1  359.99  5401.8  360.44  5437.3  360.03
  5486.7  360.75  5529.4  360.74  5571.6  361.14  5585.8  360.75  5620.8  361.38
#Mann=5,-1,0
  4525.8    0.05       0  4998.0    0.05       0  5002.0    0.05       0
  5396.1    0.07       0  5529.4    0.05       0
Bank Sta=4998,5002
Exp/Cntr=0.3,0.1

Type RM Length L Ch R = 1,981,123,123,123
BEGIN DESCRIPTION:
Stream0697 2.0
END DESCRIPTION:
XS GIS Cut Line= 3
      2402024.99     13699124.99      2401425.00     13698675.00
      2400925.01     13699274.99
#Sta/Elev= 30
  4250.1  370.45  4292.8  369.19  4328.2  366.91  4357.4  366.55  4407.4  364.05
  4442.8  363.51  4492.8  360.99  4536.5  360.29  4557.4  359.27  4713.6  356.24
  4863.6  354.71  4922.0  352.82  4928.2  353.19  4955.1  351.79  5019.6  350.62
  5019.8  350.12  5023.3  350.12  5023.6  350.62  5064.5  352.79  5071.0  353.82
  5085.4  354.04  5091.9  355.19  5163.3  356.27  5404.3  358.92  5426.4  358.50
  5507.1  359.24  5675.0  360.39  5689.3  361.43  5695.9  360.38  5781.1  360.94
#Mann=6,-1,0
  4250.1    0.05       0  4955.1    0.07       0  5019.6    0.05       0
  5023.6    0.07       0  5163.3    0.05       0  5507.1    0.07       0
Bank Sta=5019.6,5023.6
Exp/Cntr=0.3,0.1

Type RM Length L Ch R = 1,858,221,221,221
BEGIN DESCRIPTION:
E21266
END DESCRIPTION:
XS GIS Cut Line= 4
      2401910.30     13698775.79      2401495.31     13698543.57
      2401336.21     13698567.22      2400951.53     13699130.27
#Sta/Elev= 30
  4434.8  358.26  4462.6  358.25  4468.3  357.68  4506.0  356.82  4533.4  355.70
  4608.8  355.30  4624.2  355.74  4636.2  354.97  4792.6  354.36  4930.9  353.22
  4950.0  352.31  4961.2  352.29  4999.6  350.35  4999.9  349.85  5003.4  349.85
  5003.6  350.35  5042.1  352.07  5069.3  354.11  5085.0  354.10  5213.8  355.74
  5228.0  356.28  5236.9  355.83  5308.7  356.48  5335.7  356.13  5365.5  356.93
  5431.3  356.94  5524.0  358.28  5587.0  358.71  5608.8  358.76  5753.1  359.30
#Mann=6,-1,0
  4434.8    0.05       0  4999.6    0.05       0  5003.6    0.05       0
  5085.0    0.07       0  5587.0    0.05       0  5608.8    0.07       0
Bank Sta=4999.6,5003.6
Exp/Cntr=0.3,0.1

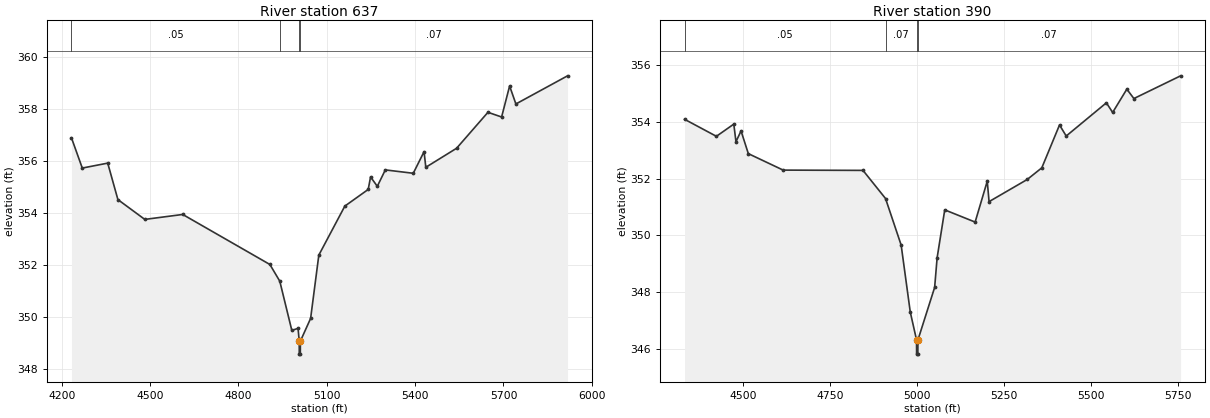
Type RM Length L Ch R = 1,637,247,247,247
BEGIN DESCRIPTION:
Stream0697 1.0
END DESCRIPTION:
XS GIS Cut Line= 3
      2402018.32     13698673.00      2401328.21     13698356.16
      2400846.45     13699146.08
#Sta/Elev= 30
  4233.0  356.88  4269.7  355.72  4356.1  355.91  4390.7  354.51  4482.0  353.75
  4610.8  353.94  4906.8  352.02  4940.4  351.38  4981.3  349.49  5002.5  349.57
  5006.4  349.08  5006.6  348.58  5010.1  348.58  5010.4  349.08  5045.1  349.95
  5073.0  352.38  5161.3  354.26  5240.7  354.90  5248.7  355.38  5271.6  355.02
  5298.8  355.65  5393.7  355.52  5430.4  356.35  5436.3  355.75  5540.8  356.48
  5647.3  357.86  5693.7  357.68  5720.9  358.87  5742.2  358.18  5917.6  359.26
#Mann=4,-1,0
  4233.0    0.05       0  4940.4    0.07       0  5006.4    0.05       0
  5010.4    0.07       0
Bank Sta=5006.4,5010.4
Exp/Cntr=0.3,0.1

Type RM Length L Ch R = 1,390,0,0,0
BEGIN DESCRIPTION:
E21265
END DESCRIPTION:
XS GIS Cut Line= 5
      2402019.91     13698567.21      2401521.11     13698195.26
      2401392.11     13698188.81      2401159.90     13698251.16
      2401080.35     13698676.89
#Sta/Elev= 30
  4332.4  354.09  4423.9  353.49  4473.9  353.92  4480.1  353.30  4494.7  353.68
  4515.6  352.88  4615.7  352.30  4845.0  352.29  4909.7  351.30  4954.6  349.66
  4980.8  347.30  4998.8  346.32  4999.0  345.82  5002.5  345.82  5002.8  346.32
  5050.8  348.17  5057.9  349.21  5079.8  350.90  5167.1  350.47  5201.9  351.91
  5207.1  351.19  5316.7  351.97  5358.6  352.38  5409.5  353.89  5428.7  353.50
  5544.1  354.67  5562.1  354.33  5602.8  355.15  5623.1  354.82  5757.3  355.62
#Mann=4,-1,0
  4332.4    0.05       0  4909.7    0.07       0  4998.8    0.05       0
  5002.8    0.07       0
Bank Sta=4998.8,5002.8
Exp/Cntr=0.3,0.1

Chan Stop Cuts=-1