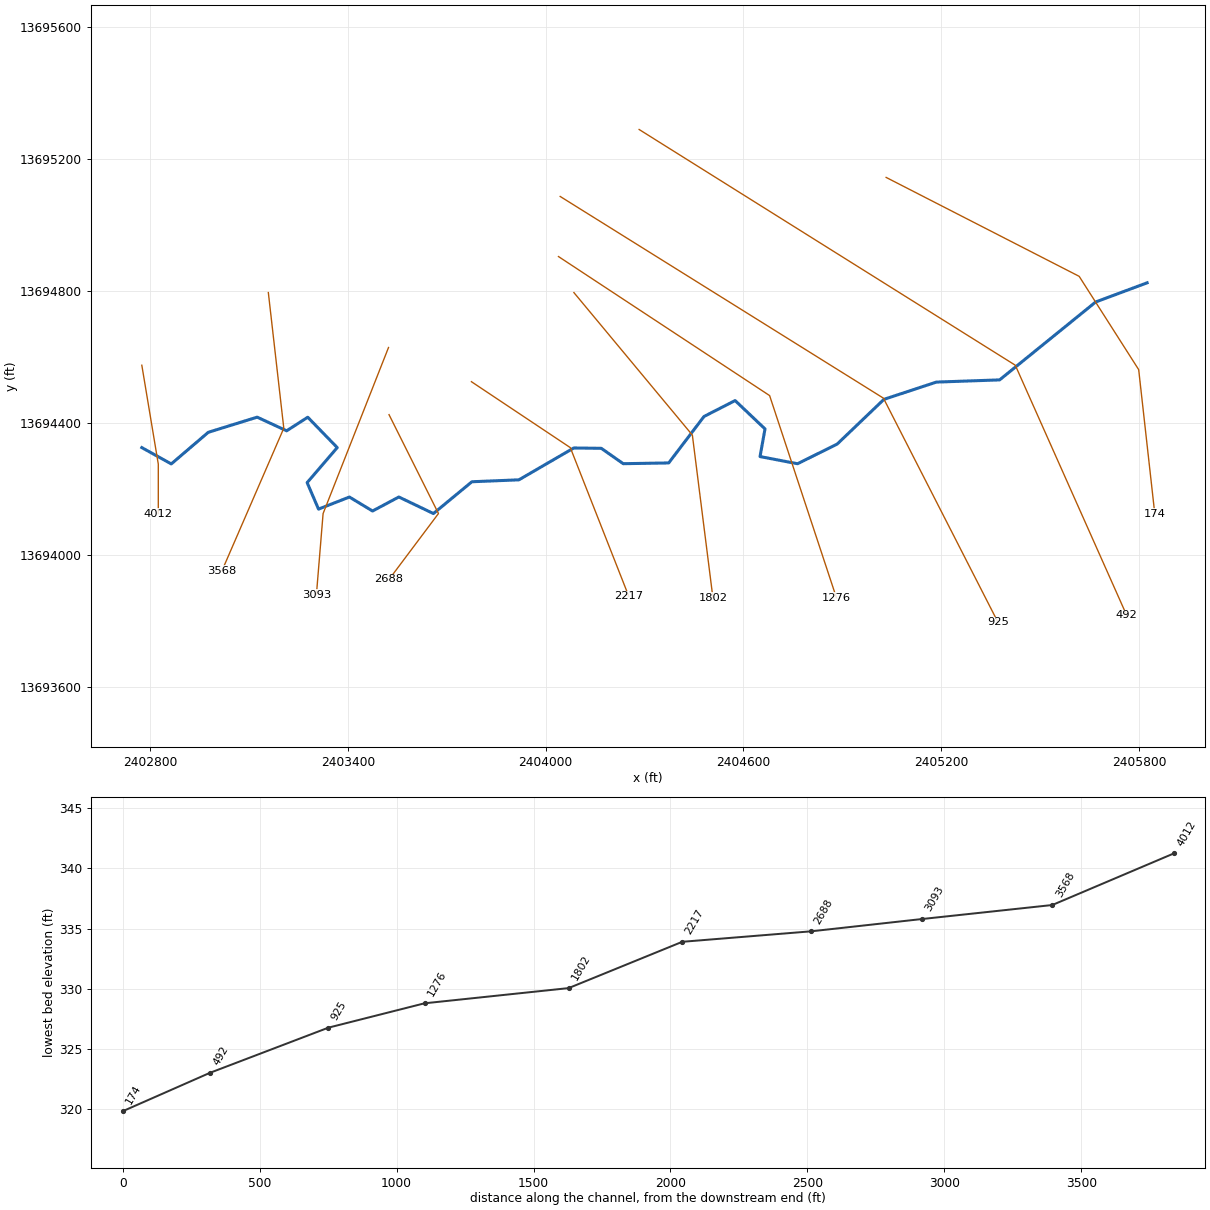
--- Stream0698.prj (project) ---

Proj Title=Stream0698 Base Level Engineering
Current Plan=p01
Default Exp/Contr=0.3,0.1
English Units
Geom File=g01
Flow File=f01
Plan File=p01
BEGIN DESCRIPTION:
Stream0698
END DESCRIPTION:

--- Stream0698.p01 (plan) ---

Plan Title=Multiple Run
Short Identifier=Multiple
Geom File=g01
Flow File=f01
Subcritical Flow
K Sum by GR= 0
Std Step Tol= 0.01
Critical Tol= 0.01
Num of Std Step Trials= 20
Max Error Tol= 0.3
Flow Tol Ratio= 0.001
Split Flow NTrial= 30
Split Flow Tol= 0.02
Split Flow Ratio= 0.02
Log Output Level= 0
Friction Slope Method= 1
Unsteady Friction Slope Method= 2
Unsteady Bridges Friction Slope Method= 1
Parabolic Critical Depth
Global Vel Dist=  1 , 1 , 1
Global Log Level= 0
CheckData=True
Encroach Param= -1, 0, 0, 0
BEGIN DESCRIPTION:
Multiple Run
END DESCRIPTION:

--- Stream0698.f01 (steady flow) ---

Flow Title=Multiple
Number of Profiles=7
Profile Names=10-year,25-year,50-year,1pct_min,100-year,1pct_plu,500-year
River Rch & RM= Stream0698,Reach-1,4012
     530     846    1130     731    1459    2912    2410
Boundary for River Rch & Prof#=Stream0698,Reach-1,1
Up Type=0
Dn Type=3
Dn Slope=0.005
Boundary for River Rch & Prof#=Stream0698,Reach-1,2
Up Type=0
Dn Type=3
Dn Slope=0.005
Boundary for River Rch & Prof#=Stream0698,Reach-1,3
Up Type=0
Dn Type=3
Dn Slope=0.005
Boundary for River Rch & Prof#=Stream0698,Reach-1,4
Up Type=0
Dn Type=3
Dn Slope=0.005
Boundary for River Rch & Prof#=Stream0698,Reach-1,5
Up Type=0
Dn Type=3
Dn Slope=0.005
Boundary for River Rch & Prof#=Stream0698,Reach-1,6
Up Type=0
Dn Type=3
Dn Slope=0.005
Boundary for River Rch & Prof#=Stream0698,Reach-1,7
Up Type=0
Dn Type=3
Dn Slope=0.005

--- Stream0698.g01 (geometry) ---

Geom Title=Existing Conditions

River Reach=Stream0698,Reach-1
Reach XY= 30
      2402775.00     13694325.00      2402864.45     13694275.50
      2402976.50     13694371.38      2403125.01     13694417.41
      2403214.36     13694375.99      2403278.44     13694417.18
      2403367.92     13694325.03      2403276.60     13694218.87
      2403311.13     13694138.40      2403404.83     13694175.09
      2403475.00     13694132.62      2403554.80     13694175.20
      2403659.66     13694124.96      2403776.47     13694221.44
      2403919.07     13694227.25      2404085.54     13694323.91
      2404169.02     13694322.83      2404235.51     13694276.21
      2404373.54     13694278.52      2404480.62     13694419.44
      2404575.08     13694467.73      2404665.69     13694381.70
      2404650.58     13694297.84      2404764.44     13694276.08
      2404884.68     13694335.76      2405026.50     13694471.39
      2405185.50     13694523.78      2405377.45     13694530.46
      2405668.95     13694766.85      2405825.00     13694825.00

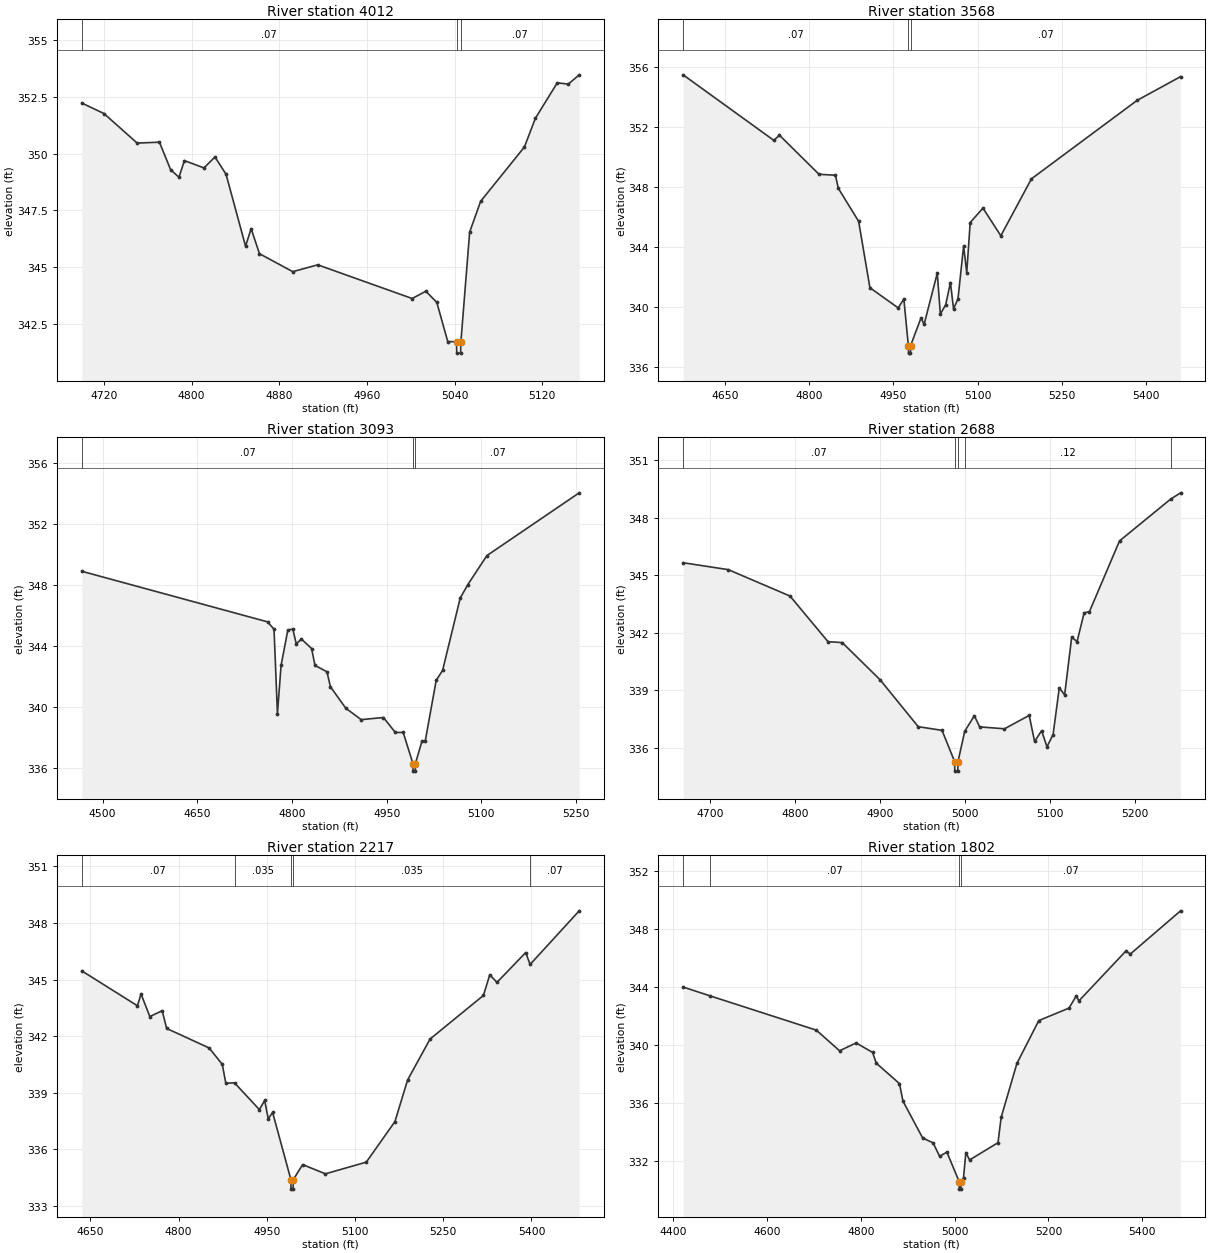
Type RM Length L Ch R = 1,4012,444,444,444
BEGIN DESCRIPTION:
Stream0698 9.0
END DESCRIPTION:
XS GIS Cut Line= 3
      2402775.01     13694574.96      2402825.00     13694275.00
      2402825.00     13694124.99
#Sta/Elev= 30
  4699.7  352.22  4719.9  351.76  4750.3  350.46  4770.6  350.50  4780.8  349.29
  4788.4  348.96  4793.4  349.69  4811.2  349.37  4821.3  349.85  4831.4  349.09
  4849.2  345.93  4854.3  346.70  4861.9  345.60  4892.3  344.81  4915.1  345.11
  5001.3  343.63  5013.8  343.95  5023.8  343.46  5033.8  341.74  5041.8  341.73
  5042.0  341.23  5045.5  341.23  5045.8  341.73  5053.8  346.55  5063.8  347.90
  5103.8  350.29  5113.8  351.55  5133.8  353.11  5143.8  353.05  5153.8  353.46
#Mann=3,-1,0
  4699.7    0.07       0  5041.8    0.05       0  5045.8    0.07       0
Bank Sta=5041.8,5045.8
Exp/Cntr=0.3,0.1

Type RM Length L Ch R = 1,3568,475,475,475
BEGIN DESCRIPTION:
Stream0698 8.0
END DESCRIPTION:
XS GIS Cut Line= 3
      2403158.85     13694795.35      2403205.73     13694383.85
      2403018.22     13693951.53
#Sta/Elev= 30
  4576.0  355.47  4737.4  351.11  4747.5  351.45  4817.9  348.85  4847.1  348.79
  4852.2  347.92  4888.4  345.72  4908.5  341.30  4958.8  339.96  4968.9  340.55
  4976.9  337.45  4977.2  336.95  4980.7  336.95  4980.9  337.45  4999.5  339.30
  5004.9  338.86  5028.4  342.27  5033.8  339.55  5043.4  340.17  5051.8  341.65
  5057.3  339.90  5065.2  340.55  5075.3  344.09  5080.8  342.30  5087.0  345.64
  5109.7  346.60  5141.5  344.76  5196.0  348.55  5384.1  353.77  5461.4  355.35
#Mann=3,-1,0
  4576.0    0.07       0  4976.9    0.05       0  4980.9    0.07       0
Bank Sta=4976.9,4980.9
Exp/Cntr=0.3,0.1

Type RM Length L Ch R = 1,3093,405,405,405
BEGIN DESCRIPTION:
Stream0698 7.0
END DESCRIPTION:
XS GIS Cut Line= 3
      2403523.45     13694628.68      2403325.00     13694125.00
      2403304.74     13693879.30
#Sta/Elev= 30
  4467.1  348.91  4761.3  345.59  4771.6  345.11  4777.0  339.57  4782.8  342.73
  4793.5  345.06  4801.4  345.11  4806.8  344.15  4815.0  344.46  4831.1  343.84
  4836.5  342.73  4855.5  342.31  4860.9  341.33  4885.3  339.92  4909.7  339.17
  4944.8  339.31  4963.8  338.33  4976.2  338.33  4991.6  336.29  4991.8  335.79
  4995.3  335.79  4995.6  336.29  5005.8  337.74  5011.0  337.74  5028.5  341.75
  5038.6  342.40  5066.5  347.15  5078.7  348.04  5108.8  349.94  5255.0  354.06
#Mann=3,-1,0
  4467.1    0.07       0  4991.6    0.05       0  4995.6    0.07       0
Bank Sta=4991.6,4995.6
Exp/Cntr=0.3,0.1

Type RM Length L Ch R = 1,2688,471,471,471
BEGIN DESCRIPTION:
Stream0698 6.0
END DESCRIPTION:
XS GIS Cut Line= 3
      2403524.98     13694425.03      2403675.00     13694125.00
      2403525.03     13693925.04
#Sta/Elev= 30
  4668.1  345.65  4721.2  345.29  4793.9  343.91  4838.6  341.53  4855.4  341.48
  4900.1  339.53  4944.8  337.09  4972.8  336.90  4987.6  335.27  4987.8  334.77
  4991.3  334.77  4991.6  335.27  4999.5  336.85  5010.8  337.66  5017.1  337.08
  5046.3  336.98  5075.4  337.68  5081.7  336.32  5090.0  336.88  5096.3  336.04
  5103.5  336.68  5110.8  339.12  5117.1  338.75  5125.4  341.77  5131.7  341.53
  5140.0  343.03  5146.3  343.10  5181.7  346.79  5241.8  348.97  5253.5  349.30
#Mann=5,-1,0
  4668.1    0.07       0  4987.6    0.05       0  4991.6    0.07       0
  4999.5    0.12       0  5241.8    0.07       0
Bank Sta=4987.6,4991.6
Exp/Cntr=0.3,0.1

Type RM Length L Ch R = 1,2217,415,415,415
BEGIN DESCRIPTION:
Stream0698 5.0
END DESCRIPTION:
XS GIS Cut Line= 3
      2403774.97     13694525.02      2404075.00     13694325.00
      2404252.60     13693873.46
#Sta/Elev= 30
  4635.4  345.46  4730.1  343.61  4736.1  344.24  4751.1  343.04  4772.1  343.35
  4779.7  342.41  4851.8  341.38  4874.3  340.51  4880.3  339.51  4895.1  339.53
  4937.4  338.11  4946.4  338.60  4952.4  337.63  4959.9  337.96  4991.0  334.40
  4991.2  333.90  4994.7  333.90  4995.0  334.40  5010.9  335.20  5049.7  334.71
  5119.2  335.33  5167.9  337.48  5189.4  339.68  5227.6  341.85  5318.4  344.16
  5329.1  345.25  5341.4  344.85  5390.2  346.43  5397.7  345.80  5481.2  348.64
#Mann=5,-1,0
  4635.4    0.07       0  4895.1   0.035       0  4991.0   0.035       0
  4995.0   0.035       0  5397.7    0.07       0
Bank Sta=4991,4995
Exp/Cntr=0.3,0.1

Type RM Length L Ch R = 1,1802,526,526,526
BEGIN DESCRIPTION:
Stream0698 4.0
END DESCRIPTION:
XS GIS Cut Line= 3
      2404085.95     13694795.29      2404445.31     13694363.02
      2404507.70     13693869.08
#Sta/Elev= 30
  4421.6  343.98  4478.3  343.38  4705.5  341.01  4755.0  339.59  4790.2  340.13
  4825.3  339.48  4833.1  338.74  4882.6  337.33  4890.1  336.12  4932.1  333.58
  4954.2  333.25  4968.2  332.32  4983.7  332.61  5010.0  330.56  5010.2  330.06
  5013.7  330.06  5014.0  330.56  5019.1  330.84  5024.1  332.58  5032.1  332.07
  5092.6  333.26  5099.3  335.00  5132.9  338.72  5179.5  341.67  5243.8  342.53
  5259.7  343.38  5264.8  343.02  5364.8  346.45  5374.8  346.26  5481.6  349.23
#Mann=4,-1,0
  4421.6    0.05       0  4478.3    0.07       0  5010.0    0.05       0
  5014.0    0.07       0
Bank Sta=5010,5014
Exp/Cntr=0.3,0.1

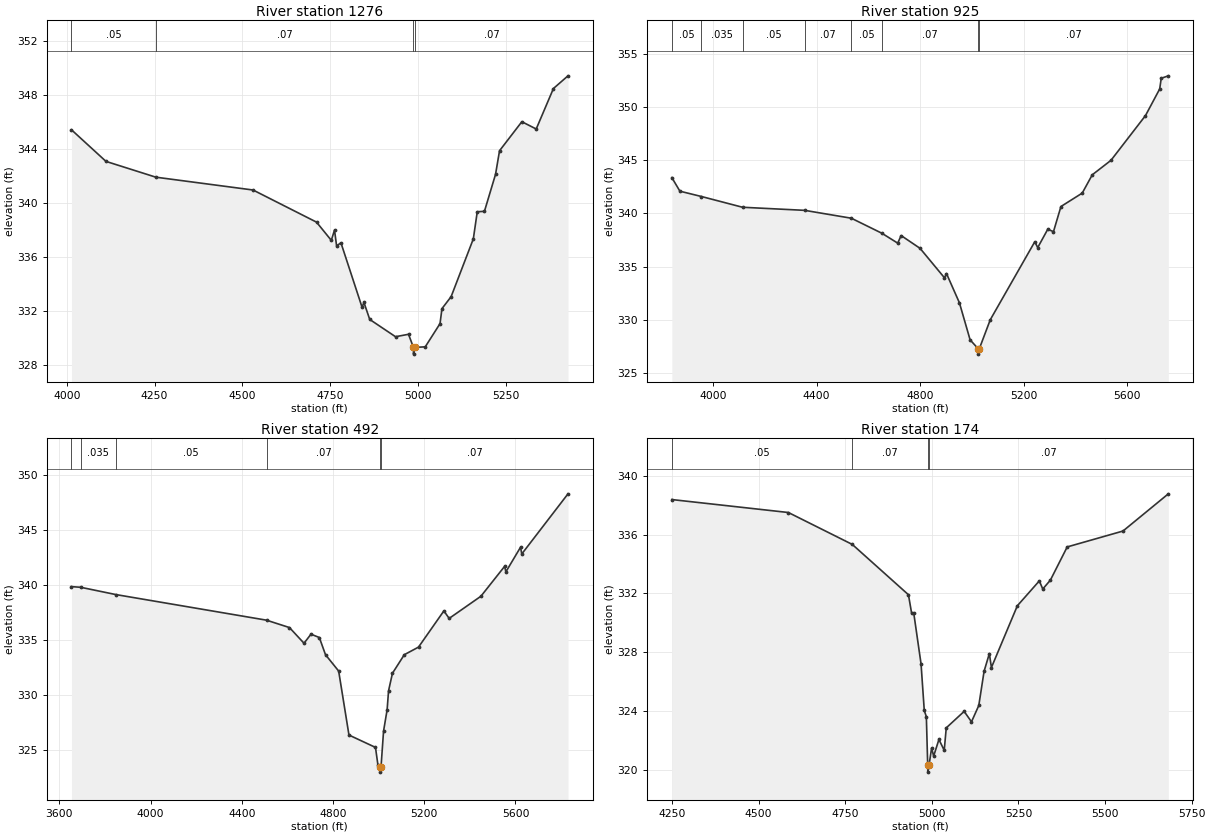
Type RM Length L Ch R = 1,1276,351,351,351
BEGIN DESCRIPTION:
Stream0698 3.0
END DESCRIPTION:
XS GIS Cut Line= 3
      2404039.08     13694904.68      2404679.69     13694482.81
      2404882.52     13693869.10
#Sta/Elev= 30
  4013.6  345.42  4111.8  343.08  4253.8  341.91  4530.4  340.96  4711.1  338.58
  4753.2  337.23  4762.3  337.99  4768.3  336.82  4780.6  337.05  4840.8  332.27
  4846.1  332.63  4862.6  331.37  4936.0  330.09  4973.0  330.27  4987.0  329.30
  4987.2  328.80  4991.0  329.30  5020.6  329.34  5062.7  331.06  5068.2  332.17
  5094.3  333.06  5157.5  337.34  5168.7  339.35  5189.1  339.38  5220.7  342.12
  5232.1  343.87  5295.6  346.02  5336.5  345.48  5385.5  348.48  5427.0  349.42
#Mann=4,-1,0
  4013.6    0.05       0  4253.8    0.07       0  4987.0    0.05       0
  4991.0    0.07       0
Bank Sta=4987,4991
Exp/Cntr=0.3,0.1

Type RM Length L Ch R = 1,925,433,433,433
BEGIN DESCRIPTION:
Stream0698 2.0
END DESCRIPTION:
XS GIS Cut Line= 3
      2404044.31     13695086.95      2405025.00     13694475.00
      2405372.41     13693795.29
#Sta/Elev= 30
  3840.1  343.37  3871.3  342.09  3954.6  341.59  4113.5  340.58  4353.5  340.29
  4534.0  339.55  4651.9  338.14  4713.2  337.21  4726.5  337.92  4799.6  336.72
  4894.0  333.95  4901.8  334.35  4951.8  331.60  4993.1  328.12  5024.6  327.28
  5024.8  326.78  5028.6  327.28  5071.0  330.01  5243.1  337.34  5254.4  336.79
  5293.2  338.51  5315.4  338.29  5344.2  340.65  5426.5  341.91  5465.3  343.63
  5537.6  344.99  5670.9  349.19  5726.0  351.70  5731.9  352.70  5759.4  352.93
#Mann=8,-1,0
  3840.1    0.05       0  3954.6   0.035       0  4113.5    0.05       0
  4353.5    0.07       0  4534.0    0.05       0  4651.9    0.07       0
  5024.6    0.05       0  5028.6    0.07       0
Bank Sta=5024.6,5028.6
Exp/Cntr=0.3,0.1

Type RM Length L Ch R = 1,492,318,318,318
BEGIN DESCRIPTION:
Stream0698 1.0
END DESCRIPTION:
XS GIS Cut Line= 3
      2404283.82     13695290.13      2405425.00     13694575.00
      2405763.03     13693816.12
#Sta/Elev= 30
  3653.0  339.84  3693.7  339.78  3847.8  339.12  4508.3  336.80  4609.0  336.13
  4672.7  334.71  4703.3  335.53  4739.9  335.23  4767.0  333.67  4824.7  332.19
  4869.9  326.39  4986.2  325.27  4996.8  323.69  5006.6  323.53  5006.9  323.03
  5010.6  323.53  5021.6  326.75  5037.3  328.69  5043.5  330.40  5060.6  331.99
  5112.5  333.67  5174.9  334.36  5286.1  337.64  5309.3  336.96  5448.6  338.97
  5552.6  341.68  5558.1  341.18  5622.3  343.41  5627.8  342.80  5830.5  348.25
#Mann=6,-1,0
  3653.0    0.07       0  3693.7   0.035       0  3847.8    0.05       0
  4508.3    0.07       0  5006.6    0.05       0  5010.6    0.07       0
Bank Sta=5006.6,5010.6
Exp/Cntr=0.3,0.1

Type RM Length L Ch R = 1,174,0,0,0
BEGIN DESCRIPTION:
E21269
END DESCRIPTION:
XS GIS Cut Line= 4
      2405033.20     13695144.76      2405618.82     13694844.63
      2405799.38     13694561.59      2405848.18     13694124.78
#Sta/Elev= 30
  4249.4  338.38  4585.8  337.50  4770.3  335.33  4932.4  331.91  4941.7  330.64
  4947.7  330.67  4968.8  327.21  4978.1  324.04  4984.1  323.62  4988.0  320.35
  4988.3  319.85  4992.0  320.35  4999.3  321.49  5005.2  320.94  5020.4  322.07
  5035.7  321.33  5041.6  322.86  5093.2  323.98  5114.4  323.27  5135.5  324.38
  5150.8  326.71  5166.0  327.91  5171.9  326.96  5246.8  331.16  5310.2  332.85
  5320.2  332.30  5342.1  332.90  5390.7  335.16  5551.7  336.24  5682.7  338.77
#Mann=4,-1,0
  4249.4    0.05       0  4770.3    0.07       0  4988.0    0.05       0
  4992.0    0.07       0
Bank Sta=4988,4992
Exp/Cntr=0.3,0.1

Chan Stop Cuts=-1