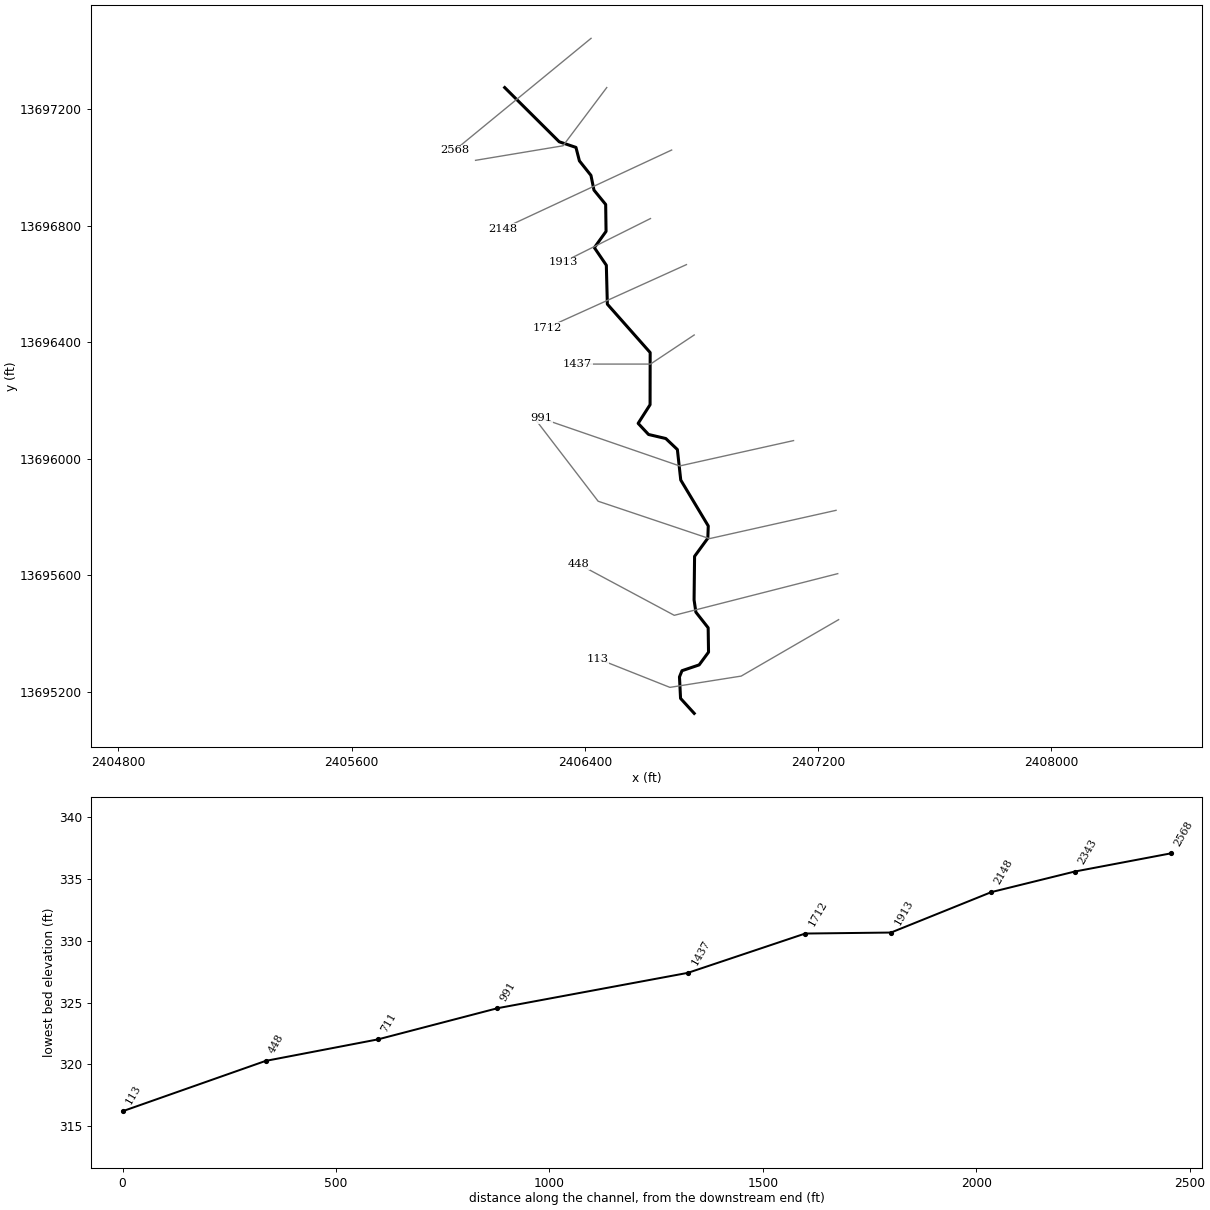
--- Stream0699.prj (project) ---

Proj Title=Stream0699 Base Level Engineering
Current Plan=p01
Default Exp/Contr=0.3,0.1
English Units
Geom File=g01
Flow File=f01
Plan File=p01
BEGIN DESCRIPTION:
Stream0699
END DESCRIPTION:

--- Stream0699.p01 (plan) ---

Plan Title=Multiple Run
Short Identifier=Multiple
Geom File=g01
Flow File=f01
Subcritical Flow
K Sum by GR= 0
Std Step Tol= 0.01
Critical Tol= 0.01
Num of Std Step Trials= 20
Max Error Tol= 0.3
Flow Tol Ratio= 0.001
Split Flow NTrial= 30
Split Flow Tol= 0.02
Split Flow Ratio= 0.02
Log Output Level= 0
Friction Slope Method= 1
Unsteady Friction Slope Method= 2
Unsteady Bridges Friction Slope Method= 1
Parabolic Critical Depth
Global Vel Dist=  1 , 1 , 1
Global Log Level= 0
CheckData=True
Encroach Param= -1, 0, 0, 0
BEGIN DESCRIPTION:
Multiple Run
END DESCRIPTION:

--- Stream0699.f01 (steady flow) ---

Flow Title=Multiple
Number of Profiles=7
Profile Names=10-year,25-year,50-year,1pct_min,100-year,1pct_plu,500-year
River Rch & RM= Stream0699,Reach-1,2568
     370     577     757     483     964    1923    1543
Boundary for River Rch & Prof#=Stream0699,Reach-1,1
Up Type=0
Dn Type=3
Dn Slope=0.005
Boundary for River Rch & Prof#=Stream0699,Reach-1,2
Up Type=0
Dn Type=3
Dn Slope=0.005
Boundary for River Rch & Prof#=Stream0699,Reach-1,3
Up Type=0
Dn Type=3
Dn Slope=0.005
Boundary for River Rch & Prof#=Stream0699,Reach-1,4
Up Type=0
Dn Type=3
Dn Slope=0.005
Boundary for River Rch & Prof#=Stream0699,Reach-1,5
Up Type=0
Dn Type=3
Dn Slope=0.005
Boundary for River Rch & Prof#=Stream0699,Reach-1,6
Up Type=0
Dn Type=3
Dn Slope=0.005
Boundary for River Rch & Prof#=Stream0699,Reach-1,7
Up Type=0
Dn Type=3
Dn Slope=0.005

--- Stream0699.g01 (geometry) ---

Geom Title=Existing Conditions

River Reach=Stream0699,Reach-1
Reach XY= 30
      2406125.00     13697275.00      2406312.02     13697088.73
      2406369.41     13697069.39      2406381.24     13697023.15
      2406420.85     13696973.31      2406431.12     13696922.82
      2406471.32     13696873.41      2406472.64     13696780.89
      2406432.56     13696725.00      2406473.60     13696664.56
      2406477.07     13696530.86      2406623.95     13696364.57
      2406623.61     13696185.43      2406582.69     13696121.33
      2406618.33     13696083.16      2406677.52     13696069.26
      2406717.25     13696031.45      2406728.83     13695926.59
      2406823.20     13695768.89      2406821.63     13695726.74
      2406776.24     13695664.50      2406774.54     13695514.82
      2406780.75     13695472.66      2406822.84     13695419.02
      2406824.11     13695335.34      2406791.92     13695291.55
      2406733.08     13695271.59      2406724.45     13695250.18
      2406728.14     13695176.50      2406775.00     13695125.00

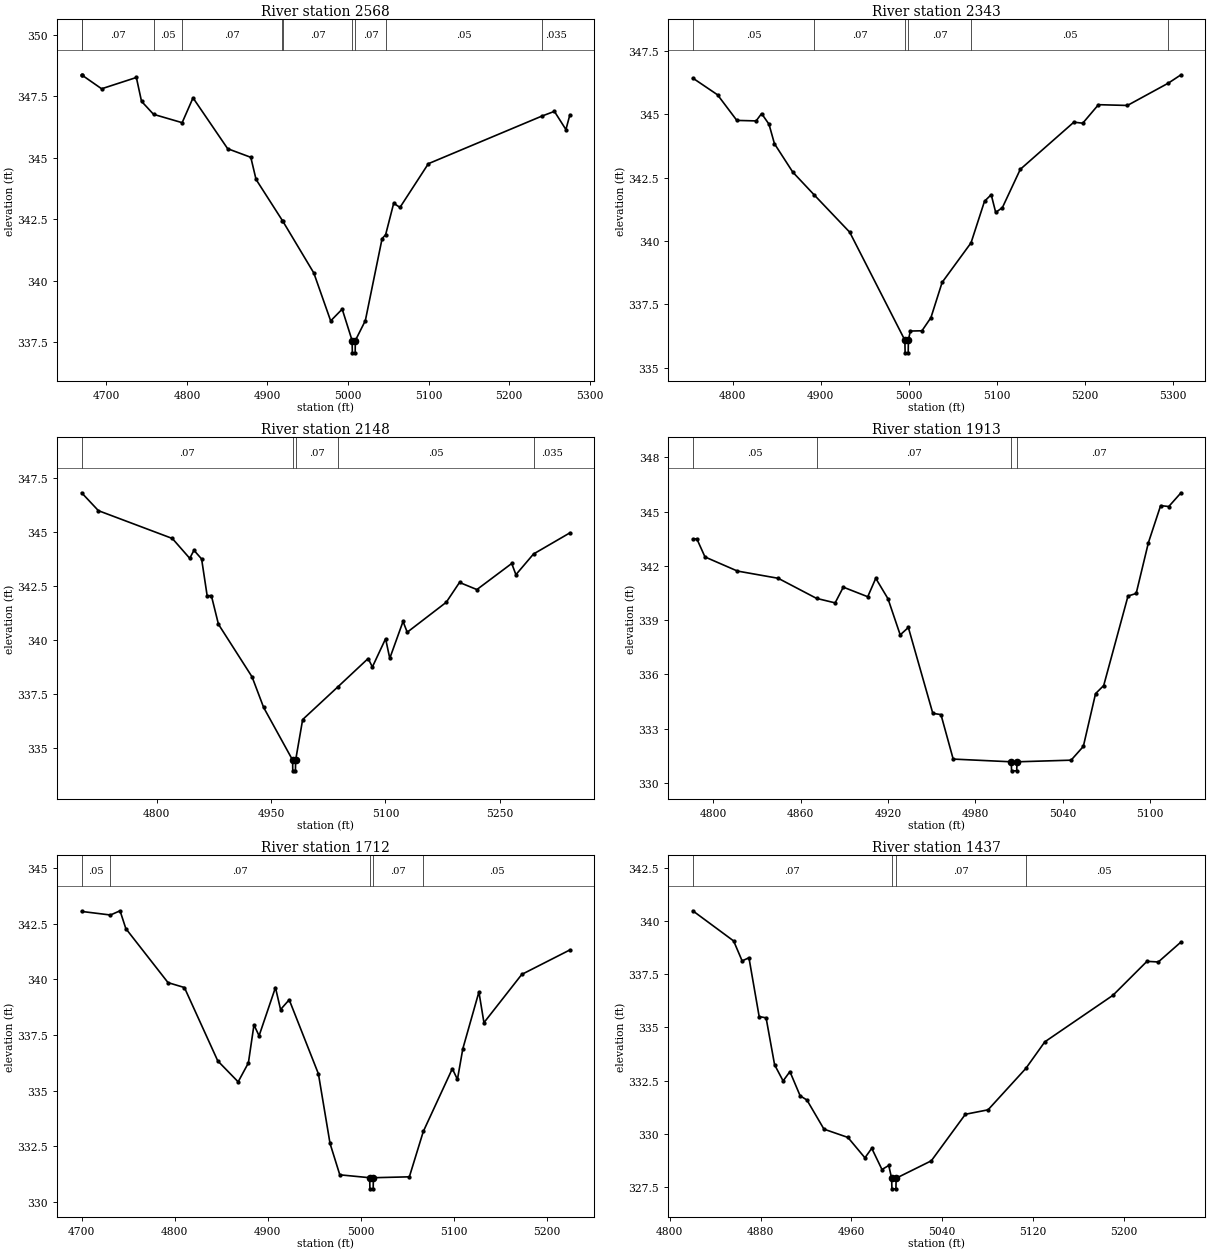
Type RM Length L Ch R = 1,2568,225,225,225
BEGIN DESCRIPTION:
XS7492
END DESCRIPTION:
XS GIS Cut Line= 2
      2406421.20     13697444.11      2405953.27     13697059.37
#Sta/Elev= 30
  4669.4  348.38  4669.7  348.37  4694.2  347.81  4737.3  348.27  4743.7  347.30
  4758.6  346.77  4794.1  346.43  4807.6  347.44  4850.6  345.37  4879.3  345.02
  4885.8  344.12  4918.6  342.44  4919.0  342.42  4957.5  340.31  4978.4  338.36
  4992.7  338.84  5005.0  337.56  5005.3  337.06  5008.8  337.06  5009.0  337.56
  5021.4  338.37  5042.2  341.71  5046.6  341.87  5056.6  343.15  5064.4  342.98
  5099.6  344.76  5240.6  346.70  5256.0  346.89  5270.3  346.15  5275.2  346.75
#Mann=10,-1,0
  4669.4    0.05       0  4669.7    0.07       0  4758.6    0.05       0
  4794.1    0.07       0  4918.6    0.05       0  4919.0    0.07       0
  5005.0    0.05       0  5009.0    0.07       0  5046.6    0.05       0
  5240.6   0.035       0
Bank Sta=5005,5009
Exp/Cntr=0.3,0.1

Type RM Length L Ch R = 1,2343,195,195,195
BEGIN DESCRIPTION:
Stream0699 5.0
END DESCRIPTION:
XS GIS Cut Line= 3
      2406475.00     13697275.00      2406325.00     13697075.00
      2406025.04     13697025.01
#Sta/Elev= 30
  4754.8  346.43  4782.9  345.77  4804.8  344.76  4826.7  344.74  4832.9  345.03
  4841.3  344.61  4847.5  343.84  4868.3  342.72  4892.9  341.81  4932.9  340.35
  4995.5  336.09  4995.8  335.59  4999.3  335.59  4999.5  336.09  5001.7  336.45
  5014.9  336.46  5025.1  336.98  5037.8  338.37  5070.6  339.93  5085.9  341.57
  5093.5  341.83  5098.6  341.13  5106.2  341.32  5126.5  342.83  5187.3  344.69
  5197.4  344.65  5215.2  345.38  5248.1  345.35  5294.5  346.23  5308.9  346.56
#Mann=6,-1,0
  4754.8    0.05       0  4892.9    0.07       0  4995.5    0.05       0
  4999.5    0.07       0  5070.6    0.05       0  5294.5   0.035       0
Bank Sta=4995.5,4999.5
Exp/Cntr=0.3,0.1

Type RM Length L Ch R = 1,2148,235,235,235
BEGIN DESCRIPTION:
E21273
END DESCRIPTION:
XS GIS Cut Line= 2
      2406697.62     13697060.41      2406117.12     13696789.51
#Sta/Elev= 30
  4701.4  346.83  4723.4  346.00  4820.4  344.71  4843.2  343.79  4848.8  344.16
  4858.8  343.76  4866.1  342.05  4871.6  342.06  4880.9  340.73  4925.0  338.29
  4940.2  336.87  4978.2  334.43  4978.4  333.93  4981.9  333.93  4982.2  334.43
  4991.4  336.31  5037.7  337.83  5077.3  339.14  5082.9  338.75  5100.2  340.06
  5105.7  339.15  5123.1  340.86  5128.6  340.36  5179.8  341.75  5197.2  342.67
  5220.0  342.34  5265.7  343.55  5271.2  343.03  5294.3  343.99  5342.0  344.97
#Mann=5,-1,0
  4701.4    0.07       0  4978.2    0.05       0  4982.2    0.07       0
  5037.7    0.05       0  5294.3   0.035       0
Bank Sta=4978.2,4982.2
Exp/Cntr=0.3,0.1

Type RM Length L Ch R = 1,1913,201,201,201
BEGIN DESCRIPTION:
Stream0699 4.0
END DESCRIPTION:
XS GIS Cut Line= 3
      2406624.97     13696824.99      2406425.00     13696725.00
      2406324.98     13696674.99
#Sta/Elev= 30
  4785.9  343.49  4788.7  343.49  4794.3  342.49  4816.6  341.71  4844.6  341.31
  4870.9  340.20  4883.7  339.95  4889.3  340.82  4906.1  340.29  4911.6  341.31
  4920.0  340.18  4928.4  338.18  4934.0  338.59  4950.8  333.84  4956.4  333.77
  4964.8  331.31  5004.7  331.16  5004.9  330.66  5008.4  330.66  5008.7  331.16
  5045.8  331.25  5054.2  332.01  5062.6  334.93  5068.2  335.38  5084.9  340.33
  5090.5  340.47  5098.9  343.28  5107.3  345.33  5112.9  345.28  5121.3  346.04
#Mann=4,-1,0
  4785.9    0.05       0  4870.9    0.07       0  5004.7    0.05       0
  5008.7    0.07       0
Bank Sta=5004.7,5008.7
Exp/Cntr=0.3,0.1

Type RM Length L Ch R = 1,1712,275,275,275
BEGIN DESCRIPTION:
E21272
END DESCRIPTION:
XS GIS Cut Line= 2
      2406748.30     13696666.73      2406270.15     13696449.93
#Sta/Elev= 30
  4700.1  343.05  4731.1  342.89  4741.4  343.08  4747.6  342.28  4793.0  339.85
  4810.6  339.63  4846.5  336.33  4868.4  335.39  4879.4  336.24  4885.4  337.95
  4890.9  337.46  4908.5  339.63  4914.0  338.64  4923.3  339.08  4954.7  335.75
  4967.2  332.62  4977.7  331.21  5009.8  331.08  5010.1  330.58  5013.6  330.58
  5013.8  331.08  5052.5  331.12  5067.5  333.16  5098.7  335.98  5104.2  335.50
  5110.0  336.88  5127.3  339.43  5132.7  338.05  5173.4  340.22  5225.1  341.32
#Mann=5,-1,0
  4700.1    0.05       0  4731.1    0.07       0  5009.8    0.05       0
  5013.8    0.07       0  5067.5    0.05       0
Bank Sta=5009.8,5013.8
Exp/Cntr=0.3,0.1

Type RM Length L Ch R = 1,1437,446,446,446
BEGIN DESCRIPTION:
Stream0699 3.0
END DESCRIPTION:
XS GIS Cut Line= 3
      2406774.97     13696424.98      2406625.00     13696325.00
      2406375.04     13696325.00
#Sta/Elev= 30
  4820.3  340.49  4856.3  339.07  4863.8  338.13  4869.8  338.28  4878.8  335.51
  4884.9  335.45  4892.4  333.24  4899.9  332.48  4905.9  332.92  4914.9  331.78
  4920.9  331.58  4935.9  330.21  4957.0  329.82  4972.0  328.86  4978.0  329.31
  4987.0  328.31  4993.0  328.50  4995.5  327.90  4995.8  327.40  4999.3  327.40
  4999.5  327.90  5030.5  328.72  5060.5  330.91  5080.5  331.12  5113.8  333.07
  5130.5  334.32  5190.5  336.51  5220.5  338.11  5230.5  338.08  5250.5  339.02
#Mann=4,-1,0
  4820.3    0.07       0  4995.5    0.05       0  4999.5    0.07       0
  5113.8    0.05       0
Bank Sta=4995.5,4999.5
Exp/Cntr=0.3,0.1

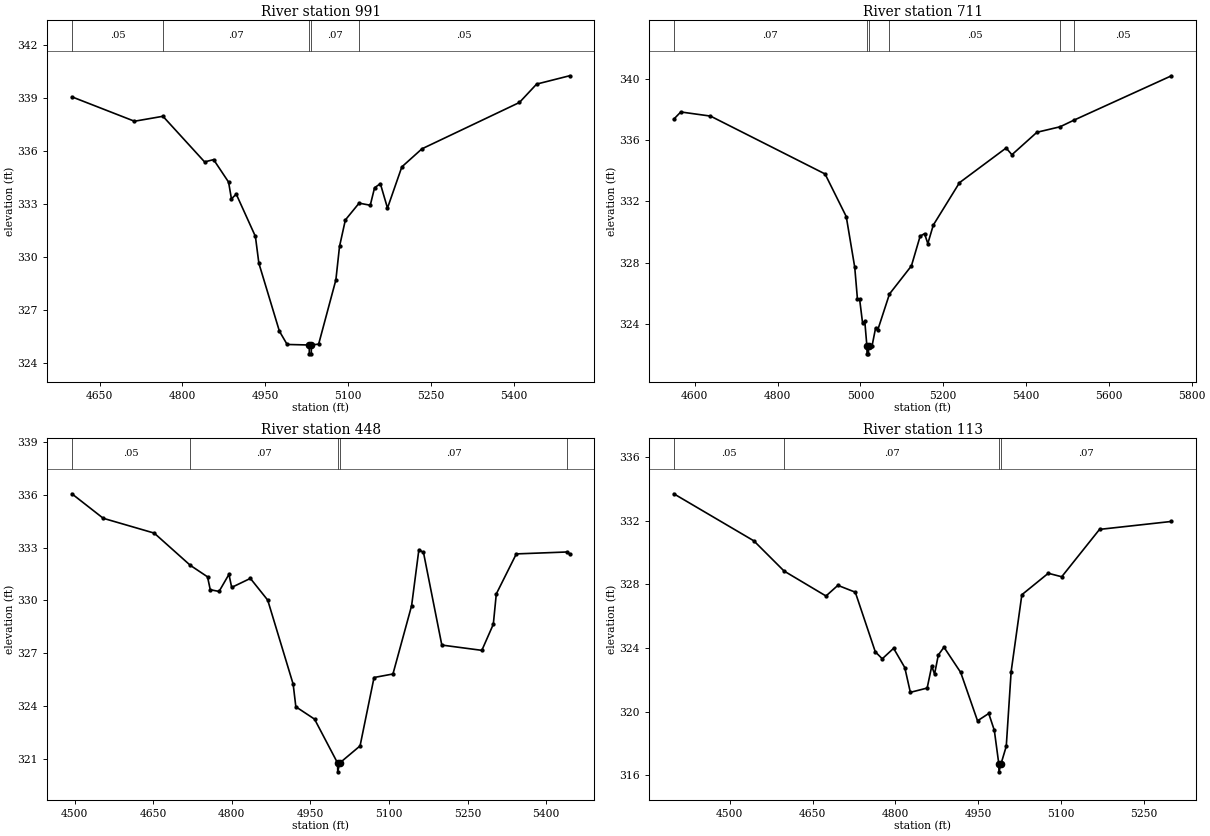
Type RM Length L Ch R = 1,991,280,280,280
BEGIN DESCRIPTION:
Stream0699 2.0
END DESCRIPTION:
XS GIS Cut Line= 3
      2407115.66     13696062.16      2406725.00     13695975.00
      2406251.08     13696138.53
#Sta/Elev= 30
  4599.8  339.07  4713.2  337.69  4764.8  337.97  4840.3  335.39  4856.6  335.52
  4883.7  334.25  4888.9  333.30  4897.6  333.57  4932.3  331.18  4938.6  329.66
  4975.8  325.82  4989.8  325.07  5029.8  325.04  5030.0  324.54  5033.5  324.54
  5033.8  325.04  5046.9  325.09  5078.1  328.72  5084.7  330.61  5095.3  332.11
  5120.2  333.06  5140.4  332.94  5148.2  333.93  5158.7  334.16  5171.6  332.78
  5197.6  335.11  5234.0  336.13  5410.6  338.75  5441.8  339.79  5501.4  340.26
#Mann=5,-1,0
  4599.8    0.05       0  4764.8    0.07       0  5029.8    0.05       0
  5033.8    0.07       0  5120.2    0.05       0
Bank Sta=5029.8,5033.8
Exp/Cntr=0.3,0.1

Type RM Length L Ch R = 1,711,263,263,263
BEGIN DESCRIPTION:
Stream0699 1.0
END DESCRIPTION:
XS GIS Cut Line= 4
      2407261.44     13695822.57      2406827.43     13695725.35
      2406445.49     13695853.82      2406230.22     13696135.05
#Sta/Elev= 30
  4549.3  337.39  4566.2  337.86  4637.9  337.59  4914.6  333.80  4965.8  331.01
  4986.3  327.69  4992.8  325.62  4998.0  325.62  5005.3  324.02  5010.6  324.14
  5015.7  322.52  5016.0  322.02  5019.5  322.02  5019.7  322.52  5028.3  322.56
  5036.8  323.73  5042.1  323.60  5070.2  325.94  5123.2  327.78  5144.3  329.73
  5154.9  329.89  5162.8  329.24  5176.0  330.45  5239.3  333.23  5351.9  335.50
  5365.9  335.06  5426.3  336.53  5482.2  336.89  5515.4  337.32  5751.2  340.23
#Mann=6,-1,0
  4549.3    0.07       0  5015.7    0.05       0  5019.7    0.07       0
  5070.2    0.05       0  5482.2    0.07       0  5515.4    0.05       0
Bank Sta=5015.7,5019.7
Exp/Cntr=0.3,0.1

Type RM Length L Ch R = 1,448,335,335,335
BEGIN DESCRIPTION:
E21271
END DESCRIPTION:
XS GIS Cut Line= 3
      2407267.28     13695605.03      2406706.56     13695461.87
      2406379.27     13695637.42
#Sta/Elev= 30
  4494.6  336.05  4554.5  334.66  4651.8  333.82  4720.8  331.99  4753.6  331.34
  4758.8  330.61  4775.6  330.51  4794.5  331.48  4799.7  330.74  4835.4  331.25
  4868.5  330.02  4917.1  325.25  4922.2  323.97  4957.9  323.27  5001.9  320.78
  5002.2  320.28  5005.9  320.78  5044.8  321.75  5071.5  325.63  5107.6  325.83
  5143.2  329.70  5157.1  332.88  5165.9  332.72  5200.9  327.47  5277.3  327.17
  5299.2  328.65  5304.9  330.37  5343.1  332.64  5440.8  332.75  5444.7  332.63
#Mann=5,-1,0
  4494.6    0.05       0  4720.8    0.07       0  5001.9    0.05       0
  5005.9    0.07       0  5440.8    0.05       0
Bank Sta=5001.9,5005.9
Exp/Cntr=0.3,0.1

Type RM Length L Ch R = 1,113,0,0,0
BEGIN DESCRIPTION:
E21270
END DESCRIPTION:
XS GIS Cut Line= 4
      2407270.23     13695446.96      2406936.20     13695253.11
      2406691.65     13695214.33      2406444.11     13695312.75
#Sta/Elev= 30
  4399.0  333.70  4543.8  330.74  4598.5  328.84  4674.3  327.27  4695.8  327.94
  4727.3  327.51  4763.5  323.76  4776.1  323.32  4796.6  323.98  4816.8  322.77
  4826.9  321.21  4857.3  321.48  4865.6  322.86  4870.7  322.36  4877.5  323.56
  4887.7  324.05  4918.0  322.46  4948.4  319.42  4968.7  319.88  4978.8  318.82
  4986.9  316.71  4987.2  316.21  4990.9  316.71  5000.4  317.82  5009.2  322.51
  5028.6  327.35  5076.4  328.70  5100.7  328.48  5169.1  331.46  5299.2  331.96
#Mann=4,-1,0
  4399.0    0.05       0  4598.5    0.07       0  4986.9    0.05       0
  4990.9    0.07       0
Bank Sta=4986.9,4990.9
Exp/Cntr=0.3,0.1

Chan Stop Cuts=-1