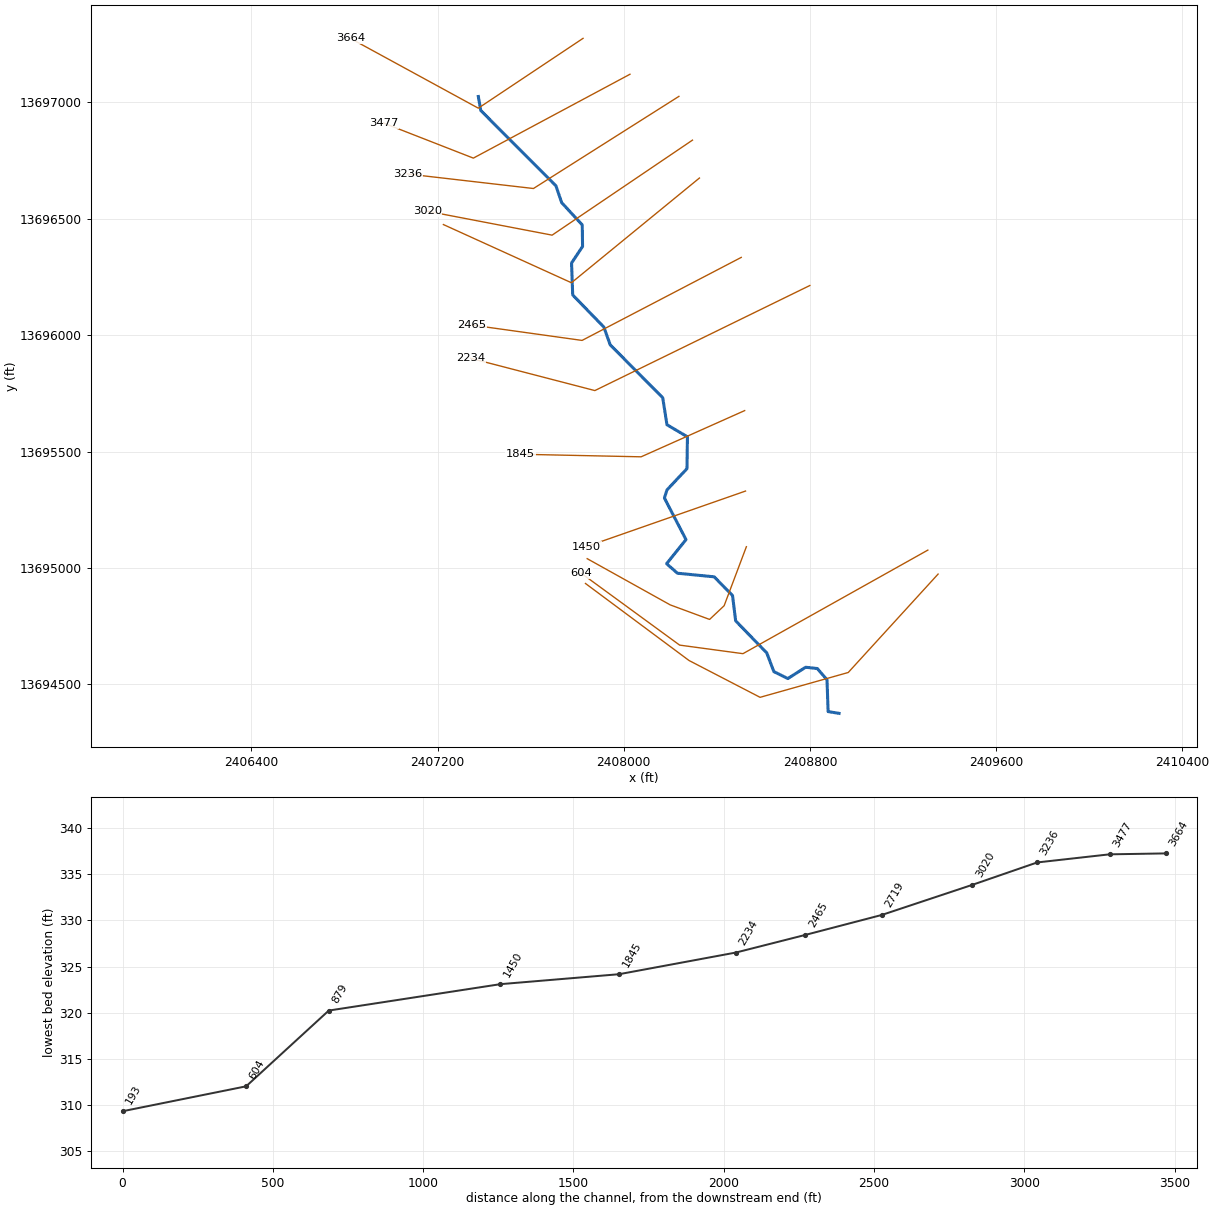
--- Stream0700.prj (project) ---

Proj Title=Stream0700 Base Level Engineering
Current Plan=p01
Default Exp/Contr=0.3,0.1
English Units
Geom File=g01
Flow File=f01
Plan File=p01
BEGIN DESCRIPTION:
Stream0700
END DESCRIPTION:

--- Stream0700.p01 (plan) ---

Plan Title=Multiple Run
Short Identifier=Multiple
Geom File=g01
Flow File=f01
Subcritical Flow
K Sum by GR= 0
Std Step Tol= 0.01
Critical Tol= 0.01
Num of Std Step Trials= 20
Max Error Tol= 0.3
Flow Tol Ratio= 0.001
Split Flow NTrial= 30
Split Flow Tol= 0.02
Split Flow Ratio= 0.02
Log Output Level= 0
Friction Slope Method= 1
Unsteady Friction Slope Method= 2
Unsteady Bridges Friction Slope Method= 1
Parabolic Critical Depth
Global Vel Dist=  1 , 1 , 1
Global Log Level= 0
CheckData=True
Encroach Param= -1, 0, 0, 0
BEGIN DESCRIPTION:
Multiple Run
END DESCRIPTION:

--- Stream0700.f01 (steady flow) ---

Flow Title=Multiple
Number of Profiles=7
Profile Names=10-year,25-year,50-year,1pct_min,100-year,1pct_plu,500-year
River Rch & RM= Stream0700,Reach-1,3664
     318     490     639     405     807    1611    1275
Boundary for River Rch & Prof#=Stream0700,Reach-1,1
Up Type=0
Dn Type=3
Dn Slope=0.005
Boundary for River Rch & Prof#=Stream0700,Reach-1,2
Up Type=0
Dn Type=3
Dn Slope=0.005
Boundary for River Rch & Prof#=Stream0700,Reach-1,3
Up Type=0
Dn Type=3
Dn Slope=0.005
Boundary for River Rch & Prof#=Stream0700,Reach-1,4
Up Type=0
Dn Type=3
Dn Slope=0.005
Boundary for River Rch & Prof#=Stream0700,Reach-1,5
Up Type=0
Dn Type=3
Dn Slope=0.005
Boundary for River Rch & Prof#=Stream0700,Reach-1,6
Up Type=0
Dn Type=3
Dn Slope=0.005
Boundary for River Rch & Prof#=Stream0700,Reach-1,7
Up Type=0
Dn Type=3
Dn Slope=0.005

--- Stream0700.g01 (geometry) ---

Geom Title=Existing Conditions

River Reach=Stream0700,Reach-1
Reach XY= 30
      2407375.00     13697025.00      2407385.51     13696965.21
      2407708.35     13696641.67      2407733.18     13696568.96
      2407821.53     13696473.50      2407822.84     13696380.98
      2407775.51     13696309.78      2407780.45     13696172.55
      2407914.22     13696034.68      2407941.65     13695958.33
      2408167.14     13695731.17      2408185.45     13695614.92
      2408273.37     13695563.16      2408271.46     13695426.48
      2408185.21     13695334.67      2408174.50     13695300.03
      2408267.20     13695121.59      2408183.83     13695018.00
      2408230.44     13694977.07      2408388.35     13694961.64
      2408467.14     13694881.19      2408480.52     13694772.57
      2408614.21     13694634.66      2408644.63     13694554.32
      2408704.73     13694524.62      2408781.16     13694573.21
      2408831.39     13694567.65      2408873.02     13694519.37
      2408877.72     13694382.71      2408925.00     13694375.00

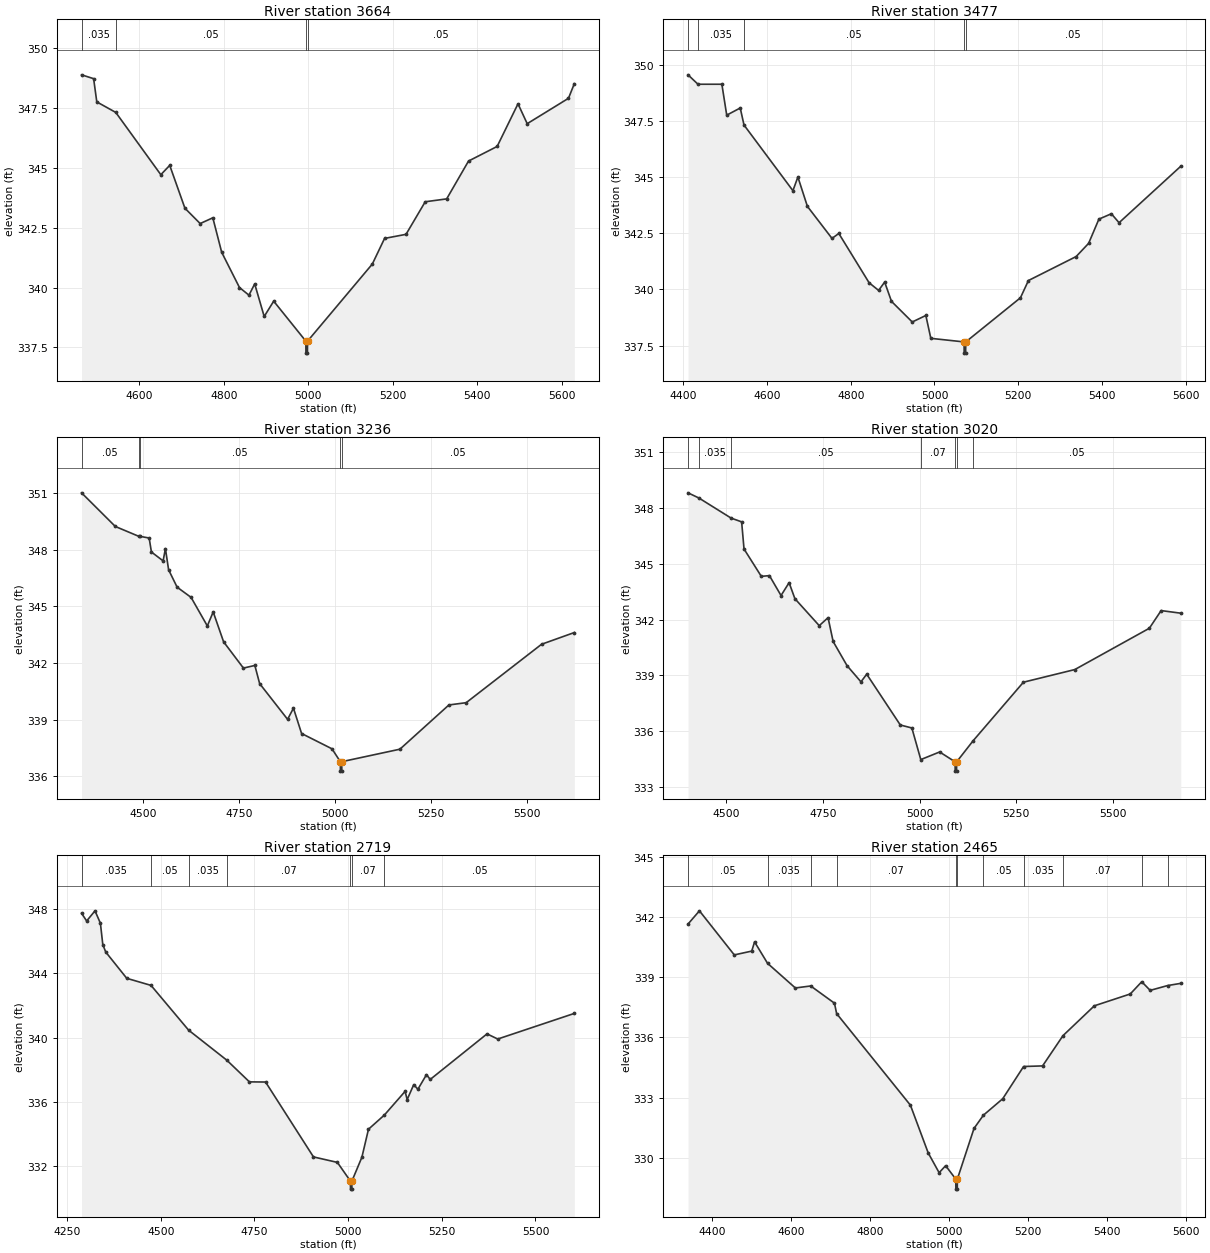
Type RM Length L Ch R = 1,3664,187,187,187
BEGIN DESCRIPTION:
Stream0700 6.0
END DESCRIPTION:
XS GIS Cut Line= 3
      2407825.02     13697275.02      2407375.00     13696975.00
      2406824.97     13697275.02
#Sta/Elev= 30
  4462.8  348.88  4491.4  348.72  4498.9  347.75  4543.9  347.31  4650.6  344.71
  4671.7  345.10  4707.7  343.31  4743.8  342.67  4773.8  342.91  4794.8  341.47
  4836.9  340.00  4859.4  339.68  4873.0  340.15  4895.5  338.79  4918.0  339.43
  4994.2  337.76  4994.4  337.26  4997.9  337.26  4998.2  337.76  5151.7  340.98
  5180.7  342.05  5231.5  342.22  5277.0  343.58  5327.8  343.70  5379.6  345.28
  5447.4  345.89  5496.8  347.67  5518.6  346.84  5616.4  347.90  5630.2  348.51
#Mann=4,-1,0
  4462.8   0.035       0  4543.9    0.05       0  4994.2    0.05       0
  4998.2    0.05       0
Bank Sta=4994.2,4998.2
Exp/Cntr=0.3,0.1

Type RM Length L Ch R = 1,3477,241,241,241
BEGIN DESCRIPTION:
E21281
END DESCRIPTION:
XS GIS Cut Line= 3
      2408026.54     13697120.75      2407353.70     13696760.43
      2406967.63     13696911.18
#Sta/Elev= 30
  4411.0  349.58  4434.8  349.16  4491.9  349.16  4503.5  347.78  4535.8  348.10
  4544.8  347.34  4661.7  344.41  4673.6  345.02  4696.3  343.71  4755.1  342.28
  4771.4  342.50  4843.8  340.30  4866.5  339.96  4881.0  340.33  4897.3  339.47
  4946.9  338.55  4979.4  338.84  4991.3  337.82  5070.8  337.66  5071.0  337.16
  5074.5  337.16  5074.8  337.66  5205.5  339.63  5224.6  340.40  5338.6  341.47
  5368.5  342.06  5393.0  343.14  5422.8  343.38  5441.2  342.98  5588.7  345.50
#Mann=5,-1,0
  4411.0    0.05       0  4434.8   0.035       0  4544.8    0.05       0
  5070.8    0.05       0  5074.8    0.05       0
Bank Sta=5070.8,5074.8
Exp/Cntr=0.3,0.1

Type RM Length L Ch R = 1,3236,216,216,216
BEGIN DESCRIPTION:
XS7495
END DESCRIPTION:
XS GIS Cut Line= 3
      2408236.79     13697025.68      2407611.81     13696629.86
      2407070.18     13696692.36
#Sta/Elev= 30
  4339.0  351.00  4427.1  349.22  4488.2  348.70  4490.6  348.70  4515.3  348.61
  4521.2  347.87  4551.7  347.40  4557.7  348.05  4566.0  346.93  4588.2  346.01
  4624.6  345.47  4667.0  343.96  4682.3  344.70  4709.4  343.12  4761.1  341.73
  4790.9  341.87  4803.4  340.91  4876.3  339.02  4891.6  339.61  4912.8  338.27
  4992.1  337.46  5013.8  336.78  5014.1  336.28  5017.6  336.28  5017.8  336.78
  5169.2  337.44  5297.0  339.78  5342.0  339.90  5538.6  342.99  5624.0  343.61
#Mann=5,-1,0
  4339.0    0.05       0  4488.2   0.035       0  4490.6    0.05       0
  5013.8    0.05       0  5017.8    0.05       0
Bank Sta=5013.8,5017.8
Exp/Cntr=0.3,0.1

Type RM Length L Ch R = 1,3020,301,301,301
BEGIN DESCRIPTION:
E21280
END DESCRIPTION:
XS GIS Cut Line= 3
      2408295.02     13696837.67      2407691.98     13696429.51
      2407155.15     13696532.46
#Sta/Elev= 30
  4400.8  348.81  4429.1  348.53  4512.4  347.45  4539.5  347.25  4545.7  345.79
  4590.4  344.32  4611.4  344.36  4641.4  343.29  4662.3  343.98  4677.3  343.12
  4740.3  341.67  4763.1  342.10  4776.2  340.82  4812.2  339.52  4848.2  338.65
  4863.1  339.06  4950.0  336.33  4979.9  336.17  5003.0  334.47  5051.8  334.88
  5091.8  334.35  5092.0  333.85  5095.5  333.85  5095.8  334.35  5138.3  335.48
  5268.5  338.63  5401.5  339.31  5594.3  341.53  5624.8  342.48  5675.6  342.34
#Mann=7,-1,0
  4400.8    0.05       0  4429.1   0.035       0  4512.4    0.05       0
  5003.0    0.07       0  5091.8    0.05       0  5095.8    0.07       0
  5138.3    0.05       0
Bank Sta=5091.8,5095.8
Exp/Cntr=0.3,0.1

Type RM Length L Ch R = 1,2719,254,254,254
BEGIN DESCRIPTION:
Stream0700 5.0
END DESCRIPTION:
XS GIS Cut Line= 3
      2408325.01     13696675.00      2407775.00     13696225.00
      2407224.99     13696475.00
#Sta/Elev= 30
  4288.8  347.72  4302.4  347.24  4324.7  347.87  4339.1  347.10  4345.5  345.77
  4353.4  345.31  4409.4  343.68  4474.2  343.24  4574.5  340.46  4676.2  338.60
  4736.7  337.25  4779.8  337.24  4907.6  332.59  4971.4  332.25  5006.2  331.09
  5006.5  330.59  5010.0  330.59  5010.2  331.09  5036.8  332.57  5054.4  334.31
  5096.8  335.19  5152.1  336.66  5157.6  336.15  5175.2  337.08  5186.2  336.79
  5209.2  337.70  5219.1  337.40  5370.7  340.23  5399.3  339.91  5603.6  341.50
#Mann=7,-1,0
  4288.8   0.035       0  4474.2    0.05       0  4574.5   0.035       0
  4676.2    0.07       0  5006.2    0.05       0  5010.2    0.07       0
  5096.8    0.05       0
Bank Sta=5006.2,5010.2
Exp/Cntr=0.3,0.1

Type RM Length L Ch R = 1,2465,231,231,231
BEGIN DESCRIPTION:
E21279
END DESCRIPTION:
XS GIS Cut Line= 3
      2408504.53     13696333.89      2407820.67     13695977.25
      2407348.22     13696043.18
#Sta/Elev= 30
  4339.1  341.66  4368.0  342.32  4456.3  340.12  4500.5  340.31  4507.7  340.77
  4540.6  339.70  4611.0  338.47  4649.9  338.57  4710.1  337.71  4715.6  337.19
  4902.5  332.62  4947.5  330.24  4975.2  329.25  4991.7  329.60  5017.4  328.93
  5017.7  328.43  5021.2  328.43  5021.4  328.93  5063.6  331.46  5087.4  332.12
  5136.3  332.94  5189.2  334.55  5237.3  334.58  5289.0  336.09  5368.5  337.58
  5459.4  338.17  5488.5  338.78  5509.9  338.35  5554.0  338.59  5587.4  338.70
#Mann=11,-1,0
  4339.1    0.05       0  4540.6   0.035       0  4649.9    0.05       0
  4715.6    0.07       0  5017.4    0.05       0  5021.4    0.07       0
  5087.4    0.05       0  5189.2   0.035       0  5289.0    0.07       0
  5488.5    0.05       0  5554.0    0.07       0
Bank Sta=5017.4,5021.4
Exp/Cntr=0.3,0.1

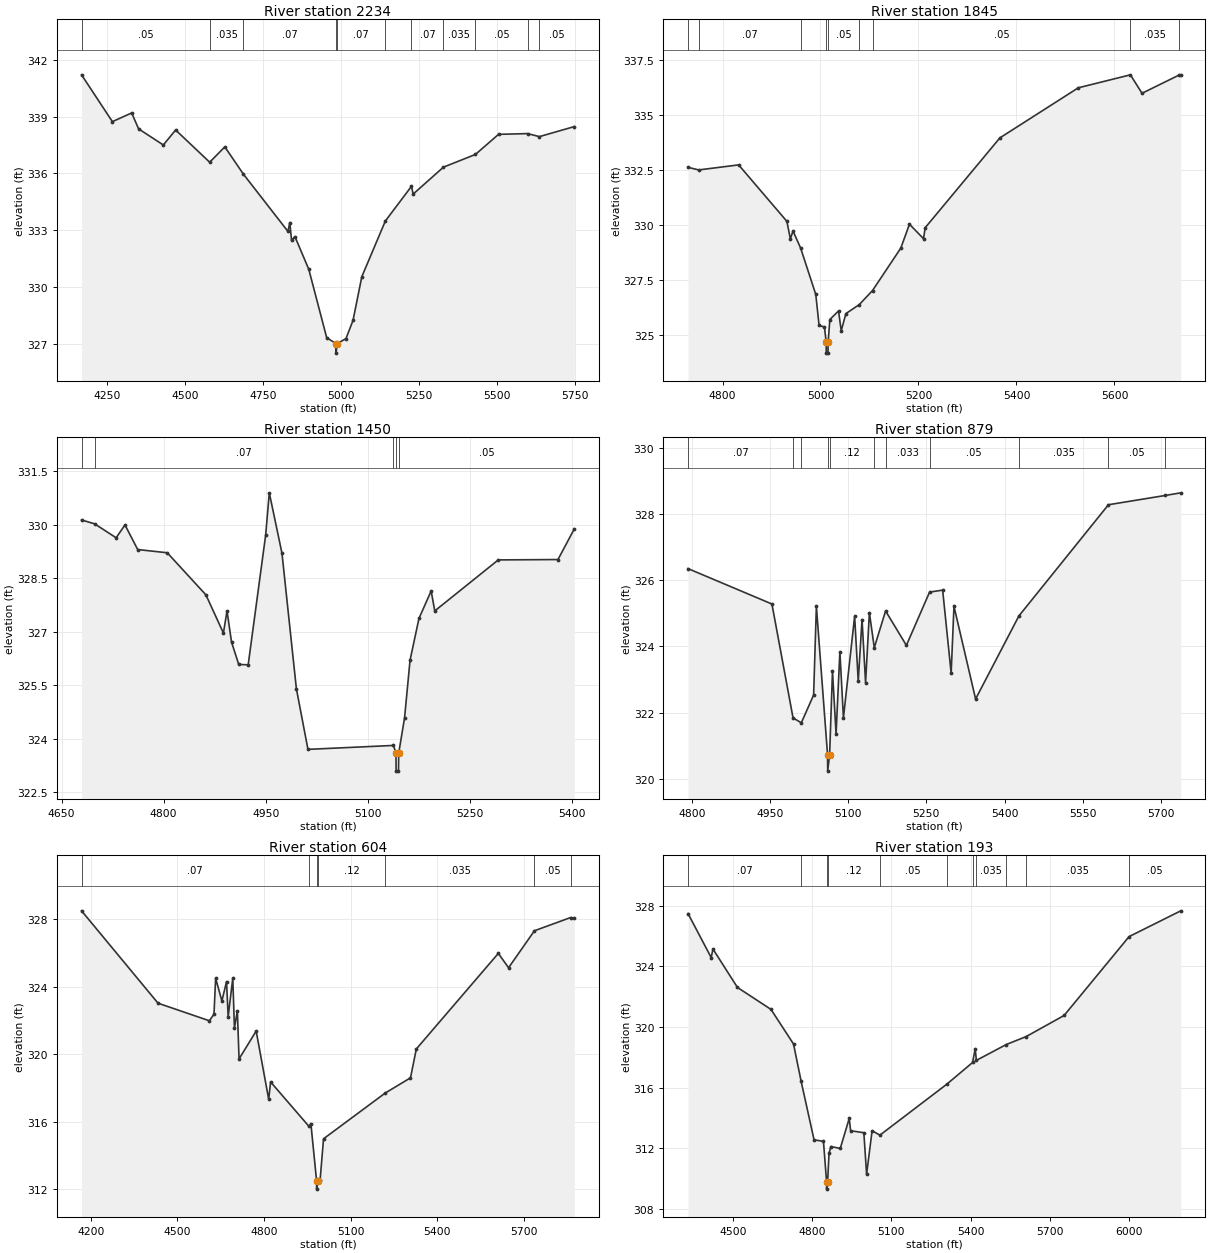
Type RM Length L Ch R = 1,2234,389,389,389
BEGIN DESCRIPTION:
XS7494
END DESCRIPTION:
XS GIS Cut Line= 3
      2408799.27     13696213.18      2407875.69     13695761.81
      2407342.27     13695900.36
#Sta/Elev= 30
  4168.3  341.20  4267.1  338.73  4328.9  339.19  4351.1  338.35  4430.3  337.50
  4469.8  338.29  4578.9  336.59  4627.4  337.40  4687.0  335.96  4829.7  332.94
  4835.7  333.41  4841.2  332.47  4852.0  332.67  4896.5  330.94  4953.8  327.34
  4983.6  327.02  4983.8  326.52  4987.6  327.02  5015.8  327.29  5038.3  328.25
  5066.4  330.55  5141.9  333.49  5225.6  335.32  5231.0  334.91  5328.0  336.33
  5430.5  337.00  5504.5  338.06  5597.8  338.10  5635.4  337.94  5747.4  338.47
#Mann=11,-1,0
  4168.3    0.05       0  4578.9   0.035       0  4687.0    0.07       0
  4983.6    0.05       0  4987.6    0.07       0  5141.9    0.05       0
  5225.6    0.07       0  5328.0   0.035       0  5430.5    0.05       0
  5597.8    0.07       0  5635.4    0.05       0
Bank Sta=4983.6,4987.6
Exp/Cntr=0.3,0.1

Type RM Length L Ch R = 1,1845,395,395,395
BEGIN DESCRIPTION:
E21278
END DESCRIPTION:
XS GIS Cut Line= 3
      2408519.30     13695675.76      2408074.37     13695477.20
      2407555.92     13695488.23
#Sta/Elev= 30
  4729.6  332.63  4751.3  332.51  4832.9  332.74  4931.4  330.17  4938.5  329.37
  4943.9  329.73  4959.5  328.95  4990.4  326.84  4997.1  325.43  5008.1  325.36
  5011.6  324.67  5011.8  324.17  5015.3  324.17  5015.6  324.67  5019.1  325.70
  5036.8  326.09  5042.3  325.19  5051.9  325.97  5079.2  326.38  5106.2  327.02
  5163.9  328.95  5181.6  330.04  5210.3  329.38  5213.7  329.88  5366.2  333.97
  5526.3  336.25  5632.6  336.84  5656.3  336.00  5731.1  336.82  5735.4  336.82
#Mann=9,-1,0
  4729.6    0.05       0  4751.3    0.07       0  4959.5    0.05       0
  5011.6    0.05       0  5015.6    0.05       0  5079.2    0.07       0
  5106.2    0.05       0  5632.6   0.035       0  5731.1    0.05       0
Bank Sta=5011.6,5015.6
Exp/Cntr=0.3,0.1

Type RM Length L Ch R = 1,1450,571,571,571
BEGIN DESCRIPTION:
E21277
END DESCRIPTION:
XS GIS Cut Line= 2
      2408522.93     13695330.11      2407839.55     13695091.30
#Sta/Elev= 30
  4679.4  330.13  4698.7  330.02  4730.2  329.63  4743.2  329.99  4761.9  329.30
  4805.3  329.21  4862.1  328.03  4887.8  326.96  4893.1  327.58  4899.7  326.71
  4910.3  326.08  4924.2  326.07  4949.9  329.71  4955.2  330.89  4973.8  329.20
  4995.0  325.40  5012.0  323.70  5137.6  323.81  5141.3  323.59  5141.5  323.09
  5145.0  323.09  5145.3  323.59  5153.9  324.58  5162.0  326.20  5175.1  327.37
  5193.0  328.14  5198.3  327.58  5291.6  329.01  5379.3  329.02  5403.3  329.88
#Mann=5,-1,0
  4679.4    0.05       0  4698.7    0.07       0  5137.6    0.05       0
  5141.3    0.05       0  5145.3    0.05       0
Bank Sta=5141.3,5145.3
Exp/Cntr=0.3,0.1

Type RM Length L Ch R = 1,879,275,275,275
BEGIN DESCRIPTION:
E21276
END DESCRIPTION:
XS GIS Cut Line= 5
      2408526.62     13695091.10      2408431.03     13694837.42
      2408368.53     13694778.59      2408199.39     13694841.09
      2407842.69     13695039.67
#Sta/Elev= 30
  4792.7  326.35  4953.7  325.28  4994.2  321.84  5010.1  321.69  5033.7  322.53
  5039.0  325.21  5060.4  320.73  5060.7  320.23  5064.4  320.73  5069.9  323.25
  5076.8  321.36  5084.1  323.84  5090.9  321.84  5112.4  324.91  5119.3  322.95
  5126.6  324.81  5133.4  322.90  5140.7  325.02  5150.1  323.96  5171.8  325.07
  5211.7  324.03  5256.2  325.64  5281.3  325.70  5297.6  323.19  5303.0  325.21
  5344.5  322.41  5427.6  324.92  5599.4  328.28  5708.3  328.56  5738.2  328.64
#Mann=11,-1,0
  4792.7    0.07       0  4994.2   0.033       0  5010.1    0.12       0
  5060.4   0.033       0  5064.4    0.12       0  5150.1    0.05       0
  5171.8   0.033       0  5256.2    0.05       0  5427.6   0.035       0
  5599.4    0.05       0  5708.3   0.035       0
Bank Sta=5060.4,5064.4
Exp/Cntr=0.3,0.1

Type RM Length L Ch R = 1,604,411,411,411
BEGIN DESCRIPTION:
E21275
END DESCRIPTION:
XS GIS Cut Line= 4
      2409306.15     13695076.42      2408511.92     13694631.51
      2408239.83     13694668.28      2407818.48     13694976.05
#Sta/Elev= 30
  4168.2  328.50  4433.1  323.03  4610.9  321.99  4626.9  322.38  4632.6  324.51
  4654.3  323.16  4670.3  324.31  4676.0  322.24  4692.0  324.51  4697.7  321.56
  4707.9  322.58  4713.7  319.73  4773.0  321.38  4816.4  317.34  4822.9  318.37
  4956.2  315.73  4962.5  315.90  4982.2  312.52  4982.4  312.02  4986.2  312.52
  4994.4  312.55  5006.3  315.00  5220.0  317.71  5307.5  318.61  5327.7  320.32
  5611.7  325.98  5647.2  325.13  5736.8  327.32  5861.7  328.10  5874.9  328.07
#Mann=7,-1,0
  4168.2    0.07       0  4956.2    0.12       0  4982.2    0.05       0
  4986.2    0.12       0  5220.0   0.035       0  5736.8    0.05       0
  5861.7   0.035       0
Bank Sta=4982.2,4986.2
Exp/Cntr=0.3,0.1

Type RM Length L Ch R = 1,193,0,0,0
BEGIN DESCRIPTION:
E21274
END DESCRIPTION:
XS GIS Cut Line= 5
      2409350.23     13694973.44      2408964.18     13694550.62
      2408585.46     13694443.99      2408280.28     13694602.09
      2407835.36     13694933.03
#Sta/Elev= 30
  4330.9  327.49  4418.5  324.59  4425.3  325.15  4517.8  322.62  4644.8  321.17
  4730.0  318.89  4758.7  316.44  4807.7  312.57  4843.3  312.47  4855.0  309.82
  4855.2  309.32  4859.0  309.82  4864.4  311.68  4871.2  312.13  4906.8  312.00
  4940.8  313.98  4946.0  313.17  4996.1  313.04  5006.5  310.30  5027.3  313.17
  5056.9  312.88  5309.3  316.23  5407.5  317.67  5417.2  318.56  5421.9  317.81
  5534.4  318.85  5610.3  319.38  5753.7  320.77  5999.5  325.97  6195.1  327.67
#Mann=11,-1,0
  4330.9    0.07       0  4758.7    0.12       0  4855.0    0.05       0
  4859.0    0.12       0  5056.9    0.05       0  5309.3   0.035       0
  5407.5    0.05       0  5421.9   0.035       0  5534.4    0.12       0
  5610.3   0.035       0  5999.5    0.05       0
Bank Sta=4855,4859
Exp/Cntr=0.3,0.1

Chan Stop Cuts=-1