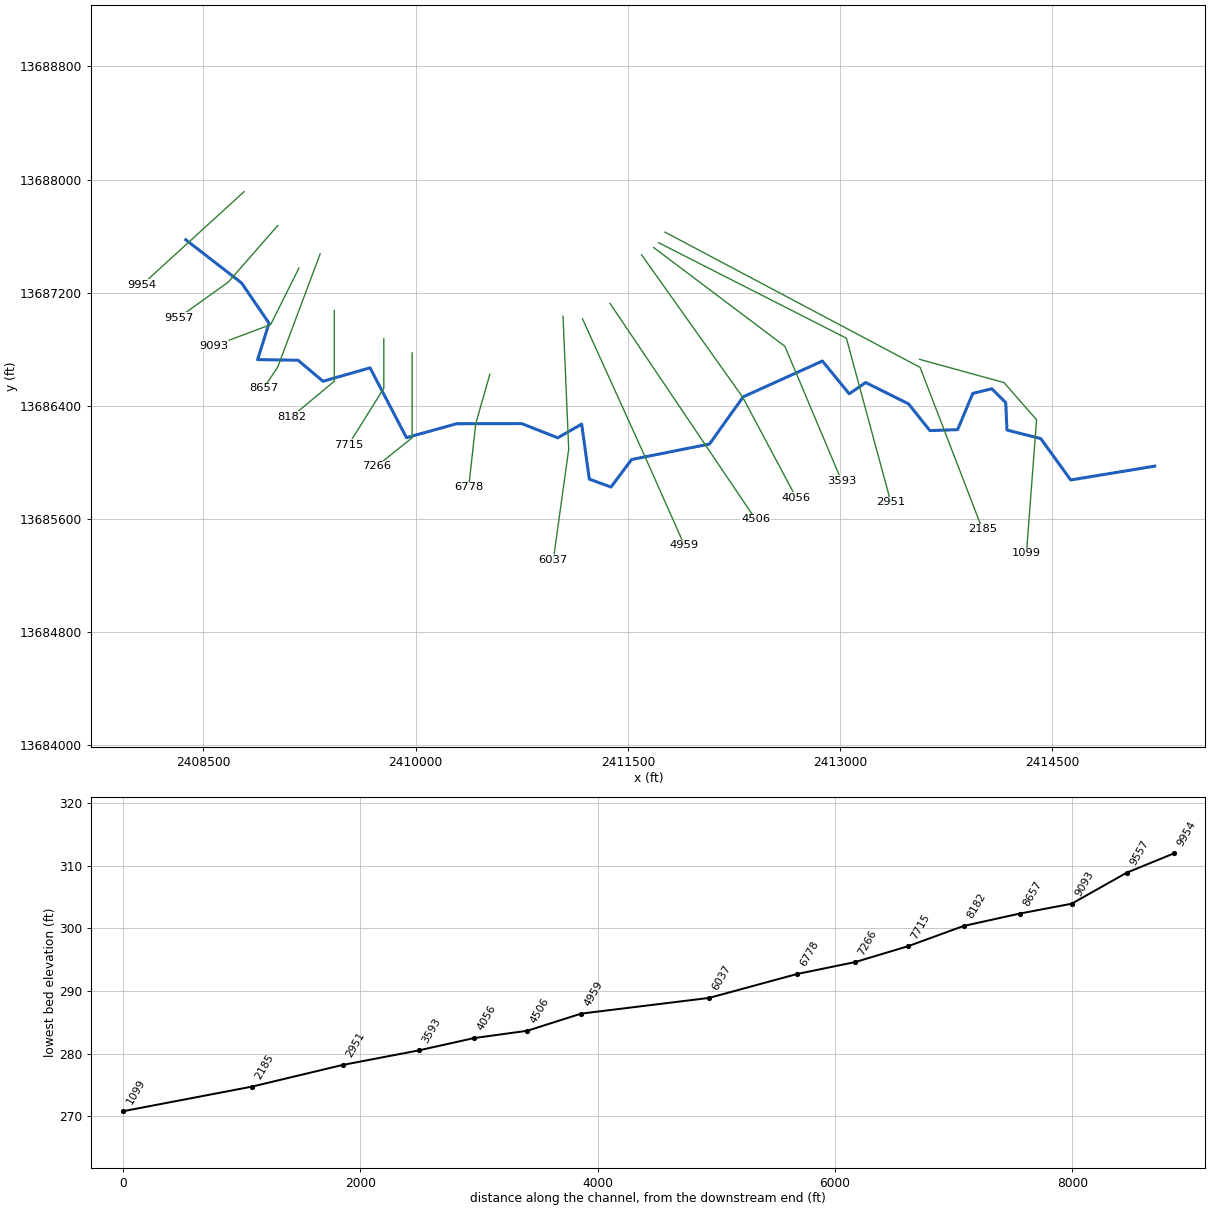
--- Stream0701.prj (project) ---

Proj Title=Stream0701 Base Level Engineering
Current Plan=p01
Default Exp/Contr=0.3,0.1
English Units
Geom File=g01
Flow File=f01
Plan File=p01
BEGIN DESCRIPTION:
Stream0701
END DESCRIPTION:

--- Stream0701.p01 (plan) ---

Plan Title=Multiple Run
Short Identifier=Multiple
Geom File=g01
Flow File=f01
Subcritical Flow
K Sum by GR= 0
Std Step Tol= 0.01
Critical Tol= 0.01
Num of Std Step Trials= 20
Max Error Tol= 0.3
Flow Tol Ratio= 0.001
Split Flow NTrial= 30
Split Flow Tol= 0.02
Split Flow Ratio= 0.02
Log Output Level= 0
Friction Slope Method= 1
Unsteady Friction Slope Method= 2
Unsteady Bridges Friction Slope Method= 1
Parabolic Critical Depth
Global Vel Dist=  1 , 1 , 1
Global Log Level= 0
CheckData=True
Encroach Param= -1, 0, 0, 0
BEGIN DESCRIPTION:
Multiple Run
END DESCRIPTION:

--- Stream0701.f01 (steady flow) ---

Flow Title=Multiple
Number of Profiles=7
Profile Names=10-year,25-year,50-year,1pct_min,100-year,1pct_plu,500-year
River Rch & RM= Stream0701,Reach-1,9954
     748    1215    1638    1070    2135    4259    3589
River Rch & RM= Stream0701,Reach-1,6778
     856    1397    1889    1236    2467    4922    4167
Boundary for River Rch & Prof#=Stream0701,Reach-1,1
Up Type=0
Dn Type=3
Dn Slope=0.005
Boundary for River Rch & Prof#=Stream0701,Reach-1,2
Up Type=0
Dn Type=3
Dn Slope=0.005
Boundary for River Rch & Prof#=Stream0701,Reach-1,3
Up Type=0
Dn Type=3
Dn Slope=0.005
Boundary for River Rch & Prof#=Stream0701,Reach-1,4
Up Type=0
Dn Type=3
Dn Slope=0.005
Boundary for River Rch & Prof#=Stream0701,Reach-1,5
Up Type=0
Dn Type=3
Dn Slope=0.005
Boundary for River Rch & Prof#=Stream0701,Reach-1,6
Up Type=0
Dn Type=3
Dn Slope=0.005
Boundary for River Rch & Prof#=Stream0701,Reach-1,7
Up Type=0
Dn Type=3
Dn Slope=0.005

--- Stream0701.g01 (geometry) ---

Geom Title=Existing Conditions

River Reach=Stream0701,Reach-1
Reach XY= 30
      2408375.00     13687575.00      2408769.53     13687269.74
      2408963.90     13686985.04      2408882.88     13686728.03
      2409168.96     13686723.38      2409345.05     13686574.79
      2409677.68     13686669.71      2409935.43     13686176.04
      2410290.16     13686274.61      2410750.03     13686275.48
      2411005.01     13686174.94      2411173.60     13686272.01
      2411227.93     13685882.97      2411381.17     13685826.76
      2411526.25     13686021.49      2412077.31     13686130.82
      2412315.19     13686464.49      2412875.34     13686717.78
      2413065.01     13686485.98      2413181.55     13686565.75
      2413484.81     13686414.49      2413635.28     13686225.98
      2413831.48     13686232.69      2413938.23     13686488.73
      2414073.51     13686521.55      2414171.47     13686423.55
      2414180.00     13686230.01      2414419.38     13686169.38
      2414630.69     13685876.88      2415225.00     13685975.00

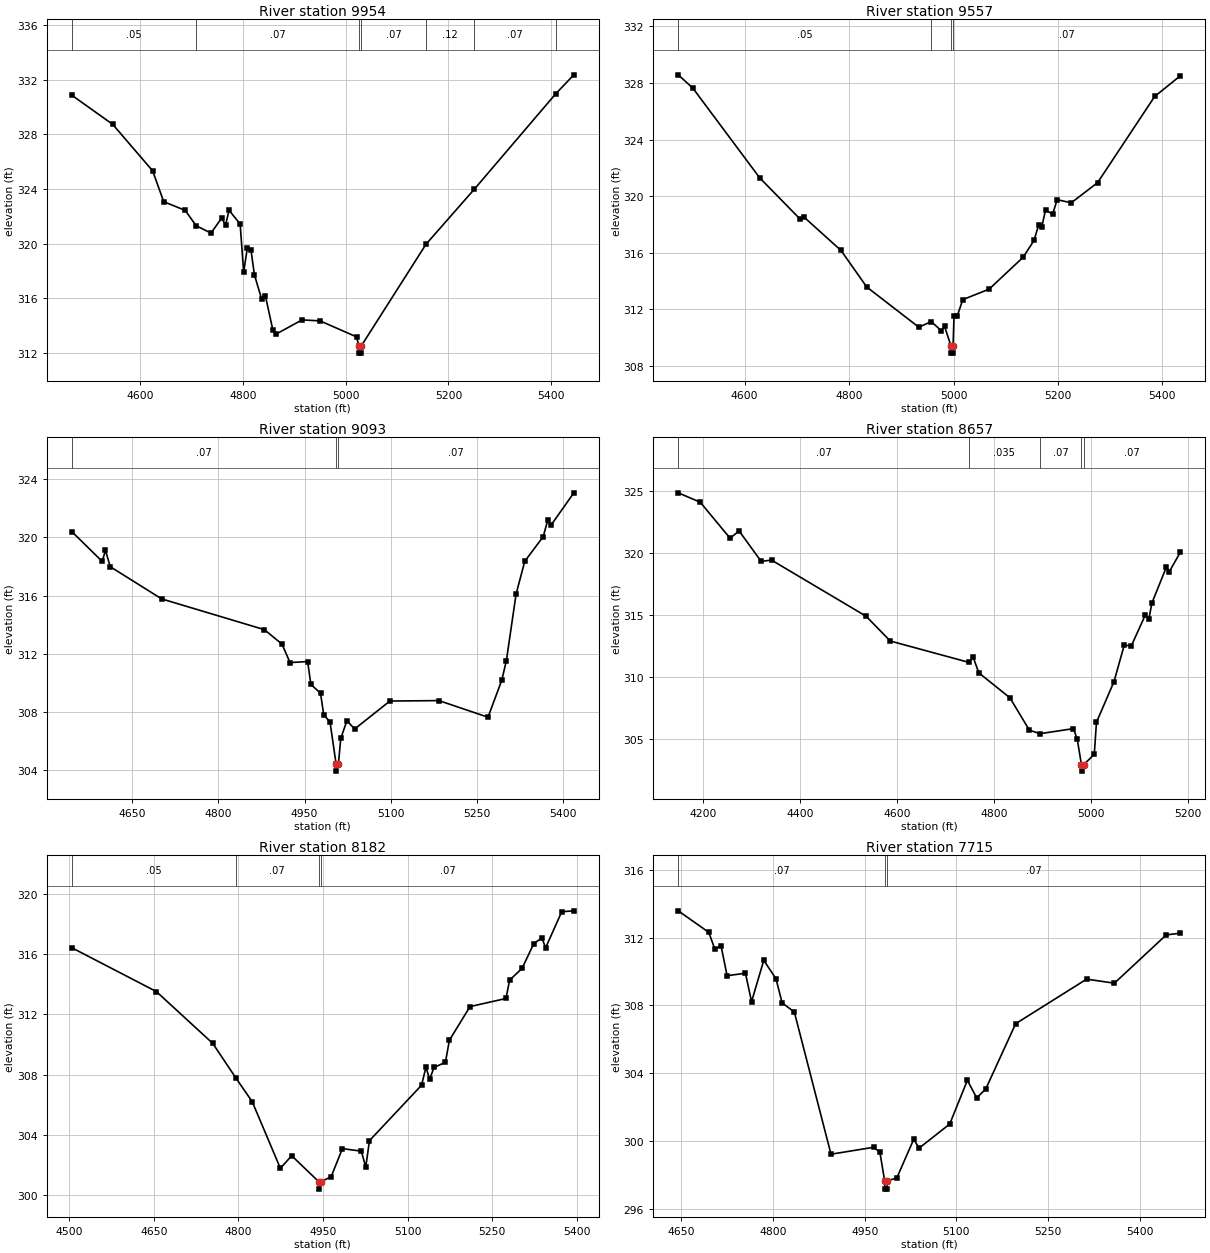
Type RM Length L Ch R = 1,9954,397,397,397
BEGIN DESCRIPTION:
XS7503
END DESCRIPTION:
XS GIS Cut Line= 2
      2408787.25     13687914.89      2408066.14     13687256.74
#Sta/Elev= 30
  4467.6  330.86  4547.1  328.73  4624.8  325.33  4646.4  323.07  4688.3  322.43
  4709.2  321.32  4738.3  320.77  4759.2  321.88  4766.6  321.35  4773.4  322.44
  4795.0  321.44  4801.8  317.92  4809.1  319.70  4816.0  319.56  4822.7  317.73
  4836.9  315.93  4844.3  316.15  4858.5  313.70  4865.3  313.39  4915.3  314.42
  4950.4  314.35  5021.3  313.18  5026.1  312.49  5026.4  311.99  5029.9  311.99
  5030.1  312.49  5156.5  319.96  5250.1  323.97  5408.6  330.96  5443.9  332.35
#Mann=7,-1,0
  4467.6    0.05       0  4709.2    0.07       0  5026.1    0.05       0
  5030.1    0.07       0  5156.5    0.12       0  5250.1    0.07       0
  5408.6   0.035       0
Bank Sta=5026.1,5030.1
Exp/Cntr=0.3,0.1

Type RM Length L Ch R = 1,9557,464,464,464
BEGIN DESCRIPTION:
Stream0701 19.0
END DESCRIPTION:
XS GIS Cut Line= 3
      2409024.99     13687674.99      2408675.00     13687275.00
      2408325.01     13687025.00
#Sta/Elev= 30
  4472.8  328.57  4500.8  327.63  4628.9  321.29  4706.7  318.36  4713.4  318.53
  4784.6  316.16  4833.9  313.58  4933.6  310.74  4957.5  311.14  4976.3  310.50
  4982.9  310.80  4995.2  309.41  4995.4  308.91  4998.9  308.91  4999.2  309.41
  5001.0  311.56  5007.4  311.56  5017.8  312.69  5068.2  313.43  5133.3  315.68
  5154.2  316.87  5162.8  317.93  5169.0  317.82  5176.3  319.02  5189.9  318.72
  5198.5  319.75  5225.5  319.53  5275.9  320.95  5385.3  327.04  5434.4  328.50
#Mann=4,-1,0
  4472.8    0.05       0  4957.5    0.07       0  4995.2    0.05       0
  4999.2    0.07       0
Bank Sta=4995.2,4999.2
Exp/Cntr=0.3,0.1

Type RM Length L Ch R = 1,9093,436,436,436
BEGIN DESCRIPTION:
Stream0701 18.0
END DESCRIPTION:
XS GIS Cut Line= 3
      2409174.98     13687374.97      2408975.00     13686975.00
      2408574.98     13686824.99
#Sta/Elev= 30
  4544.5  320.39  4597.6  318.34  4603.2  319.11  4611.5  317.98  4701.0  315.77
  4879.9  313.66  4910.6  312.67  4924.6  311.40  4955.3  311.47  4960.9  309.90
  4977.7  309.30  4983.3  307.83  4994.3  307.31  5004.8  304.45  5005.0  303.95
  5008.9  304.45  5013.0  306.20  5023.7  307.41  5037.1  306.84  5098.5  308.76
  5183.9  308.79  5269.4  307.65  5293.4  310.19  5301.4  311.53  5318.3  316.10
  5333.4  318.35  5365.5  320.04  5373.5  321.18  5378.8  320.81  5418.9  323.05
#Mann=3,-1,0
  4544.5    0.07       0  5004.8    0.05       0  5008.9    0.07       0
Bank Sta=5004.8,5008.9
Exp/Cntr=0.3,0.1

Type RM Length L Ch R = 1,8657,475,475,475
BEGIN DESCRIPTION:
Stream0701 17.0
END DESCRIPTION:
XS GIS Cut Line= 3
      2409325.01     13687475.01      2409025.00     13686675.00
      2408925.00     13686524.99
#Sta/Elev= 30
  4149.4  324.84  4194.8  324.08  4256.2  321.18  4274.9  321.76  4320.3  319.31
  4341.7  319.41  4536.6  314.88  4586.4  312.88  4748.1  311.16  4757.3  311.56
  4768.9  310.31  4832.9  308.30  4873.0  305.69  4894.7  305.40  4963.8  305.81
  4971.8  304.94  4980.4  302.88  4980.7  302.38  4984.6  302.88  5006.8  303.74
  5011.3  306.32  5047.4  309.60  5068.4  312.53  5083.4  312.51  5112.0  314.98
  5119.5  314.69  5125.5  315.94  5155.5  318.86  5161.6  318.49  5184.1  320.04
#Mann=5,-1,0
  4149.4    0.07       0  4748.1   0.035       0  4894.7    0.07       0
  4980.4    0.05       0  4984.6    0.07       0
Bank Sta=4980.4,4984.6
Exp/Cntr=0.3,0.1

Type RM Length L Ch R = 1,8182,467,467,467
BEGIN DESCRIPTION:
Stream0701 16.0
END DESCRIPTION:
XS GIS Cut Line= 3
      2409425.00     13687074.97      2409425.00     13686575.00
      2409124.99     13686324.99
#Sta/Elev= 30
  4504.5  316.42  4654.5  313.51  4754.5  310.07  4795.2  307.79  4824.5  306.20
  4874.5  301.77  4894.5  302.61  4942.4  300.89  4942.6  300.39  4946.6  300.89
  4964.5  301.21  4984.5  303.08  5018.1  302.91  5025.9  301.85  5032.5  303.61
  5124.9  307.29  5132.7  308.49  5139.2  307.68  5147.0  308.47  5167.2  308.81
  5174.3  310.28  5210.8  312.51  5274.6  313.05  5281.1  314.27  5303.2  315.05
  5324.0  316.70  5338.4  317.07  5344.9  316.41  5373.5  318.81  5395.0  318.87
#Mann=4,-1,0
  4504.5    0.05       0  4795.2    0.07       0  4942.4    0.05       0
  4946.6    0.07       0
Bank Sta=4942.4,4946.6
Exp/Cntr=0.3,0.1

Type RM Length L Ch R = 1,7715,449,449,449
BEGIN DESCRIPTION:
Stream0701 15.0
END DESCRIPTION:
XS GIS Cut Line= 3
      2409775.00     13686874.97      2409775.00     13686525.00
      2409524.99     13686124.98
#Sta/Elev= 30
  4644.7  313.58  4694.7  312.31  4704.7  311.31  4714.7  311.52  4724.7  309.75
  4754.7  309.90  4764.7  308.22  4784.7  310.66  4804.7  309.57  4814.7  308.15
  4834.7  307.61  4894.7  299.22  4964.7  299.63  4974.7  299.34  4982.5  297.66
  4982.8  297.16  4986.6  297.16  4986.8  297.66  5002.3  297.81  5030.1  300.10
  5038.9  299.58  5089.0  301.00  5117.9  303.58  5133.2  302.54  5148.0  303.07
  5196.9  306.92  5313.1  309.55  5358.5  309.31  5443.4  312.16  5466.4  312.26
#Mann=3,-1,0
  4644.7    0.07       0  4982.5    0.05       0  4986.8    0.07       0
Bank Sta=4982.5,4986.8
Exp/Cntr=0.3,0.1

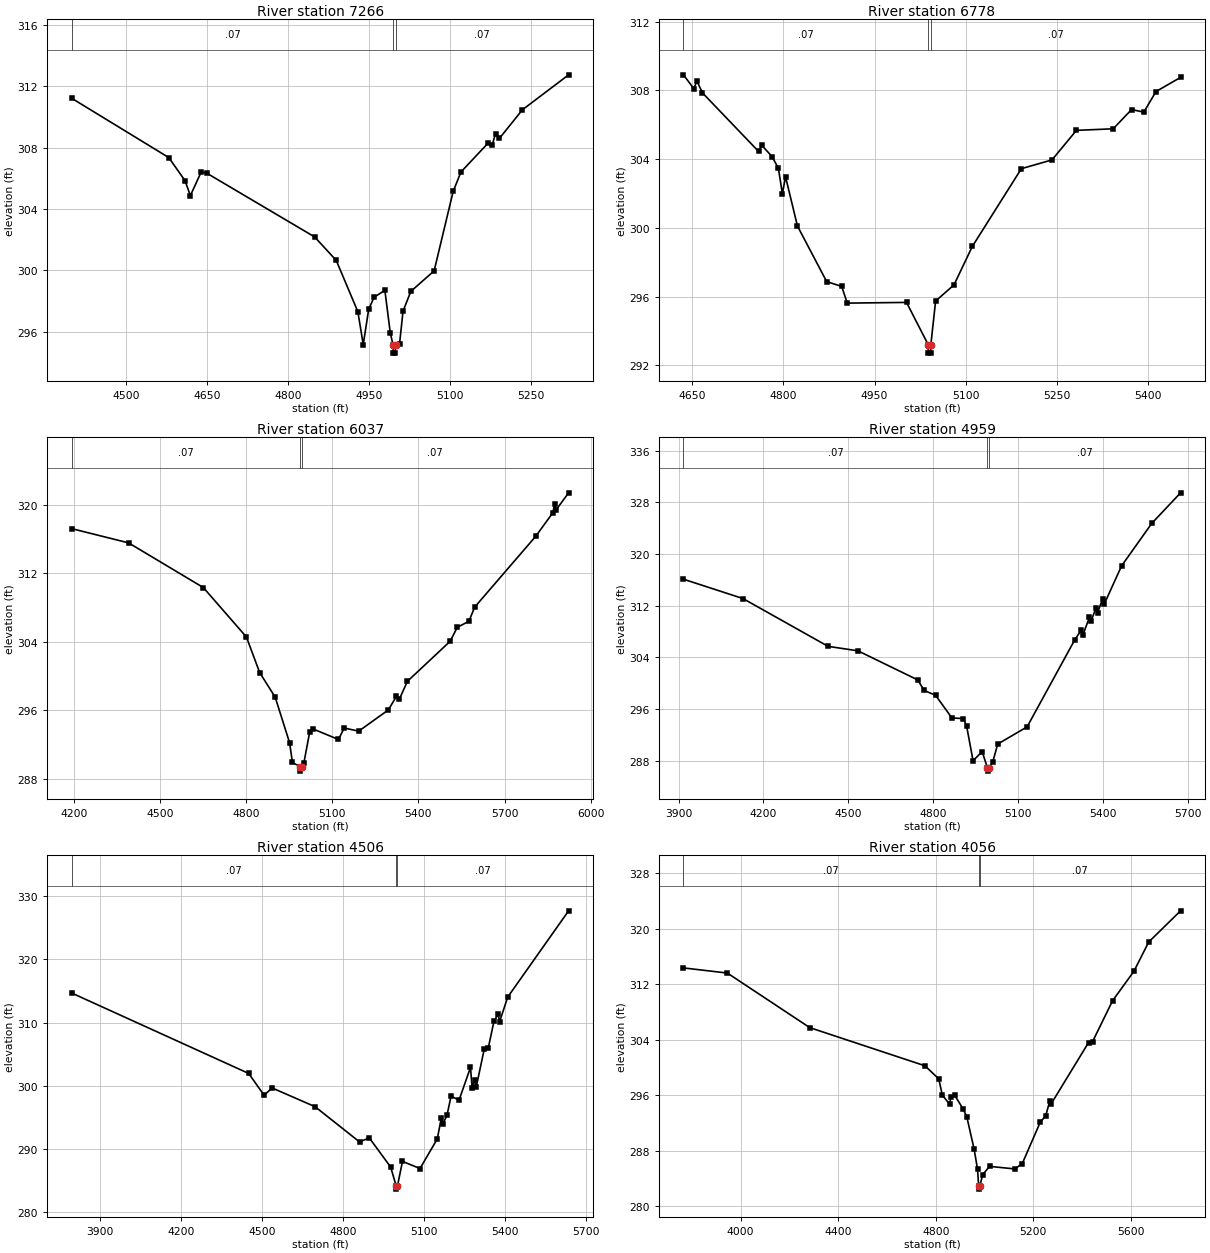
Type RM Length L Ch R = 1,7266,488,488,488
BEGIN DESCRIPTION:
Stream0701 14.0
END DESCRIPTION:
XS GIS Cut Line= 3
      2409975.00     13686774.99      2409975.00     13686175.00
      2409725.04     13685975.03
#Sta/Elev= 30
  4399.3  311.22  4579.3  307.35  4609.3  305.85  4619.3  304.87  4639.3  306.41
  4649.3  306.34  4849.3  302.18  4889.3  300.65  4929.3  297.31  4939.3  295.17
  4949.3  297.46  4959.3  298.25  4979.3  298.70  4989.3  295.94  4994.6  295.11
  4994.9  294.61  4998.7  294.61  4999.0  295.11  5006.5  295.22  5012.9  297.34
  5027.3  298.63  5070.5  299.97  5105.7  305.14  5120.1  306.41  5169.8  308.27
  5177.8  308.16  5184.2  308.90  5191.4  308.60  5233.8  310.46  5319.4  312.74
#Mann=3,-1,0
  4399.3    0.07       0  4994.6    0.05       0  4999.0    0.07       0
Bank Sta=4994.6,4999
Exp/Cntr=0.3,0.1

Type RM Length L Ch R = 1,6778,741,741,741
BEGIN DESCRIPTION:
Stream0701 13.0
END DESCRIPTION:
XS GIS Cut Line= 3
      2410525.01     13686625.02      2410425.00     13686275.00
      2410375.00     13685824.99
#Sta/Elev= 30
  4636.0  308.90  4652.9  308.10  4658.1  308.53  4667.2  307.85  4759.5  304.44
  4764.7  304.80  4781.6  304.14  4792.0  303.46  4798.5  301.98  4803.7  302.97
  4823.2  300.11  4871.3  296.87  4896.0  296.59  4905.1  295.62  5002.5  295.66
  5038.0  293.21  5038.3  292.71  5042.2  292.71  5042.5  293.21  5050.3  295.74
  5080.5  296.68  5110.7  298.92  5191.2  303.44  5241.5  303.95  5281.7  305.67
  5342.1  305.76  5372.3  306.88  5392.4  306.73  5412.5  307.93  5452.8  308.75
#Mann=3,-1,0
  4636.0    0.07       0  5038.0    0.05       0  5042.5    0.07       0
Bank Sta=5038,5042.5
Exp/Cntr=0.3,0.1

Type RM Length L Ch R = 1,6037,1078,1078,1078
BEGIN DESCRIPTION:
XS7502
END DESCRIPTION:
XS GIS Cut Line= 3
      2411042.03     13687033.59      2411082.09     13686095.04
      2410973.36     13685311.05
#Sta/Elev= 30
  4192.2  317.23  4391.0  315.56  4651.2  310.34  4801.3  304.56  4847.3  300.41
  4901.4  297.53  4951.5  292.21  4961.5  289.90  4989.2  289.39  4989.5  288.89
  4993.8  289.39  5001.5  289.88  5021.5  293.46  5031.6  293.84  5121.6  292.59
  5141.7  293.93  5192.2  293.56  5295.3  296.04  5323.5  297.62  5333.6  297.29
  5362.0  299.39  5510.5  304.06  5535.5  305.69  5575.9  306.40  5596.0  308.05
  5808.1  316.31  5868.6  319.10  5874.2  320.13  5879.3  319.41  5923.1  321.41
#Mann=3,-1,0
  4192.2    0.07       0  4989.2    0.05       0  4993.8    0.07       0
Bank Sta=4989.2,4993.8
Exp/Cntr=0.3,0.1

Type RM Length L Ch R = 1,4959,453,453,453
BEGIN DESCRIPTION:
XS7501
END DESCRIPTION:
XS GIS Cut Line= 3
      2411179.39     13687016.37      2411625.75     13686032.09
      2411900.24     13685414.50
#Sta/Elev= 30
  3917.4  316.08  4127.5  313.09  4428.4  305.69  4533.8  305.00  4745.0  300.50
  4768.1  298.86  4808.3  298.12  4865.9  294.61  4906.6  294.51  4918.1  293.33
  4940.7  287.99  4973.0  289.41  4991.4  286.88  4991.8  286.38  4996.2  286.88
  5010.0  287.75  5027.8  290.57  5131.7  293.23  5300.0  306.69  5323.3  308.22
  5328.7  307.44  5352.0  310.18  5357.5  309.58  5375.2  311.63  5380.7  310.90
  5398.5  313.02  5404.0  312.20  5465.5  318.14  5572.2  324.72  5674.0  329.45
#Mann=3,-1,0
  3917.4    0.07       0  4991.4    0.05       0  4996.2    0.07       0
Bank Sta=4991.4,4996.2
Exp/Cntr=0.3,0.1

Type RM Length L Ch R = 1,4506,450,450,450
BEGIN DESCRIPTION:
XS7500
END DESCRIPTION:
XS GIS Cut Line= 2
      2411373.94     13687125.16      2412403.10     13685598.57
#Sta/Elev= 30
  3793.5  314.69  4449.7  301.95  4506.6  298.51  4536.6  299.65  4695.5  296.69
  4860.4  291.11  4896.4  291.75  4975.6  287.13  4995.9  284.14  4996.3  283.64
  5000.7  284.14  5019.3  288.03  5084.1  286.90  5148.3  291.59  5163.2  294.93
  5169.3  294.01  5184.2  295.34  5199.2  298.35  5228.9  297.73  5271.2  302.90
  5277.2  299.71  5286.1  300.94  5292.2  299.74  5322.1  305.80  5337.1  305.99
  5358.1  310.19  5373.1  311.36  5379.1  310.15  5409.1  314.04  5634.6  327.69
#Mann=3,-1,0
  3793.5    0.07       0  4995.9    0.05       0  5000.7    0.07       0
Bank Sta=4995.9,5000.7
Exp/Cntr=0.3,0.1

Type RM Length L Ch R = 1,4056,463,463,463
BEGIN DESCRIPTION:
XS7499
END DESCRIPTION:
XS GIS Cut Line= 3
      2411597.16     13687468.48      2412312.49     13686461.30
      2412690.08     13685751.89
#Sta/Elev= 30
  3765.4  314.36  3945.3  313.62  4283.5  305.75  4755.9  300.25  4812.4  298.37
  4827.2  296.03  4856.7  294.73  4862.9  295.75  4877.6  296.02  4913.3  293.98
  4928.1  292.81  4957.6  288.24  4971.7  285.32  4976.1  282.97  4976.4  282.47
  4981.0  282.97  4993.3  284.57  5020.8  285.75  5125.0  285.38  5155.2  286.16
  5229.2  292.15  5251.2  293.04  5267.5  295.11  5273.1  294.74  5427.0  303.60
  5443.2  303.72  5525.4  309.62  5613.3  313.89  5673.6  318.09  5804.4  322.59
#Mann=3,-1,0
  3765.4    0.07       0  4976.1    0.05       0  4981.0    0.07       0
Bank Sta=4976.1,4981
Exp/Cntr=0.3,0.1

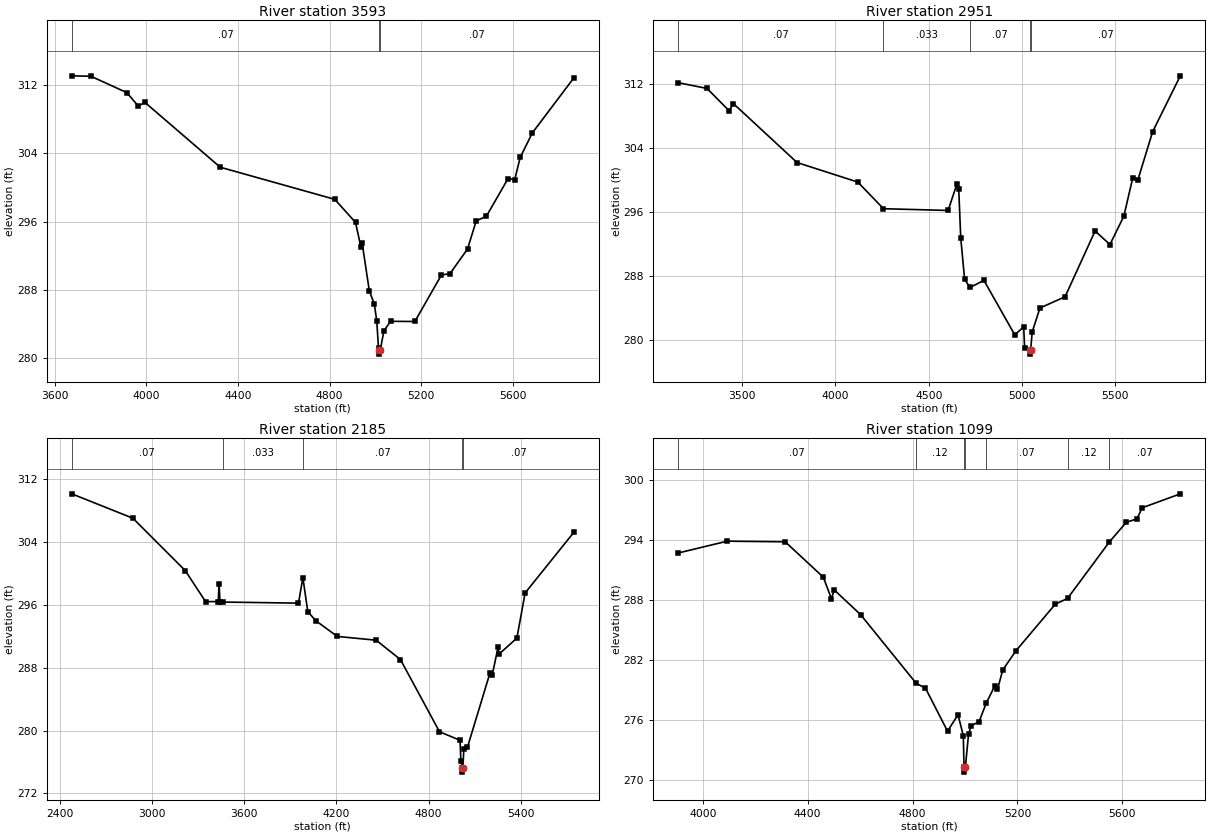
Type RM Length L Ch R = 1,3593,642,642,642
BEGIN DESCRIPTION:
XS7498
END DESCRIPTION:
XS GIS Cut Line= 3
      2411682.99     13687520.01      2412610.07     13686821.83
      2413010.33     13685872.65
#Sta/Elev= 30
  3675.1  313.09  3758.6  313.04  3915.5  311.12  3965.5  309.54  3993.9  309.99
  4322.9  302.39  4822.6  298.63  4913.2  295.93  4936.9  293.01  4942.3  293.47
  4973.3  287.93  4995.2  286.38  5005.9  284.40  5013.5  281.18  5016.4  281.01
  5016.8  280.51  5021.3  281.01  5037.2  283.25  5066.3  284.35  5172.1  284.33
  5288.1  289.78  5325.3  289.93  5401.8  292.81  5440.0  296.12  5483.9  296.64
  5578.7  301.06  5607.9  300.95  5631.6  303.53  5684.5  306.40  5865.8  312.85
#Mann=3,-1,0
  3675.1    0.07       0  5016.4    0.05       0  5021.3    0.07       0
Bank Sta=5016.4,5021.3
Exp/Cntr=0.3,0.1

Type RM Length L Ch R = 1,2951,766,766,766
BEGIN DESCRIPTION:
XS7497
END DESCRIPTION:
XS GIS Cut Line= 3
      2411717.36     13687554.33      2413045.01     13686879.06
      2413359.39     13685718.71
#Sta/Elev= 30
  3157.1  312.15  3311.5  311.43  3430.3  308.63  3452.6  309.54  3793.9  302.16
  4120.0  299.71  4257.4  296.38  4603.9  296.16  4651.3  299.48  4660.9  298.85
  4671.5  292.77  4692.3  287.55  4721.2  286.52  4795.9  287.41  4961.6  280.58
  5009.1  281.60  5014.2  278.89  5041.2  278.68  5041.6  278.18  5046.2  278.68
  5054.9  280.97  5096.3  283.95  5231.0  285.36  5391.9  293.59  5471.6  291.90
  5546.1  295.44  5593.6  300.23  5620.6  299.93  5700.3  306.01  5848.8  313.01
#Mann=5,-1,0
  3157.1    0.07       0  4257.4   0.033       0  4721.2    0.07       0
  5041.2    0.05       0  5046.2    0.07       0
Bank Sta=5041.2,5046.2
Exp/Cntr=0.3,0.1

Type RM Length L Ch R = 1,2185,1086,1086,1086
BEGIN DESCRIPTION:
XS7496
END DESCRIPTION:
XS GIS Cut Line= 3
      2411763.07     13687628.76      2413565.78     13686673.04
      2414006.13     13685529.27
#Sta/Elev= 30
  2479.3  310.15  2877.1  307.04  3217.2  300.38  3349.7  296.42  3432.0  296.43
  3437.6  298.63  3443.6  296.37  3459.9  296.37  3954.1  296.23  3982.7  299.48
  4014.5  295.16  4066.1  294.00  4206.7  291.99  4459.3  291.51  4617.2  289.05
  4871.2  279.86  5004.9  278.76  5010.5  276.15  5018.7  275.21  5019.1  274.71
  5023.7  275.21  5029.5  277.63  5053.4  277.89  5198.7  287.27  5214.1  287.05
  5253.3  290.70  5258.7  289.74  5374.8  291.78  5428.4  297.53  5745.3  305.25
#Mann=5,-1,0
  2479.3    0.07       0  3459.9   0.033       0  3982.7    0.07       0
  5018.7    0.05       0  5023.7    0.07       0
Bank Sta=5018.7,5023.7
Exp/Cntr=0.3,0.1

Type RM Length L Ch R = 1,1099,0,0,0
BEGIN DESCRIPTION:
E21282
END DESCRIPTION:
XS GIS Cut Line= 4
      2413561.83     13686729.87      2414159.14     13686565.47
      2414389.30     13686302.43      2414318.07     13685359.96
#Sta/Elev= 30
  3906.6  292.71  4093.0  293.89  4314.4  293.83  4459.6  290.29  4490.7  288.14
  4501.1  289.02  4601.6  286.55  4814.0  279.66  4849.3  279.18  4933.2  274.88
  4973.3  276.52  4993.4  274.44  4996.2  271.28  4996.6  270.78  5001.3  271.28
  5013.5  274.59  5023.5  275.41  5053.6  275.84  5081.5  277.72  5113.7  279.42
  5123.8  279.05  5143.8  281.00  5194.0  282.92  5344.4  287.59  5390.7  288.16
  5550.2  293.81  5615.2  295.79  5655.3  296.12  5675.3  297.23  5820.8  298.63
#Mann=7,-1,0
  3906.6    0.07       0  4814.0    0.12       0  4996.2    0.05       0
  5001.3    0.12       0  5081.5    0.07       0  5390.7    0.12       0
  5550.2    0.07       0
Bank Sta=4996.2,5001.3
Exp/Cntr=0.3,0.1

Chan Stop Cuts=-1