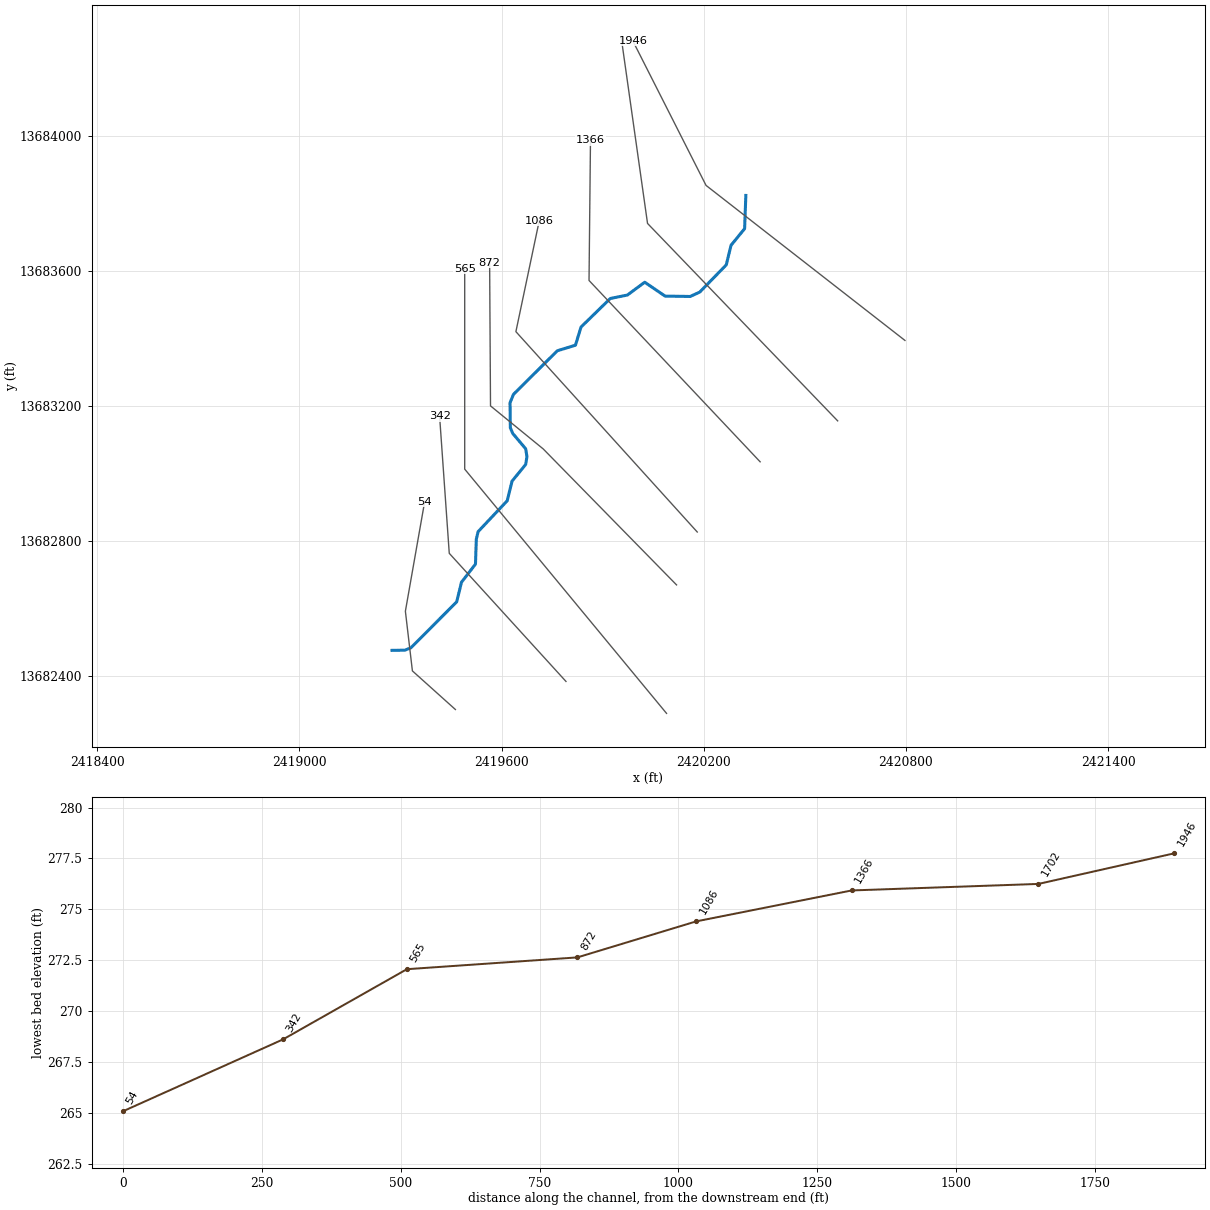
--- Stream0703.prj (project) ---

Proj Title=Stream0703 Base Level Engineering
Current Plan=p01
Default Exp/Contr=0.3,0.1
English Units
Geom File=g01
Flow File=f01
Plan File=p01
BEGIN DESCRIPTION:
Stream0703
END DESCRIPTION:

--- Stream0703.p01 (plan) ---

Plan Title=Multiple Run
Short Identifier=Multiple
Geom File=g01
Flow File=f01
Subcritical Flow
K Sum by GR= 0
Std Step Tol= 0.01
Critical Tol= 0.01
Num of Std Step Trials= 20
Max Error Tol= 0.3
Flow Tol Ratio= 0.001
Split Flow NTrial= 30
Split Flow Tol= 0.02
Split Flow Ratio= 0.02
Log Output Level= 0
Friction Slope Method= 1
Unsteady Friction Slope Method= 2
Unsteady Bridges Friction Slope Method= 1
Parabolic Critical Depth
Global Vel Dist=  1 , 1 , 1
Global Log Level= 0
CheckData=True
Encroach Param= -1, 0, 0, 0
BEGIN DESCRIPTION:
Multiple Run
END DESCRIPTION:

--- Stream0703.f01 (steady flow) ---

Flow Title=Multiple
Number of Profiles=7
Profile Names=10-year,25-year,50-year,1pct_min,100-year,1pct_plu,500-year
River Rch & RM= Stream0703,Reach-1,1946
     287     439     569     358     715    1427    1115
Boundary for River Rch & Prof#=Stream0703,Reach-1,1
Up Type=0
Dn Type=3
Dn Slope=0.005
Boundary for River Rch & Prof#=Stream0703,Reach-1,2
Up Type=0
Dn Type=3
Dn Slope=0.005
Boundary for River Rch & Prof#=Stream0703,Reach-1,3
Up Type=0
Dn Type=3
Dn Slope=0.005
Boundary for River Rch & Prof#=Stream0703,Reach-1,4
Up Type=0
Dn Type=3
Dn Slope=0.005
Boundary for River Rch & Prof#=Stream0703,Reach-1,5
Up Type=0
Dn Type=3
Dn Slope=0.005
Boundary for River Rch & Prof#=Stream0703,Reach-1,6
Up Type=0
Dn Type=3
Dn Slope=0.005
Boundary for River Rch & Prof#=Stream0703,Reach-1,7
Up Type=0
Dn Type=3
Dn Slope=0.005

--- Stream0703.g01 (geometry) ---

Geom Title=Existing Conditions

River Reach=Stream0703,Reach-1
Reach XY= 30
      2420325.00     13683825.00      2420321.37     13683726.50
      2420281.11     13683677.18      2420266.87     13683618.92
      2420188.33     13683538.33      2420159.79     13683525.25
      2420085.49     13683526.26      2420024.99     13683567.47
      2419973.35     13683529.45      2419922.70     13683519.20
      2419835.88     13683434.44      2419819.38     13683380.62
      2419765.58     13683364.11      2419635.43     13683234.79
      2419625.24     13683209.78      2419626.12     13683135.55
      2419633.14     13683118.95      2419671.63     13683073.26
      2419675.41     13683050.00      2419671.66     13683026.72
      2419631.18     13682977.19      2419616.84     13682918.95
      2419530.54     13682827.42      2419525.13     13682804.95
      2419522.67     13682730.97      2419481.14     13682677.17
      2419466.86     13682618.94      2419331.21     13682482.76
      2419313.16     13682475.59      2419275.00     13682475.00

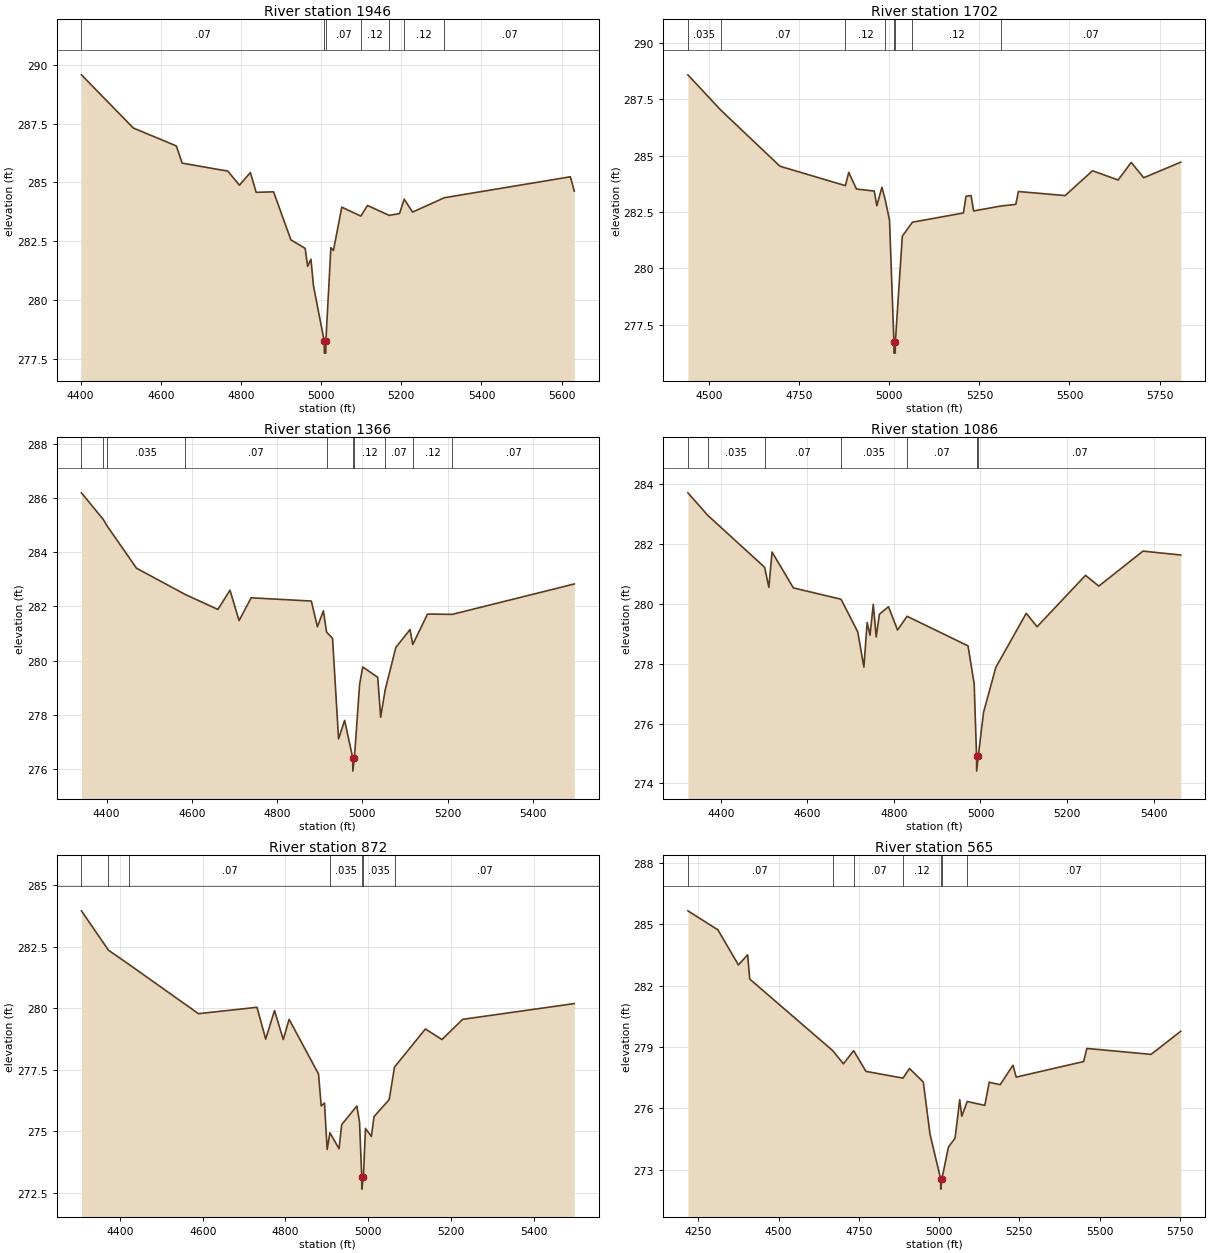
Type RM Length L Ch R = 1,1946,244,244,244
BEGIN DESCRIPTION:
XS7508
END DESCRIPTION:
XS GIS Cut Line= 3
      2420797.14     13683394.79      2420206.86     13683854.86
      2419989.60     13684283.78
#Sta/Elev= 30
  4402.3  289.57  4531.8  287.31  4639.0  286.55  4653.5  285.82  4767.5  285.48
  4796.4  284.88  4823.6  285.42  4838.1  284.58  4881.5  284.60  4924.8  282.56
  4960.2  282.20  4966.5  281.44  4974.7  281.74  4981.0  280.61  5007.9  278.25
  5008.2  277.75  5011.7  277.75  5011.9  278.25  5024.4  282.23  5030.8  282.11
  5051.6  283.95  5099.0  283.57  5115.8  284.02  5169.9  283.60  5195.7  283.68
  5207.3  284.29  5228.0  283.74  5307.4  284.35  5621.7  285.24  5631.5  284.63
#Mann=7,-1,0
  4402.3    0.07       0  5007.9    0.05       0  5011.9    0.07       0
  5099.0    0.12       0  5169.9    0.07       0  5207.3    0.12       0
  5307.4    0.07       0
Bank Sta=5007.9,5011.9
Exp/Cntr=0.3,0.1

Type RM Length L Ch R = 1,1702,336,336,336
BEGIN DESCRIPTION:
XS7507
END DESCRIPTION:
XS GIS Cut Line= 3
      2420597.51     13683156.05      2420033.25     13683742.01
      2419955.48     13684291.26
#Sta/Elev= 30
  4440.8  288.58  4531.9  287.02  4696.4  284.53  4878.0  283.67  4887.3  284.26
  4908.7  283.52  4958.1  283.43  4965.3  282.78  4979.4  283.60  4989.1  283.01
  5000.5  282.14  5012.7  276.75  5012.9  276.25  5016.4  276.25  5016.7  276.75
  5036.0  281.43  5064.0  282.05  5205.6  282.46  5212.8  283.20  5226.9  283.23
  5233.9  282.55  5310.7  282.77  5351.0  282.84  5358.3  283.41  5488.0  283.23
  5564.0  284.33  5635.1  283.92  5671.4  284.70  5706.1  284.02  5809.0  284.71
#Mann=8,-1,0
  4440.8   0.035       0  4531.9    0.07       0  4878.0    0.12       0
  4989.1    0.07       0  5012.7    0.05       0  5016.7    0.07       0
  5064.0    0.12       0  5310.7    0.07       0
Bank Sta=5012.7,5016.7
Exp/Cntr=0.3,0.1

Type RM Length L Ch R = 1,1366,280,280,280
BEGIN DESCRIPTION:
XS7506
END DESCRIPTION:
XS GIS Cut Line= 3
      2420367.42     13683034.58      2419859.64     13683572.74
      2419863.98     13683989.41
#Sta/Elev= 30
  4340.8  286.19  4392.0  285.21  4400.6  284.98  4470.1  283.41  4584.8  282.44
  4661.0  281.89  4689.4  282.60  4710.8  281.48  4739.1  282.32  4880.3  282.20
  4894.5  281.25  4908.6  281.84  4916.0  281.06  4930.1  280.82  4944.2  277.12
  4958.4  277.80  4977.4  276.43  4977.7  275.93  4981.4  276.43  4993.6  279.13
  5000.9  279.77  5036.1  279.39  5043.0  277.92  5053.5  278.92  5078.6  280.49
  5111.9  281.15  5118.3  280.60  5153.0  281.72  5211.2  281.71  5497.4  282.83
#Mann=10,-1,0
  4340.8   0.035       0  4392.0    0.07       0  4400.6   0.035       0
  4584.8    0.07       0  4916.0    0.12       0  4977.4    0.05       0
  4981.4    0.12       0  5053.5    0.07       0  5118.3    0.12       0
  5211.2    0.07       0
Bank Sta=4977.4,4981.4
Exp/Cntr=0.3,0.1

Type RM Length L Ch R = 1,1086,214,214,214
BEGIN DESCRIPTION:
XS7505
END DESCRIPTION:
XS GIS Cut Line= 3
      2420180.79     13682826.25      2419642.62     13683420.83
      2419711.99     13683750.34
#Sta/Elev= 30
  4324.0  283.72  4370.4  282.96  4501.2  281.23  4511.1  280.56  4518.4  281.74
  4567.7  280.54  4677.8  280.16  4716.4  279.07  4730.6  277.89  4738.1  279.38
  4744.8  278.96  4752.3  279.99  4759.0  278.90  4766.5  279.66  4787.4  279.91
  4808.3  279.13  4830.4  279.59  4971.2  278.60  4985.4  277.33  4990.9  274.91
  4991.1  274.41  4994.9  274.91  5007.1  276.38  5035.4  277.88  5105.7  279.69
  5130.7  279.24  5242.6  280.96  5273.3  280.60  5375.5  281.77  5462.7  281.64
#Mann=7,-1,0
  4324.0    0.07       0  4370.4   0.035       0  4501.2    0.07       0
  4677.8   0.035       0  4830.4    0.07       0  4990.9    0.05       0
  4994.9    0.07       0
Bank Sta=4990.9,4994.9
Exp/Cntr=0.3,0.1

Type RM Length L Ch R = 1,872,307,307,307
BEGIN DESCRIPTION:
E21285
END DESCRIPTION:
XS GIS Cut Line= 4
      2420119.38     13682669.27      2419723.54     13683072.93
      2419567.29     13683200.53      2419564.68     13683625.03
#Sta/Elev= 30
  4306.7  283.95  4372.1  282.35  4421.9  281.77  4589.7  279.77  4731.1  280.03
  4752.2  278.74  4773.5  279.90  4794.7  278.72  4808.8  279.54  4879.9  277.32
  4886.4  276.02  4894.3  276.14  4900.8  274.25  4907.5  274.93  4929.5  274.28
  4935.9  275.26  4972.6  276.02  4979.0  275.37  4984.4  273.14  4984.6  272.64
  4988.4  273.14  4993.4  275.11  5007.7  274.78  5014.2  275.59  5050.8  276.28
  5063.6  277.60  5138.3  279.15  5178.3  278.72  5228.3  279.54  5498.3  280.18
#Mann=7,-1,0
  4306.7    0.05       0  4372.1   0.035       0  4421.9    0.07       0
  4907.5   0.035       0  4984.4   0.035       0  4988.4   0.035       0
  5063.6    0.07       0
Bank Sta=4984.4,4988.4
Exp/Cntr=0.3,0.1

Type RM Length L Ch R = 1,565,223,223,223
BEGIN DESCRIPTION:
XS7504
END DESCRIPTION:
XS GIS Cut Line= 3
      2420089.65     13682288.05      2419490.71     13683012.85
      2419490.71     13683607.50
#Sta/Elev= 30
  4217.8  285.65  4311.3  284.72  4375.1  283.01  4403.8  283.50  4410.3  282.32
  4668.3  278.83  4702.1  278.18  4734.0  278.82  4772.4  277.81  4887.6  277.48
  4907.9  277.95  4950.9  277.29  4971.8  274.74  5004.9  272.56  5005.2  272.06
  5008.9  272.56  5029.1  274.11  5049.9  274.55  5064.3  276.43  5070.7  275.62
  5087.7  276.34  5142.4  276.15  5156.2  277.28  5190.2  277.16  5230.2  278.11
  5240.2  277.53  5450.2  278.29  5460.2  278.93  5660.2  278.64  5752.7  279.77
#Mann=7,-1,0
  4217.8    0.07       0  4668.3    0.12       0  4734.0    0.07       0
  4887.6    0.12       0  5004.9    0.05       0  5008.9    0.12       0
  5087.7    0.07       0
Bank Sta=5004.9,5008.9
Exp/Cntr=0.3,0.1

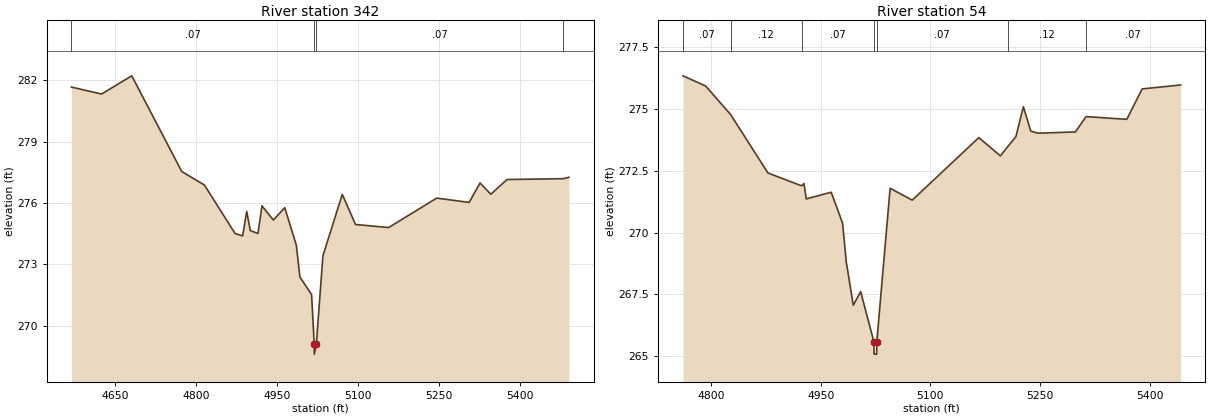
Type RM Length L Ch R = 1,342,288,288,288
BEGIN DESCRIPTION:
E21284
END DESCRIPTION:
XS GIS Cut Line= 3
      2419791.23     13682382.83      2419444.89     13682763.03
      2419416.24     13683169.32
#Sta/Elev= 30
  4569.4  281.67  4625.2  281.33  4681.2  282.22  4773.8  277.54  4815.8  276.88
  4872.5  274.51  4886.6  274.39  4894.1  275.59  4900.8  274.65  4915.0  274.51
  4922.4  275.86  4943.4  275.17  4964.6  275.77  4986.0  273.94  4992.7  272.38
  5014.3  271.52  5019.1  269.11  5019.4  268.61  5023.1  269.11  5035.3  273.42
  5071.1  276.42  5095.7  274.95  5157.0  274.80  5246.1  276.24  5306.2  276.03
  5326.3  276.98  5346.3  276.43  5376.4  277.15  5480.5  277.19  5491.0  277.26
#Mann=4,-1,0
  4569.4    0.07       0  5019.1    0.05       0  5023.1    0.07       0
  5480.5    0.12       0
Bank Sta=5019.1,5023.1
Exp/Cntr=0.3,0.1

Type RM Length L Ch R = 1,54,0,0,0
BEGIN DESCRIPTION:
E21283
END DESCRIPTION:
XS GIS Cut Line= 4
      2419463.11     13682299.50      2419335.51     13682414.07
      2419314.68     13682591.16      2419371.97     13682916.67
#Sta/Elev= 30
  4761.7  276.34  4792.6  275.93  4826.9  274.77  4877.8  272.41  4923.8  271.89
  4927.1  271.98  4930.2  271.36  4964.3  271.63  4979.9  270.38  4984.9  268.82
  4994.5  267.06  5004.6  267.61  5022.7  265.58  5023.0  265.08  5026.5  265.08
  5026.7  265.58  5044.9  271.79  5075.1  271.31  5166.2  273.84  5195.7  273.10
  5205.6  273.47  5216.9  273.88  5227.1  275.09  5237.2  274.10  5247.4  274.02
  5298.2  274.07  5312.8  274.69  5368.5  274.58  5389.5  275.81  5442.0  275.97
#Mann=7,-1,0
  4761.7    0.07       0  4826.9    0.12       0  4923.8    0.07       0
  5022.7    0.05       0  5026.7    0.07       0  5205.6    0.12       0
  5312.8    0.07       0
Bank Sta=5022.7,5026.7
Exp/Cntr=0.3,0.1

Chan Stop Cuts=-1