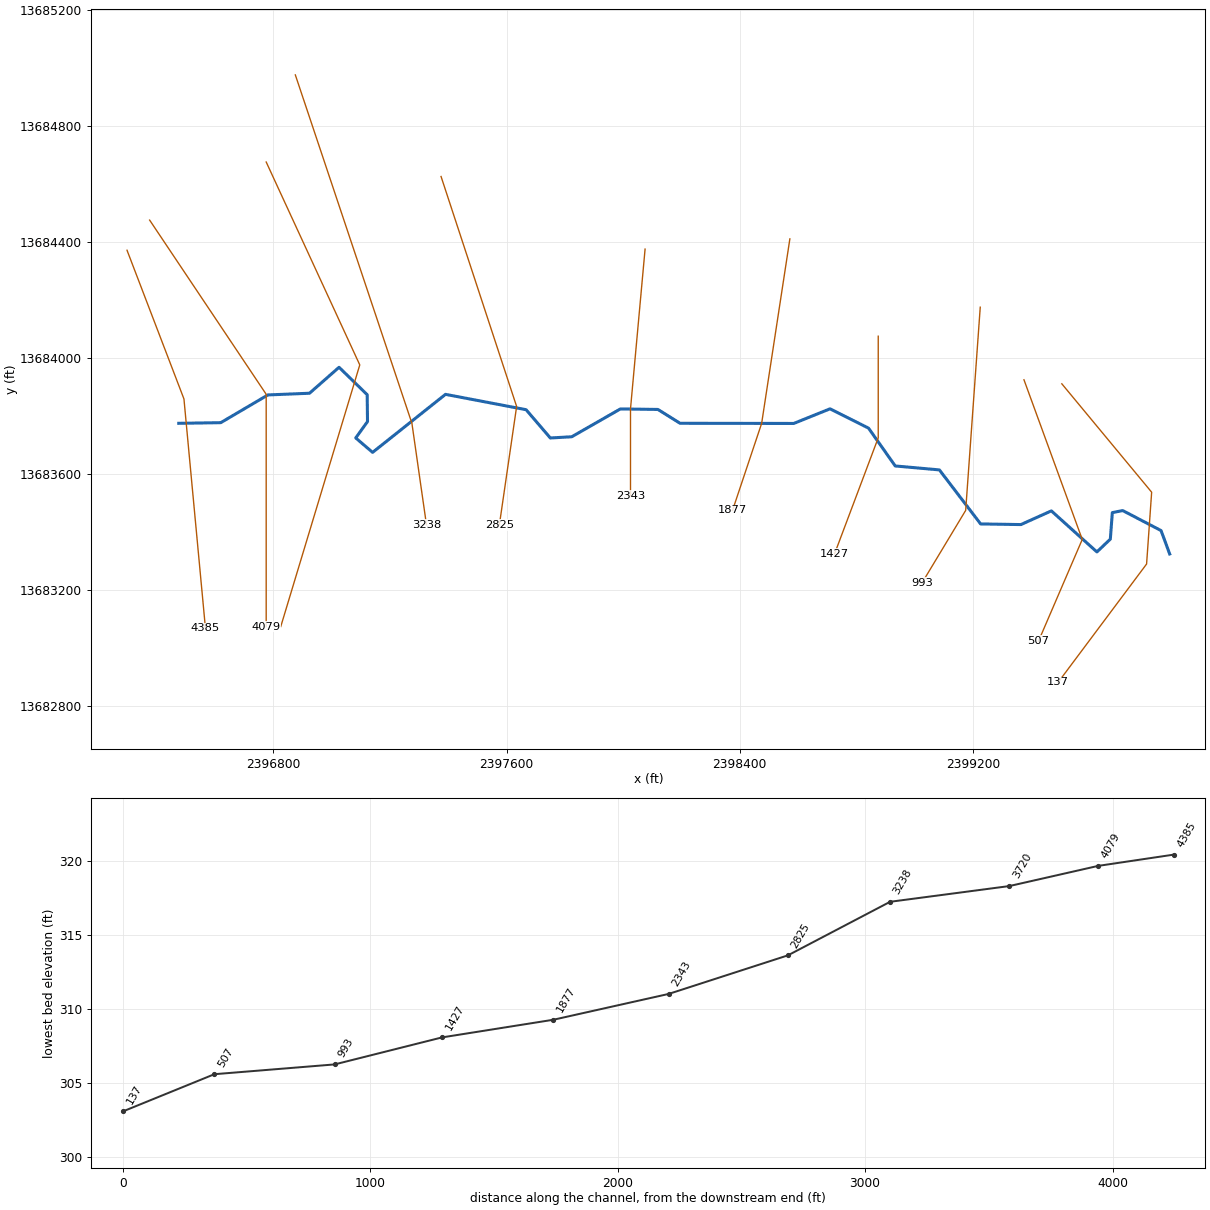
--- Stream0705.prj (project) ---

Proj Title=Stream0705 Base Level Engineering
Current Plan=p01
Default Exp/Contr=0.3,0.1
English Units
Geom File=g01
Flow File=f01
Plan File=p01
BEGIN DESCRIPTION:
Stream0705
END DESCRIPTION:

--- Stream0705.p01 (plan) ---

Plan Title=Multiple Run
Short Identifier=Multiple
Geom File=g01
Flow File=f01
Subcritical Flow
K Sum by GR= 0
Std Step Tol= 0.01
Critical Tol= 0.01
Num of Std Step Trials= 20
Max Error Tol= 0.3
Flow Tol Ratio= 0.001
Split Flow NTrial= 30
Split Flow Tol= 0.02
Split Flow Ratio= 0.02
Log Output Level= 0
Friction Slope Method= 1
Unsteady Friction Slope Method= 2
Unsteady Bridges Friction Slope Method= 1
Parabolic Critical Depth
Global Vel Dist=  1 , 1 , 1
Global Log Level= 0
CheckData=True
Encroach Param= -1, 0, 0, 0
BEGIN DESCRIPTION:
Multiple Run
END DESCRIPTION:

--- Stream0705.f01 (steady flow) ---

Flow Title=Multiple
Number of Profiles=7
Profile Names=10-year,25-year,50-year,1pct_min,100-year,1pct_plu,500-year
River Rch & RM= Stream0705,Reach-1,4385
     708    1148    1546    1008    2010    4011    3369
Boundary for River Rch & Prof#=Stream0705,Reach-1,1
Up Type=0
Dn Type=3
Dn Slope=0.005
Boundary for River Rch & Prof#=Stream0705,Reach-1,2
Up Type=0
Dn Type=3
Dn Slope=0.005
Boundary for River Rch & Prof#=Stream0705,Reach-1,3
Up Type=0
Dn Type=3
Dn Slope=0.005
Boundary for River Rch & Prof#=Stream0705,Reach-1,4
Up Type=0
Dn Type=3
Dn Slope=0.005
Boundary for River Rch & Prof#=Stream0705,Reach-1,5
Up Type=0
Dn Type=3
Dn Slope=0.005
Boundary for River Rch & Prof#=Stream0705,Reach-1,6
Up Type=0
Dn Type=3
Dn Slope=0.005
Boundary for River Rch & Prof#=Stream0705,Reach-1,7
Up Type=0
Dn Type=3
Dn Slope=0.005

--- Stream0705.g01 (geometry) ---

Geom Title=Existing Conditions

River Reach=Stream0705,Reach-1
Reach XY= 30
      2396475.00     13683775.00      2396619.09     13683777.20
      2396780.93     13683872.75      2396923.53     13683878.57
      2397025.02     13683967.92      2397121.54     13683873.53
      2397122.63     13683780.88      2397082.23     13683724.62
      2397140.08     13683674.89      2397390.22     13683874.76
      2397666.68     13683821.89      2397749.88     13683724.48
      2397823.41     13683728.67      2397990.22     13683824.51
      2398119.06     13683822.75      2398195.03     13683775.07
      2398585.19     13683774.55      2398709.61     13683824.92
      2398841.71     13683758.37      2398933.31     13683628.08
      2399084.82     13683614.53      2399226.25     13683428.44
      2399364.50     13683426.23      2399468.97     13683473.38
      2399625.24     13683331.97      2399671.36     13683376.09
      2399678.16     13683467.41      2399713.81     13683474.50
      2399845.47     13683405.50      2399875.00     13683325.00

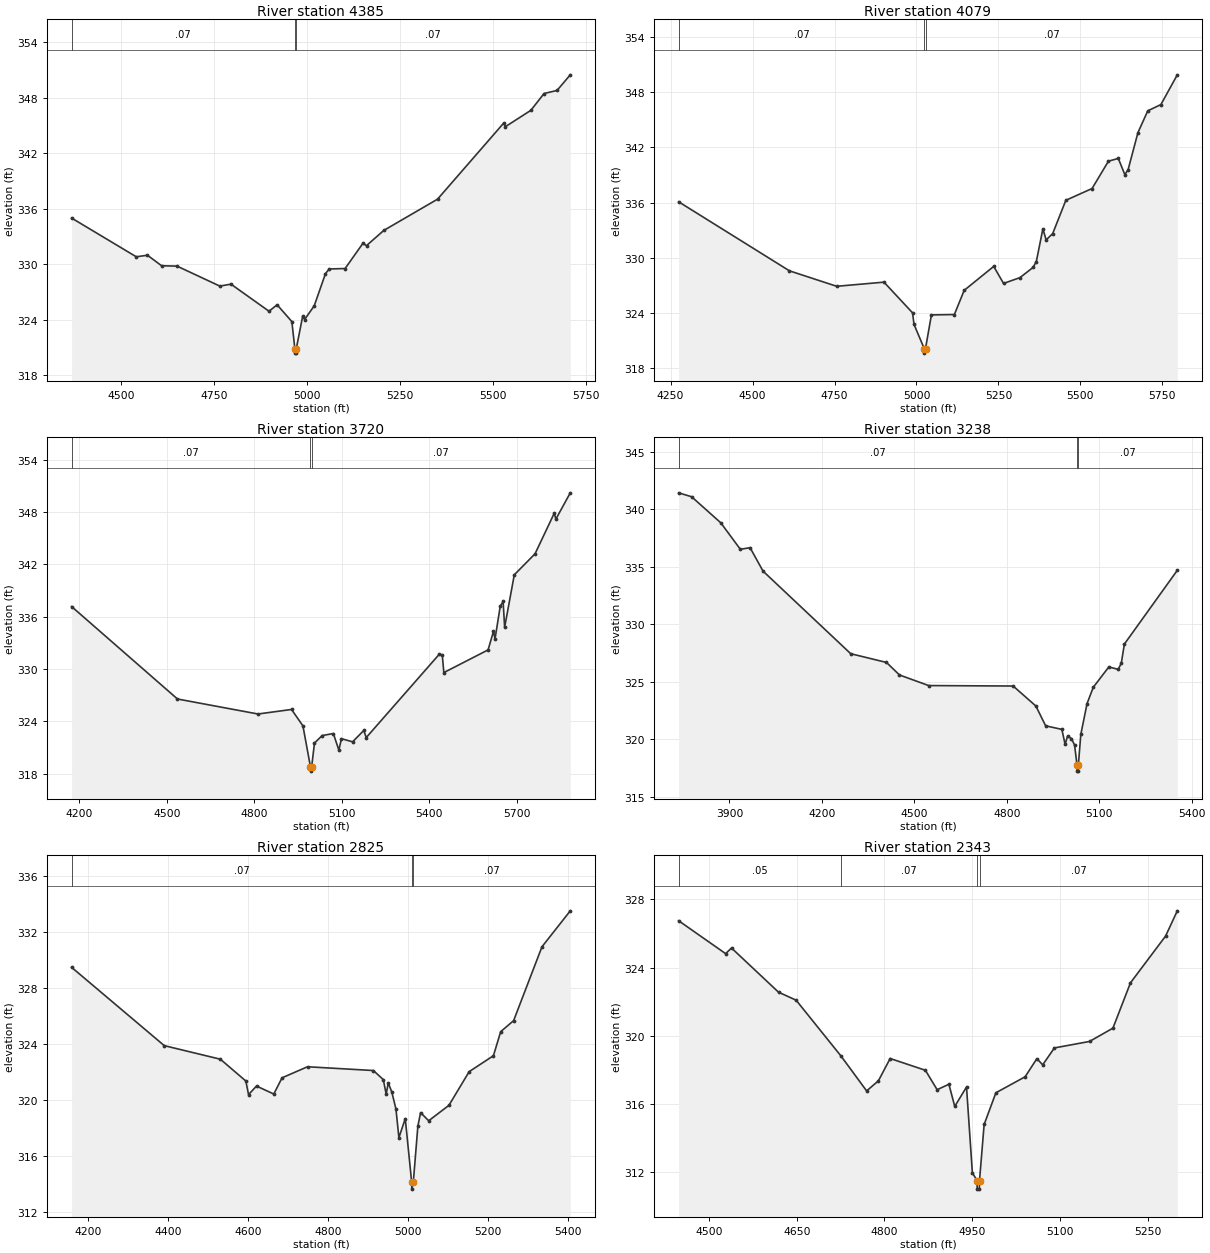
Type RM Length L Ch R = 1,4385,306,306,306
BEGIN DESCRIPTION:
XS7510
END DESCRIPTION:
XS GIS Cut Line= 3
      2396297.48     13684371.09      2396492.80     13683858.94
      2396566.53     13683069.51
#Sta/Elev= 30
  4367.5  335.01  4541.4  330.82  4571.5  330.99  4609.5  329.85  4651.1  329.81
  4766.1  327.65  4796.1  327.86  4898.4  324.93  4920.1  325.63  4959.8  323.81
  4967.8  320.90  4968.1  320.40  4971.6  320.40  4971.8  320.90  4989.0  324.42
  4994.0  324.03  5020.0  325.52  5050.2  329.00  5060.2  329.50  5103.0  329.55
  5150.6  332.26  5160.6  332.03  5207.0  333.67  5351.5  337.05  5529.0  345.26
  5534.0  344.89  5602.5  346.66  5638.0  348.48  5672.9  348.81  5708.5  350.50
#Mann=3,-1,0
  4367.5    0.07       0  4967.8    0.05       0  4971.8    0.07       0
Bank Sta=4967.8,4971.8
Exp/Cntr=0.3,0.1

Type RM Length L Ch R = 1,4079,359,359,359
BEGIN DESCRIPTION:
Stream0705 9.0
END DESCRIPTION:
XS GIS Cut Line= 3
      2396375.03     13684474.96      2396775.00     13683875.00
      2396775.00     13683074.96
#Sta/Elev= 30
  4274.4  336.08  4612.4  328.58  4756.6  326.90  4900.8  327.35  4987.9  324.02
  4992.5  322.75  5023.5  320.14  5023.7  319.64  5027.5  320.14  5045.5  323.79
  5115.5  323.83  5145.5  326.46  5235.5  329.06  5265.5  327.21  5315.5  327.84
  5355.5  328.95  5365.5  329.59  5385.5  333.14  5395.5  331.94  5415.5  332.63
  5455.5  336.24  5535.5  337.52  5585.5  340.49  5615.5  340.79  5635.5  339.03
  5645.5  339.57  5675.5  343.60  5705.5  345.96  5745.5  346.64  5795.5  349.87
#Mann=3,-1,0
  4274.4    0.07       0  5023.5    0.05       0  5027.5    0.07       0
Bank Sta=5023.5,5027.5
Exp/Cntr=0.3,0.1

Type RM Length L Ch R = 1,3720,482,482,482
BEGIN DESCRIPTION:
Stream0705 8.0
END DESCRIPTION:
XS GIS Cut Line= 3
      2396775.01     13684674.98      2397096.09     13683976.13
      2396825.00     13683075.01
#Sta/Elev= 30
  4173.6  337.15  4536.7  326.55  4812.8  324.83  4927.8  325.35  4966.9  323.47
  4992.7  318.78  4992.9  318.28  4996.8  318.78  5006.5  321.50  5032.9  322.36
  5071.2  322.59  5090.1  320.69  5099.0  322.00  5137.2  321.64  5175.5  322.94
  5184.0  322.13  5434.7  331.69  5444.8  331.60  5450.1  329.58  5601.8  332.18
  5620.4  334.31  5625.6  333.43  5643.5  337.18  5653.4  337.73  5658.6  334.77
  5691.7  340.79  5762.9  343.20  5829.0  347.87  5834.2  347.17  5883.7  350.19
#Mann=3,-1,0
  4173.6    0.07       0  4992.7    0.05       0  4996.8    0.07       0
Bank Sta=4992.7,4996.8
Exp/Cntr=0.3,0.1

Type RM Length L Ch R = 1,3238,413,413,413
BEGIN DESCRIPTION:
Stream0705 7.0
END DESCRIPTION:
XS GIS Cut Line= 3
      2396875.01     13684974.98      2397275.00     13683775.00
      2397324.99     13683425.04
#Sta/Elev= 30
  3735.1  341.42  3777.2  341.08  3872.1  338.81  3935.4  336.51  3967.0  336.65
  4009.1  334.61  4293.7  327.43  4409.7  326.67  4451.9  325.58  4546.7  324.66
  4820.8  324.62  4894.6  322.88  4926.2  321.16  4978.9  320.85  4989.4  319.55
  4997.4  320.26  5010.1  320.05  5020.2  319.48  5028.2  317.72  5028.5  317.22
  5032.1  317.22  5032.3  317.72  5040.4  320.41  5060.6  323.09  5080.8  324.51
  5131.3  326.28  5161.6  326.07  5171.7  326.59  5181.8  328.27  5353.5  334.68
#Mann=3,-1,0
  3735.1    0.07       0  5028.2    0.05       0  5032.3    0.07       0
Bank Sta=5028.2,5032.3
Exp/Cntr=0.3,0.1

Type RM Length L Ch R = 1,2825,482,482,482
BEGIN DESCRIPTION:
Stream0705 6.0
END DESCRIPTION:
XS GIS Cut Line= 3
      2397374.99     13684625.04      2397634.29     13683832.90
      2397575.00     13683424.99
#Sta/Elev= 30
  4159.1  329.47  4390.6  323.87  4530.7  322.90  4594.4  321.34  4601.1  320.37
  4621.0  320.98  4664.2  320.41  4684.8  321.57  4748.4  322.36  4913.0  322.09
  4937.8  321.44  4944.9  320.40  4950.1  321.20  4958.8  320.57  4969.3  319.35
  4976.7  317.29  4992.6  318.65  5008.6  314.11  5008.9  313.61  5012.7  314.11
  5024.1  318.12  5030.9  319.08  5051.1  318.50  5101.6  319.60  5152.2  322.01
  5212.8  323.15  5231.0  324.87  5263.3  325.66  5334.1  330.94  5404.8  333.51
#Mann=3,-1,0
  4159.1    0.07       0  5008.6    0.05       0  5012.7    0.07       0
Bank Sta=5008.6,5012.7
Exp/Cntr=0.3,0.1

Type RM Length L Ch R = 1,2343,466,466,466
BEGIN DESCRIPTION:
Stream0705 5.0
END DESCRIPTION:
XS GIS Cut Line= 3
      2398075.00     13684374.98      2398025.00     13683825.00
      2398025.00     13683525.05
#Sta/Elev= 30
  4448.2  326.75  4528.5  324.82  4538.6  325.15  4618.9  322.56  4649.0  322.09
  4725.6  318.82  4769.5  316.77  4789.6  317.36  4809.7  318.67  4869.9  317.98
  4890.0  316.84  4910.1  317.16  4920.1  315.86  4940.2  317.00  4950.2  311.97
  4958.2  311.51  4958.5  311.01  4962.1  311.01  4962.4  311.51  4970.3  314.80
  4990.4  316.66  5040.4  317.60  5060.4  318.66  5070.4  318.30  5090.4  319.29
  5150.4  319.67  5190.4  320.45  5220.4  323.11  5280.4  325.85  5300.4  327.33
#Mann=4,-1,0
  4448.2    0.05       0  4725.6    0.07       0  4958.2    0.05       0
  4962.4    0.07       0
Bank Sta=4958.2,4962.4
Exp/Cntr=0.3,0.1

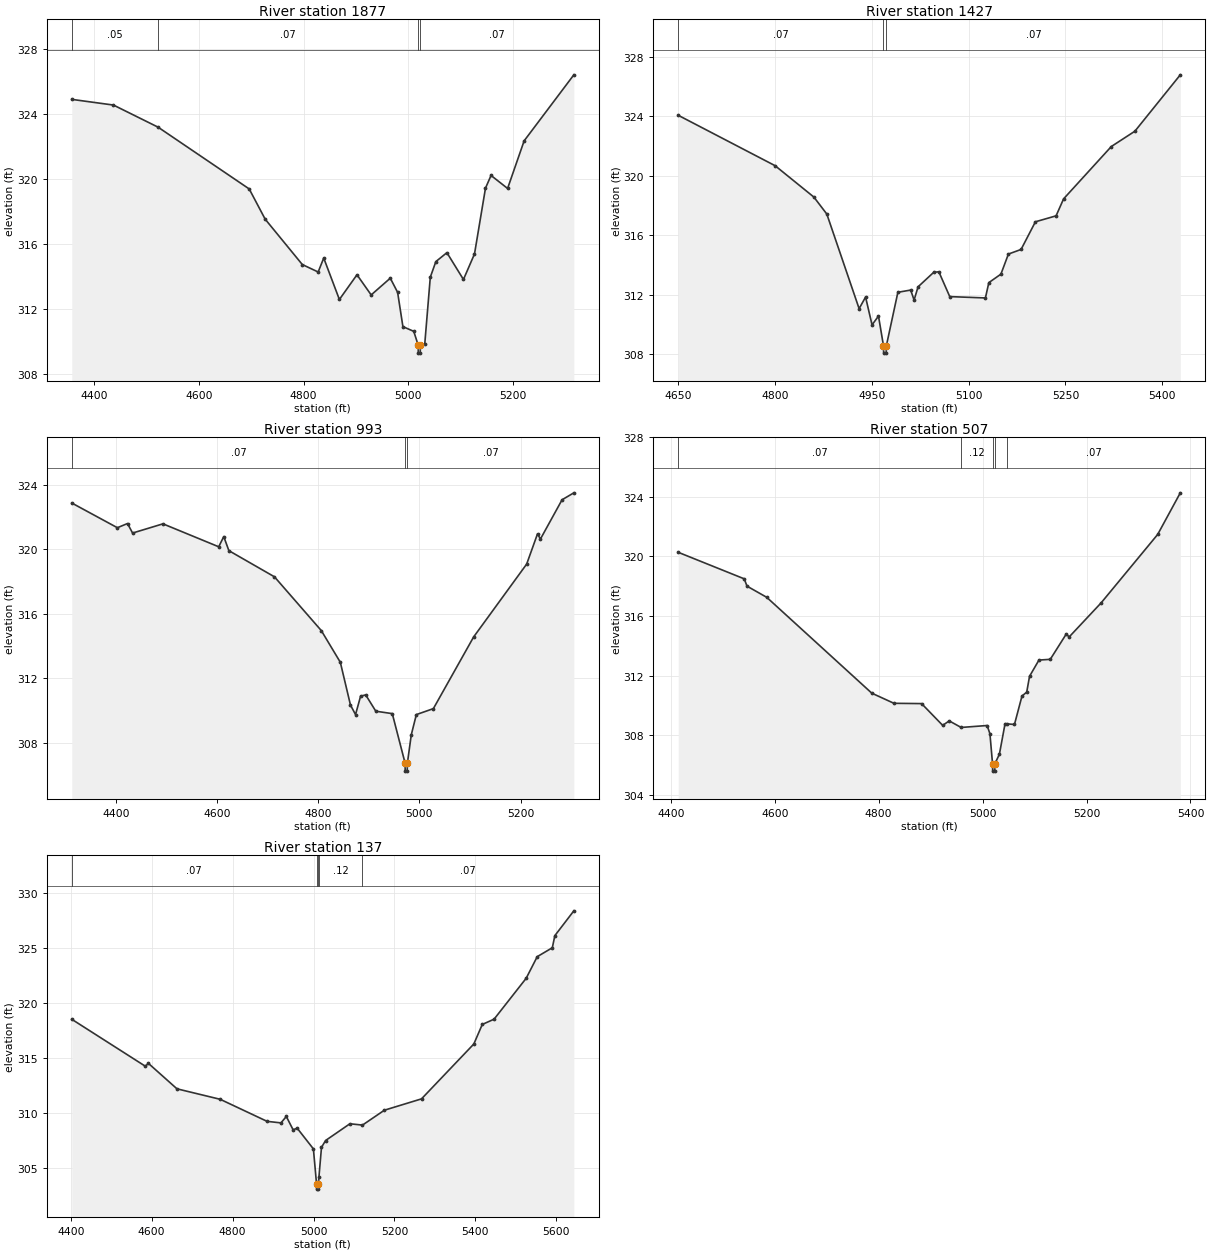
Type RM Length L Ch R = 1,1877,450,450,450
BEGIN DESCRIPTION:
Stream0705 4.0
END DESCRIPTION:
XS GIS Cut Line= 3
      2398571.78     13684410.13      2398475.00     13683775.00
      2398375.00     13683474.99
#Sta/Elev= 30
  4357.5  324.88  4437.1  324.53  4522.3  323.17  4696.3  319.37  4726.8  317.51
  4797.7  314.72  4828.0  314.26  4838.6  315.12  4868.5  312.57  4902.1  314.09
  4929.2  312.85  4965.7  313.88  4979.7  313.01  4989.8  310.90  5010.5  310.61
  5018.9  309.77  5019.2  309.27  5022.9  309.27  5023.1  309.77  5031.6  309.86
  5042.1  313.94  5052.7  314.90  5073.8  315.45  5105.4  313.80  5126.5  315.37
  5147.5  319.42  5158.1  320.20  5189.7  319.40  5221.3  322.33  5316.2  326.39
#Mann=4,-1,0
  4357.5    0.05       0  4522.3    0.07       0  5018.9    0.05       0
  5023.1    0.07       0
Bank Sta=5018.9,5023.1
Exp/Cntr=0.3,0.1

Type RM Length L Ch R = 1,1427,434,434,434
BEGIN DESCRIPTION:
Stream0705 3.0
END DESCRIPTION:
XS GIS Cut Line= 3
      2398875.00     13684074.98      2398875.00     13683725.00
      2398724.99     13683324.98
#Sta/Elev= 30
  4650.6  324.07  4800.6  320.68  4860.6  318.57  4880.6  317.43  4930.6  311.07
  4940.6  311.85  4950.6  309.98  4960.6  310.57  4968.3  308.58  4968.6  308.08
  4972.5  308.08  4972.8  308.58  4990.6  312.17  5010.4  312.32  5015.7  311.65
  5021.9  312.54  5046.0  313.51  5054.0  313.55  5070.9  311.88  5126.1  311.79
  5131.4  312.82  5150.1  313.39  5161.7  314.74  5181.3  315.05  5203.5  316.91
  5235.5  317.31  5247.1  318.45  5321.0  321.97  5357.5  323.00  5427.8  326.79
#Mann=3,-1,0
  4650.6    0.07       0  4968.3    0.05       0  4972.8    0.07       0
Bank Sta=4968.3,4972.8
Exp/Cntr=0.3,0.1

Type RM Length L Ch R = 1,993,486,486,486
BEGIN DESCRIPTION:
Stream0705 2.0
END DESCRIPTION:
XS GIS Cut Line= 3
      2399225.00     13684174.98      2399175.00     13683475.00
      2399025.01     13683225.01
#Sta/Elev= 30
  4312.2  322.86  4402.4  321.33  4422.5  321.59  4432.5  321.00  4492.6  321.57
  4602.9  320.15  4612.9  320.78  4623.0  319.91  4713.2  318.29  4805.9  314.96
  4843.5  313.00  4863.6  310.35  4873.6  309.76  4883.6  310.90  4893.7  310.98
  4913.7  309.97  4946.3  309.82  4971.6  306.76  4971.9  306.26  4975.8  306.26
  4976.2  306.76  4983.9  308.51  4993.9  309.76  5027.6  310.13  5107.3  314.57
  5212.2  319.08  5233.6  320.95  5239.4  320.63  5282.2  323.06  5305.5  323.49
#Mann=3,-1,0
  4312.2    0.07       0  4971.6    0.05       0  4976.2    0.07       0
Bank Sta=4971.6,4976.2
Exp/Cntr=0.3,0.1

Type RM Length L Ch R = 1,507,370,370,370
BEGIN DESCRIPTION:
Stream0705 1.0
END DESCRIPTION:
XS GIS Cut Line= 3
      2399375.00     13683925.00      2399575.00     13683375.00
      2399425.01     13683025.03
#Sta/Elev= 30
  4414.4  320.28  4541.4  318.50  4546.7  318.01  4584.7  317.26  4786.8  310.83
  4829.4  310.15  4882.6  310.13  4923.2  308.67  4935.8  308.97  4958.7  308.53
  5008.7  308.66  5014.1  308.11  5019.1  306.10  5019.4  305.60  5023.4  305.60
  5023.7  306.10  5032.3  306.73  5043.2  308.78  5047.2  308.77  5061.3  308.73
  5075.8  310.64  5084.9  310.90  5090.3  311.96  5108.4  313.05  5130.2  313.10
  5161.0  314.80  5166.5  314.60  5228.1  316.89  5336.9  321.48  5380.4  324.27
#Mann=5,-1,0
  4414.4    0.07       0  4958.7    0.12       0  5019.1    0.05       0
  5023.7    0.12       0  5047.2    0.07       0
Bank Sta=5019.1,5023.7
Exp/Cntr=0.3,0.1

Type RM Length L Ch R = 1,137,0,0,0
BEGIN DESCRIPTION:
XS7509
END DESCRIPTION:
XS GIS Cut Line= 4
      2399504.94     13683911.03      2399813.11     13683537.76
      2399795.75     13683290.36      2399491.94     13682882.40
#Sta/Elev= 30
  4402.6  318.50  4584.4  314.24  4592.0  314.50  4662.6  312.19  4769.4  311.24
  4885.2  309.24  4919.5  309.10  4932.8  309.68  4949.6  308.47  4959.6  308.62
  4999.7  306.74  5007.4  303.59  5007.7  303.09  5011.7  303.09  5012.0  303.59
  5013.3  304.15  5019.7  306.88  5029.8  307.50  5089.9  309.02  5121.0  308.90
  5175.1  310.25  5266.9  311.28  5396.2  316.26  5417.0  318.03  5446.2  318.51
  5525.5  322.22  5552.8  324.18  5590.1  324.99  5596.4  326.09  5643.3  328.34
#Mann=5,-1,0
  4402.6    0.07       0  5007.4    0.05       0  5012.0    0.07       0
  5013.3    0.12       0  5121.0    0.07       0
Bank Sta=5007.4,5012
Exp/Cntr=0.3,0.1

Chan Stop Cuts=-1