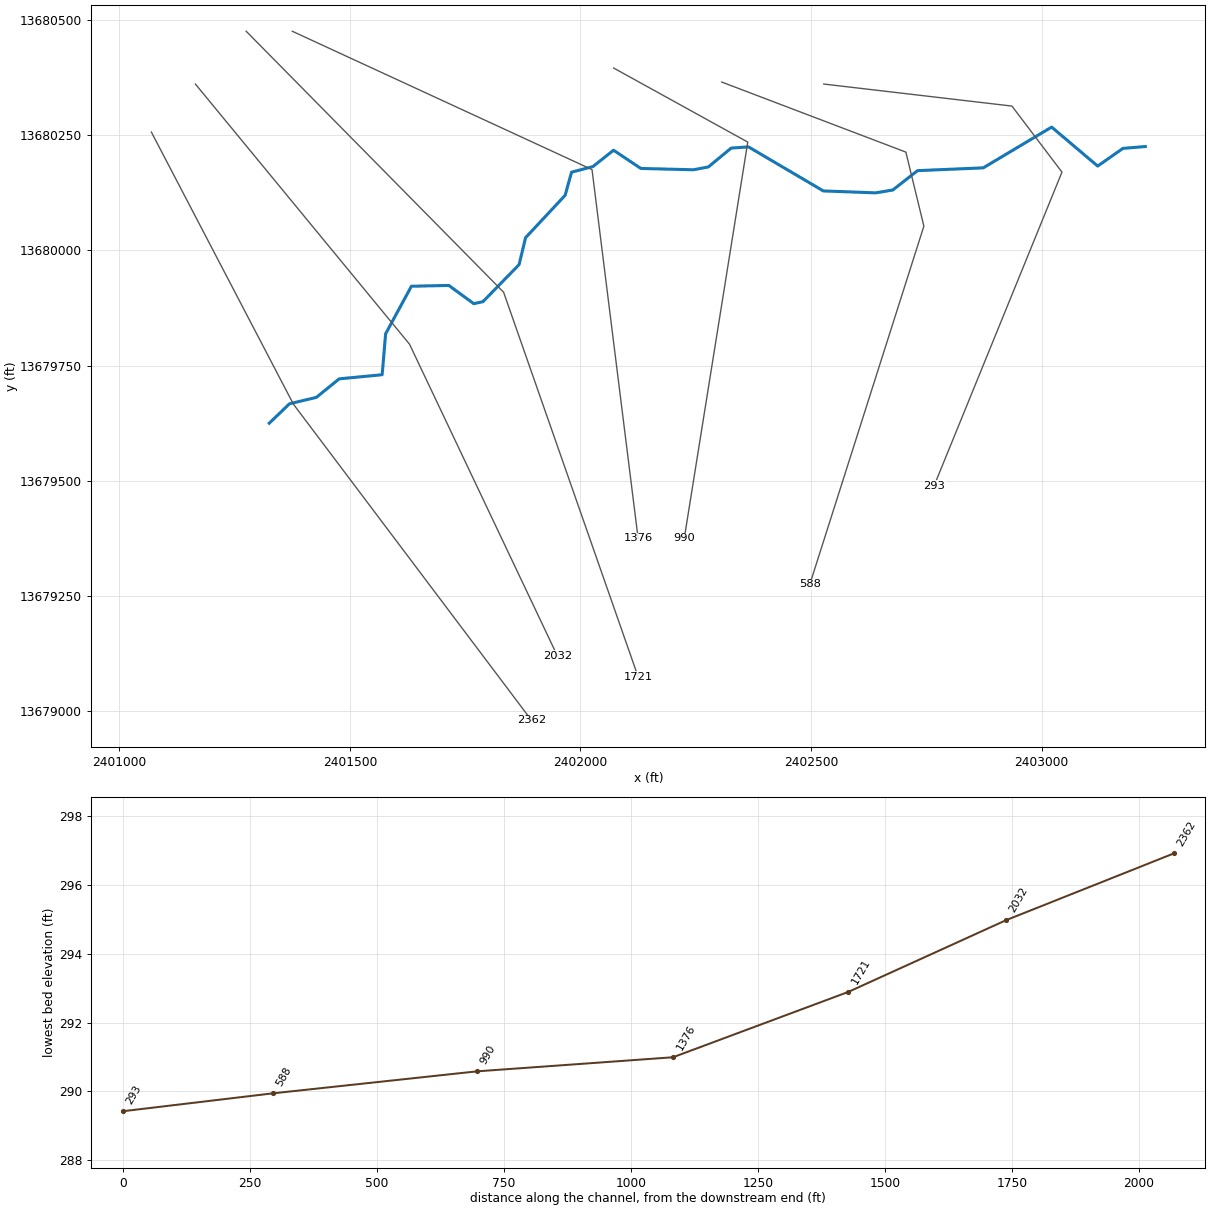
--- Stream0706.prj (project) ---

Proj Title=Stream0706 Base Level Engineering
Current Plan=p01
Default Exp/Contr=0.3,0.1
English Units
Geom File=g01
Flow File=f01
Plan File=p01
BEGIN DESCRIPTION:
Stream0706
END DESCRIPTION:

--- Stream0706.p01 (plan) ---

Plan Title=Multiple Run
Short Identifier=Multiple
Geom File=g01
Flow File=f01
Subcritical Flow
K Sum by GR= 0
Std Step Tol= 0.01
Critical Tol= 0.01
Num of Std Step Trials= 20
Max Error Tol= 0.3
Flow Tol Ratio= 0.001
Split Flow NTrial= 30
Split Flow Tol= 0.02
Split Flow Ratio= 0.02
Log Output Level= 0
Friction Slope Method= 1
Unsteady Friction Slope Method= 2
Unsteady Bridges Friction Slope Method= 1
Parabolic Critical Depth
Global Vel Dist=  1 , 1 , 1
Global Log Level= 0
CheckData=True
Encroach Param= -1, 0, 0, 0
BEGIN DESCRIPTION:
Multiple Run
END DESCRIPTION:

--- Stream0706.f01 (steady flow) ---

Flow Title=Multiple
Number of Profiles=7
Profile Names=10-year,25-year,50-year,1pct_min,100-year,1pct_plu,500-year
River Rch & RM= Stream0706,Reach-1,2362
     752    1228    1663    1090    2175    4340    3687
Boundary for River Rch & Prof#=Stream0706,Reach-1,1
Up Type=0
Dn Type=3
Dn Slope=0.005
Boundary for River Rch & Prof#=Stream0706,Reach-1,2
Up Type=0
Dn Type=3
Dn Slope=0.005
Boundary for River Rch & Prof#=Stream0706,Reach-1,3
Up Type=0
Dn Type=3
Dn Slope=0.005
Boundary for River Rch & Prof#=Stream0706,Reach-1,4
Up Type=0
Dn Type=3
Dn Slope=0.005
Boundary for River Rch & Prof#=Stream0706,Reach-1,5
Up Type=0
Dn Type=3
Dn Slope=0.005
Boundary for River Rch & Prof#=Stream0706,Reach-1,6
Up Type=0
Dn Type=3
Dn Slope=0.005
Boundary for River Rch & Prof#=Stream0706,Reach-1,7
Up Type=0
Dn Type=3
Dn Slope=0.005

--- Stream0706.g01 (geometry) ---

Geom Title=Existing Conditions

River Reach=Stream0706,Reach-1
Reach XY= 30
      2401325.00     13679625.00      2401368.85     13679667.09
      2401427.22     13679681.02      2401476.66     13679721.15
      2401569.89     13679730.11      2401577.36     13679818.96
      2401633.32     13679922.03      2401714.41     13679923.77
      2401768.47     13679884.29      2401788.41     13679888.52
      2401866.84     13679968.91      2401880.87     13680027.28
      2401966.70     13680119.26      2401980.62     13680169.44
      2402026.95     13680181.55      2402071.65     13680216.97
      2402130.86     13680177.45      2402245.14     13680174.62
      2402277.35     13680180.78      2402326.74     13680221.63
      2402364.32     13680224.25      2402526.56     13680128.74
      2402640.16     13680124.53      2402677.33     13680130.74
      2402730.94     13680172.73      2402873.44     13680178.76
      2403021.77     13680267.15      2403121.61     13680182.62
      2403176.36     13680220.98      2403225.00     13680225.00

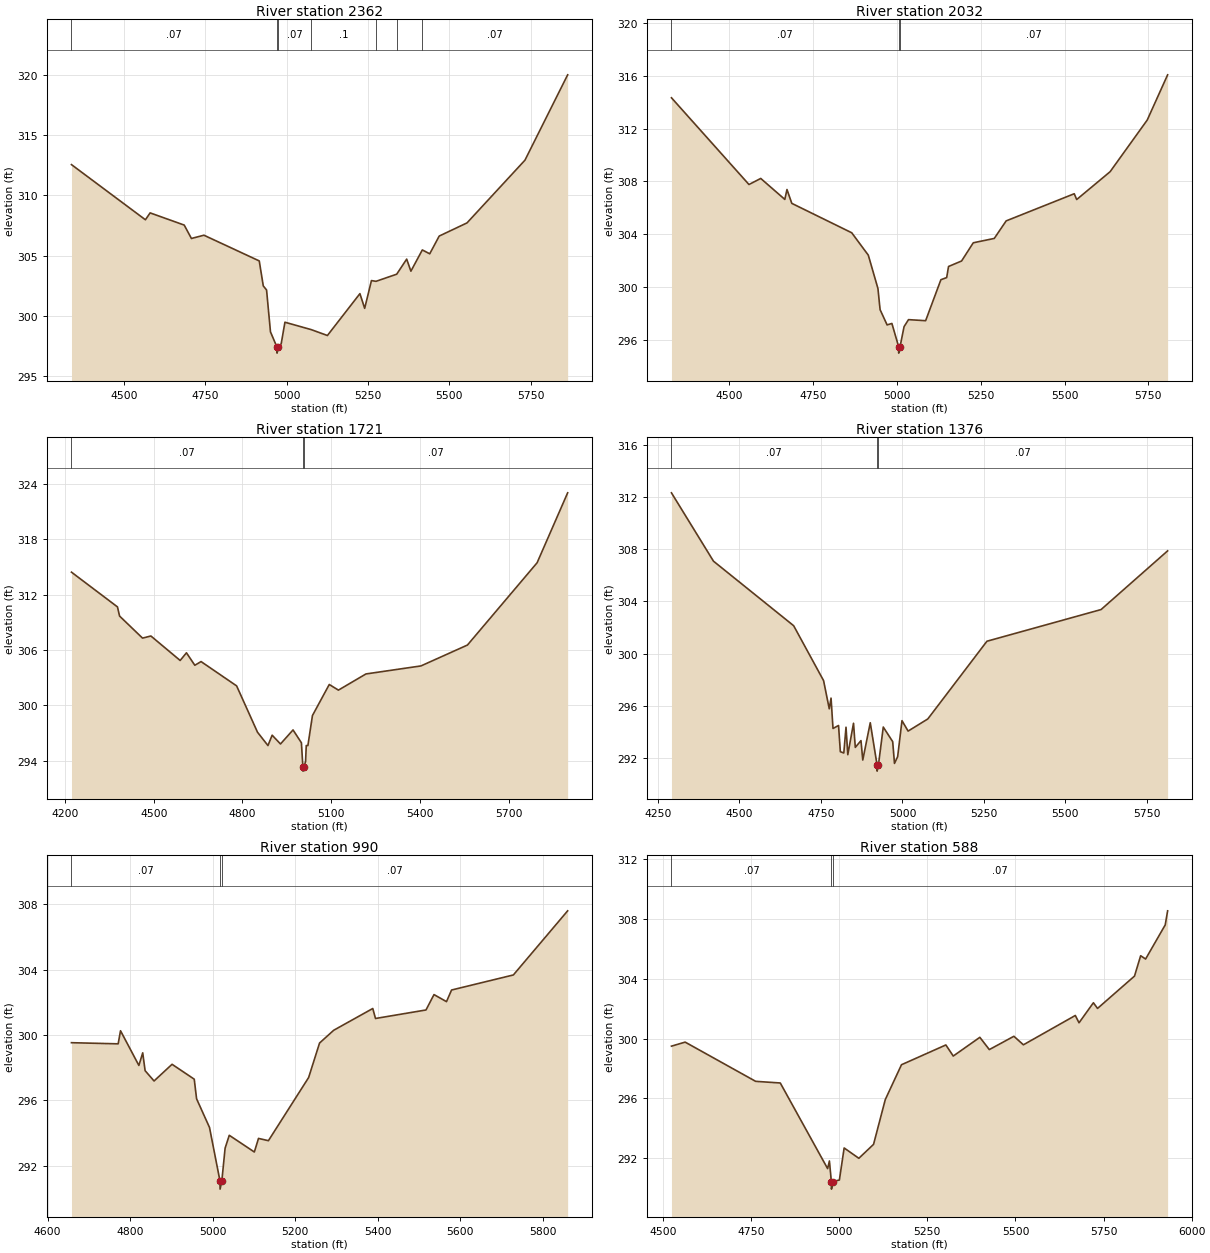
Type RM Length L Ch R = 1,2362,330,330,330
BEGIN DESCRIPTION:
Stream0706 4.0
END DESCRIPTION:
XS GIS Cut Line= 3
      2401069.34     13680256.36      2401377.52     13679666.06
      2401894.00     13678980.31
#Sta/Elev= 30
  4339.1  312.54  4566.3  307.97  4580.7  308.54  4685.5  307.53  4707.6  306.42
  4746.1  306.69  4916.0  304.56  4928.4  302.49  4938.5  302.15  4950.5  298.68
  4970.4  297.42  4970.7  296.92  4974.8  297.42  4983.4  297.69  4994.9  299.48
  5075.4  298.87  5125.4  298.38  5225.3  301.85  5239.9  300.63  5260.7  302.93
  5274.7  302.87  5338.3  303.46  5369.0  304.71  5381.9  303.71  5417.0  305.47
  5439.8  305.15  5468.9  306.62  5554.3  307.71  5732.4  312.91  5863.5  319.98
#Mann=7,-1,0
  4339.1    0.07       0  4970.4    0.05       0  4974.8    0.07       0
  5075.4     0.1       0  5274.7    0.07       0  5338.3     0.1       0
  5417.0    0.07       0
Bank Sta=4970.4,4974.8
Exp/Cntr=0.3,0.1

Type RM Length L Ch R = 1,2032,311,311,311
BEGIN DESCRIPTION:
XS7511
END DESCRIPTION:
XS GIS Cut Line= 3
      2401164.86     13680360.48      2401629.25     13679796.27
      2401950.03     13679120.04
#Sta/Elev= 30
  4328.1  314.35  4559.2  307.77  4594.3  308.23  4666.1  306.64  4672.5  307.39
  4686.9  306.34  4865.5  304.11  4915.0  302.41  4943.7  299.88  4950.1  298.28
  4971.0  297.12  4985.3  297.23  5005.3  295.48  5005.6  294.98  5009.7  295.48
  5021.6  296.99  5034.8  297.52  5085.9  297.44  5131.4  300.55  5148.6  300.71
  5154.1  301.55  5193.1  301.97  5227.9  303.35  5290.5  303.68  5325.9  305.01
  5528.9  307.07  5536.2  306.63  5635.8  308.74  5746.5  312.66  5807.3  316.09
#Mann=3,-1,0
  4328.1    0.07       0  5005.3    0.05       0  5009.7    0.07       0
Bank Sta=5005.3,5009.7
Exp/Cntr=0.3,0.1

Type RM Length L Ch R = 1,1721,345,345,345
BEGIN DESCRIPTION:
Stream0706 3.0
END DESCRIPTION:
XS GIS Cut Line= 3
      2401274.97     13680475.03      2401833.25     13679909.11
      2402125.00     13679075.00
#Sta/Elev= 30
  4221.5  314.43  4377.1  310.67  4384.2  309.68  4461.9  307.29  4490.2  307.52
  4589.2  304.87  4610.5  305.70  4638.8  304.35  4659.9  304.75  4780.2  302.12
  4850.9  297.10  4886.2  295.66  4900.4  296.78  4928.6  295.83  4971.1  297.35
  4999.4  295.96  5004.3  293.39  5004.6  292.89  5008.7  293.39  5013.5  293.95
  5015.8  295.66  5021.3  295.66  5036.8  298.91  5093.6  302.27  5124.6  301.66
  5217.7  303.41  5403.9  304.28  5561.1  306.54  5796.8  315.45  5900.1  323.02
#Mann=3,-1,0
  4221.5    0.07       0  5004.3    0.05       0  5008.7    0.07       0
Bank Sta=5004.3,5008.7
Exp/Cntr=0.3,0.1

Type RM Length L Ch R = 1,1376,386,386,386
BEGIN DESCRIPTION:
Stream0706 2.0
END DESCRIPTION:
XS GIS Cut Line= 3
      2401375.00     13680475.00      2402025.00     13680175.00
      2402125.00     13679375.01
#Sta/Elev= 30
  4291.4  312.33  4420.3  307.09  4666.3  302.14  4758.1  297.93  4775.5  295.77
  4781.0  296.59  4787.0  294.26  4804.0  294.49  4809.5  292.48  4820.1  292.38
  4826.9  294.36  4832.4  292.25  4849.9  294.66  4855.4  292.81  4872.8  293.33
  4878.3  291.84  4901.3  294.70  4922.0  291.49  4922.3  290.99  4926.5  291.49
  4941.2  294.37  4970.1  293.25  4975.6  291.58  4985.3  292.10  4998.6  294.86
  5017.4  294.06  5077.8  294.99  5259.2  300.95  5609.4  303.38  5813.5  307.88
#Mann=3,-1,0
  4291.4    0.07       0  4922.0    0.05       0  4926.5    0.07       0
Bank Sta=4922,4926.5
Exp/Cntr=0.3,0.1

Type RM Length L Ch R = 1,990,402,402,402
BEGIN DESCRIPTION:
Stream0706 1.0
END DESCRIPTION:
XS GIS Cut Line= 3
      2402071.92     13680395.25      2402362.76     13680234.64
      2402225.01     13679375.04
#Sta/Elev= 30
  4657.7  299.53  4770.9  299.46  4776.6  300.26  4821.1  298.14  4830.4  298.91
  4836.2  297.82  4857.9  297.19  4901.5  298.21  4955.3  297.30  4961.0  296.10
  4992.3  294.35  5017.7  291.08  5018.0  290.58  5022.2  291.08  5030.1  293.08
  5040.2  293.87  5101.0  292.85  5111.1  293.68  5135.1  293.54  5232.6  297.40
  5259.1  299.51  5293.4  300.29  5388.1  301.62  5394.7  301.01  5517.1  301.53
  5536.5  302.47  5566.8  302.04  5579.1  302.75  5728.9  303.67  5860.5  307.59
#Mann=3,-1,0
  4657.7    0.07       0  5017.7    0.05       0  5022.2    0.07       0
Bank Sta=5017.7,5022.2
Exp/Cntr=0.3,0.1

Type RM Length L Ch R = 1,588,295,295,295
BEGIN DESCRIPTION:
XS7512
END DESCRIPTION:
XS GIS Cut Line= 4
      2402306.36     13680364.83      2402705.64     13680212.93
      2402744.70     13680052.34      2402497.32     13679275.45
#Sta/Elev= 30
  4524.0  299.49  4562.9  299.76  4762.9  297.14  4832.8  297.03  4967.1  291.31
  4972.2  291.82  4977.7  290.44  4978.0  289.94  4982.2  290.44  5000.5  290.55
  5014.0  292.69  5055.7  292.00  5097.4  292.93  5130.7  295.92  5176.7  298.25
  5302.6  299.57  5323.6  298.83  5399.0  300.08  5425.9  299.26  5495.6  300.15
  5522.6  299.58  5669.9  301.54  5680.4  301.05  5721.2  302.39  5732.9  302.01
  5837.8  304.17  5855.3  305.53  5869.3  305.31  5925.0  307.59  5931.8  308.53
#Mann=3,-1,0
  4524.0    0.07       0  4977.7    0.05       0  4982.2    0.07       0
Bank Sta=4977.7,4982.2
Exp/Cntr=0.3,0.1

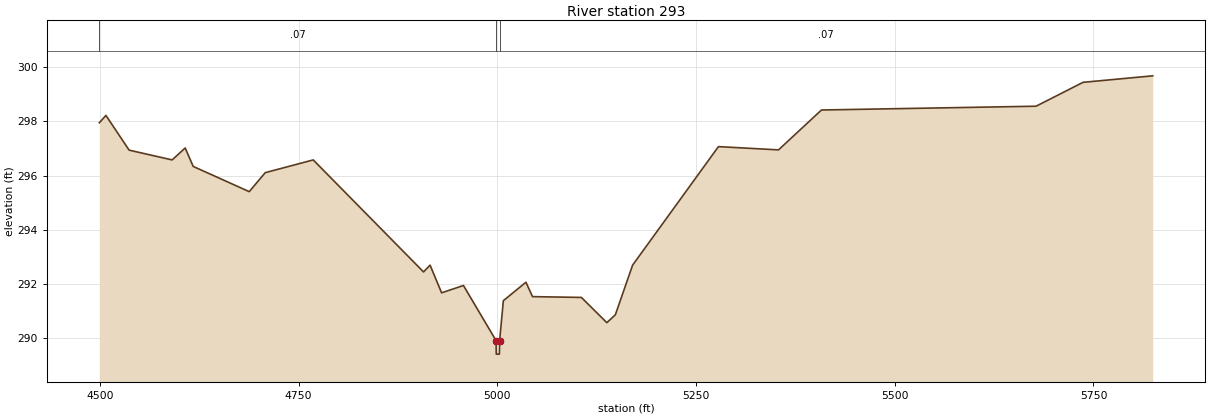
Type RM Length L Ch R = 1,293,0,0,0
BEGIN DESCRIPTION:
XS7513
END DESCRIPTION:
XS GIS Cut Line= 4
      2402527.71     13680360.50      2402935.68     13680312.76
      2403044.18     13680169.53      2402766.78     13679489.04
#Sta/Elev= 30
  4499.3  297.95  4507.6  298.22  4536.8  296.94  4590.9  296.58  4607.3  297.02
  4617.4  296.34  4687.9  295.41  4708.0  296.11  4768.4  296.58  4907.2  292.45
  4915.4  292.70  4929.9  291.68  4957.4  291.95  4998.4  289.92  4998.7  289.42
  5002.6  289.42  5002.9  289.92  5007.6  291.39  5036.0  292.07  5044.3  291.54
  5105.8  291.51  5137.8  290.58  5148.5  290.87  5170.2  292.70  5278.2  297.07
  5353.8  296.95  5407.8  298.42  5677.8  298.56  5736.9  299.44  5824.6  299.68
#Mann=3,-1,0
  4499.3    0.07       0  4998.4    0.05       0  5002.9    0.07       0
Bank Sta=4998.4,5002.9
Exp/Cntr=0.3,0.1

Chan Stop Cuts=-1