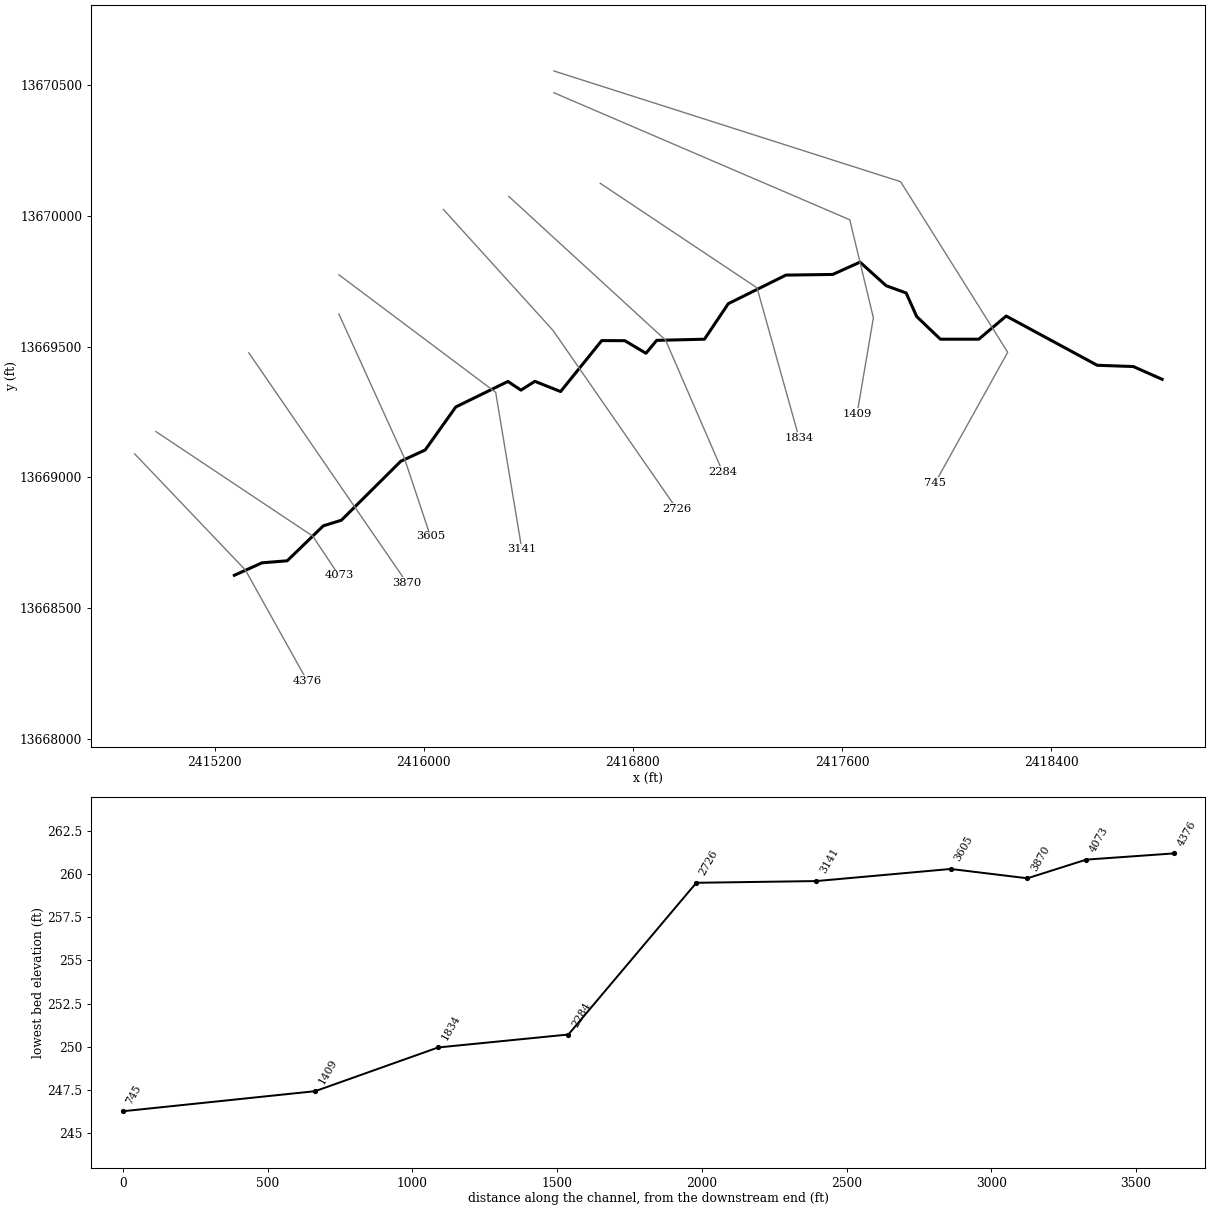
--- Stream0708.prj (project) ---

Proj Title=Stream0708 Base Level Engineering
Current Plan=p01
Default Exp/Contr=0.3,0.1
English Units
Geom File=g01
Flow File=f01
Plan File=p01
BEGIN DESCRIPTION:
Stream0708
END DESCRIPTION:

--- Stream0708.p01 (plan) ---

Plan Title=Multiple Run
Short Identifier=Multiple
Geom File=g01
Flow File=f01
Subcritical Flow
K Sum by GR= 0
Std Step Tol= 0.01
Critical Tol= 0.01
Num of Std Step Trials= 20
Max Error Tol= 0.3
Flow Tol Ratio= 0.001
Split Flow NTrial= 30
Split Flow Tol= 0.02
Split Flow Ratio= 0.02
Log Output Level= 0
Friction Slope Method= 1
Unsteady Friction Slope Method= 2
Unsteady Bridges Friction Slope Method= 1
Parabolic Critical Depth
Global Vel Dist=  1 , 1 , 1
Global Log Level= 0
CheckData=True
Encroach Param= -1, 0, 0, 0
BEGIN DESCRIPTION:
Multiple Run
END DESCRIPTION:

--- Stream0708.f01 (steady flow) ---

Flow Title=Multiple
Number of Profiles=7
Profile Names=10-year,25-year,50-year,1pct_min,100-year,1pct_plu,500-year
River Rch & RM= Stream0708,Reach-1,4376
     521     831    1107     714    1425    2844    2341
Boundary for River Rch & Prof#=Stream0708,Reach-1,1
Up Type=0
Dn Type=3
Dn Slope=0.005
Boundary for River Rch & Prof#=Stream0708,Reach-1,2
Up Type=0
Dn Type=3
Dn Slope=0.005
Boundary for River Rch & Prof#=Stream0708,Reach-1,3
Up Type=0
Dn Type=3
Dn Slope=0.005
Boundary for River Rch & Prof#=Stream0708,Reach-1,4
Up Type=0
Dn Type=3
Dn Slope=0.005
Boundary for River Rch & Prof#=Stream0708,Reach-1,5
Up Type=0
Dn Type=3
Dn Slope=0.005
Boundary for River Rch & Prof#=Stream0708,Reach-1,6
Up Type=0
Dn Type=3
Dn Slope=0.005
Boundary for River Rch & Prof#=Stream0708,Reach-1,7
Up Type=0
Dn Type=3
Dn Slope=0.005

--- Stream0708.g01 (geometry) ---

Geom Title=Existing Conditions

River Reach=Stream0708,Reach-1
Reach XY= 30
      2415275.00     13668625.00      2415380.92     13668672.77
      2415477.43     13668680.52      2415615.32     13668814.22
      2415684.68     13668835.78      2415911.79     13669061.37
      2416005.23     13669104.58      2416122.45     13669269.27
      2416321.77     13669366.77      2416371.67     13669333.55
      2416424.91     13669367.19      2416523.36     13669328.15
      2416680.71     13669523.11      2416769.05     13669522.80
      2416850.04     13669474.68      2416890.94     13669524.00
      2417073.75     13669528.45      2417165.00     13669664.37
      2417385.50     13669773.80      2417564.50     13669776.24
      2417668.96     13669823.37      2417768.98     13669733.19
      2417845.47     13669705.37      2417885.78     13669615.31
      2417976.46     13669528.52      2418123.53     13669528.55
      2418228.23     13669617.16      2418576.56     13669428.76
      2418714.53     13669423.87      2418825.00     13669375.00

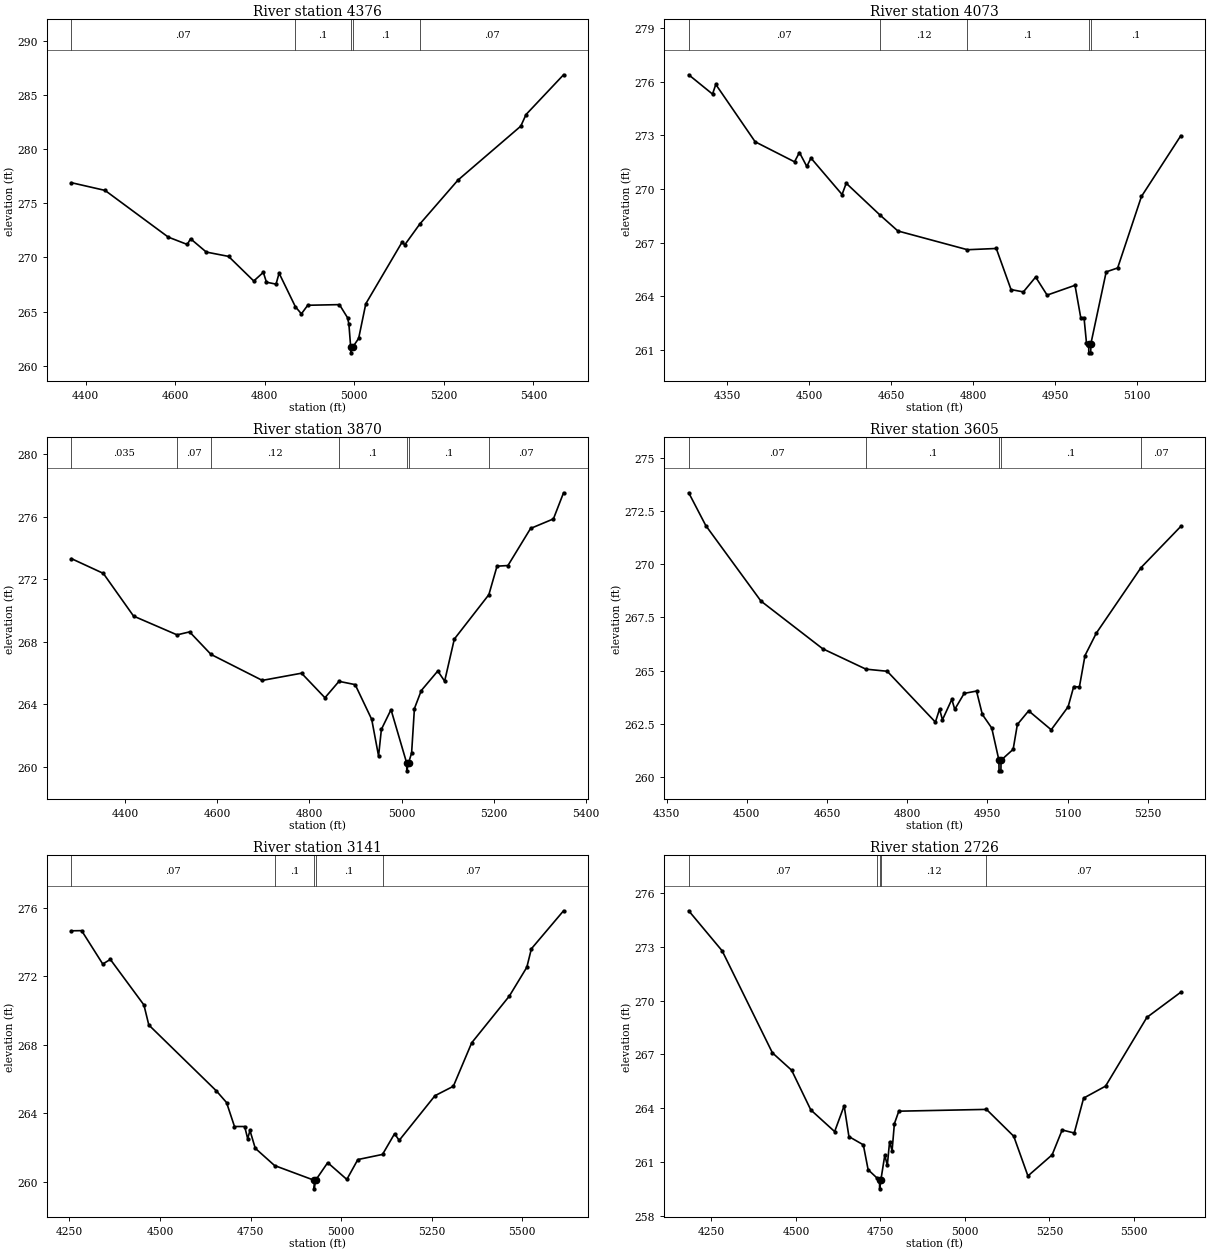
Type RM Length L Ch R = 1,4376,303,303,303
BEGIN DESCRIPTION:
XS7521
END DESCRIPTION:
XS GIS Cut Line= 3
      2414893.76     13669089.58      2415317.36     13668645.14
      2415553.45     13668221.57
#Sta/Elev= 30
  4368.6  276.89  4443.6  276.18  4584.8  271.87  4627.3  271.19  4634.5  271.72
  4669.7  270.49  4719.4  270.09  4775.7  267.82  4797.1  268.62  4804.0  267.71
  4825.4  267.53  4832.3  268.54  4868.7  265.44  4882.1  264.79  4896.2  265.58
  4967.0  265.64  4985.3  264.42  4988.2  263.81  4992.2  261.69  4992.4  261.19
  4996.2  261.69  5009.9  262.52  5025.9  265.72  5107.1  271.42  5112.8  271.15
  5146.2  273.06  5231.7  277.13  5372.0  282.11  5383.7  283.18  5467.5  286.85
#Mann=5,-1,0
  4368.6    0.07       0  4868.7     0.1       0  4992.2    0.05       0
  4996.2     0.1       0  5146.2    0.07       0
Bank Sta=4992.2,4996.2
Exp/Cntr=0.3,0.1

Type RM Length L Ch R = 1,4073,203,203,203
BEGIN DESCRIPTION:
Stream0708 8.0
END DESCRIPTION:
XS GIS Cut Line= 3
      2414974.99     13669175.00      2415575.00     13668775.00
      2415675.00     13668625.00
#Sta/Elev= 30
  4279.1  276.39  4322.7  275.31  4328.7  275.85  4400.8  272.64  4472.9  271.52
  4481.9  272.04  4495.4  271.26  4503.0  271.73  4560.0  269.69  4567.6  270.32
  4628.8  268.56  4662.2  267.65  4789.7  266.60  4842.5  266.67  4869.5  264.37
  4892.1  264.24  4914.6  265.07  4935.6  264.06  4986.7  264.61  4997.2  262.80
  5003.2  262.80  5007.7  261.39  5011.7  261.33  5012.0  260.83  5015.5  260.83
  5015.7  261.33  5043.8  265.36  5064.8  265.58  5108.4  269.58  5180.5  272.98
#Mann=5,-1,0
  4279.1    0.07       0  4628.8    0.12       0  4789.7     0.1       0
  5011.7    0.05       0  5015.7     0.1       0
Bank Sta=5011.7,5015.7
Exp/Cntr=0.3,0.1

Type RM Length L Ch R = 1,3870,265,265,265
BEGIN DESCRIPTION:
E21286
END DESCRIPTION:
XS GIS Cut Line= 2
      2415330.40     13669476.35      2415935.27     13668596.02
#Sta/Elev= 30
  4283.6  273.31  4352.7  272.37  4418.4  269.64  4512.8  268.44  4540.0  268.63
  4586.5  267.19  4697.8  265.53  4783.0  265.99  4833.8  264.42  4864.3  265.47
  4899.4  265.26  4935.3  263.04  4950.2  260.70  4956.3  262.40  4977.2  263.66
  5011.2  260.25  5011.5  259.75  5015.2  260.25  5021.9  260.89  5028.0  263.73
  5042.9  264.88  5078.7  266.13  5093.6  265.48  5114.6  268.17  5189.6  271.01
  5207.3  272.83  5231.0  272.87  5280.1  275.24  5329.7  275.85  5351.7  277.52
#Mann=7,-1,0
  4283.6   0.035       0  4512.8    0.07       0  4586.5    0.12       0
  4864.3     0.1       0  5011.2    0.05       0  5015.2     0.1       0
  5189.6    0.07       0
Bank Sta=5011.2,5015.2
Exp/Cntr=0.3,0.1

Type RM Length L Ch R = 1,3605,464,464,464
BEGIN DESCRIPTION:
Stream0708 7.0
END DESCRIPTION:
XS GIS Cut Line= 3
      2415674.99     13669625.02      2415925.00     13669075.00
      2416025.00     13668775.00
#Sta/Elev= 30
  4391.5  273.36  4423.4  271.82  4526.6  268.27  4642.0  266.03  4722.9  265.07
  4762.8  264.97  4852.9  262.58  4860.6  263.19  4866.1  262.69  4883.6  263.65
  4889.1  263.18  4906.7  263.93  4929.8  264.04  4940.7  262.94  4958.3  262.30
  4971.7  260.79  4971.9  260.29  4975.4  260.29  4975.7  260.79  4998.3  261.30
  5006.2  262.47  5027.3  263.11  5069.5  262.22  5101.1  263.30  5111.6  264.25
  5122.2  264.23  5132.7  265.71  5153.8  266.76  5237.4  269.84  5311.9  271.78
#Mann=5,-1,0
  4391.5    0.07       0  4722.9     0.1       0  4971.7    0.05       0
  4975.7     0.1       0  5237.4    0.07       0
Bank Sta=4971.7,4975.7
Exp/Cntr=0.3,0.1

Type RM Length L Ch R = 1,3141,415,415,415
BEGIN DESCRIPTION:
Stream0708 6.0
END DESCRIPTION:
XS GIS Cut Line= 3
      2415675.02     13669774.99      2416275.00     13669325.00
      2416375.01     13668724.96
#Sta/Elev= 30
  4255.7  274.66  4283.8  274.67  4342.1  272.72  4363.0  272.99  4455.7  270.33
  4469.2  269.16  4655.7  265.31  4683.8  264.63  4705.7  263.23  4733.8  263.23
  4742.1  262.52  4748.4  263.00  4763.0  261.96  4816.4  260.95  4925.6  260.09
  4925.8  259.59  4929.6  260.09  4963.0  261.12  5015.8  260.14  5046.2  261.30
  5114.3  261.60  5147.6  262.81  5160.3  262.42  5259.1  265.03  5309.8  265.58
  5360.5  268.12  5464.4  270.85  5512.6  272.53  5525.2  273.61  5614.0  275.83
#Mann=5,-1,0
  4255.7    0.07       0  4816.4     0.1       0  4925.6    0.05       0
  4929.6     0.1       0  5114.3    0.07       0
Bank Sta=4925.6,4929.6
Exp/Cntr=0.3,0.1

Type RM Length L Ch R = 1,2726,442,442,442
BEGIN DESCRIPTION:
Stream0708 5.0
END DESCRIPTION:
XS GIS Cut Line= 3
      2416075.00     13670025.00      2416494.78     13669561.58
      2416968.04     13668878.61
#Sta/Elev= 30
  4182.7  275.03  4281.7  272.79  4430.4  267.09  4487.2  266.12  4544.0  263.90
  4614.5  262.69  4642.6  264.13  4656.8  262.41  4699.4  261.95  4713.6  260.56
  4740.7  260.08  4747.4  259.99  4747.6  259.49  4751.4  259.99  4762.9  261.37
  4770.4  260.81  4777.1  262.12  4784.5  261.62  4791.3  263.13  4804.4  263.83
  5063.8  263.93  5144.5  262.43  5186.5  260.21  5258.1  261.39  5287.8  262.78
  5323.6  262.61  5351.3  264.56  5416.2  265.23  5538.4  269.07  5638.9  270.48
#Mann=5,-1,0
  4182.7    0.07       0  4740.7    0.12       0  4747.4    0.05       0
  4751.4    0.12       0  5063.8    0.07       0
Bank Sta=4747.4,4751.4
Exp/Cntr=0.3,0.1

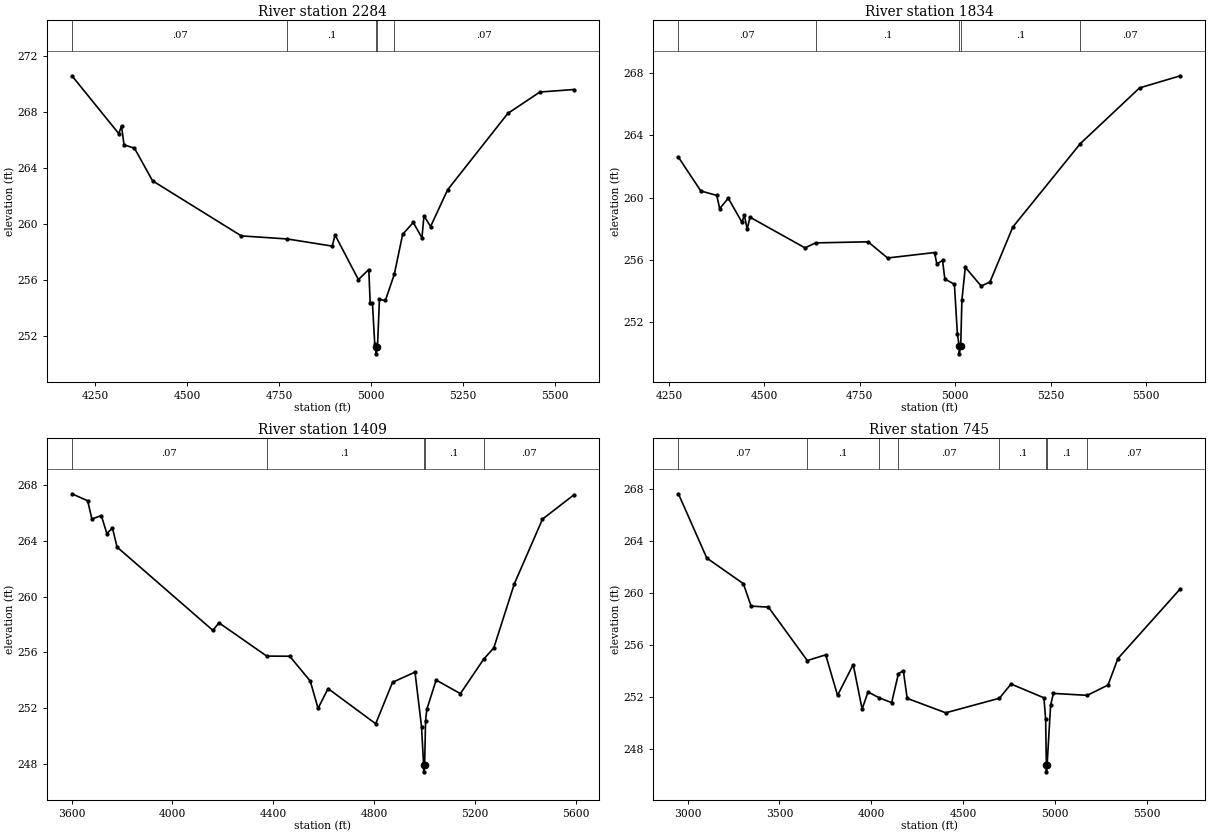
Type RM Length L Ch R = 1,2284,450,450,450
BEGIN DESCRIPTION:
Stream0708 4.0
END DESCRIPTION:
XS GIS Cut Line= 3
      2416325.01     13670074.99      2416925.00     13669525.00
      2417143.73     13669020.18
#Sta/Elev= 30
  4186.8  270.56  4314.1  266.43  4321.5  266.98  4328.3  265.63  4356.7  265.39
  4406.0  263.06  4647.1  259.13  4772.3  258.91  4894.4  258.40  4901.8  259.20
  4965.3  256.01  4993.6  256.73  4997.3  254.34  5003.5  254.34  5009.7  251.43
  5013.2  251.21  5013.4  250.71  5017.2  251.21  5022.5  254.59  5038.7  254.52
  5062.9  256.39  5085.6  259.24  5114.5  260.09  5138.0  258.99  5143.5  260.56
  5161.5  259.80  5207.8  262.42  5371.3  267.87  5458.5  269.40  5550.9  269.58
#Mann=5,-1,0
  4186.8    0.07       0  4772.3     0.1       0  5013.2    0.05       0
  5017.2     0.1       0  5062.9    0.07       0
Bank Sta=5013.2,5017.2
Exp/Cntr=0.3,0.1

Type RM Length L Ch R = 1,1834,425,425,425
BEGIN DESCRIPTION:
Stream0708 3.0
END DESCRIPTION:
XS GIS Cut Line= 3
      2416674.98     13670125.01      2417275.00     13669725.00
      2417435.42     13669152.07
#Sta/Elev= 30
  4274.3  262.60  4332.9  260.43  4375.0  260.14  4382.5  259.29  4405.0  259.96
  4441.1  258.41  4447.1  258.89  4454.6  257.98  4462.1  258.74  4606.3  256.77
  4633.8  257.09  4771.6  257.16  4822.7  256.12  4945.9  256.47  4951.9  255.74
  4966.9  255.96  4972.9  254.77  4998.0  254.43  5005.8  251.25  5010.5  250.46
  5010.7  249.96  5014.5  250.46  5017.7  253.43  5026.6  255.52  5068.1  254.32
  5091.1  254.57  5151.2  258.11  5328.2  263.47  5483.5  267.05  5590.4  267.83
#Mann=5,-1,0
  4274.3    0.07       0  4633.8     0.1       0  5010.5    0.05       0
  5014.5     0.1       0  5328.2    0.07       0
Bank Sta=5010.5,5014.5
Exp/Cntr=0.3,0.1

Type RM Length L Ch R = 1,1409,664,664,664
BEGIN DESCRIPTION:
XS7520
END DESCRIPTION:
XS GIS Cut Line= 4
      2416497.88     13670471.54      2417629.86     13669985.42
      2417720.14     13669610.42      2417657.64     13669242.35
#Sta/Elev= 30
  3601.4  267.37  3663.6  266.87  3680.6  265.56  3718.0  265.81  3739.7  264.52
  3762.2  264.91  3780.3  263.55  4160.8  257.57  4184.3  258.12  4374.1  255.73
  4465.2  255.72  4546.8  253.94  4577.7  251.98  4617.4  253.40  4806.3  250.88
  4873.2  253.85  4962.2  254.58  4988.1  250.68  4996.4  247.93  4996.6  247.43
  5000.4  247.93  5004.2  251.11  5009.3  251.92  5046.1  254.01  5142.3  253.04
  5235.1  255.52  5274.9  256.32  5356.4  260.92  5468.0  265.55  5592.4  267.29
#Mann=5,-1,0
  3601.4    0.07       0  4374.1     0.1       0  4996.4    0.05       0
  5000.4     0.1       0  5235.1    0.07       0
Bank Sta=4996.4,5000.4
Exp/Cntr=0.3,0.1

Type RM Length L Ch R = 1,745,0,0,0
BEGIN DESCRIPTION:
XS7519
END DESCRIPTION:
XS GIS Cut Line= 4
      2416497.91     13670554.86      2417824.31     13670131.25
      2418234.03     13669478.47      2417956.68     13668979.24
#Sta/Elev= 30
  2949.8  267.61  3104.2  262.68  3303.7  260.71  3345.7  258.99  3440.1  258.91
  3652.0  254.81  3752.2  255.25  3816.6  252.14  3902.0  254.50  3950.6  251.09
  3982.7  252.40  4043.7  251.95  4111.5  251.58  4148.0  253.79  4175.0  254.04
  4196.0  251.91  4406.0  250.80  4698.6  251.92  4761.8  253.01  4940.9  251.95
  4950.3  250.31  4954.2  246.77  4954.5  246.27  4958.2  246.77  4977.4  251.39
  4992.7  252.29  5176.6  252.14  5290.1  252.93  5343.8  254.96  5684.0  260.32
#Mann=8,-1,0
  2949.8    0.07       0  3652.0     0.1       0  4043.7    0.12       0
  4148.0    0.07       0  4698.6     0.1       0  4954.2    0.05       0
  4958.2     0.1       0  5176.6    0.07       0
Bank Sta=4954.2,4958.2
Exp/Cntr=0.3,0.1

Chan Stop Cuts=-1