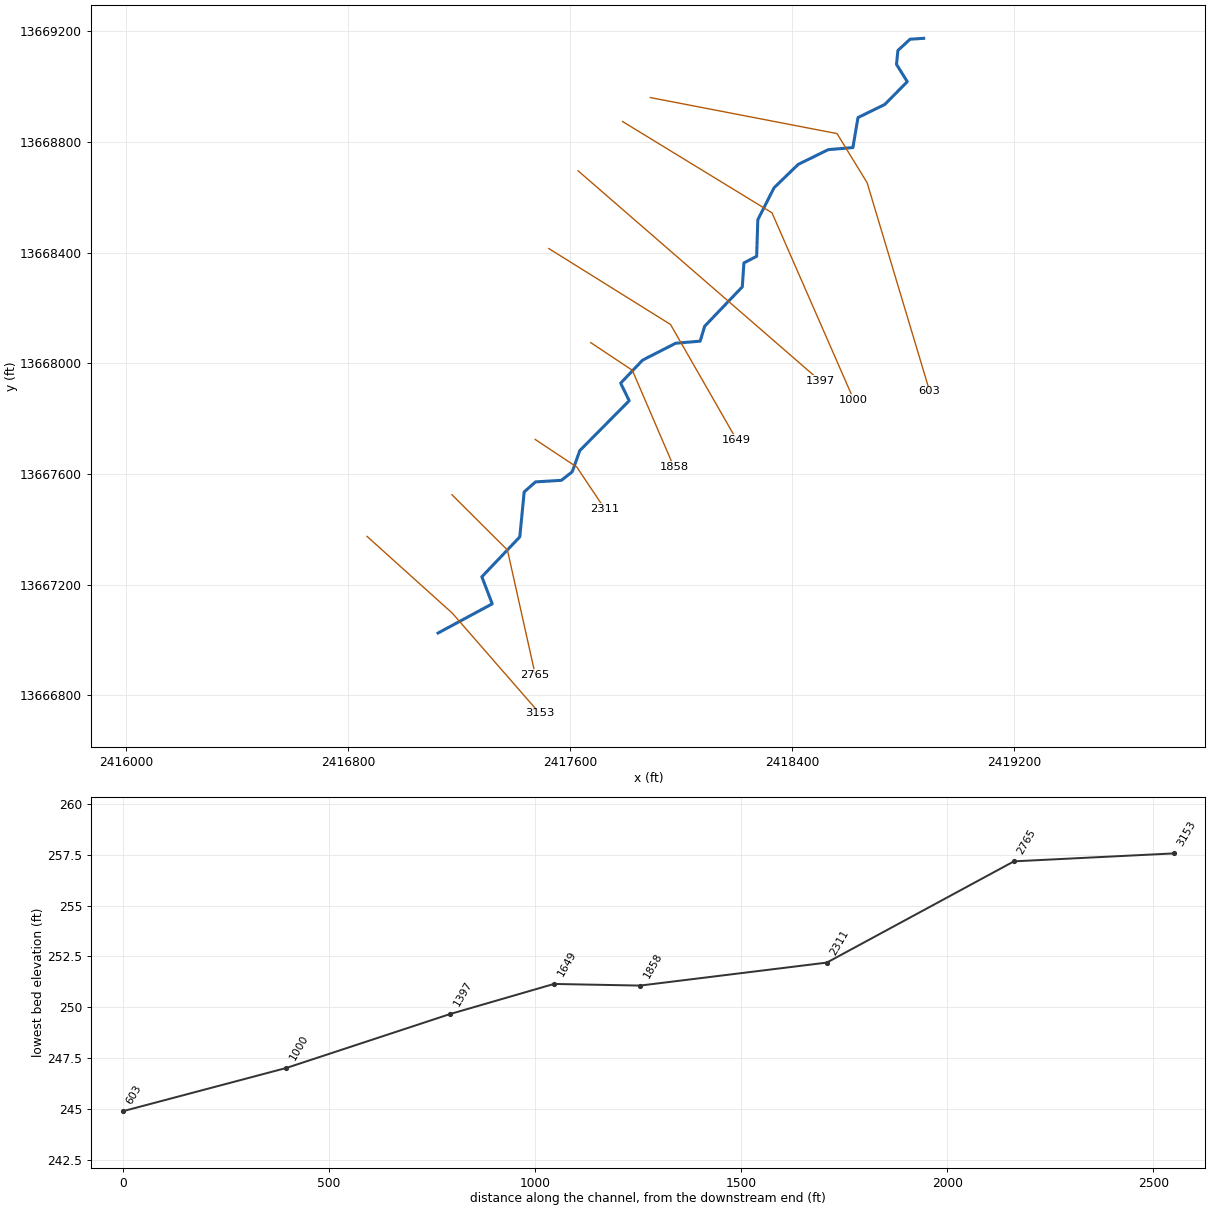
--- Stream0709.prj (project) ---

Proj Title=Stream0709 Base Level Engineering
Current Plan=p01
Default Exp/Contr=0.3,0.1
English Units
Geom File=g01
Flow File=f01
Plan File=p01
BEGIN DESCRIPTION:
Stream0709
END DESCRIPTION:

--- Stream0709.p01 (plan) ---

Plan Title=Multiple Run
Short Identifier=Multiple
Geom File=g01
Flow File=f01
Subcritical Flow
K Sum by GR= 0
Std Step Tol= 0.01
Critical Tol= 0.01
Num of Std Step Trials= 20
Max Error Tol= 0.3
Flow Tol Ratio= 0.001
Split Flow NTrial= 30
Split Flow Tol= 0.02
Split Flow Ratio= 0.02
Log Output Level= 0
Friction Slope Method= 1
Unsteady Friction Slope Method= 2
Unsteady Bridges Friction Slope Method= 1
Parabolic Critical Depth
Global Vel Dist=  1 , 1 , 1
Global Log Level= 0
CheckData=True
Encroach Param= -1, 0, 0, 0
BEGIN DESCRIPTION:
Multiple Run
END DESCRIPTION:

--- Stream0709.f01 (steady flow) ---

Flow Title=Multiple
Number of Profiles=7
Profile Names=10-year,25-year,50-year,1pct_min,100-year,1pct_plu,500-year
River Rch & RM= Stream0709,Reach-1,3153
     492     779    1033     665    1326    2646    2162
Boundary for River Rch & Prof#=Stream0709,Reach-1,1
Up Type=0
Dn Type=3
Dn Slope=0.005
Boundary for River Rch & Prof#=Stream0709,Reach-1,2
Up Type=0
Dn Type=3
Dn Slope=0.005
Boundary for River Rch & Prof#=Stream0709,Reach-1,3
Up Type=0
Dn Type=3
Dn Slope=0.005
Boundary for River Rch & Prof#=Stream0709,Reach-1,4
Up Type=0
Dn Type=3
Dn Slope=0.005
Boundary for River Rch & Prof#=Stream0709,Reach-1,5
Up Type=0
Dn Type=3
Dn Slope=0.005
Boundary for River Rch & Prof#=Stream0709,Reach-1,6
Up Type=0
Dn Type=3
Dn Slope=0.005
Boundary for River Rch & Prof#=Stream0709,Reach-1,7
Up Type=0
Dn Type=3
Dn Slope=0.005

--- Stream0709.g01 (geometry) ---

Geom Title=Existing Conditions

River Reach=Stream0709,Reach-1
Reach XY= 30
      2417125.00     13667025.00      2417320.21     13667130.59
      2417282.83     13667228.39      2417419.53     13667372.55
      2417435.33     13667535.17      2417476.25     13667571.49
      2417569.28     13667577.08      2417608.54     13667607.87
      2417635.79     13667684.66      2417813.76     13667865.00
      2417783.00     13667928.35      2417861.73     13668011.38
      2417981.05     13668072.63      2418069.53     13668080.26
      2418085.90     13668134.38      2418221.36     13668276.56
      2418227.09     13668362.98      2418273.02     13668386.97
      2418277.25     13668519.06      2418335.75     13668634.71
      2418422.69     13668719.18      2418531.06     13668772.63
      2418619.89     13668780.11      2418638.27     13668888.62
      2418734.71     13668935.79      2418815.86     13669018.25
      2418776.97     13669081.06      2418782.23     13669131.30
      2418825.94     13669171.86      2418875.00     13669175.00

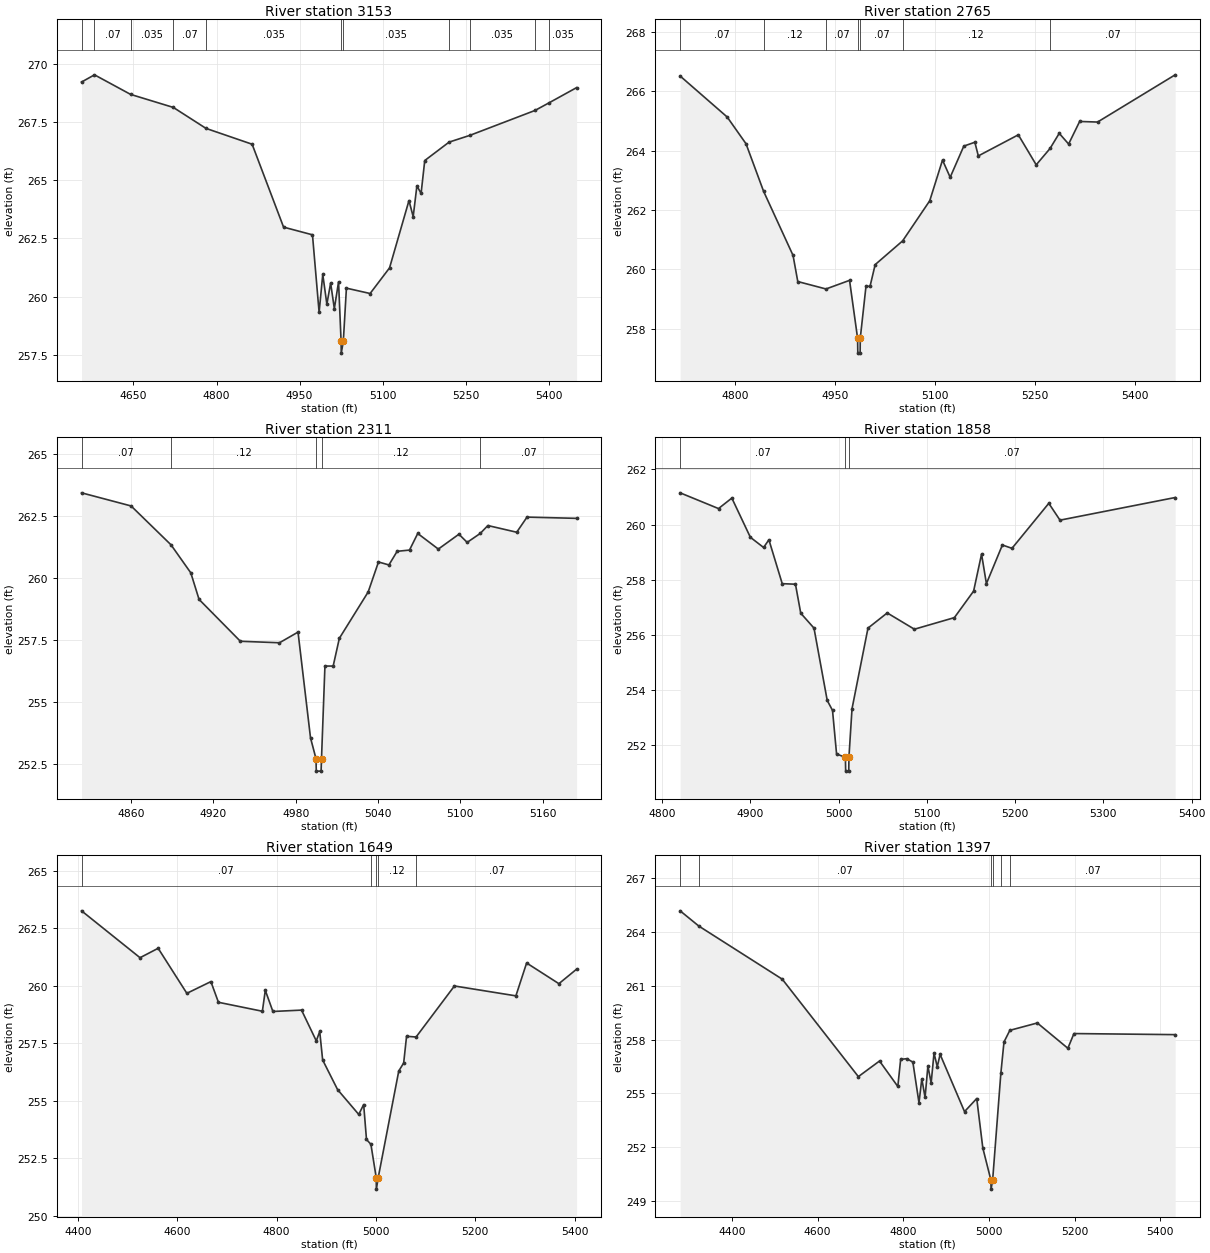
Type RM Length L Ch R = 1,3153,388,388,388
BEGIN DESCRIPTION:
Stream0709 7.0
END DESCRIPTION:
XS GIS Cut Line= 3
      2416869.02     13667374.43      2417176.69     13667096.53
      2417491.18     13666734.57
#Sta/Elev= 30
  4556.2  269.21  4579.6  269.52  4644.8  268.68  4722.0  268.12  4781.0  267.22
  4864.3  266.54  4921.1  262.98  4973.3  262.65  4985.3  259.32  4991.9  260.95
  4999.3  259.67  5006.1  260.58  5012.8  259.48  5020.4  260.63  5025.0  258.07
  5025.3  257.57  5029.0  258.07  5034.6  260.36  5077.4  260.13  5112.5  261.23
  5147.6  264.12  5155.2  263.43  5161.9  264.75  5169.5  264.43  5176.1  265.84
  5220.0  266.63  5257.5  266.92  5375.2  267.99  5400.0  268.31  5450.3  268.97
#Mann=11,-1,0
  4556.2   0.035       0  4579.6    0.07       0  4644.8   0.035       0
  4722.0    0.07       0  4781.0   0.035       0  5025.0   0.035       0
  5029.0   0.035       0  5220.0    0.07       0  5257.5   0.035       0
  5375.2    0.07       0  5400.0   0.035       0
Bank Sta=5025,5029
Exp/Cntr=0.3,0.1

Type RM Length L Ch R = 1,2765,454,454,454
BEGIN DESCRIPTION:
Stream0709 6.0
END DESCRIPTION:
XS GIS Cut Line= 3
      2417174.97     13667525.03      2417375.00     13667325.00
      2417475.01     13666874.96
#Sta/Elev= 30
  4716.8  266.51  4787.5  265.13  4815.8  264.23  4842.2  262.63  4886.5  260.47
  4893.6  259.59  4936.0  259.34  4971.4  259.63  4983.5  257.68  4983.8  257.18
  4987.3  257.18  4987.5  257.68  4996.1  259.43  5002.2  259.43  5009.9  260.16
  5051.2  260.96  5091.9  262.31  5111.1  263.68  5122.6  263.10  5143.1  264.15
  5159.7  264.28  5164.9  263.82  5225.0  264.53  5251.9  263.52  5272.7  264.07
  5286.5  264.58  5300.6  264.22  5317.2  264.98  5344.1  264.96  5460.7  266.55
#Mann=7,-1,0
  4716.8    0.07       0  4842.2    0.12       0  4936.0    0.07       0
  4983.5    0.05       0  4987.5    0.07       0  5051.2    0.12       0
  5272.7    0.07       0
Bank Sta=4983.5,4987.5
Exp/Cntr=0.3,0.1

Type RM Length L Ch R = 1,2311,453,453,453
BEGIN DESCRIPTION:
Stream0709 5.0
END DESCRIPTION:
XS GIS Cut Line= 3
      2417475.00     13667725.00      2417625.00     13667625.00
      2417725.02     13667474.97
#Sta/Elev= 30
  4824.0  263.43  4860.1  262.90  4889.2  261.33  4903.6  260.20  4909.6  259.13
  4939.7  257.44  4968.2  257.38  4981.7  257.81  4990.8  253.54  4994.8  252.70
  4995.0  252.20  4998.5  252.20  4998.8  252.70  5001.3  256.44  5007.3  256.44
  5011.8  257.56  5032.8  259.43  5040.3  260.64  5047.9  260.52  5053.9  261.07
  5062.9  261.12  5068.9  261.79  5083.9  261.16  5098.9  261.76  5104.9  261.43
  5114.4  261.79  5120.0  262.11  5141.0  261.84  5148.5  262.45  5184.6  262.40
#Mann=5,-1,0
  4824.0    0.07       0  4889.2    0.12       0  4994.8    0.05       0
  4998.8    0.12       0  5114.4    0.07       0
Bank Sta=4994.8,4998.8
Exp/Cntr=0.3,0.1

Type RM Length L Ch R = 1,1858,209,209,209
BEGIN DESCRIPTION:
Stream0709 4.0
END DESCRIPTION:
XS GIS Cut Line= 3
      2417675.02     13668074.99      2417825.00     13667975.00
      2417974.98     13667625.04
#Sta/Elev= 30
  4820.3  261.15  4863.8  260.58  4878.9  260.96  4899.9  259.54  4914.9  259.17
  4920.9  259.45  4936.0  257.86  4951.0  257.84  4957.0  256.79  4972.0  256.25
  4987.0  253.63  4993.0  253.27  4997.6  251.69  5007.6  251.57  5007.9  251.07
  5011.4  251.07  5011.6  251.57  5015.1  253.33  5033.2  256.25  5055.0  256.80
  5085.8  256.21  5131.1  256.63  5152.9  257.59  5161.9  258.93  5167.4  257.86
  5185.5  259.26  5196.4  259.14  5238.1  260.77  5250.8  260.16  5381.3  260.98
#Mann=3,-1,0
  4820.3    0.07       0  5007.6    0.05       0  5011.6    0.07       0
Bank Sta=5007.6,5011.6
Exp/Cntr=0.3,0.1

Type RM Length L Ch R = 1,1649,252,252,252
BEGIN DESCRIPTION:
E21287
END DESCRIPTION:
XS GIS Cut Line= 3
      2417524.19     13668414.99      2417962.71     13668140.54
      2418200.70     13667724.07
#Sta/Elev= 30
  4407.1  263.26  4524.9  261.22  4561.4  261.63  4619.2  259.67  4667.6  260.18
  4682.8  259.28  4771.3  258.89  4777.2  259.80  4792.5  258.88  4850.2  258.94
  4879.9  257.60  4886.8  258.01  4892.7  256.77  4922.8  255.48  4965.4  254.40
  4975.3  254.83  4981.0  253.31  4989.9  253.10  5000.6  251.65  5000.9  251.15
  5004.6  251.65  5046.0  256.29  5055.9  256.64  5061.7  257.80  5080.9  257.77
  5158.1  259.99  5281.9  259.56  5303.5  260.99  5368.5  260.09  5404.1  260.72
#Mann=5,-1,0
  4407.1    0.07       0  4989.9    0.12       0  5000.6    0.05       0
  5004.6    0.12       0  5080.9    0.07       0
Bank Sta=5000.6,5004.6
Exp/Cntr=0.3,0.1

Type RM Length L Ch R = 1,1397,397,397,397
BEGIN DESCRIPTION:
XS7524
END DESCRIPTION:
XS GIS Cut Line= 2
      2417629.61     13668696.09      2418501.01     13667937.40
#Sta/Elev= 30
  4279.3  265.18  4323.0  264.33  4517.7  261.37  4695.3  255.94  4744.7  256.81
  4787.4  255.39  4794.0  256.90  4808.3  256.94  4822.5  256.75  4836.8  254.48
  4843.4  255.82  4851.0  254.78  4857.6  256.53  4865.2  255.59  4871.9  257.25
  4879.5  256.49  4886.1  257.18  4943.1  253.99  4971.6  254.72  4985.8  251.96
  5004.7  250.17  5005.0  249.67  5008.7  250.17  5027.9  256.13  5035.2  257.87
  5048.9  258.52  5113.0  258.93  5184.3  257.52  5198.5  258.34  5434.7  258.28
#Mann=6,-1,0
  4279.3    0.05       0  4323.0    0.07       0  5004.7    0.05       0
  5008.7    0.07       0  5027.9    0.12       0  5048.9    0.07       0
Bank Sta=5004.7,5008.7
Exp/Cntr=0.3,0.1

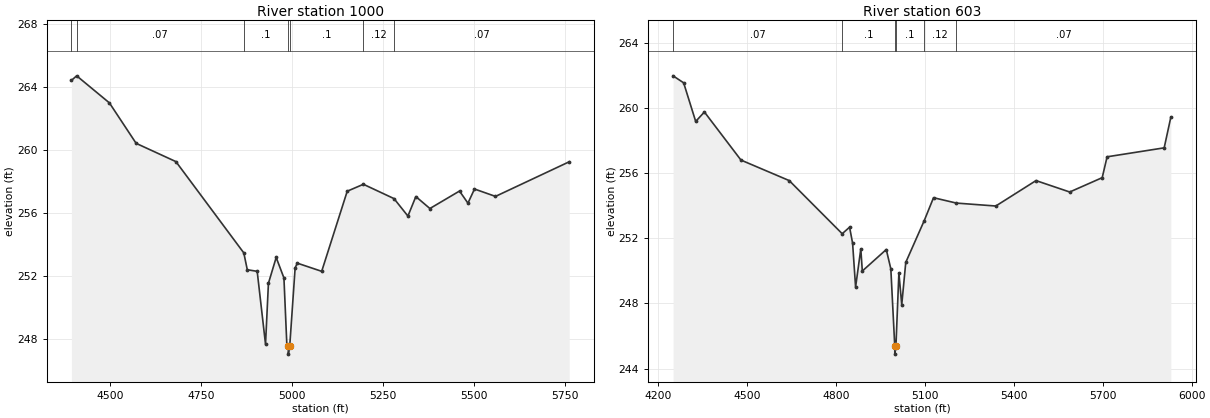
Type RM Length L Ch R = 1,1000,397,397,397
BEGIN DESCRIPTION:
XS7523
END DESCRIPTION:
XS GIS Cut Line= 3
      2417790.16     13668874.06      2418328.39     13668544.18
      2418622.89     13667868.56
#Sta/Elev= 30
  4394.0  264.41  4408.4  264.70  4498.4  262.98  4571.9  260.41  4681.2  259.25
  4867.8  253.45  4877.4  252.38  4904.6  252.28  4927.5  247.65  4935.5  251.52
  4956.8  253.16  4978.1  251.86  4986.1  247.62  4990.0  247.52  4990.2  247.02
  4994.0  247.52  5008.9  252.50  5014.8  252.80  5081.9  252.28  5152.1  257.37
  5196.5  257.81  5280.7  256.90  5318.9  255.79  5340.7  257.03  5379.3  256.27
  5460.7  257.38  5483.9  256.61  5501.9  257.51  5559.6  257.04  5762.3  259.24
#Mann=7,-1,0
  4394.0    0.05       0  4408.4    0.07       0  4867.8     0.1       0
  4990.0    0.05       0  4994.0     0.1       0  5196.5    0.12       0
  5280.7    0.07       0
Bank Sta=4990,4994
Exp/Cntr=0.3,0.1

Type RM Length L Ch R = 1,603,0,0,0
BEGIN DESCRIPTION:
XS7522
END DESCRIPTION:
XS GIS Cut Line= 4
      2417889.99     13668960.86      2418562.76     13668830.64
      2418671.27     13668652.69      2418896.59     13667898.72
#Sta/Elev= 30
  4249.2  261.97  4284.9  261.54  4325.6  259.17  4355.0  259.75  4478.4  256.80
  4641.4  255.54  4820.2  252.28  4845.1  252.68  4855.3  251.70  4865.4  249.00
  4883.0  251.35  4888.1  249.99  4969.0  251.31  4984.4  250.12  4997.6  245.39
  4997.9  244.89  5001.6  245.39  5011.6  249.88  5021.2  247.92  5034.8  250.52
  5097.3  253.09  5128.5  254.49  5205.6  254.16  5338.8  253.98  5474.5  255.54
  5588.3  254.84  5698.0  255.72  5714.5  257.00  5907.2  257.55  5929.8  259.44
#Mann=6,-1,0
  4249.2    0.07       0  4820.2     0.1       0  4997.6    0.05       0
  5001.6     0.1       0  5097.3    0.12       0  5205.6    0.07       0
Bank Sta=4997.6,5001.6
Exp/Cntr=0.3,0.1

Chan Stop Cuts=-1