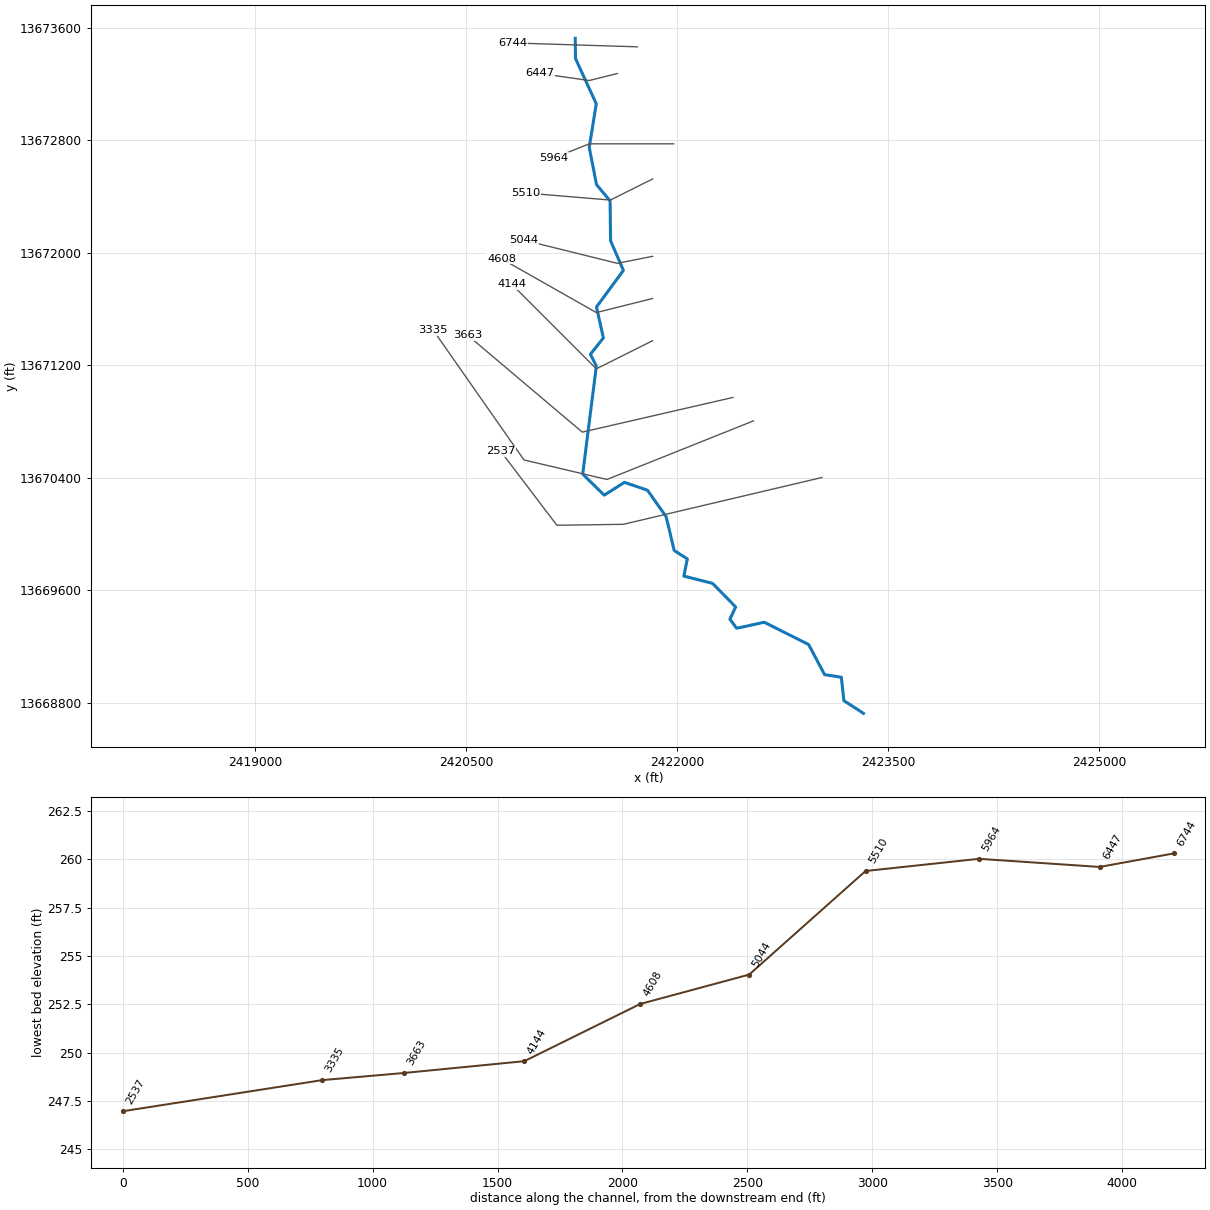
--- Stream0710.prj (project) ---

Proj Title=Stream0710 Base Level Engineering
Current Plan=p01
Default Exp/Contr=0.3,0.1
English Units
Geom File=g01
Flow File=f01
Plan File=p01
BEGIN DESCRIPTION:
Stream0710
END DESCRIPTION:

--- Stream0710.p01 (plan) ---

Plan Title=Multiple Run
Short Identifier=Multiple
Geom File=g01
Flow File=f01
Subcritical Flow
K Sum by GR= 0
Std Step Tol= 0.01
Critical Tol= 0.01
Num of Std Step Trials= 20
Max Error Tol= 0.3
Flow Tol Ratio= 0.001
Split Flow NTrial= 30
Split Flow Tol= 0.02
Split Flow Ratio= 0.02
Log Output Level= 0
Friction Slope Method= 1
Unsteady Friction Slope Method= 2
Unsteady Bridges Friction Slope Method= 1
Parabolic Critical Depth
Global Vel Dist=  1 , 1 , 1
Global Log Level= 0
CheckData=True
Encroach Param= -1, 0, 0, 0
BEGIN DESCRIPTION:
Multiple Run
END DESCRIPTION:

--- Stream0710.f01 (steady flow) ---

Flow Title=Multiple
Number of Profiles=7
Profile Names=10-year,25-year,50-year,1pct_min,100-year,1pct_plu,500-year
River Rch & RM= Stream0710,Reach-1,6744
     444     695     914     583    1163    2321    1864
Boundary for River Rch & Prof#=Stream0710,Reach-1,1
Up Type=0
Dn Type=3
Dn Slope=0.005
Boundary for River Rch & Prof#=Stream0710,Reach-1,2
Up Type=0
Dn Type=3
Dn Slope=0.005
Boundary for River Rch & Prof#=Stream0710,Reach-1,3
Up Type=0
Dn Type=3
Dn Slope=0.005
Boundary for River Rch & Prof#=Stream0710,Reach-1,4
Up Type=0
Dn Type=3
Dn Slope=0.005
Boundary for River Rch & Prof#=Stream0710,Reach-1,5
Up Type=0
Dn Type=3
Dn Slope=0.005
Boundary for River Rch & Prof#=Stream0710,Reach-1,6
Up Type=0
Dn Type=3
Dn Slope=0.005
Boundary for River Rch & Prof#=Stream0710,Reach-1,7
Up Type=0
Dn Type=3
Dn Slope=0.005

--- Stream0710.g01 (geometry) ---

Geom Title=Existing Conditions

River Reach=Stream0710,Reach-1
Reach XY= 30
      2421275.00     13673525.00      2421276.82     13673381.12
      2421424.48     13673059.78      2421374.60     13672750.00
      2421426.06     13672485.44      2421522.93     13672369.14
      2421526.22     13672085.50      2421617.47     13671874.99
      2421425.93     13671614.52      2421475.20     13671395.05
      2421382.83     13671278.40      2421425.21     13671195.21
      2421328.13     13670426.63      2421481.05     13670276.58
      2421624.90     13670367.67      2421788.65     13670311.74
      2421921.45     13670123.53      2421978.54     13669883.49
      2422071.90     13669823.55      2422047.30     13669701.26
      2422251.67     13669649.23      2422415.85     13669481.73
      2422374.64     13669395.03      2422422.38     13669329.99
      2422619.11     13669373.03      2422934.81     13669214.49
      2423047.88     13669000.59      2423167.18     13668981.82
      2423185.46     13668815.18      2423325.00     13668725.00

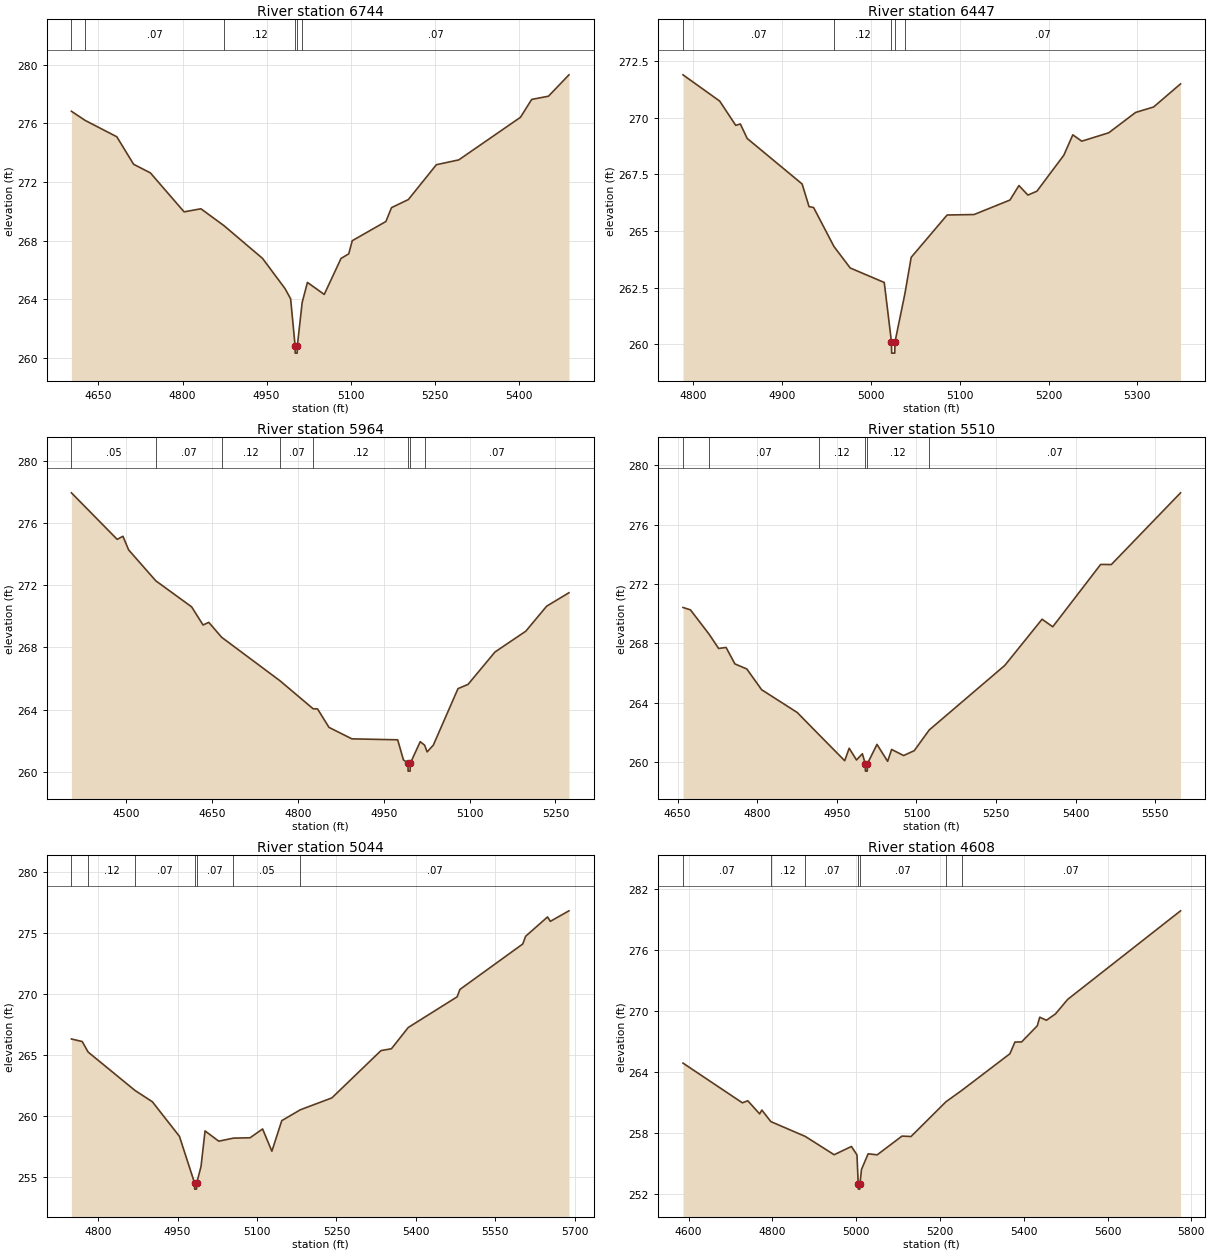
Type RM Length L Ch R = 1,6744,297,297,297
BEGIN DESCRIPTION:
XS7526
END DESCRIPTION:
XS GIS Cut Line= 2
      2421715.97     13673464.58      2420828.51     13673492.32
#Sta/Elev= 30
  4601.7  276.83  4626.5  276.20  4682.7  275.09  4712.7  273.21  4742.7  272.62
  4802.8  269.96  4832.8  270.17  4873.9  269.02  4942.8  266.78  4982.9  264.72
  4992.9  264.02  5000.9  260.81  5001.1  260.31  5004.6  260.31  5004.9  260.81
  5013.5  263.77  5022.9  265.14  5052.9  264.32  5082.9  266.78  5096.6  267.09
  5102.9  267.99  5162.9  269.30  5173.0  270.25  5203.0  270.80  5253.0  273.18
  5293.0  273.51  5403.1  276.42  5423.1  277.64  5453.1  277.86  5489.6  279.32
#Mann=6,-1,0
  4601.7    0.05       0  4626.5    0.07       0  4873.9    0.12       0
  5000.9    0.05       0  5004.9    0.12       0  5013.5    0.07       0
Bank Sta=5000.9,5004.9
Exp/Cntr=0.3,0.1

Type RM Length L Ch R = 1,6447,483,483,483
BEGIN DESCRIPTION:
Stream0710 11.0
END DESCRIPTION:
XS GIS Cut Line= 3
      2421575.03     13673275.01      2421375.00     13673225.00
      2421025.03     13673275.00
#Sta/Elev= 30
  4788.8  271.90  4830.1  270.74  4848.1  269.67  4853.3  269.73  4861.0  269.09
  4922.8  267.08  4930.6  266.08  4935.7  266.04  4958.6  264.32  4976.9  263.37
  5015.2  262.73  5023.3  260.11  5023.5  259.61  5027.0  259.61  5027.3  260.11
  5038.4  262.23  5045.5  263.84  5085.9  265.71  5116.2  265.73  5156.6  266.37
  5166.7  267.01  5176.8  266.59  5186.9  266.76  5217.2  268.35  5227.3  269.25
  5237.4  268.97  5267.7  269.34  5298.0  270.24  5318.2  270.48  5348.5  271.50
#Mann=5,-1,0
  4788.8    0.07       0  4958.6    0.12       0  5023.3    0.05       0
  5027.3    0.12       0  5038.4    0.07       0
Bank Sta=5023.3,5027.3
Exp/Cntr=0.3,0.1

Type RM Length L Ch R = 1,5964,454,454,454
BEGIN DESCRIPTION:
Stream0710 10.0
END DESCRIPTION:
XS GIS Cut Line= 3
      2421974.96     13672775.00      2421375.00     13672775.00
      2421125.02     13672675.01
#Sta/Elev= 30
  4404.3  277.97  4484.3  274.97  4494.3  275.17  4504.3  274.29  4551.7  272.30
  4614.3  270.62  4634.3  269.45  4644.3  269.62  4666.7  268.66  4768.5  265.86
  4826.6  264.05  4834.3  264.04  4854.3  262.85  4894.3  262.11  4974.3  262.05
  4984.3  260.76  4992.3  260.53  4992.5  260.03  4996.0  260.03  4996.3  260.53
  5013.7  261.93  5021.4  261.70  5025.8  261.27  5036.6  261.71  5079.7  265.35
  5097.2  265.62  5144.3  267.71  5198.1  269.05  5234.5  270.66  5273.5  271.53
#Mann=8,-1,0
  4404.3    0.05       0  4551.7    0.07       0  4666.7    0.12       0
  4768.5    0.07       0  4826.6    0.12       0  4992.3    0.05       0
  4996.3    0.12       0  5021.4    0.07       0
Bank Sta=4992.3,4996.3
Exp/Cntr=0.3,0.1

Type RM Length L Ch R = 1,5510,466,466,466
BEGIN DESCRIPTION:
Stream0710 9.0
END DESCRIPTION:
XS GIS Cut Line= 3
      2421825.02     13672525.01      2421525.00     13672375.00
      2420925.01     13672425.00
#Sta/Elev= 30
  4660.1  270.42  4674.1  270.26  4709.5  268.61  4727.2  267.66  4741.2  267.73
  4757.9  266.62  4780.3  266.28  4808.3  264.88  4875.3  263.35  4916.5  261.85
  4964.8  260.10  4973.2  260.94  4987.1  260.15  4998.0  260.57  5003.6  259.90
  5003.8  259.40  5007.3  259.40  5007.6  259.90  5025.6  261.20  5045.7  260.06
  5053.2  260.86  5075.8  260.45  5095.9  260.78  5124.0  262.17  5266.5  266.52
  5336.7  269.63  5356.8  269.12  5447.1  273.32  5467.2  273.31  5597.6  278.14
#Mann=6,-1,0
  4660.1    0.05       0  4709.5    0.07       0  4916.5    0.12       0
  5003.6    0.05       0  5007.6    0.12       0  5124.0    0.07       0
Bank Sta=5003.6,5007.6
Exp/Cntr=0.3,0.1

Type RM Length L Ch R = 1,5044,436,436,436
BEGIN DESCRIPTION:
Stream0710 8.0
END DESCRIPTION:
XS GIS Cut Line= 3
      2421825.04     13671975.01      2421575.00     13671925.00
      2420910.37     13672089.59
#Sta/Elev= 30
  4749.5  266.32  4769.9  266.11  4781.1  265.25  4869.3  262.12  4902.5  261.18
  4953.5  258.36  4982.1  254.54  4982.3  254.04  4985.8  254.04  4986.1  254.54
  4994.3  255.89  5001.9  258.80  5027.8  257.96  5055.3  258.21  5086.9  258.24
  5110.6  258.96  5128.1  257.14  5146.8  259.64  5181.9  260.53  5241.4  261.50
  5334.2  265.37  5353.9  265.52  5385.7  267.26  5478.1  269.77  5483.2  270.37
  5602.0  274.09  5607.4  274.72  5648.8  276.30  5654.0  275.94  5689.2  276.80
#Mann=7,-1,0
  4749.5    0.07       0  4781.1    0.12       0  4869.3    0.07       0
  4982.1    0.05       0  4986.1    0.07       0  5055.3    0.05       0
  5181.9    0.07       0
Bank Sta=4982.1,4986.1
Exp/Cntr=0.3,0.1

Type RM Length L Ch R = 1,4608,464,464,464
BEGIN DESCRIPTION:
Stream0710 7.0
END DESCRIPTION:
XS GIS Cut Line= 3
      2421825.02     13671675.00      2421425.00     13671575.00
      2420750.72     13671957.62
#Sta/Elev= 30
  4586.7  264.90  4728.4  261.00  4741.3  261.20  4769.7  259.91  4774.8  260.29
  4796.5  259.15  4878.5  257.70  4947.5  255.90  4988.7  256.71  5001.9  255.89
  5005.0  253.02  5005.2  252.52  5008.7  252.52  5009.0  253.02  5012.7  254.45
  5028.6  255.99  5050.2  255.89  5109.4  257.73  5131.0  257.69  5214.3  261.10
  5252.8  262.24  5367.0  265.82  5379.0  266.97  5394.9  266.98  5432.4  268.57
  5438.2  269.41  5454.1  269.11  5475.7  269.73  5504.9  271.16  5774.3  279.86
#Mann=7,-1,0
  4586.7    0.07       0  4796.5    0.12       0  4878.5    0.07       0
  5005.0    0.05       0  5009.0    0.07       0  5214.3    0.05       0
  5252.8    0.07       0
Bank Sta=5005,5009
Exp/Cntr=0.3,0.1

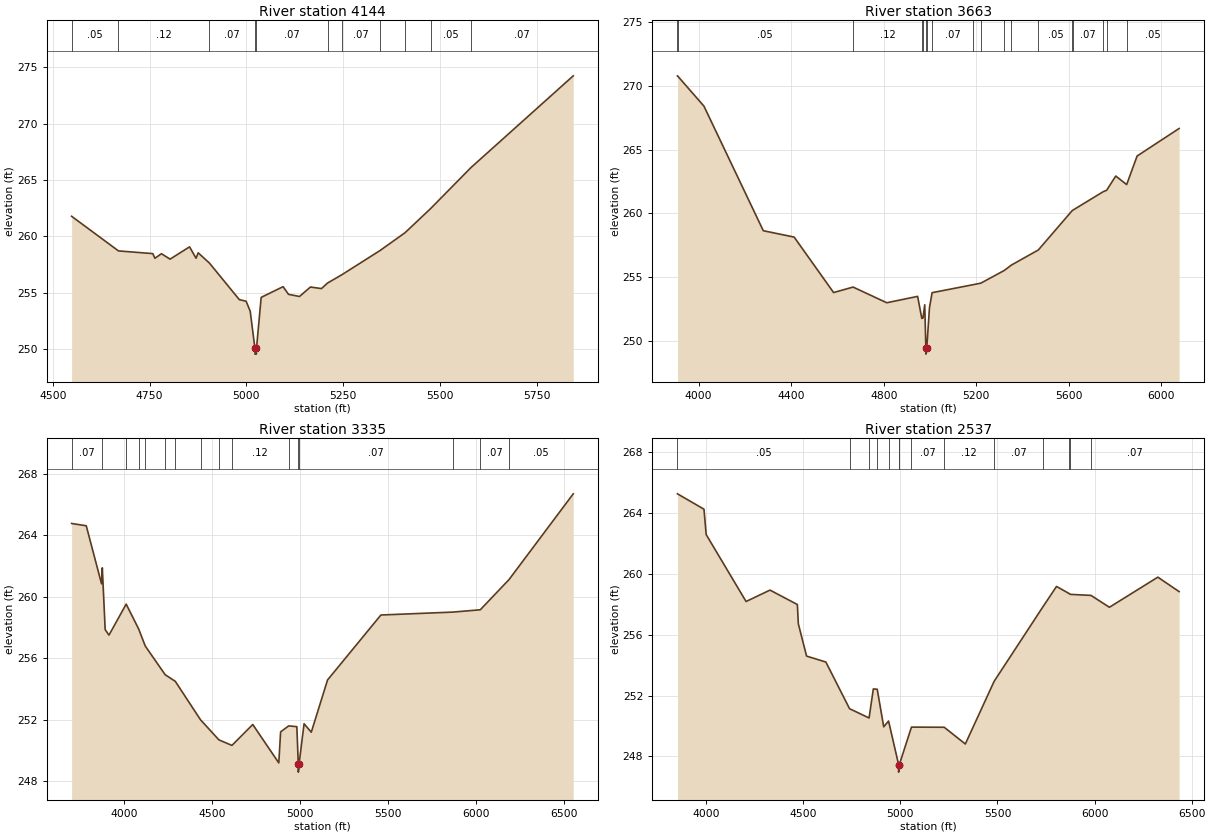
Type RM Length L Ch R = 1,4144,481,481,481
BEGIN DESCRIPTION:
Stream0710 6.0
END DESCRIPTION:
XS GIS Cut Line= 3
      2421824.98     13671374.99      2421425.00     13671175.00
      2420825.02     13671774.98
#Sta/Elev= 30
  4548.6  261.78  4669.6  258.71  4758.2  258.47  4763.8  258.06  4780.6  258.46
  4802.9  257.98  4853.2  259.07  4870.0  258.06  4875.6  258.54  4904.6  257.63
  4981.8  254.39  4999.3  254.25  5009.9  253.36  5022.1  250.06  5022.3  249.56
  5025.8  249.56  5026.1  250.06  5038.2  254.59  5094.8  255.54  5108.9  254.86
  5137.2  254.67  5165.5  255.51  5193.8  255.37  5209.7  255.86  5247.2  256.61
  5345.1  258.74  5409.7  260.32  5475.8  262.46  5580.2  266.10  5844.3  274.23
#Mann=11,-1,0
  4548.6    0.05       0  4669.6    0.12       0  4904.6    0.07       0
  5022.1    0.05       0  5026.1    0.07       0  5209.7    0.05       0
  5247.2    0.07       0  5345.1    0.05       0  5409.7    0.07       0
  5475.8    0.05       0  5580.2    0.07       0
Bank Sta=5022.1,5026.1
Exp/Cntr=0.3,0.1

Type RM Length L Ch R = 1,3663,328,328,328
BEGIN DESCRIPTION:
Stream0710 5.0
END DESCRIPTION:
XS GIS Cut Line= 3
      2422396.56     13670971.53      2421325.00     13670725.00
      2420508.82     13671414.98
#Sta/Elev= 30
  3908.5  270.78  3908.6  270.78  4023.0  268.40  4279.5  258.63  4412.9  258.13
  4583.3  253.78  4667.6  254.21  4813.1  252.98  4946.5  253.48  4964.6  251.75
  4969.8  251.79  4977.3  252.82  4982.1  249.45  4982.3  248.95  4986.1  249.45
  4997.8  252.59  5009.1  253.77  5187.5  254.40  5220.2  254.52  5320.8  255.51
  5352.3  255.94  5468.3  257.12  5615.8  260.23  5616.5  260.23  5748.6  261.69
  5763.4  261.80  5803.0  262.92  5850.1  262.25  5895.3  264.49  6076.8  266.65
#Mann=18,-1,0
  3908.5   0.035       0  3908.6    0.05       0  4667.6    0.12       0
  4964.6    0.07       0  4969.8    0.12       0  4982.1    0.05       0
  4986.1    0.12       0  5009.1    0.07       0  5187.5   0.035       0
  5220.2    0.07       0  5320.8   0.035       0  5352.3    0.07       0
  5468.3    0.05       0  5615.8   0.035       0  5616.5    0.07       0
  5748.6    0.05       0  5763.4    0.07       0  5850.1    0.05       0
Bank Sta=4982.1,4986.1
Exp/Cntr=0.3,0.1

Type RM Length L Ch R = 1,3335,798,798,798
BEGIN DESCRIPTION:
XS7525
END DESCRIPTION:
XS GIS Cut Line= 4
      2422542.34     13670804.85      2421500.69     13670388.19
      2420910.42     13670527.08      2420264.81     13671450.37
#Sta/Elev= 30
  3700.0  264.77  3783.3  264.62  3870.3  260.84  3874.7  261.88  3891.0  257.86
  3912.5  257.50  4010.5  259.52  4081.6  257.90  4119.1  256.79  4232.6  254.92
  4290.1  254.49  4433.5  251.99  4538.3  250.68  4612.3  250.32  4731.0  251.68
  4879.1  249.18  4889.4  251.20  4935.3  251.59  4981.8  251.54  4990.1  249.08
  4990.4  248.58  4994.1  249.08  5022.9  251.73  5064.0  251.18  5156.5  254.58
  5460.1  258.81  5870.1  259.00  6025.8  259.15  6189.6  261.12  6554.9  266.70
#Mann=16,-1,0
  3700.0    0.07       0  3870.3   0.035       0  4010.5    0.05       0
  4081.6   0.035       0  4119.1    0.05       0  4232.6    0.12       0
  4290.1    0.05       0  4433.5    0.12       0  4538.3    0.07       0
  4612.3    0.12       0  4935.3    0.07       0  4990.1    0.05       0
  4994.1    0.07       0  5870.1    0.05       0  6025.8    0.07       0
  6189.6    0.05       0
Bank Sta=4990.1,4994.1
Exp/Cntr=0.3,0.1

Type RM Length L Ch R = 1,2537,0,0,0
BEGIN DESCRIPTION:
E21288
END DESCRIPTION:
XS GIS Cut Line= 4
      2423028.93     13670402.24      2421617.27     13670069.31
      2421144.49     13670062.65      2420744.95     13670588.70
#Sta/Elev= 30
  3851.7  265.27  3988.2  264.26  3999.6  262.59  4205.0  258.19  4328.4  258.94
  4469.2  257.99  4474.3  256.72  4516.7  254.60  4616.0  254.21  4738.1  251.14
  4838.6  250.53  4860.5  252.44  4880.6  252.42  4914.0  249.95  4939.0  250.33
  4990.6  247.47  4990.8  246.97  4994.6  247.47  5056.9  249.93  5225.6  249.92
  5334.4  248.82  5482.7  252.94  5733.5  257.83  5804.1  259.18  5870.8  258.70
  5874.1  258.66  5981.8  258.59  6076.5  257.81  6326.0  259.79  6435.5  258.84
#Mann=14,-1,0
  3851.7    0.05       0  4738.1   0.035       0  4838.6    0.05       0
  4880.6   0.035       0  4939.0    0.05       0  4990.6    0.05       0
  4994.6    0.05       0  5056.9    0.07       0  5225.6    0.12       0
  5482.7    0.07       0  5733.5    0.12       0  5870.8    0.07       0
  5874.1    0.12       0  5981.8    0.07       0
Bank Sta=4990.6,4994.6
Exp/Cntr=0.3,0.1

Chan Stop Cuts=-1