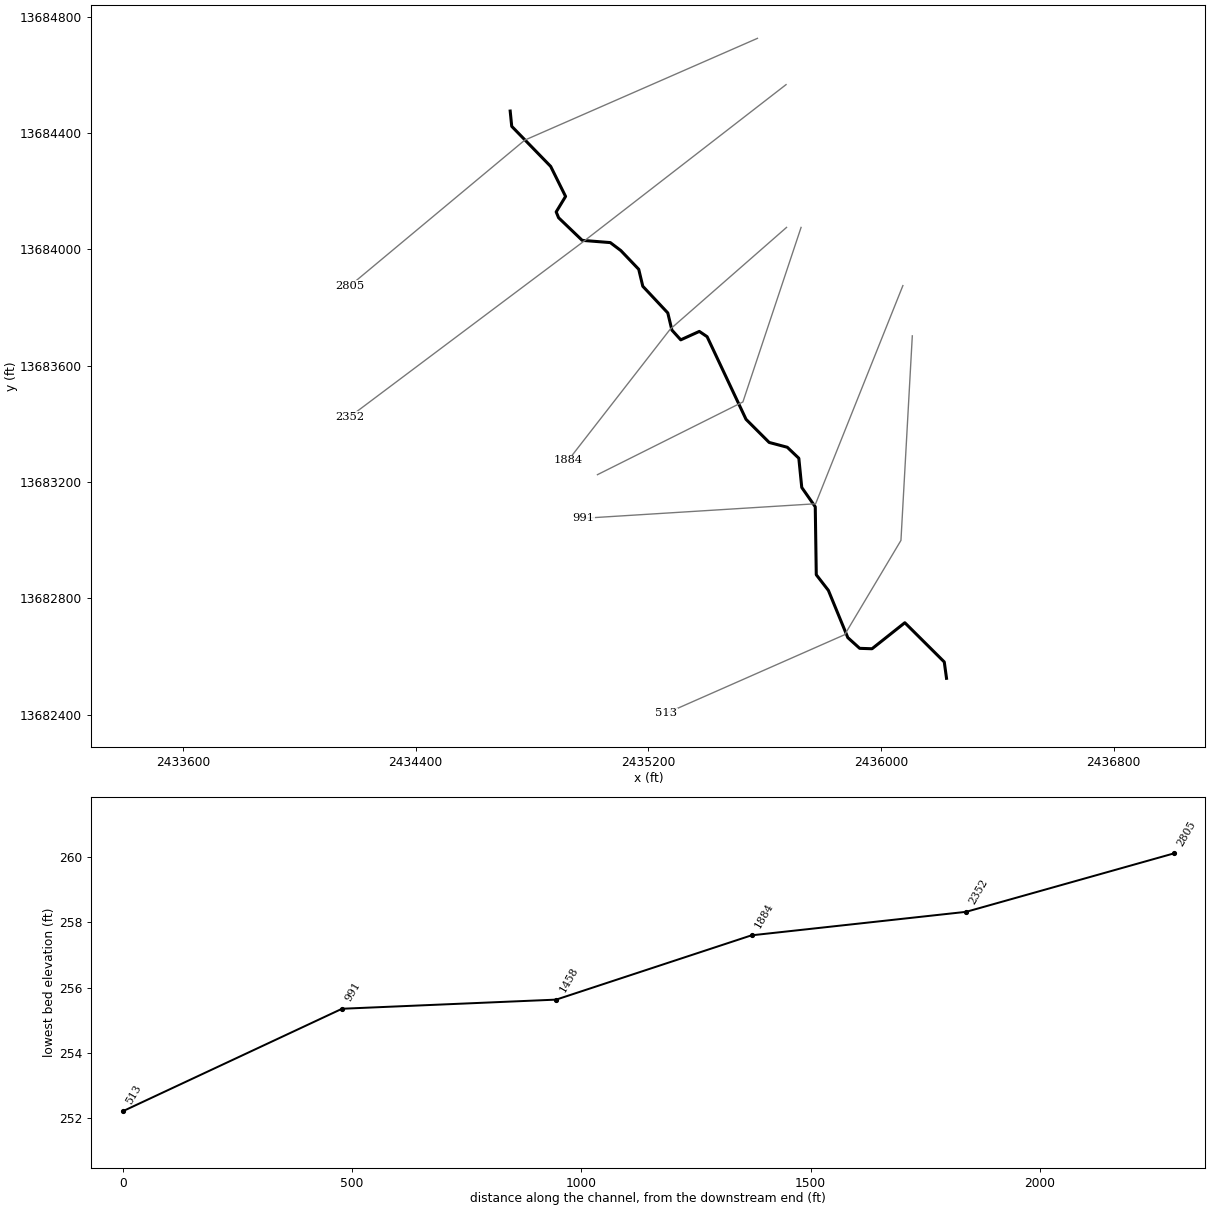
--- Stream0715.prj (project) ---

Proj Title=Stream0715 Base Level Engineering
Current Plan=p01
Default Exp/Contr=0.3,0.1
English Units
Geom File=g01
Flow File=f01
Plan File=p01
BEGIN DESCRIPTION:
Stream0715
END DESCRIPTION:

--- Stream0715.p01 (plan) ---

Plan Title=Multiple Run
Short Identifier=Multiple
Geom File=g01
Flow File=f01
Subcritical Flow
K Sum by GR= 0
Std Step Tol= 0.01
Critical Tol= 0.01
Num of Std Step Trials= 20
Max Error Tol= 0.3
Flow Tol Ratio= 0.001
Split Flow NTrial= 30
Split Flow Tol= 0.02
Split Flow Ratio= 0.02
Log Output Level= 0
Friction Slope Method= 1
Unsteady Friction Slope Method= 2
Unsteady Bridges Friction Slope Method= 1
Parabolic Critical Depth
Global Vel Dist=  1 , 1 , 1
Global Log Level= 0
CheckData=True
Encroach Param= -1, 0, 0, 0
BEGIN DESCRIPTION:
Multiple Run
END DESCRIPTION:

--- Stream0715.f01 (steady flow) ---

Flow Title=Multiple
Number of Profiles=7
Profile Names=10-year,25-year,50-year,1pct_min,100-year,1pct_plu,500-year
River Rch & RM= Stream0715,Reach-1,2805
     686    1106    1485     965    1925    3841    3205
Boundary for River Rch & Prof#=Stream0715,Reach-1,1
Up Type=0
Dn Type=3
Dn Slope=0.005
Boundary for River Rch & Prof#=Stream0715,Reach-1,2
Up Type=0
Dn Type=3
Dn Slope=0.005
Boundary for River Rch & Prof#=Stream0715,Reach-1,3
Up Type=0
Dn Type=3
Dn Slope=0.005
Boundary for River Rch & Prof#=Stream0715,Reach-1,4
Up Type=0
Dn Type=3
Dn Slope=0.005
Boundary for River Rch & Prof#=Stream0715,Reach-1,5
Up Type=0
Dn Type=3
Dn Slope=0.005
Boundary for River Rch & Prof#=Stream0715,Reach-1,6
Up Type=0
Dn Type=3
Dn Slope=0.005
Boundary for River Rch & Prof#=Stream0715,Reach-1,7
Up Type=0
Dn Type=3
Dn Slope=0.005

--- Stream0715.g01 (geometry) ---

Geom Title=Existing Conditions

River Reach=Stream0715,Reach-1
Reach XY= 30
      2434725.00     13684475.00      2434730.31     13684422.48
      2434864.25     13684284.68      2434915.41     13684181.55
      2434883.14     13684128.32      2434891.37     13684108.30
      2434972.54     13684030.52      2435069.12     13684022.85
      2435105.27     13683995.51      2435166.85     13683931.07
      2435180.87     13683872.72      2435266.82     13683781.00
      2435280.86     13683722.17      2435311.32     13683688.51
      2435375.20     13683717.52      2435401.99     13683699.36
      2435535.76     13683415.30      2435615.32     13683335.78
      2435677.57     13683319.26      2435717.26     13683281.45
      2435727.36     13683180.98      2435773.78     13683114.50
      2435777.24     13682880.93      2435818.88     13682827.18
      2435885.63     13682664.88      2435926.43     13682628.01
      2435968.91     13682626.58      2436081.67     13682716.04
      2436217.24     13682581.21      2436225.00     13682525.00

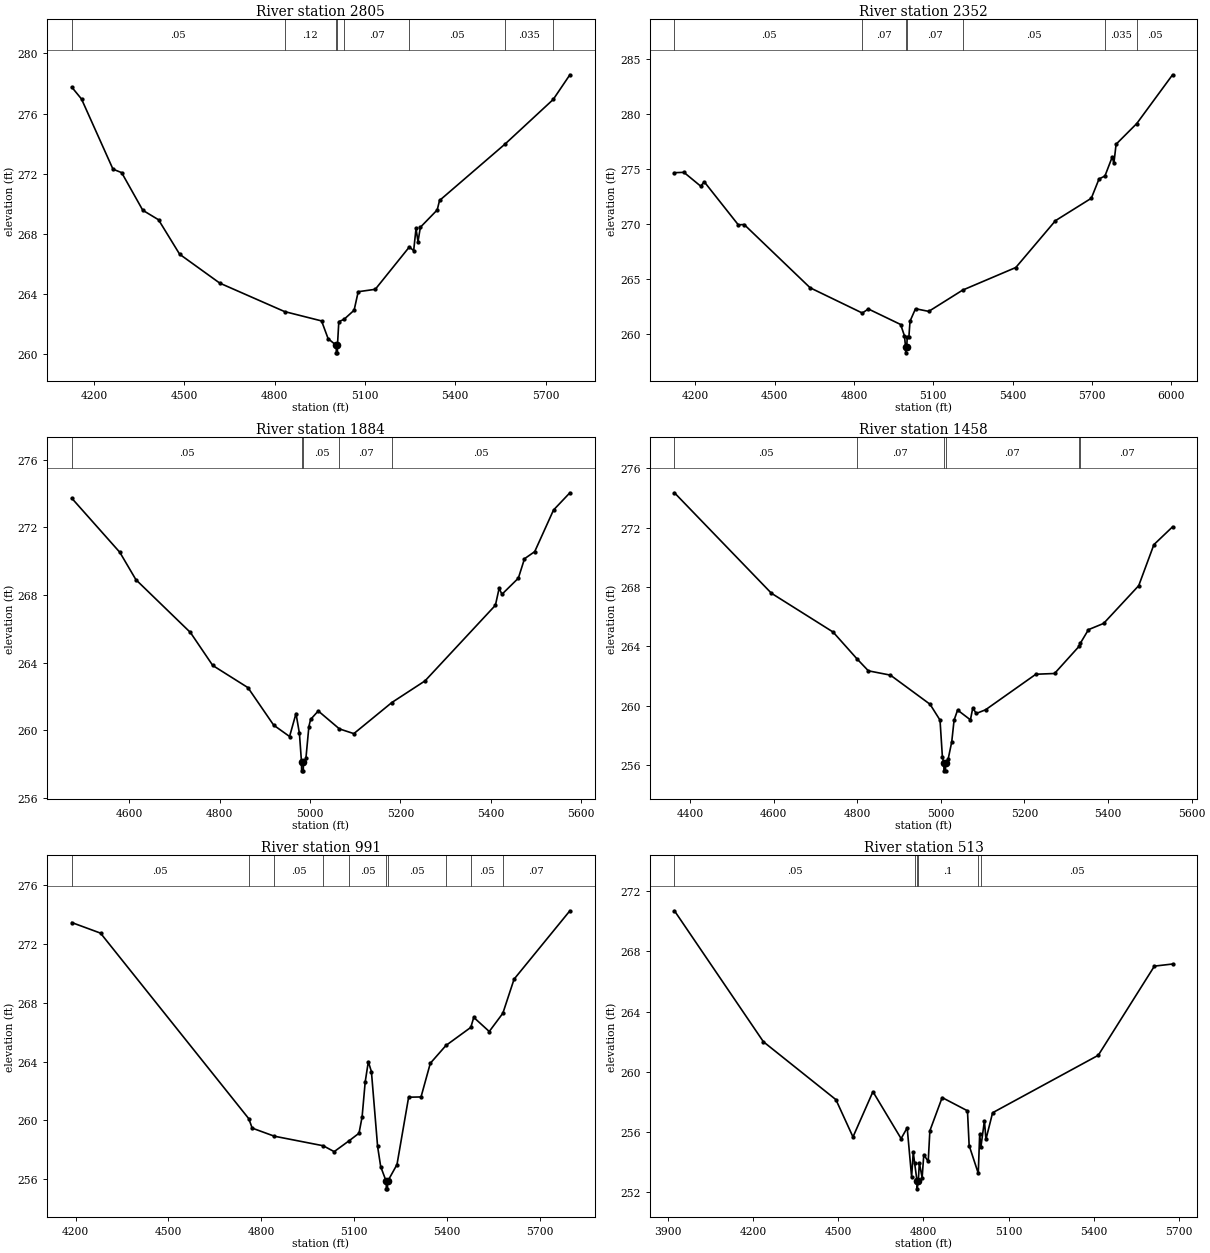
Type RM Length L Ch R = 1,2805,453,453,453
BEGIN DESCRIPTION:
Stream0715 6.0
END DESCRIPTION:
XS GIS Cut Line= 3
      2435575.02     13684725.01      2434775.00     13684375.00
      2434174.97     13683874.98
#Sta/Elev= 30
  4126.6  277.76  4159.0  276.97  4263.5  272.31  4292.3  272.08  4362.5  269.58
  4414.7  268.95  4484.9  266.66  4618.2  264.74  4833.5  262.85  4956.2  262.23
  4978.0  261.05  5004.9  260.61  5005.2  260.11  5008.8  260.11  5009.0  260.61
  5013.5  262.18  5031.1  262.34  5064.3  262.94  5077.9  264.17  5134.6  264.33
  5247.6  267.14  5262.1  266.90  5269.9  268.37  5276.5  267.49  5284.3  268.45
  5340.2  269.60  5348.0  270.23  5566.2  273.99  5725.5  276.94  5780.9  278.58
#Mann=8,-1,0
  4126.6    0.05       0  4833.5    0.12       0  5004.9    0.05       0
  5009.0    0.12       0  5031.1    0.07       0  5247.6    0.05       0
  5566.2   0.035       0  5725.5    0.05       0
Bank Sta=5004.9,5009
Exp/Cntr=0.3,0.1

Type RM Length L Ch R = 1,2352,468,468,468
BEGIN DESCRIPTION:
Stream0715 5.0
END DESCRIPTION:
XS GIS Cut Line= 3
      2435673.33     13684565.87      2434975.00     13684025.00
      2434174.99     13683424.99
#Sta/Elev= 30
  4121.4  274.66  4157.2  274.69  4220.5  273.44  4234.2  273.83  4362.8  269.93
  4384.9  269.96  4634.4  264.22  4831.7  261.93  4854.4  262.30  4976.6  260.89
  4991.1  259.85  4995.3  258.82  4995.6  258.32  4999.5  258.82  5001.5  259.77
  5007.8  259.77  5012.0  261.19  5032.8  262.32  5082.8  262.08  5211.0  264.01
  5412.0  266.06  5562.0  270.31  5697.4  272.34  5726.6  274.09  5749.0  274.36
  5776.6  276.09  5782.8  275.50  5791.1  277.24  5869.4  279.12  6004.7  283.54
#Mann=7,-1,0
  4121.4    0.05       0  4831.7    0.07       0  4995.3    0.05       0
  4999.5    0.07       0  5211.0    0.05       0  5749.0   0.035       0
  5869.4    0.05       0
Bank Sta=4995.3,4999.5
Exp/Cntr=0.3,0.1

Type RM Length L Ch R = 1,1884,426,426,426
BEGIN DESCRIPTION:
Stream0715 4.0
END DESCRIPTION:
XS GIS Cut Line= 3
      2435675.01     13684075.01      2435275.00     13683725.00
      2434925.00     13683275.00
#Sta/Elev= 30
  4473.0  273.72  4579.3  270.52  4614.9  268.90  4735.4  265.78  4784.8  263.83
  4862.6  262.52  4919.6  260.30  4954.7  259.63  4968.9  260.99  4976.5  259.81
  4981.1  258.10  4981.3  257.60  4985.0  257.60  4985.3  258.10  4990.8  258.33
  4997.4  260.22  5001.2  260.64  5018.1  261.14  5064.9  260.08  5096.8  259.80
  5180.9  261.64  5254.3  262.92  5409.9  267.39  5418.1  268.39  5424.4  268.04
  5460.6  268.99  5474.2  270.14  5496.8  270.56  5538.4  273.02  5574.6  274.04
#Mann=5,-1,0
  4473.0    0.05       0  4981.1    0.05       0  4985.3    0.05       0
  5064.9    0.07       0  5180.9    0.05       0
Bank Sta=4981.1,4985.3
Exp/Cntr=0.3,0.1

Type RM Length L Ch R = 1,1458,467,467,467
BEGIN DESCRIPTION:
Stream0715 3.0
END DESCRIPTION:
XS GIS Cut Line= 3
      2435724.99     13684074.98      2435525.00     13683475.00
      2435025.04     13683225.02
#Sta/Elev= 30
  4363.0  274.34  4594.9  267.58  4742.4  264.97  4799.1  263.18  4826.8  262.36
  4879.5  262.07  4974.3  260.11  4998.2  259.04  5003.8  256.59  5007.3  256.13
  5007.6  255.63  5011.3  255.63  5011.6  256.13  5017.8  256.44  5026.2  257.58
  5031.8  259.04  5040.2  259.72  5070.9  259.06  5076.5  259.86  5084.9  259.49
  5107.2  259.74  5227.4  262.13  5272.1  262.18  5330.8  264.01  5333.9  264.22
  5353.2  265.13  5389.5  265.55  5473.4  268.09  5509.7  270.85  5554.4  272.05
#Mann=6,-1,0
  4363.0    0.05       0  4799.1    0.07       0  5007.3    0.05       0
  5011.6    0.07       0  5330.8    0.05       0  5333.9    0.07       0
Bank Sta=5007.3,5011.6
Exp/Cntr=0.3,0.1

Type RM Length L Ch R = 1,991,478,478,478
BEGIN DESCRIPTION:
Stream0715 2.0
END DESCRIPTION:
XS GIS Cut Line= 3
      2436075.00     13683874.99      2435775.00     13683125.00
      2434975.03     13683075.00
#Sta/Elev= 30
  4187.8  273.46  4280.7  272.74  4759.7  260.12  4770.7  259.48  4842.2  258.93
  5000.1  258.28  5035.6  257.88  5084.5  258.63  5115.8  259.13  5125.8  260.24
  5135.8  262.62  5145.9  264.00  5155.9  263.32  5175.9  258.23  5185.9  256.86
  5203.8  255.85  5204.1  255.35  5207.8  255.35  5208.1  255.85  5238.5  257.00
  5276.1  261.58  5316.2  261.60  5346.2  263.89  5396.7  265.10  5477.0  266.33
  5486.5  267.01  5536.6  266.05  5580.5  267.29  5616.8  269.61  5797.1  274.26
#Mann=10,-1,0
  4187.8    0.05       0  4759.7    0.12       0  4842.2    0.05       0
  5000.1    0.07       0  5084.5    0.05       0  5203.8    0.05       0
  5208.1    0.05       0  5396.7    0.07       0  5477.0    0.05       0
  5580.5    0.07       0
Bank Sta=5203.8,5208.1
Exp/Cntr=0.3,0.1

Type RM Length L Ch R = 1,513,0,0,0
BEGIN DESCRIPTION:
Stream0715 1.0
END DESCRIPTION:
XS GIS Cut Line= 4
      2436107.38     13683702.18      2436068.32     13682999.05
      2435875.00     13682675.00      2435261.02     13682404.42
#Sta/Elev= 30
  3923.9  270.70  4236.9  261.99  4492.0  258.14  4552.0  255.66  4622.2  258.67
  4721.3  255.55  4742.7  256.27  4758.3  253.00  4764.1  254.66  4768.9  253.92
  4777.5  252.71  4777.8  252.21  4781.8  252.71  4785.5  253.94  4795.3  252.95
  4801.1  254.48  4816.7  254.03  4822.5  256.07  4865.7  258.28  4954.8  257.40
  4960.7  255.09  4992.8  253.24  4997.7  255.83  5002.2  255.01  5014.4  256.74
  5019.8  255.50  5043.2  257.27  5414.9  261.09  5612.5  267.02  5676.4  267.16
#Mann=6,-1,0
  3923.9    0.05       0  4768.9     0.1       0  4777.5    0.05       0
  4781.8     0.1       0  4992.8    0.07       0  5002.2    0.05       0
Bank Sta=4777.5,4781.8
Exp/Cntr=0.3,0.1

Chan Stop Cuts=-1