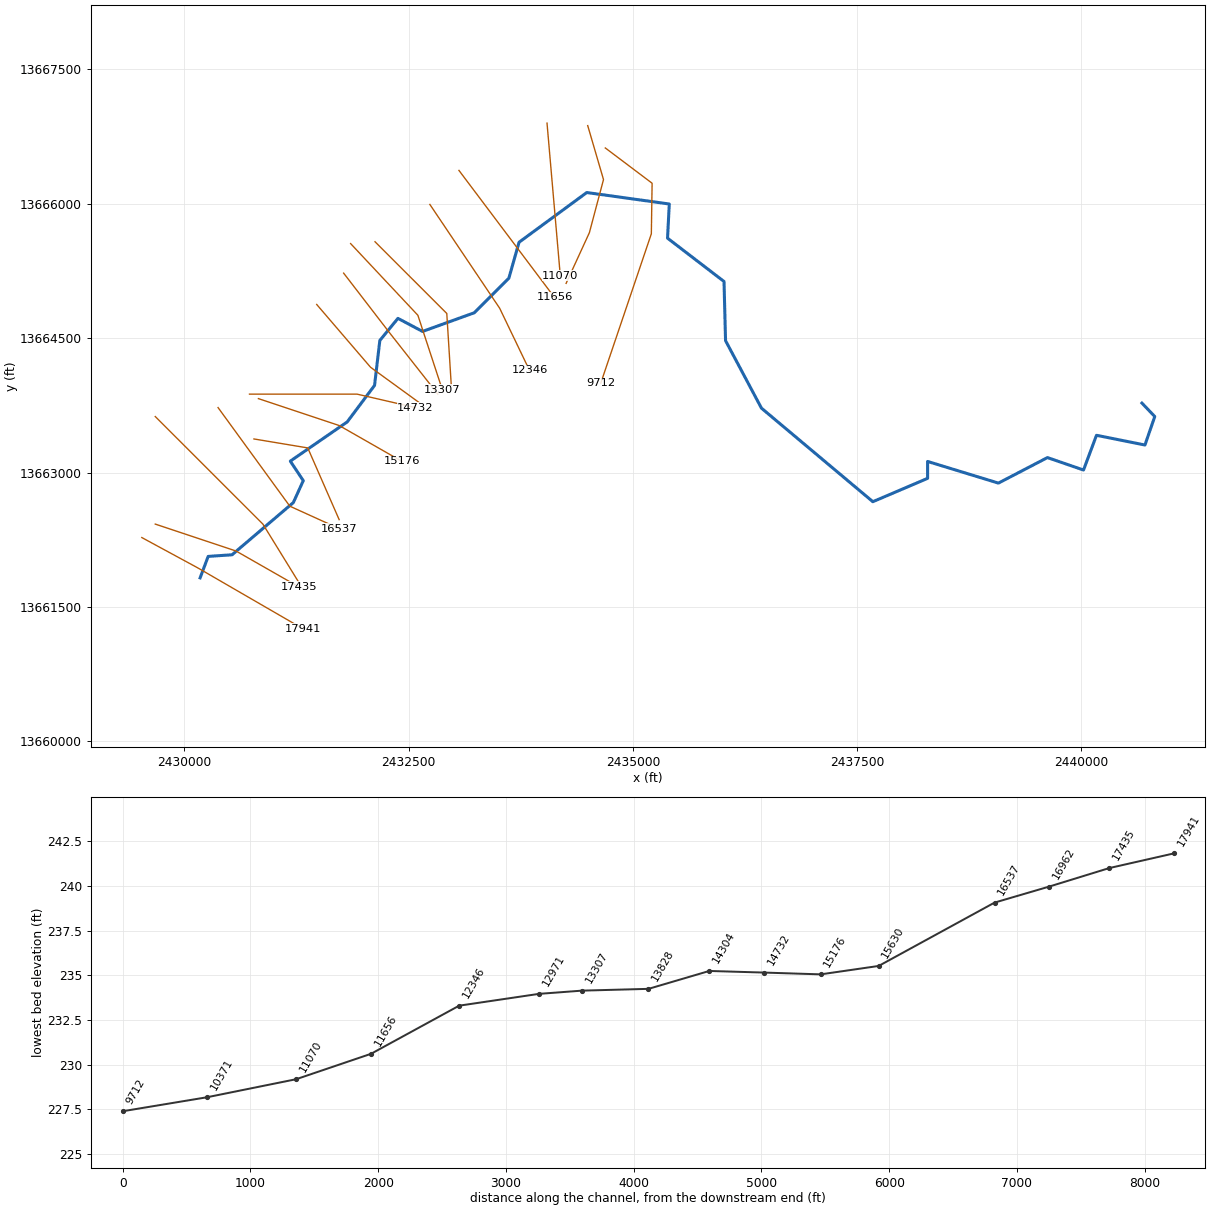
--- Stream0716.prj (project) ---

Proj Title=Stream0716 Base Level Engineering
Current Plan=p01
Default Exp/Contr=0.3,0.1
English Units
Geom File=g01
Flow File=f01
Plan File=p01
Y Axis Title=Elevation
X Axis Title(PF)=Main Channel Distance
X Axis Title(XS)=Station
BEGIN DESCRIPTION:
Stream0716
END DESCRIPTION:
DSS Export Rating Curves= 0
DSS Export Rating Curve Sorted= 0
DSS Export Volume Flow Curves= 0
DXF OffsetX= 0
DXF OffsetY= 0
DXF ScaleX= 1
DXF ScaleY= 10

--- Stream0716.p01 (plan) ---

Plan Title=Multiple Run
Short Identifier=Multiple
Geom File=g01
Flow File=f01
Subcritical Flow
K Sum by GR= 0
Std Step Tol= 0.01
Critical Tol= 0.01
Num of Std Step Trials= 20
Max Error Tol= 0.3
Flow Tol Ratio= 0.001
Split Flow NTrial= 30
Split Flow Tol= 0.02
Split Flow Ratio= 0.02
Log Output Level= 0
Friction Slope Method= 1
Unsteady Friction Slope Method= 2
Unsteady Bridges Friction Slope Method= 1
Parabolic Critical Depth
Global Vel Dist=  1 , 1 , 1
Global Log Level= 0
CheckData=True
Encroach Param= -1, 0, 0, 0
BEGIN DESCRIPTION:
Multiple Run
END DESCRIPTION:

--- Stream0716.f01 (steady flow) ---

Flow Title=Multiple
Number of Profiles=7
Profile Names=10-year,25-year,50-year,1pct_min,100-year,1pct_plu,500-year
River Rch & RM= Stream0716,Reach-1,17941
     621     995    1331     862    1720    3431    2844
River Rch & RM= Stream0716,Reach-1,16962
     815    1313    1762    1142    2278    4545    3776
River Rch & RM= Stream0716,Reach-1,10371
     979    1585    2132    1384    2761    5509    4593
Boundary for River Rch & Prof#=Stream0716,Reach-1,1
Up Type=0
Dn Type=3
Dn Slope=0.005
Boundary for River Rch & Prof#=Stream0716,Reach-1,2
Up Type=0
Dn Type=3
Dn Slope=0.005
Boundary for River Rch & Prof#=Stream0716,Reach-1,3
Up Type=0
Dn Type=3
Dn Slope=0.005
Boundary for River Rch & Prof#=Stream0716,Reach-1,4
Up Type=0
Dn Type=3
Dn Slope=0.005
Boundary for River Rch & Prof#=Stream0716,Reach-1,5
Up Type=0
Dn Type=3
Dn Slope=0.005
Boundary for River Rch & Prof#=Stream0716,Reach-1,6
Up Type=0
Dn Type=3
Dn Slope=0.005
Boundary for River Rch & Prof#=Stream0716,Reach-1,7
Up Type=0
Dn Type=3
Dn Slope=0.005

--- Stream0716.g01 (geometry) ---

Geom Title=Existing Conditions
Program Version=4.10

River Reach=Stream0716      ,Reach-1
Reach XY= 30
        2430175.       13661825.      2430264.88     13662064.66
      2430531.19     13662082.81      2431214.24     13662665.32
      2431325.11      13662909.8      2431180.45     13663127.44
      2431814.62     13663564.89      2432119.65      13663972.3
      2432178.54     13664473.53      2432380.61     13664720.23
      2432654.84     13664574.53      2433231.45     13664782.75
      2433617.24     13665168.83      2433730.62     13665569.38
      2434485.68     13666124.25      2435405.39      13665996.1
       2435386.1     13665614.94      2436015.71     13665131.69
      2436032.83      13664471.6      2436433.02     13663718.66
        2437675.       13662675.      2438285.56     13662935.48
      2438285.14     13663124.06        2439075.      13662882.5
      2439621.59     13663167.19      2440023.75     13663028.36
      2440168.25      13663415.9      2440708.61     13663307.36
      2440818.02     13663625.21        2440675.       13663775.

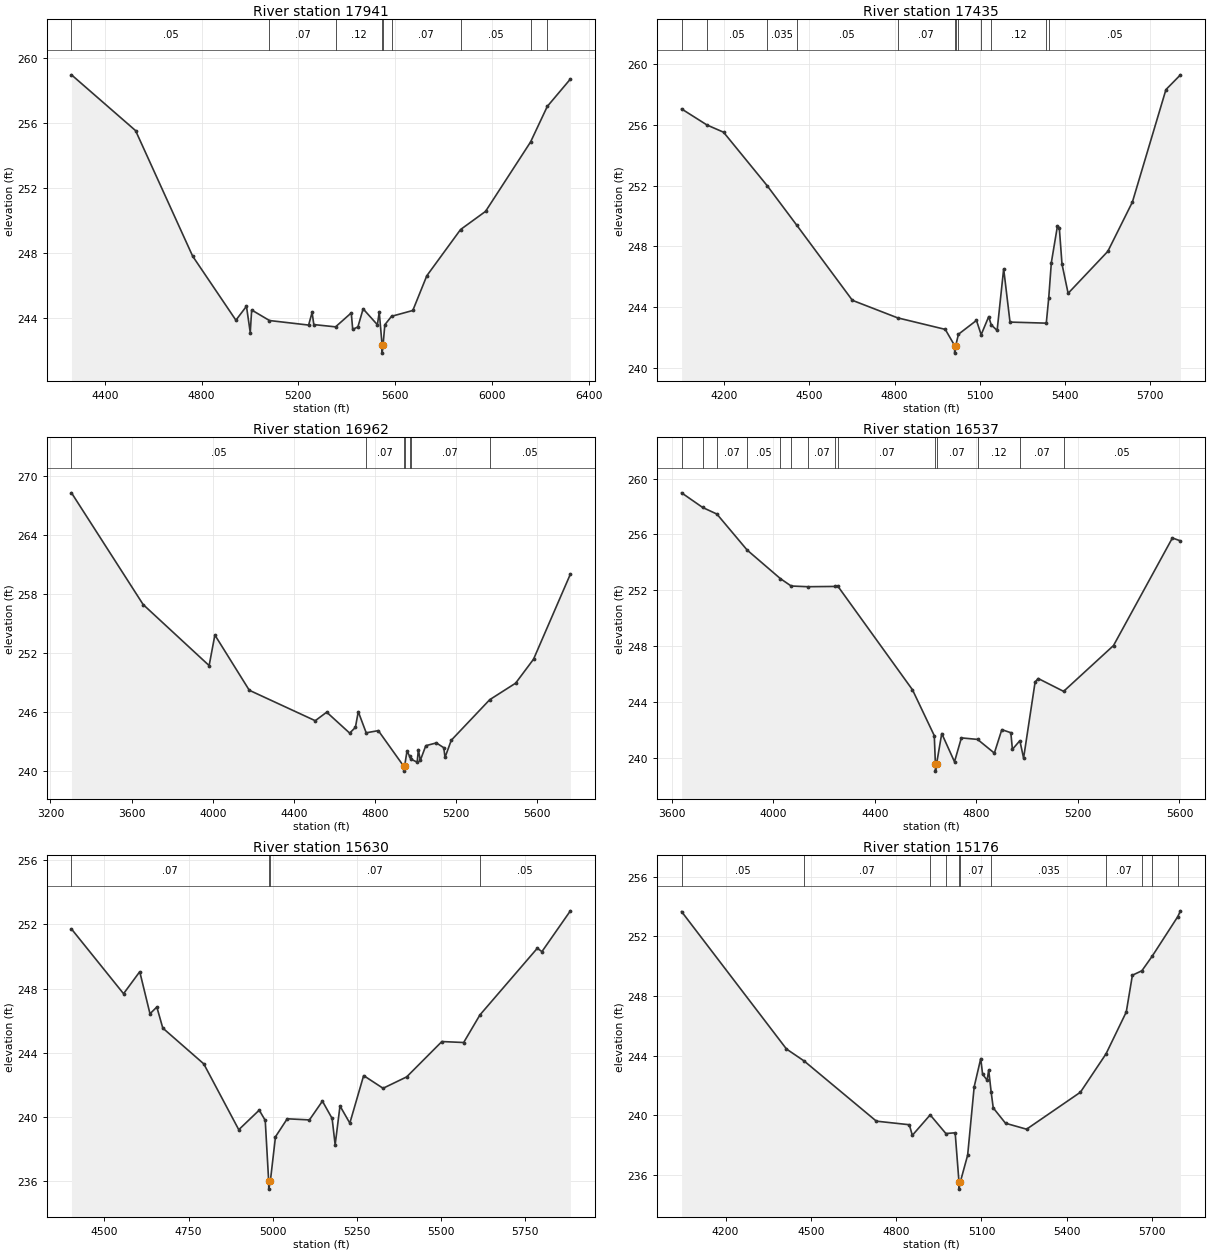
Type RM Length L Ch R = 1 ,17941   ,506,506,506
BEGIN DESCRIPTION:
Stream0716 24.0
END DESCRIPTION:
XS GIS Cut Line= 3
      2429524.98     13662275.01      2430152.66     13661934.59
       2431318.3     13661259.26
#Sta/Elev= 30
  4262.7  258.97  4527.5  255.53  4763.3  247.79    4942  243.84  4985.6   244.7
  5001.3  243.08  5007.1  244.47  5080.7  243.82  5242.4  243.54  5256.8  244.32
  5263.9  243.57  5353.7  243.43  5418.6  244.29  5424.6  243.27  5446.1  243.43
  5467.6  244.54  5526.5  243.56  5534.2  244.34    5546  242.31  5546.2  241.81
    5550  242.31  5557.3  243.56    5585  244.08  5672.9  244.44  5730.7  246.58
  5870.1  249.43  5973.4  250.55  6159.4  254.83  6228.4  257.02  6323.9  258.71
#Mann= 9 ,-1 , 0
  4262.7     .05       0  5080.7     .07       0  5353.7     .12       0
    5546     .05       0    5550     .12       0    5585     .07       0
  5870.1     .05       0  6159.4     .07       0  6228.4     .05       0
Bank Sta=5546,5550
XS Rating Curve= 0 ,0
Exp/Cntr=0.3,0.1

Type RM Length L Ch R = 1 ,17435   ,473,473,473
BEGIN DESCRIPTION:
Stream0716 23.0
END DESCRIPTION:
XS GIS Cut Line= 3
      2429674.97     13662425.01        2430575.       13662125.
      2431274.96     13661725.02
#Sta/Elev= 30
    4051  257.04  4140.7  255.98  4198.6  255.51  4351.9     252  4456.9  249.38
  4651.9  244.46  4810.7  243.31  4978.6  242.55  5011.4  241.49  5011.6  240.99
  5015.4  241.49  5024.9  242.23  5088.3  243.14  5104.8   242.2  5131.4  243.39
  5140.2  242.85    5161  242.48    5184  246.53  5206.3  243.03  5333.9  242.96
  5342.6  244.64  5351.7  246.94  5373.3  249.36  5379.8   249.2  5389.2  246.84
  5410.7  244.92  5550.4  247.68  5636.8  250.92  5754.8  258.31  5805.9  259.28
#Mann= 12 ,-1 , 0
    4051    .035       0  4140.7     .05       0  4351.9    .035       0
  4456.9     .05       0  4810.7     .07       0  5011.4     .05       0
  5015.4     .07       0  5024.9     .12       0  5104.8     .07       0
  5140.2     .12       0  5333.9     .07       0  5342.6     .05       0
Bank Sta=5011.4,5015.4
XS Rating Curve= 0 ,0
Exp/Cntr=0.3,0.1

Type RM Length L Ch R = 1 ,16962   ,425,425,425
BEGIN DESCRIPTION:
Stream0716 22.0
END DESCRIPTION:
XS GIS Cut Line= 3
      2429675.01     13663624.99        2430875.       13662425.
      2431275.02     13661774.97
#Sta/Elev= 30
  3303.6  268.27  3657.1   256.9  3982.4  250.69  4010.7   253.8  4180.4  248.18
  4505.7  245.08  4562.2  245.95  4675.4  243.82  4703.7   244.4  4717.8     246
  4756.9  243.85  4816.8  244.07  4941.9  240.45  4942.2  239.95  4946.3  240.45
  4958.2  241.99  4971.3  241.46  4976.4  241.18  5008.4  240.86  5014.2  242.14
  5023.8  241.04  5050.9  242.54    5103  242.82  5139.7  242.33  5145.6  241.34
  5176.4  243.09  5366.1  247.22  5493.8   248.9  5582.2  251.34  5763.9     260
#Mann= 7 ,-1 , 0
  3303.6     .05       0  4756.9     .07       0  4941.9     .05       0
  4946.3     .07       0  4971.3     .12       0  4976.4     .07       0
  5366.1     .05       0
Bank Sta=4941.9,4946.3
XS Rating Curve= 0 ,0
Exp/Cntr=0.3,0.1

Type RM Length L Ch R = 1 ,16537   ,907,907,907
BEGIN DESCRIPTION:
Stream0716 21.0
END DESCRIPTION:
XS GIS Cut Line= 3
      2430374.99     13663725.01        2431175.       13662625.
      2431724.99       13662375.
#Sta/Elev= 30
  3639.6  258.98  3722.8  257.93  3778.7  257.46    3898  254.88  4028.6  252.84
  4071.2  252.31  4136.6  252.26  4245.4  252.28  4253.6  252.33  4548.8  244.88
  4634.6   241.6    4639  239.56  4639.3  239.06  4643.4  239.56    4664  241.75
  4714.2  239.73  4741.3  241.44  4805.1  241.33  4871.1  240.35  4900.5  242.03
    4936  241.81  4942.2  240.62  4971.6  241.24  4986.2  239.99  5031.6  245.44
  5043.7  245.69  5143.8  244.77  5340.3  248.05  5572.1  255.75  5603.9  255.54
#Mann= 14 ,-1 , 0
  3639.6     .07       0  3722.8     .05       0  3778.7     .07       0
    3898     .05       0  4028.6     .07       0  4071.2     .05       0
  4136.6     .07       0  4245.4     .05       0  4253.6     .07       0
    4639     .05       0  4643.4     .07       0  4805.1     .12       0
  4971.6     .07       0  5143.8     .05       0
Bank Sta=4639,4643.4
XS Rating Curve= 0 ,0
Exp/Cntr=0.3,0.1

Type RM Length L Ch R = 1 ,15630   ,454,454,454
BEGIN DESCRIPTION:
Stream0716 20.0
END DESCRIPTION:
XS GIS Cut Line= 3
      2430775.05     13663374.99        2431375.       13663275.
      2431724.98     13662475.04
#Sta/Elev= 30
  4402.4  251.72    4557  247.69  4605.1  249.06  4635.5  246.44  4655.8  246.86
  4673.5  245.55  4795.2  243.32  4899.1  239.22  4959.9  240.44  4977.7   239.8
  4987.9  236.02  4988.2  235.52  4992.9  236.02  5008.1  238.78    5043   239.9
  5108.9  239.83  5147.5     241  5176.3  239.92  5185.3  238.28  5199.7   240.7
  5228.9  239.63  5269.9  242.59  5327.6   241.8  5397.7  242.51  5502.2  244.71
  5566.9  244.65  5615.3  246.37  5785.6  250.52  5799.3  250.31  5883.8  252.85
#Mann= 4 ,-1 , 0
  4402.4     .07       0  4987.9     .05       0  4992.9     .07       0
  5615.3     .05       0
Bank Sta=4987.9,4992.9
XS Rating Curve= 0 ,0
Exp/Cntr=0.3,0.1

Type RM Length L Ch R = 1 ,15176   ,444,444,444
BEGIN DESCRIPTION:
Stream0716 19.0
END DESCRIPTION:
XS GIS Cut Line= 3
      2430824.98     13663825.01        2431725.       13663525.
      2432424.97     13663125.02
#Sta/Elev= 30
  4045.2  253.67  4414.2  244.45  4476.1  243.65  4730.4  239.61  4846.3  239.37
  4856.9  238.66  4919.7  240.03  4974.9  238.78  5007.6  238.83  5020.9  235.55
  5021.2  235.05    5026  235.55  5051.5  237.33  5074.5  241.92  5097.6  243.81
    5104  242.76  5119.9  242.36  5125.6  243.04    5134  241.59  5141.5   240.5
  5184.7  239.47  5258.8  239.07  5448.1  241.55  5538.1  244.12  5609.4  246.93
    5631   249.4  5664.4   249.7  5701.1  250.69  5790.6  253.33  5800.1  253.72
#Mann= 11 ,-1 , 0
  4045.2     .05       0  4476.1     .07       0  4919.7     .12       0
  4974.9     .07       0  5020.9     .05       0    5026     .07       0
    5134    .035       0  5538.1     .07       0  5664.4    .035       0
  5701.1     .07       0  5790.6     .05       0
Bank Sta=5020.9,5026
XS Rating Curve= 0 ,0
Exp/Cntr=0.3,0.1

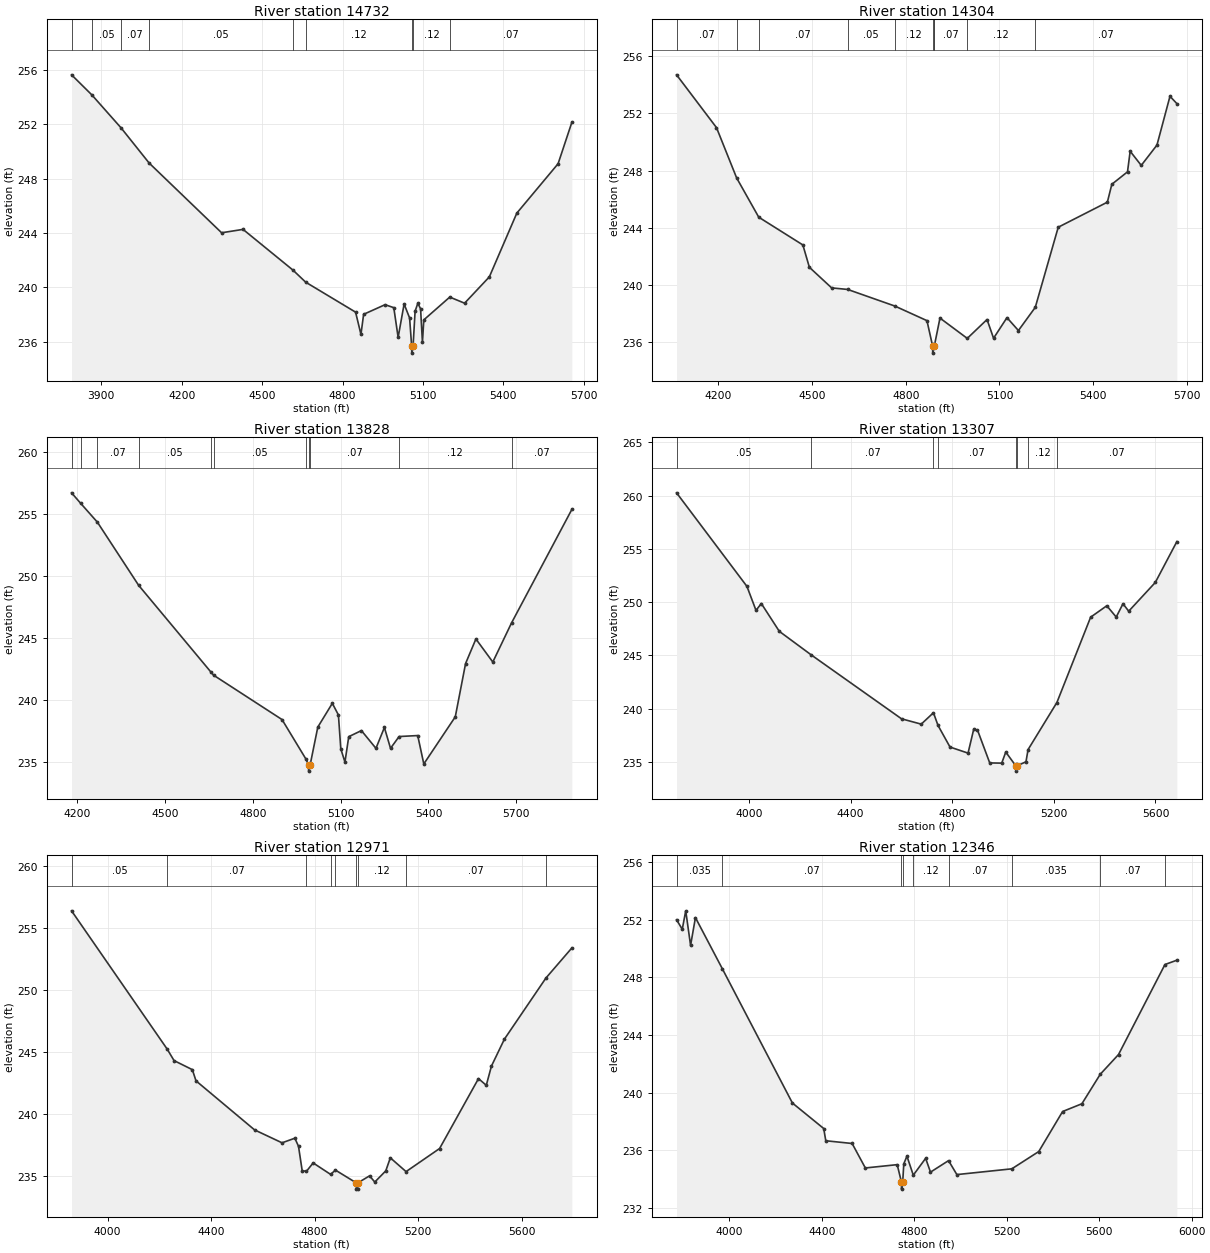
Type RM Length L Ch R = 1 ,14732   ,428,428,428
BEGIN DESCRIPTION:
Stream0716 18.0
END DESCRIPTION:
XS GIS Cut Line= 3
      2430724.99       13663875.        2431925.       13663875.
        2432575.       13663725.
#Sta/Elev= 30
  3788.8  255.66  3864.6  254.18  3973.6  251.75  4078.3  249.16  4348.8  244.02
  4428.8  244.27    4615  241.27  4662.5  240.38  4848.8  238.17  4868.8  236.53
  4878.8  238.01  4958.8  238.72  4991.4   238.5  5007.6  236.31  5029.9  238.77
  5050.4  237.74  5058.1  235.65  5058.5  235.15  5063.3  235.65  5070.9  238.24
  5081.2  238.83  5091.4  238.41  5098.3  235.95  5103.4   237.6  5200.3  239.28
  5255.6  238.83    5348  240.77  5450.6  245.47  5604.6  249.11  5655.9  252.16
#Mann= 9 ,-1 , 0
  3788.8     .07       0  3864.6     .05       0  3973.6     .07       0
  4078.3     .05       0    4615     .07       0  4662.5     .12       0
  5058.1     .05       0  5063.3     .12       0  5200.3     .07       0
Bank Sta=5058.1,5063.3
XS Rating Curve= 0 ,0
Exp/Cntr=0.3,0.1

Type RM Length L Ch R = 1 ,14304   ,476,476,476
BEGIN DESCRIPTION:
Stream0716 17.0
END DESCRIPTION:
XS GIS Cut Line= 3
        2431475.       13664875.        2432075.       13664175.
      2432624.98     13663775.02
#Sta/Elev= 30
    4066  254.69  4193.9     251  4258.5  247.48  4329.2  244.74  4470.5   242.8
  4491.3  241.24  4562.6   239.8  4614.1  239.69    4765  238.53  4867.8  237.51
  4885.9  235.74  4886.3  235.24  4891.3  235.74  4891.6  235.76  4909.5  237.69
  4996.9  236.27  5060.2  237.59  5081.1  236.28    5124  237.72  5160.7  236.82
  5214.7  238.44  5288.2  244.04  5445.5  245.79  5459.8  247.04    5510  247.91
  5518.5  249.35    5554  248.36  5604.3  249.78    5646  253.19    5668  252.68
#Mann= 10 ,-1 , 0
    4066     .07       0  4258.5     .05       0  4329.2     .07       0
  4614.1     .05       0    4765     .12       0  4885.9     .05       0
  4891.3     .12       0  4891.6     .07       0  4996.9     .12       0
  5214.7     .07       0
Bank Sta=4885.9,4891.3
XS Rating Curve= 0 ,0
Exp/Cntr=0.3,0.1

Type RM Length L Ch R = 1 ,13828   ,521,521,521
BEGIN DESCRIPTION:
Stream0716 16.0
END DESCRIPTION:
XS GIS Cut Line= 3
      2431774.97     13665225.04        2432275.       13664575.
      2432824.98     13663875.03
#Sta/Elev= 30
  4179.9  256.69  4210.8  255.85  4268.3  254.32  4409.2  249.23  4657.1  242.21
  4665.4  241.98  4899.4   238.4  4981.5   235.2    4990  234.74  4990.5  234.24
  4995.5  234.74  5021.7  237.79  5071.4  239.71  5092.2  238.77  5100.3  236.04
  5114.5  234.97  5127.5  237.02  5170.8  237.51  5220.5  236.08  5249.4  237.76
  5270.3  236.08  5299.6  237.03  5363.3  237.11  5384.1  234.82  5491.7  238.62
  5526.9  242.92  5562.2   244.9    5620  243.04  5683.9  246.19  5890.2  255.35
#Mann= 11 ,-1 , 0
  4179.9     .07       0  4210.8     .05       0  4268.3     .07       0
  4409.2     .05       0  4657.1     .07       0  4665.4     .05       0
  4981.5     .07       0    4990     .05       0  4995.5     .07       0
  5299.6     .12       0  5683.9     .07       0
Bank Sta=4990,4995.5
XS Rating Curve= 0 ,0
Exp/Cntr=0.3,0.1

Type RM Length L Ch R = 1 ,13307   ,336,336,336
BEGIN DESCRIPTION:
Stream0716 15.0
END DESCRIPTION:
XS GIS Cut Line= 3
      2431852.77     13665554.67      2432602.78     13664754.66
      2432875.01     13663924.98
#Sta/Elev= 30
  3714.5  260.26  3991.6  251.48  4027.3  249.23  4048.3  249.87  4119.1  247.26
  4244.7  245.05  4600.3  239.05  4677.9  238.55    4726  239.62  4743.9  238.43
  4791.2   236.4  4862.2  235.83  4884.4  238.06  4899.3     238  4947.6  234.91
  4994.8  234.89  5010.7  235.93  5050.1  234.64  5050.5  234.14  5055.6  234.64
  5090.3  235.02  5098.5  236.16    5212  240.58  5344.9  248.59  5408.5  249.66
  5445.6   248.6  5472.2  249.85  5494.8  249.15  5599.5  251.85  5684.3  255.68
#Mann= 8 ,-1 , 0
  3714.5     .05       0  4244.7     .07       0    4726     .05       0
  4743.9     .07       0  5050.1     .05       0  5055.6     .07       0
  5098.5     .12       0    5212     .07       0
Bank Sta=5050.1,5055.6
XS Rating Curve= 0 ,0
Exp/Cntr=0.3,0.1

Type RM Length L Ch R = 1 ,12971   ,625,625,625
BEGIN DESCRIPTION:
Stream0716 14.0
END DESCRIPTION:
XS GIS Cut Line= 3
        2432125.       13665575.        2432925.       13664775.
        2432975.     13663975.04
#Sta/Elev= 30
    3861  256.37  4230.6  245.23    4257  244.31  4327.7  243.58  4341.8  242.68
  4568.1  238.73  4674.2  237.69  4723.7  238.06  4737.8  237.41    4752  235.45
  4768.3  235.39  4794.4  236.07  4861.6  235.15  4880.7  235.49  4961.3  234.46
  4961.7  233.96  4966.4  233.96  4966.8  234.46  5012.4  235.03  5032.5  234.53
    5075  235.43  5092.6  236.48  5153.4  235.37  5282.9  237.23  5433.2  242.86
  5463.3  242.32  5483.3  243.87  5533.4  246.04  5693.8  250.96  5793.9  253.38
#Mann= 9 ,-1 , 0
    3861     .05       0  4230.6     .07       0  4768.3     .12       0
  4861.6     .07       0  4880.7     .12       0  4961.3     .05       0
  4966.8     .12       0  5153.4     .07       0  5693.8     .05       0
Bank Sta=4961.3,4966.8
XS Rating Curve= 0 ,0
Exp/Cntr=0.3,0.1

Type RM Length L Ch R = 1 ,12346   ,690,690,690
BEGIN DESCRIPTION:
XS7533
END DESCRIPTION:
XS GIS Cut Line= 3
      2432736.56     13665991.06      2433514.52     13664833.38
      2433847.64     13664139.38
#Sta/Elev= 30
  3771.5  252.01  3796.2  251.35  3811.2  252.63  3832.2  250.23  3853.2  252.16
  3969.8   248.6  4272.8  239.28  4408.2  237.51  4417.2  236.66  4531.2  236.47
  4588.3  234.77  4726.2     235  4744.4   233.8  4744.9   233.3    4750   233.8
  4754.7  235.06  4768.3  235.59  4795.8  234.27  4849.2  235.44  4870.2  234.48
  4948.3  235.28  4984.3  234.31  5222.1  234.71  5338.6  235.91  5441.8  238.69
  5525.3  239.23  5604.8  241.28  5683.8  242.65  5884.6   248.9  5936.1   249.2
#Mann= 9 ,-1 , 0
  3771.5    .035       0  3969.8     .07       0  4744.4     .05       0
    4750     .07       0  4795.8     .12       0  4948.3     .07       0
  5222.1    .035       0  5604.8     .07       0  5884.6    .035       0
Bank Sta=4744.4,4750
XS Rating Curve= 0 ,0
Exp/Cntr=0.3,0.1

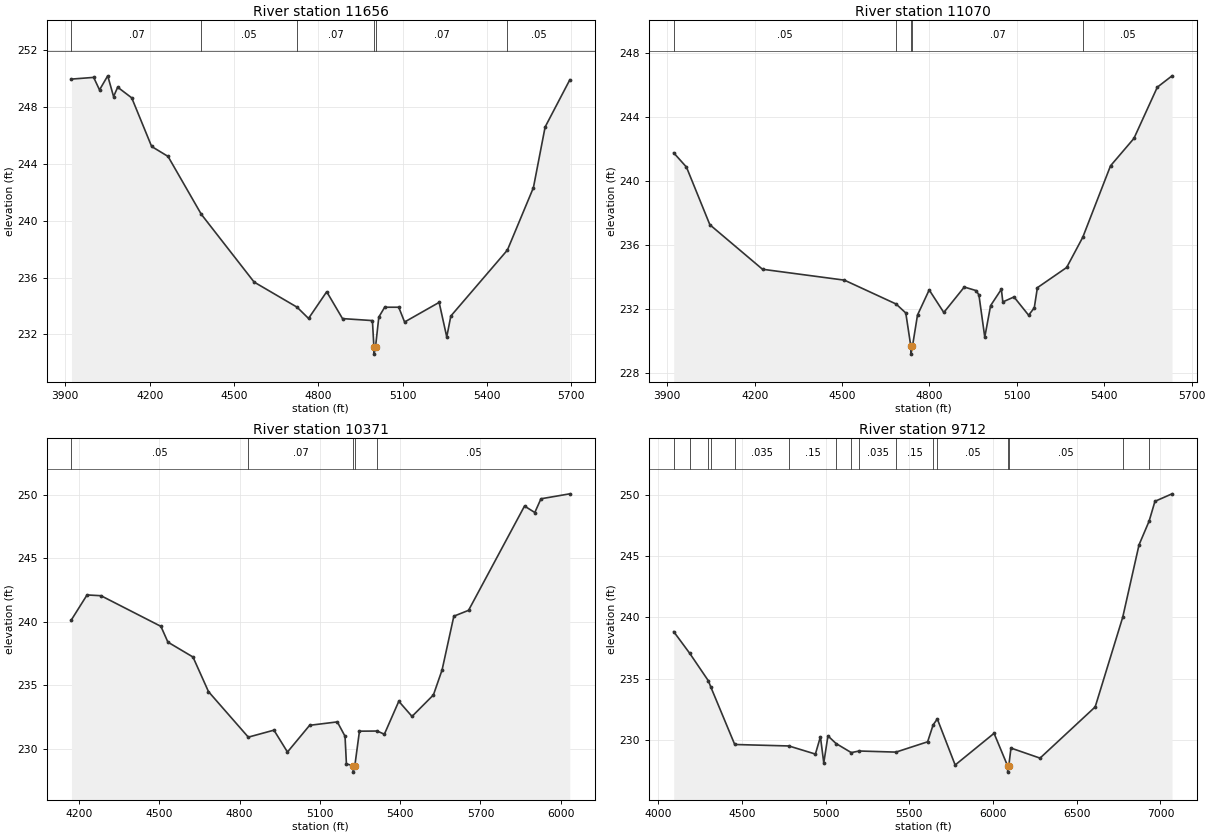
Type RM Length L Ch R = 1 ,11656   ,586,586,586
BEGIN DESCRIPTION:
XS7532
END DESCRIPTION:
XS GIS Cut Line= 2
      2433060.73     13666370.74      2434125.77     13664953.77
#Sta/Elev= 30
  3921.8  249.96  4000.8  250.08  4021.6   249.2  4050.8  250.19  4071.6  248.73
  4086.2  249.39  4136.2  248.64    4207  245.22  4265.3  244.52  4383.6  240.45
  4571.5  235.68  4724.5  233.91  4765.1  233.12  4829.7     235  4885.9  233.11
  4992.3  232.97  4997.6  231.11  4998.1  230.61  5003.3  231.11  5015.1  233.22
  5035.9  233.91  5085.9  233.91  5106.7  232.87  5229.6  234.25  5256.7  231.82
  5271.2  233.29  5472.4  237.93  5564.9  242.32  5606.6  246.59  5694.4  249.91
#Mann= 6 ,-1 , 0
  3921.8     .07       0  4383.6     .05       0  4724.5     .07       0
  4997.6     .05       0  5003.3     .07       0  5472.4     .05       0
Bank Sta=4997.6,5003.3
XS Rating Curve= 0 ,0
Exp/Cntr=0.3,0.1

Type RM Length L Ch R = 1 ,11070   ,699,699,699
BEGIN DESCRIPTION:
XS7531
END DESCRIPTION:
XS GIS Cut Line= 2
      2434042.42     13666898.65       2434190.6     13665194.58
#Sta/Elev= 30
  3922.2  241.76    3966  240.87  4046.3  237.27    4227  234.49  4508.1  233.81
  4685.5  232.32  4718.8  231.76    4736  229.69  4736.5  229.19  4741.8  229.69
    4759  231.63  4799.1   233.2  4849.3  231.79  4919.6  233.38  4959.8  233.16
  4969.8  232.89  4989.9  230.25  5009.9  232.22  5046.8  233.24  5051.9  232.45
  5090.2  232.76  5140.4  231.62  5159.8  232.08  5170.5  233.34  5270.9   234.6
  5326.3  236.49  5421.5  240.95  5501.8  242.66  5582.1  245.86  5632.7  246.57
#Mann= 5 ,-1 , 0
  3922.2     .05       0  4685.5     .07       0    4736     .05       0
  4741.8     .07       0  5326.3     .05       0
Bank Sta=4736,4741.8
XS Rating Curve= 0 ,0
Exp/Cntr=0.3,0.1

Type RM Length L Ch R = 1 ,10371   ,659,659,659
BEGIN DESCRIPTION:
XS7530
END DESCRIPTION:
XS GIS Cut Line= 4
      2434496.22     13666870.89      2434672.19     13666268.88
      2434514.75     13665676.16      2434255.42     13665111.21
#Sta/Elev= 30
  4171.7  240.16  4229.9  242.11    4282  242.05    4506  239.64  4532.1   238.4
  4625.8  237.23  4683.7  234.51  4832.5  230.93  4928.3  231.48  4978.8  229.76
  5061.6  231.86  5165.1  232.13  5193.9     231  5199.1  228.83  5223.8  228.68
  5224.3  228.18  5230.5  228.68  5247.8   231.4    5314  231.41  5340.9  231.16
  5394.8  233.75  5444.2  232.56  5524.2  234.25  5556.5  236.21  5600.5  240.44
  5655.5   240.9  5864.6   249.1    5903  248.59    5926  249.67  6033.8  250.06
#Mann= 5 ,-1 , 0
  4171.7     .05       0  4832.5     .07       0  5223.8     .05       0
  5230.5     .07       0    5314     .05       0
Bank Sta=5223.8,5230.5
XS Rating Curve= 0 ,0
Exp/Cntr=0.3,0.1

Type RM Length L Ch R = 1 ,9712    ,0,0,0
BEGIN DESCRIPTION:
E21289
END DESCRIPTION:
XS GIS Cut Line= 4
      2434692.56      13666621.2      2435214.06     13666227.95
      2435205.51      13665663.7      2434641.82     13663998.27
#Sta/Elev= 30
  4093.4  238.84  4189.3  237.07  4300.2  234.84  4315.3  234.32  4457.8  229.65
  4781.2  229.53  4939.5  228.87  4969.5  230.28  4989.5  228.15  5014.4  230.35
  5062.8  229.73  5153.7  228.99  5201.1  229.12  5420.5  229.03  5609.6  229.87
  5642.6  231.25  5667.5  231.73    5774  227.98  6006.3  230.56  6087.4   227.9
  6087.9   227.4  6094.1   227.9  6107.2  229.36  6280.8  228.54  6610.1  232.71
  6774.5  240.01    6872  245.91  6932.2  247.84    6967  249.45  7069.1  250.06
#Mann= 16 ,-1 , 0
  4093.4    .035       0  4189.3     .05       0  4300.2    .035       0
  4315.3     .05       0  4457.8    .035       0  4781.2     .15       0
  5062.8     .07       0  5153.7     .15       0  5201.1    .035       0
  5420.5     .15       0  5642.6     .07       0  5667.5     .05       0
  6087.4     .05       0  6094.1     .05       0  6774.5    .035       0
  6932.2     .07       0
Bank Sta=6087.4,6094.1
XS Rating Curve= 0 ,0
Exp/Cntr=0.3,0.1

Chan Stop Cuts=-1
Use User Specified Reach Order=0
Composite Channel Slope=5