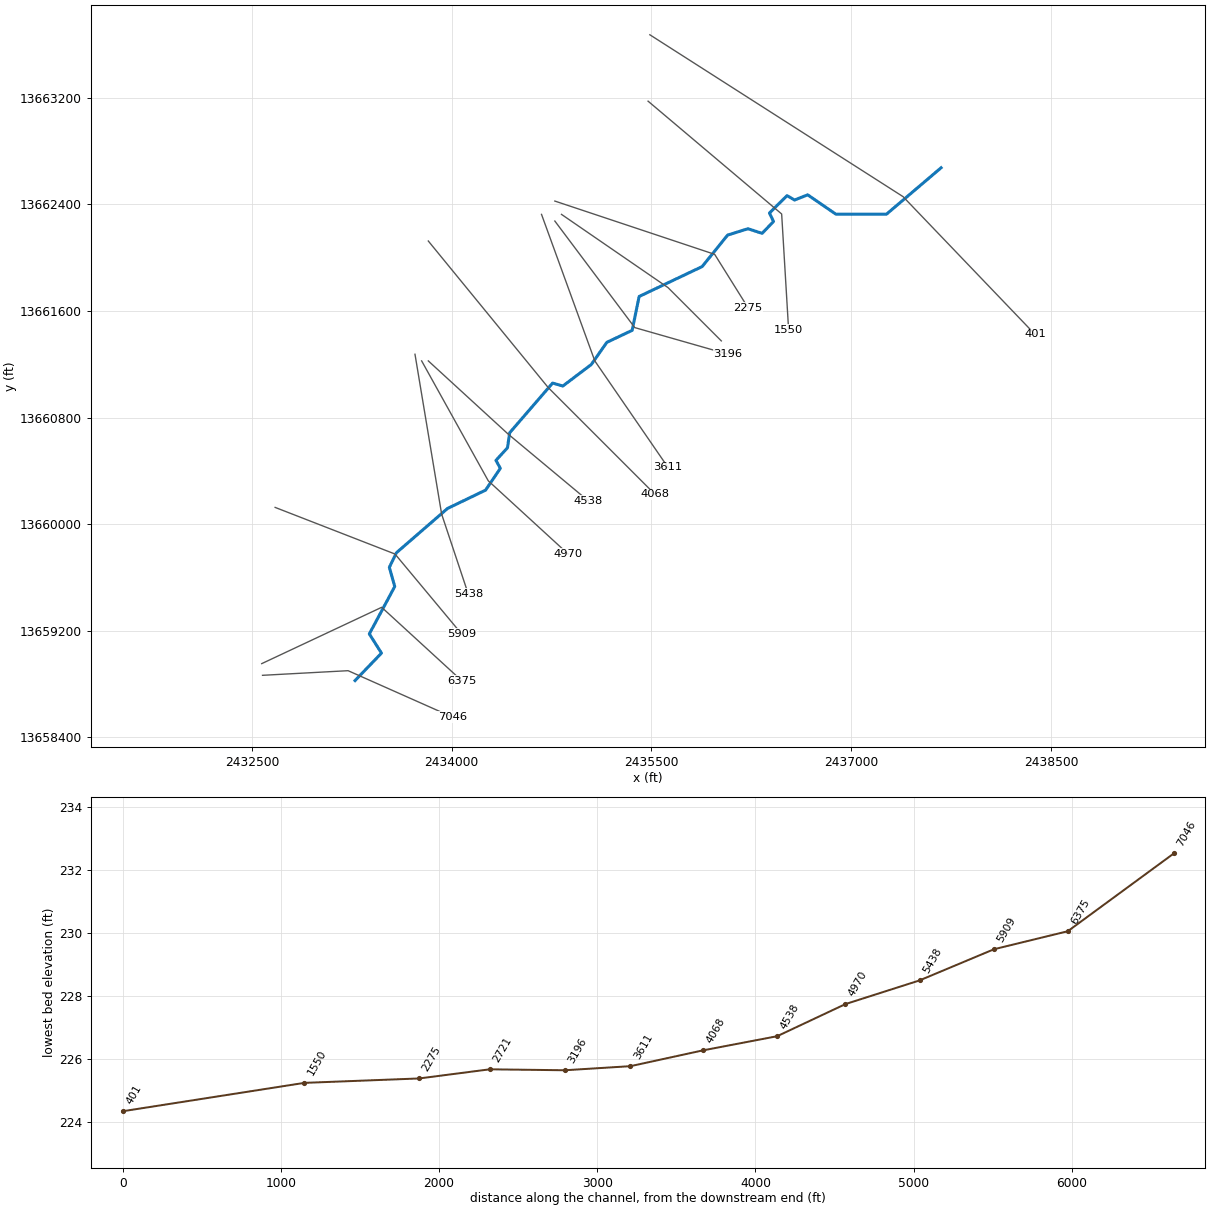
--- Stream0717.prj (project) ---

Proj Title=Stream0717 Base Level Engineering
Current Plan=p01
Default Exp/Contr=0.3,0.1
English Units
Geom File=g01
Flow File=f01
Plan File=p01
BEGIN DESCRIPTION:
Stream0717
END DESCRIPTION:

--- Stream0717.p01 (plan) ---

Plan Title=Multiple Run
Short Identifier=Multiple
Geom File=g01
Flow File=f01
Subcritical Flow
K Sum by GR= 0
Std Step Tol= 0.01
Critical Tol= 0.01
Num of Std Step Trials= 20
Max Error Tol= 0.3
Flow Tol Ratio= 0.001
Split Flow NTrial= 30
Split Flow Tol= 0.02
Split Flow Ratio= 0.02
Log Output Level= 0
Friction Slope Method= 1
Unsteady Friction Slope Method= 2
Unsteady Bridges Friction Slope Method= 1
Parabolic Critical Depth
Global Vel Dist=  1 , 1 , 1
Global Log Level= 0
CheckData=True
Encroach Param= -1, 0, 0, 0
BEGIN DESCRIPTION:
Multiple Run
END DESCRIPTION:

--- Stream0717.f01 (steady flow) ---

Flow Title=Multiple
Number of Profiles=7
Profile Names=10-year,25-year,50-year,1pct_min,100-year,1pct_plu,500-year
River Rch & RM= Stream0717,Reach-1,7046
     569     904    1200     771    1539    3070    2507
River Rch & RM= Stream0717,Reach-1,4068
     709    1132    1509     973    1941    3872    3179
Boundary for River Rch & Prof#=Stream0717,Reach-1,1
Up Type=0
Dn Type=3
Dn Slope=0.005
Boundary for River Rch & Prof#=Stream0717,Reach-1,2
Up Type=0
Dn Type=3
Dn Slope=0.005
Boundary for River Rch & Prof#=Stream0717,Reach-1,3
Up Type=0
Dn Type=3
Dn Slope=0.005
Boundary for River Rch & Prof#=Stream0717,Reach-1,4
Up Type=0
Dn Type=3
Dn Slope=0.005
Boundary for River Rch & Prof#=Stream0717,Reach-1,5
Up Type=0
Dn Type=3
Dn Slope=0.005
Boundary for River Rch & Prof#=Stream0717,Reach-1,6
Up Type=0
Dn Type=3
Dn Slope=0.005
Boundary for River Rch & Prof#=Stream0717,Reach-1,7
Up Type=0
Dn Type=3
Dn Slope=0.005

--- Stream0717.g01 (geometry) ---

Geom Title=Existing Conditions

River Reach=Stream0717,Reach-1
Reach XY= 30
      2433275.00     13658825.00      2433473.42     13659031.05
      2433382.11     13659175.00      2433573.02     13659530.90
      2433532.53     13659675.01      2433585.74     13659784.70
      2433968.94     13660116.86      2434255.23     13660254.87
      2434365.68     13660418.34      2434333.02     13660478.33
      2434419.45     13660572.57      2434435.52     13660684.79
      2434758.30     13661058.62      2434835.00     13661036.24
      2435048.84     13661197.86      2435165.30     13661364.24
      2435355.56     13661454.45      2435407.86     13661708.55
      2435881.05     13661933.16      2436072.33     13662169.58
      2436225.01     13662217.41      2436331.09     13662182.50
      2436417.00     13662271.65      2436386.24     13662335.00
      2436518.33     13662465.70      2436574.91     13662432.84
      2436673.35     13662471.83      2436885.50     13662326.20
      2437264.50     13662326.20      2437675.00     13662675.00

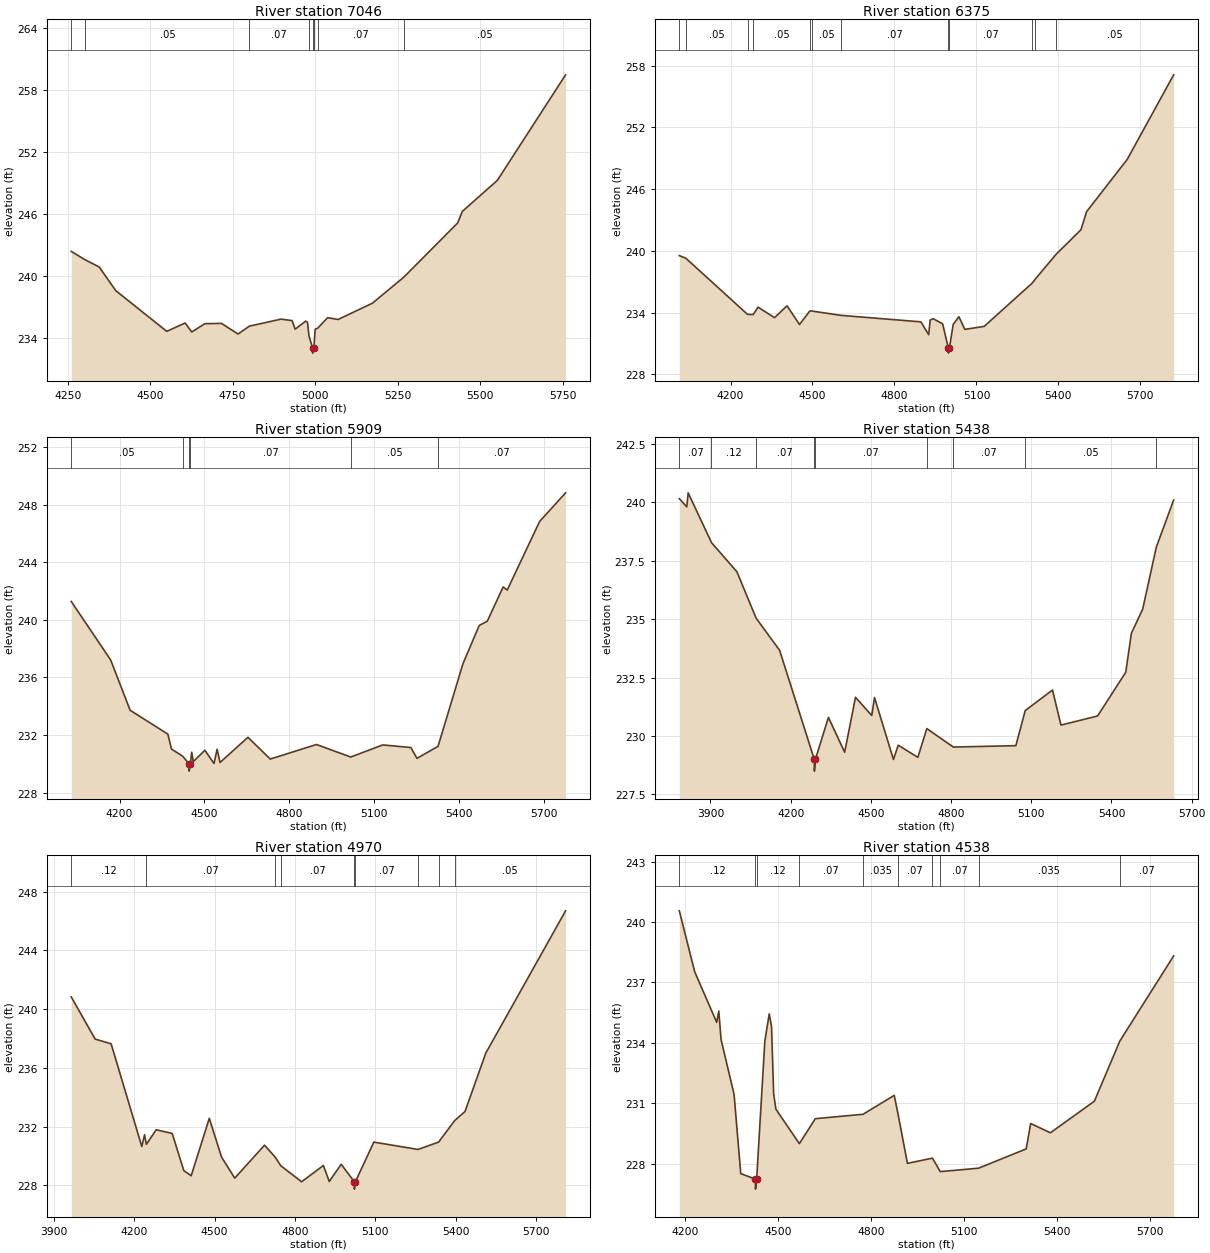
Type RM Length L Ch R = 1,7046,671,671,671
BEGIN DESCRIPTION:
XS7535
END DESCRIPTION:
XS GIS Cut Line= 3
      2432580.35     13658864.41      2433222.74     13658899.13
      2434004.02     13658551.90
#Sta/Elev= 30
  4260.9  242.38  4303.5  241.56  4345.7  240.87  4395.8  238.58  4550.4  234.64
  4606.1  235.45  4626.1  234.58  4666.1  235.38  4716.2  235.41  4766.3  234.38
  4800.6  235.14  4896.5  235.82  4930.4  235.68  4939.5  234.85  4971.4  235.63
  4976.9  235.52  4981.5  234.19  4992.3  233.03  4992.5  232.53  4996.3  233.03
  5000.2  234.84  5007.6  234.94  5038.0  235.96  5069.9  235.79  5173.9  237.37
  5268.6  239.88  5432.0  245.13  5446.1  246.25  5552.4  249.26  5759.2  259.48
#Mann=8,-1,0
  4260.9    0.07       0  4303.5    0.05       0  4800.6    0.07       0
  4981.5    0.05       0  4992.3    0.05       0  4996.3    0.05       0
  5007.6    0.07       0  5268.6    0.05       0
Bank Sta=4992.3,4996.3
Exp/Cntr=0.3,0.1

Type RM Length L Ch R = 1,6375,466,466,466
BEGIN DESCRIPTION:
Stream0717 11.0
END DESCRIPTION:
XS GIS Cut Line= 3
      2432574.27     13658952.07      2433475.00     13659375.00
      2434074.98     13658825.02
#Sta/Elev= 30
  4012.7  239.54  4036.5  239.29  4262.2  233.83  4283.2  233.81  4300.7  234.53
  4361.1  233.51  4406.8  234.66  4452.4  232.84  4490.2  234.16  4497.7  234.15
  4605.0  233.73  4896.8  233.10  4925.2  231.85  4930.7  233.28  4941.5  233.41
  4976.3  232.91  4997.1  230.56  4997.4  230.06  5001.1  230.56  5014.9  232.85
  5035.8  233.60  5057.4  232.37  5128.3  232.66  5304.1  236.87  5315.6  237.27
  5391.5  239.67  5482.3  242.05  5503.2  243.82  5651.8  248.90  5821.7  257.12
#Mann=12,-1,0
  4012.7    0.07       0  4036.5    0.05       0  4262.2    0.07       0
  4283.2    0.05       0  4490.2    0.07       0  4497.7    0.05       0
  4605.0    0.07       0  4997.1    0.05       0  5001.1    0.07       0
  5304.1    0.05       0  5315.6    0.07       0  5391.5    0.05       0
Bank Sta=4997.1,5001.1
Exp/Cntr=0.3,0.1

Type RM Length L Ch R = 1,5909,471,471,471
BEGIN DESCRIPTION:
Stream0717 10.0
END DESCRIPTION:
XS GIS Cut Line= 3
      2432675.03     13660124.99      2433575.00     13659775.00
      2434074.97     13659175.04
#Sta/Elev= 30
  4029.4  241.28  4168.8  237.21  4237.4  233.72  4370.8  232.06  4383.4  231.03
  4423.5  230.52  4445.8  229.99  4446.1  229.49  4449.8  229.99  4455.1  230.80
  4460.5  230.15  4501.5  230.94  4533.7  230.02  4544.8  231.01  4555.1  230.09
  4653.6  231.84  4732.5  230.33  4895.8  231.34  5016.9  230.47  5129.8  231.31
  5229.3  231.13  5250.8  230.38  5325.3  231.21  5413.5  236.96  5470.8  239.61
  5499.4  239.91  5555.4  242.29  5569.7  242.07  5684.3  246.84  5776.0  248.83
#Mann=6,-1,0
  4029.4    0.05       0  4423.5    0.07       0  4445.8    0.05       0
  4449.8    0.07       0  5016.9    0.05       0  5325.3    0.07       0
Bank Sta=4445.8,4449.8
Exp/Cntr=0.3,0.1

Type RM Length L Ch R = 1,5438,468,468,468
BEGIN DESCRIPTION:
Stream0717 9.0
END DESCRIPTION:
XS GIS Cut Line= 3
      2433725.00     13661275.02      2433925.00     13660075.00
      2434124.99     13659475.03
#Sta/Elev= 30
  3783.7  240.16  3811.6  239.81  3816.7  240.41  3904.0  238.28  3999.2  237.03
  4070.7  235.05  4158.8  233.67  4288.6  229.00  4288.9  228.50  4292.6  229.00
  4341.3  230.80  4402.1  229.31  4442.7  231.66  4503.5  230.88  4513.7  231.65
  4584.6  229.00  4602.4  229.61  4675.9  229.09  4709.4  230.32  4808.7  229.53
  5042.4  229.59  5077.4  231.09  5179.5  231.97  5211.1  230.47  5348.1  230.86
  5453.5  232.73  5474.6  234.40  5516.8  235.43  5567.9  238.09  5632.7  240.10
#Mann=9,-1,0
  3783.7    0.07       0  3904.0    0.12       0  4070.7    0.07       0
  4288.6    0.05       0  4292.6    0.07       0  4709.4    0.05       0
  4808.7    0.07       0  5077.4    0.05       0  5567.9    0.07       0
Bank Sta=4288.6,4292.6
Exp/Cntr=0.3,0.1

Type RM Length L Ch R = 1,4970,432,432,432
BEGIN DESCRIPTION:
Stream0717 8.0
END DESCRIPTION:
XS GIS Cut Line= 3
      2433775.00     13661225.00      2434275.00     13660325.00
      2434875.00     13659775.00
#Sta/Elev= 30
  3965.7  240.83  4054.9  237.96  4114.4  237.64  4228.8  230.65  4239.1  231.45
  4245.8  230.80  4282.6  231.79  4342.1  231.54  4385.5  229.01  4413.0  228.66
  4480.5  232.57  4526.2  229.93  4575.4  228.50  4686.4  230.74  4724.8  229.96
  4747.2  229.34  4824.8  228.25  4906.0  229.36  4927.8  228.27  4972.4  229.44
  5021.3  228.25  5021.6  227.75  5025.3  228.25  5094.2  230.95  5258.8  230.45
  5335.7  230.95  5395.3  232.41  5434.0  233.03  5511.7  237.01  5809.2  246.69
#Mann=9,-1,0
  3965.7    0.12       0  4245.8    0.07       0  4724.8    0.05       0
  4747.2    0.07       0  5021.3    0.05       0  5025.3    0.07       0
  5258.8    0.05       0  5335.7    0.07       0  5395.3    0.05       0
Bank Sta=5021.3,5025.3
Exp/Cntr=0.3,0.1

Type RM Length L Ch R = 1,4538,470,470,470
BEGIN DESCRIPTION:
Stream0717 7.0
END DESCRIPTION:
XS GIS Cut Line= 3
      2433825.02     13661224.98      2434425.00     13660675.00
      2435024.97     13660175.02
#Sta/Elev= 30
  4181.9  240.56  4231.5  237.53  4302.4  235.02  4309.2  235.58  4316.6  234.16
  4358.5  231.44  4380.1  227.50  4427.4  227.23  4427.7  226.73  4431.4  227.23
  4457.8  234.09  4472.0  235.44  4479.4  234.81  4486.2  231.46  4493.6  230.70
  4569.2  228.99  4620.6  230.23  4774.7  230.45  4875.3  231.39  4887.9  230.43
  4917.8  228.01  4998.6  228.27  5023.7  227.60  5147.3  227.77  5301.1  228.73
  5315.4  229.99  5379.2  229.53  5521.0  231.10  5603.2  234.09  5776.8  238.32
#Mann=10,-1,0
  4181.9    0.12       0  4427.4   0.035       0  4431.4    0.12       0
  4569.2    0.07       0  4774.7   0.035       0  4887.9    0.07       0
  4998.6   0.035       0  5023.7    0.07       0  5147.3   0.035       0
  5603.2    0.07       0
Bank Sta=4427.4,4431.4
Exp/Cntr=0.3,0.1

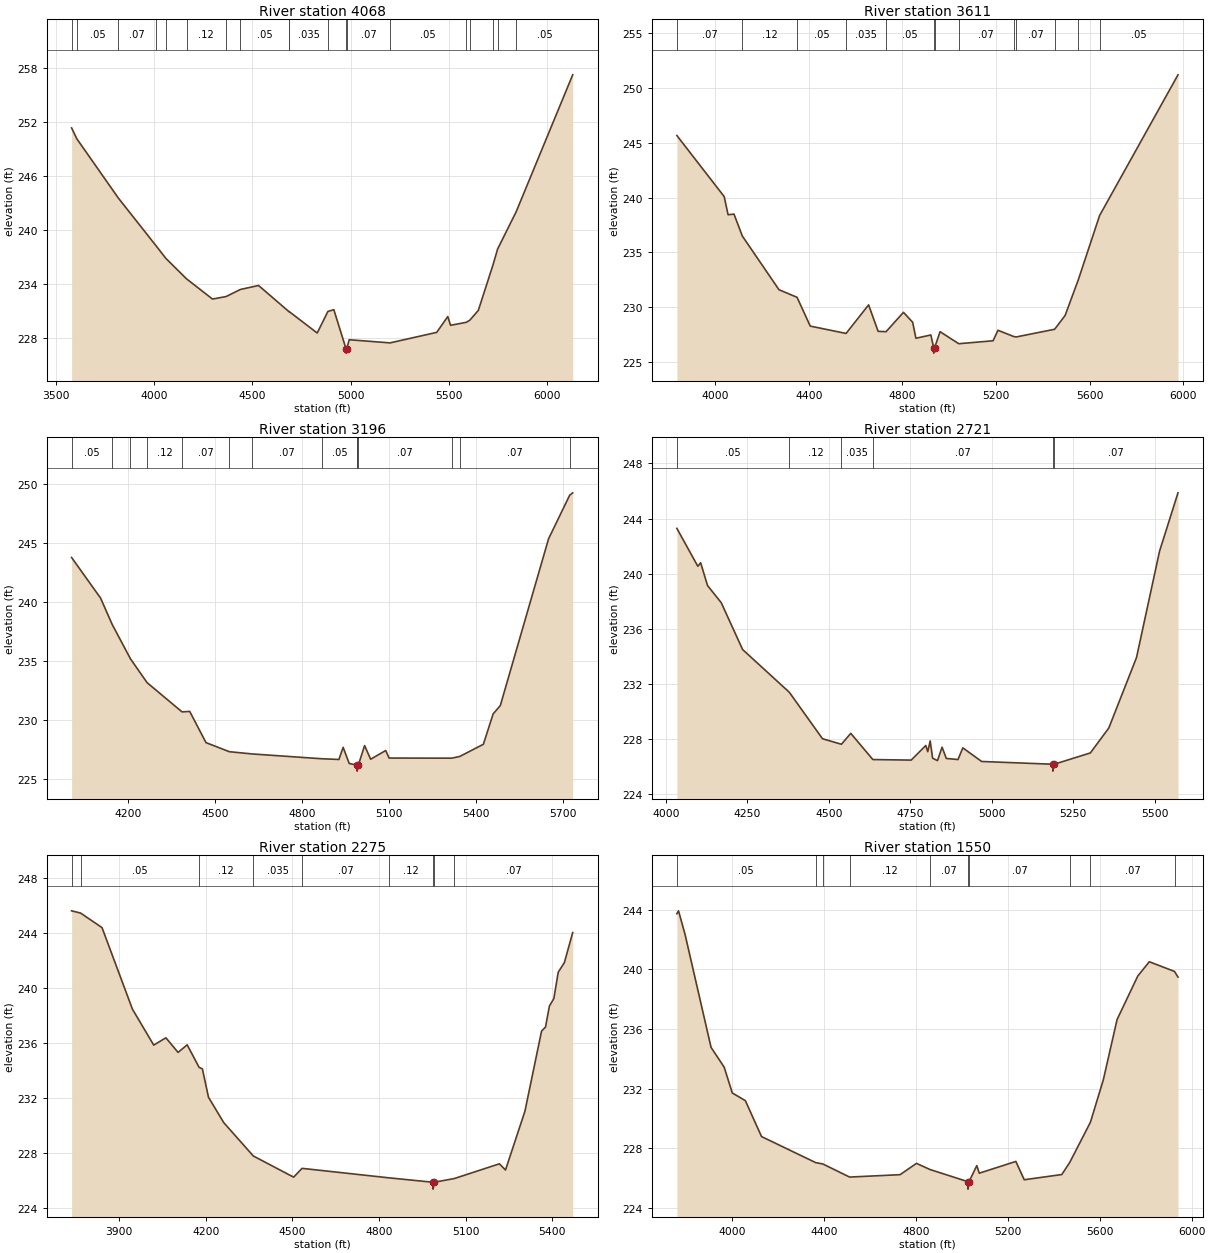
Type RM Length L Ch R = 1,4068,457,457,457
BEGIN DESCRIPTION:
Stream0717 6.0
END DESCRIPTION:
XS GIS Cut Line= 3
      2433825.01     13662124.98      2434725.00     13661025.00
      2435524.99     13660225.01
#Sta/Elev= 30
  3579.3  251.36  3605.9  250.15  3817.4  243.55  4008.2  238.27  4059.5  236.83
  4164.9  234.55  4297.1  232.30  4366.3  232.58  4439.1  233.37  4531.8  233.81
  4687.5  230.88  4688.1  230.90  4830.4  228.52  4884.9  230.92  4915.1  231.12
  4977.0  226.78  4977.2  226.28  4981.1  226.78  4993.4  227.77  5201.4  227.42
  5439.0  228.59  5495.5  230.35  5509.7  229.38  5589.9  229.71  5607.8  229.95
  5651.1  231.04  5725.8  236.10  5749.5  237.88  5843.5  242.00  6131.9  257.27
#Mann=19,-1,0
  3579.3    0.07       0  3605.9    0.05       0  3817.4    0.07       0
  4008.2    0.12       0  4059.5    0.07       0  4164.9    0.12       0
  4366.3    0.07       0  4439.1    0.05       0  4687.5    0.07       0
  4688.1   0.035       0  4884.9    0.07       0  4977.0    0.05       0
  4981.1    0.07       0  5201.4    0.05       0  5589.9   0.035       0
  5607.8    0.07       0  5725.8    0.05       0  5749.5    0.07       0
  5843.5    0.05       0
Bank Sta=4977,4981.1
Exp/Cntr=0.3,0.1

Type RM Length L Ch R = 1,3611,415,415,415
BEGIN DESCRIPTION:
Stream0717 5.0
END DESCRIPTION:
XS GIS Cut Line= 3
      2434675.01     13662324.98      2435075.00     13661225.00
      2435625.01     13660424.98
#Sta/Elev= 30
  3836.4  245.67  4038.6  240.09  4055.2  238.43  4080.4  238.49  4116.2  236.48
  4272.6  231.58  4350.0  230.88  4406.3  228.25  4559.4  227.58  4655.7  230.19
  4696.3  227.77  4730.2  227.74  4804.7  229.51  4843.9  228.60  4857.9  227.14
  4921.7  227.44  4933.6  226.28  4933.9  225.78  4937.8  226.28  4961.0  227.74
  5041.0  226.64  5187.5  226.91  5208.5  227.87  5275.4  227.30  5286.6  227.26
  5450.5  227.96  5495.3  229.22  5552.3  232.52  5642.8  238.36  5977.7  251.22
#Mann=13,-1,0
  3836.4    0.07       0  4116.2    0.12       0  4350.0    0.05       0
  4559.4   0.035       0  4730.2    0.05       0  4933.6    0.05       0
  4937.8    0.05       0  5041.0    0.07       0  5275.4    0.05       0
  5286.6    0.07       0  5450.5    0.05       0  5552.3    0.07       0
  5642.8    0.05       0
Bank Sta=4933.6,4937.8
Exp/Cntr=0.3,0.1

Type RM Length L Ch R = 1,3196,475,475,475
BEGIN DESCRIPTION:
Stream0717 4.0
END DESCRIPTION:
XS GIS Cut Line= 3
      2434775.02     13662274.97      2435375.00     13661475.00
      2436075.02     13661274.99
#Sta/Elev= 30
  4004.5  243.79  4104.5  240.34  4144.4  238.11  4207.4  235.19  4264.9  233.16
  4385.4  230.68  4411.8  230.72  4468.0  228.07  4548.4  227.30  4626.5  227.11
  4867.5  226.70  4926.3  226.64  4940.9  227.67  4961.8  226.30  4988.1  226.16
  4988.8  226.15  4989.1  225.65  4993.1  226.15  5014.9  227.82  5035.7  226.66
  5087.7  227.40  5099.4  226.76  5314.9  226.75  5342.6  226.89  5424.4  227.93
  5458.2  230.51  5482.9  231.22  5649.3  245.38  5722.1  249.08  5732.5  249.28
#Mann=14,-1,0
  4004.5    0.05       0  4144.4    0.12       0  4207.4    0.07       0
  4264.9    0.12       0  4385.4    0.07       0  4548.4   0.035       0
  4626.5    0.07       0  4867.5    0.05       0  4988.1    0.07       0
  4988.8    0.05       0  4993.1    0.07       0  5314.9   0.035       0
  5342.6    0.07       0  5722.1    0.05       0
Bank Sta=4988.8,4993.1
Exp/Cntr=0.3,0.1

Type RM Length L Ch R = 1,2721,446,446,446
BEGIN DESCRIPTION:
Stream0717 3.0
END DESCRIPTION:
XS GIS Cut Line= 3
      2434824.98     13662325.01      2435625.00     13661775.00
      2436024.97     13661375.03
#Sta/Elev= 30
  4034.3  243.29  4098.6  240.54  4107.1  240.80  4128.4  239.14  4170.3  237.90
  4235.9  234.50  4379.1  231.40  4480.8  228.03  4538.8  227.63  4567.5  228.42
  4635.2  226.52  4752.8  226.48  4797.5  227.54  4803.5  227.09  4811.0  227.87
  4818.4  226.62  4833.3  226.44  4847.4  227.42  4860.4  226.60  4896.2  226.52
  4911.1  227.37  4968.7  226.38  5186.8  226.18  5187.1  225.68  5191.1  226.18
  5302.1  227.00  5358.7  228.81  5443.6  233.92  5514.3  241.64  5570.8  245.87
#Mann=6,-1,0
  4034.3    0.05       0  4379.1    0.12       0  4538.8   0.035       0
  4635.2    0.07       0  5186.8    0.05       0  5191.1    0.07       0
Bank Sta=5186.8,5191.1
Exp/Cntr=0.3,0.1

Type RM Length L Ch R = 1,2275,725,725,725
BEGIN DESCRIPTION:
Stream0717 2.0
END DESCRIPTION:
XS GIS Cut Line= 3
      2434774.97     13662425.01      2435975.00     13662025.00
      2436224.98     13661625.04
#Sta/Elev= 30
  3734.8  245.62  3765.8  245.46  3840.2  244.40  3945.7  238.47  4019.4  235.86
  4061.6  236.39  4103.8  235.33  4135.4  235.88  4176.7  234.24  4188.1  234.13
  4209.2  232.07  4261.9  230.23  4364.5  227.80  4504.3  226.26  4533.4  226.90
  4834.8  226.21  4987.1  225.89  4987.4  225.39  4991.4  225.89  5061.2  226.16
  5217.3  227.23  5238.5  226.78  5305.8  231.05  5363.5  236.88  5377.1  237.17
  5390.7  238.70  5406.0  239.24  5421.3  241.16  5442.6  241.86  5471.4  244.04
#Mann=9,-1,0
  3734.8    0.07       0  3765.8    0.05       0  4176.7    0.12       0
  4364.5   0.035       0  4533.4    0.07       0  4834.8    0.12       0
  4987.1    0.05       0  4991.4    0.12       0  5061.2    0.07       0
Bank Sta=4987.1,4991.4
Exp/Cntr=0.3,0.1

Type RM Length L Ch R = 1,1550,1149,1149,1149
BEGIN DESCRIPTION:
Stream0717 1.0
END DESCRIPTION:
XS GIS Cut Line= 3
      2435475.03     13663174.98      2436477.95     13662327.95
      2436530.01     13661460.26
#Sta/Elev= 30
  3758.6  243.75  3765.7  243.94  3794.3  242.35  3907.4  234.77  3964.6  233.44
  3999.8  231.71  4056.9  231.19  4127.2  228.78  4363.1  227.03  4394.1  226.94
  4510.7  226.06  4730.5  226.22  4801.9  226.98  4860.2  226.57  5025.8  225.75
  5026.2  225.25  5030.6  225.75  5064.6  226.83  5075.3  226.32  5234.6  227.11
  5271.1  225.88  5434.7  226.23  5469.5  227.05  5559.2  229.74  5615.3  232.58
  5675.4  236.64  5765.5  239.56  5815.6  240.52  5925.4  239.87  5940.6  239.49
#Mann=10,-1,0
  3758.6    0.05       0  4363.1    0.12       0  4394.1   0.035       0
  4510.7    0.12       0  4860.2    0.07       0  5025.8    0.05       0
  5030.6    0.07       0  5469.5   0.035       0  5559.2    0.07       0
  5925.4    0.05       0
Bank Sta=5025.8,5030.6
Exp/Cntr=0.3,0.1

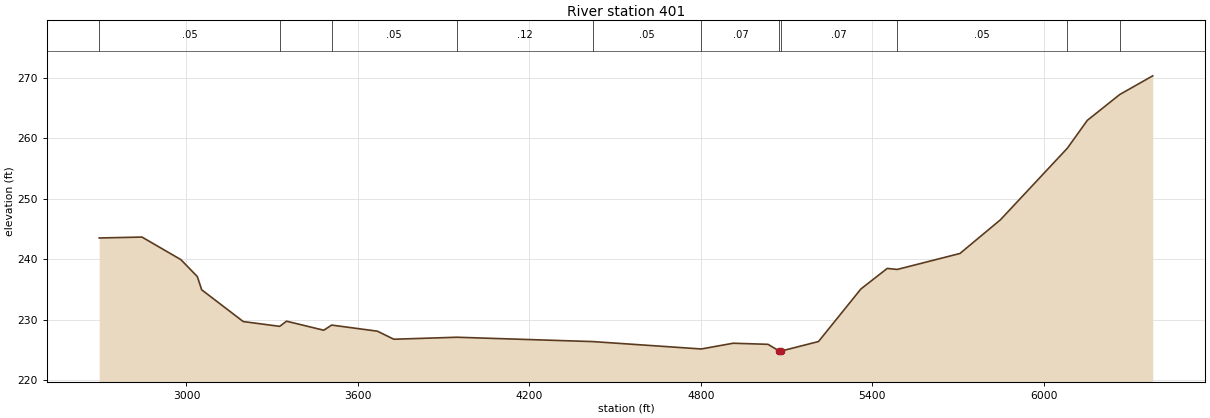
Type RM Length L Ch R = 1,401,0,0,0
BEGIN DESCRIPTION:
XS7534
END DESCRIPTION:
XS GIS Cut Line= 3
      2435488.34     13663673.46      2437389.41     13662458.16
      2438378.97     13661425.19
#Sta/Elev= 30
  2694.6  243.54  2844.3  243.69  2980.5  239.96  3038.0  237.16  3053.2  234.98
  3198.7  229.73  3326.1  228.94  3350.1  229.79  3480.3  228.30  3508.1  229.15
  3668.1  228.14  3725.7  226.81  3946.2  227.14  4422.5  226.42  4801.5  225.20
  4913.2  226.15  5035.0  225.97  5074.8  224.85  5075.2  224.35  5080.1  224.85
  5211.7  226.43  5360.2  235.12  5452.3  238.51  5487.2  238.34  5706.8  240.98
  5848.3  246.54  6082.6  258.37  6152.4  262.97  6265.9  267.24  6381.4  270.33
#Mann=11,-1,0
  2694.6    0.05       0  3326.1    0.07       0  3508.1    0.05       0
  3946.2    0.12       0  4422.5    0.05       0  4801.5    0.07       0
  5074.8    0.05       0  5080.1    0.07       0  5487.2    0.05       0
  6082.6    0.07       0  6265.9    0.05       0
Bank Sta=5074.8,5080.1
Exp/Cntr=0.3,0.1

Chan Stop Cuts=-1