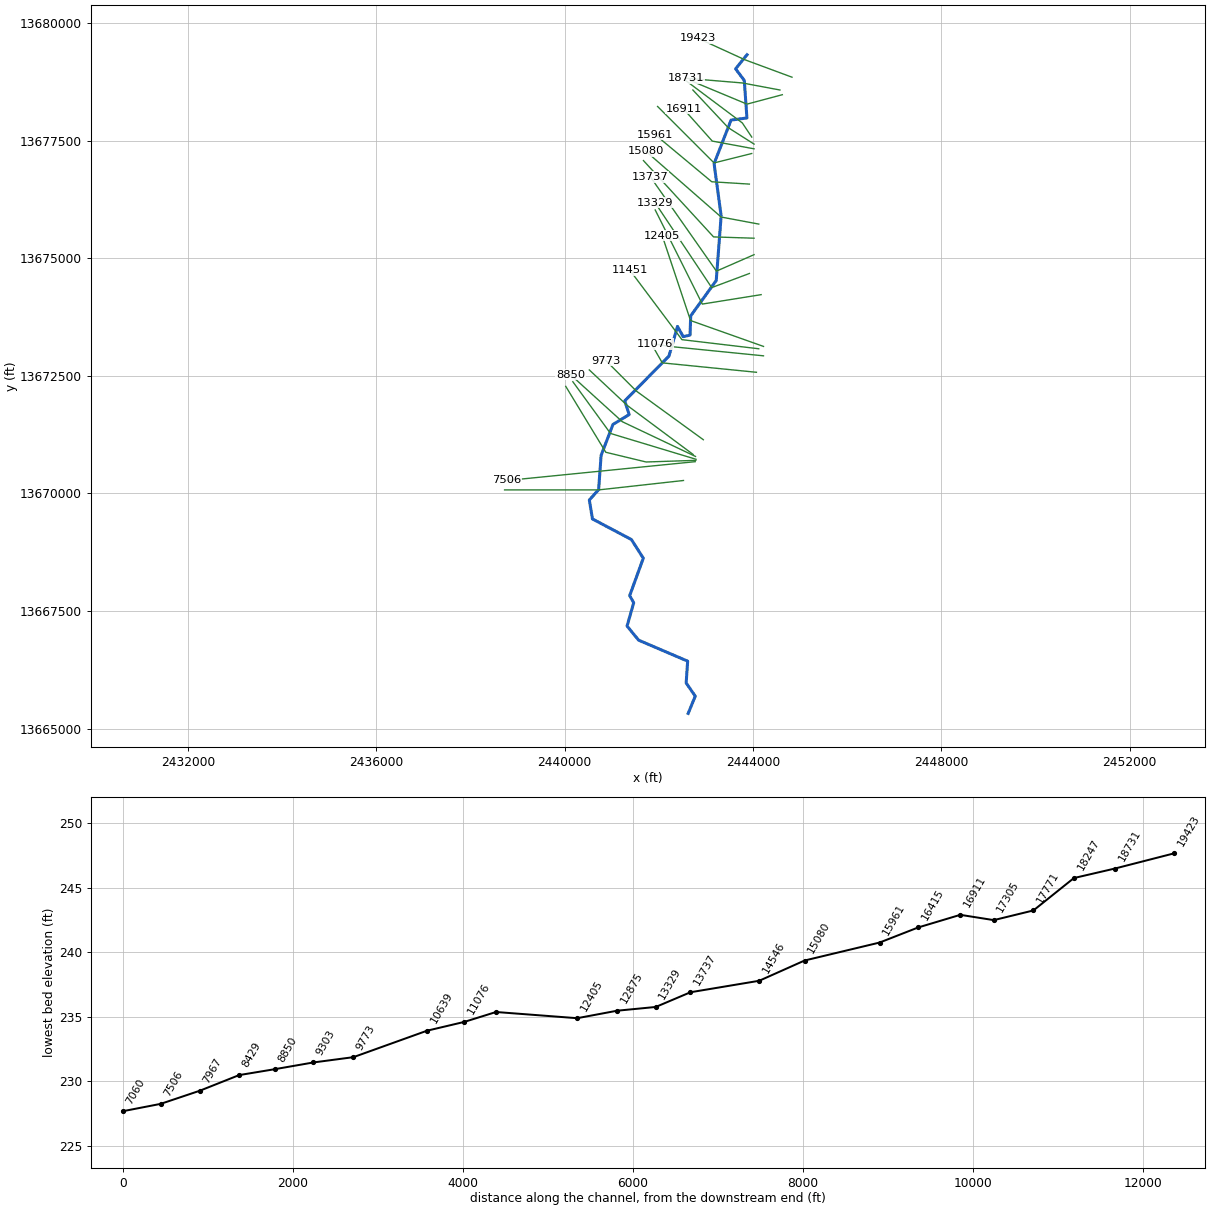
--- Stream0718.prj (project) ---

Proj Title=Stream0718 Base Level Engineering
Current Plan=p01
Default Exp/Contr=0.3,0.1
English Units
Geom File=g01
Flow File=f01
Plan File=p01
Y Axis Title=Elevation
X Axis Title(PF)=Main Channel Distance
X Axis Title(XS)=Station
BEGIN DESCRIPTION:
Stream0718
END DESCRIPTION:
DSS Export Rating Curves= 0
DSS Export Rating Curve Sorted= 0
DSS Export Volume Flow Curves= 0
DXF OffsetX= 0
DXF OffsetY= 0
DXF ScaleX= 1
DXF ScaleY= 10

--- Stream0718.p01 (plan) ---

Plan Title=Multiple Run
Short Identifier=Multiple
Geom File=g01
Flow File=f01
Subcritical Flow
K Sum by GR= 0
Std Step Tol= 0.01
Critical Tol= 0.01
Num of Std Step Trials= 20
Max Error Tol= 0.3
Flow Tol Ratio= 0.001
Split Flow NTrial= 30
Split Flow Tol= 0.02
Split Flow Ratio= 0.02
Log Output Level= 0
Friction Slope Method= 1
Unsteady Friction Slope Method= 2
Unsteady Bridges Friction Slope Method= 1
Parabolic Critical Depth
Global Vel Dist=  1 , 1 , 1
Global Log Level= 0
CheckData=True
Encroach Param= -1, 0, 0, 0
BEGIN DESCRIPTION:
Multiple Run
END DESCRIPTION:

--- Stream0718.f01 (steady flow) ---

Flow Title=Multiple
Number of Profiles=7
Profile Names=10-year,25-year,50-year,1pct_min,100-year,1pct_plu,500-year
River Rch & RM= Stream0718,Reach-1,19423
     950    1563    2128    1401    2795    5577    4781
River Rch & RM= Stream0718,Reach-1,18731
    1147    1891    2576    1695    3382    6747    5778
River Rch & RM= Stream0718,Reach-1,12875
    1296    2140    2918    1920    3832    7645    6549
River Rch & RM= Stream0718,Reach-1,8850
    1402    2310    3144    2063    4116    8213    6999
River Rch & RM= Stream0718,Reach-1,897
    1365    2237    3034    1983    3957    7895    6675
Boundary for River Rch & Prof#=Stream0718,Reach-1,1
Up Type=0
Dn Type=3
Dn Slope=0.005
Boundary for River Rch & Prof#=Stream0718,Reach-1,2
Up Type=0
Dn Type=3
Dn Slope=0.005
Boundary for River Rch & Prof#=Stream0718,Reach-1,3
Up Type=0
Dn Type=3
Dn Slope=0.005
Boundary for River Rch & Prof#=Stream0718,Reach-1,4
Up Type=0
Dn Type=3
Dn Slope=0.005
Boundary for River Rch & Prof#=Stream0718,Reach-1,5
Up Type=0
Dn Type=3
Dn Slope=0.005
Boundary for River Rch & Prof#=Stream0718,Reach-1,6
Up Type=0
Dn Type=3
Dn Slope=0.005
Boundary for River Rch & Prof#=Stream0718,Reach-1,7
Up Type=0
Dn Type=3
Dn Slope=0.005

--- Stream0718.g01 (geometry) ---

Geom Title=Existing Conditions
Program Version=4.10

River Reach=Stream0718      ,Reach-1
Reach XY= 30
        2443875.       13679325.      2443632.08       13679025.
      2443816.96     13678778.32      2443872.94     13677980.85
      2443535.52     13677935.54      2443175.52     13677009.78
      2443325.31     13675899.96      2443221.18     13674526.59
      2442678.74     13673773.44      2442664.67     13673364.82
      2442518.19     13673332.75      2442398.01     13673549.47
      2442216.88     13672918.95      2441277.46     13671966.83
      2441371.84     13671676.65      2441027.94     13671467.03
      2440775.68     13670809.16      2440722.75     13670080.93
      2440525.31     13669859.96      2440591.28     13669457.86
      2441419.53     13669019.74      2441671.69     13668623.26
      2441382.78      13667828.4      2441467.71     13667674.91
      2441326.86     13667181.13      2441572.71     13666880.84
       2442613.9     13666435.08       2442582.5     13665971.42
      2442775.43     13665690.18        2442625.       13665325.

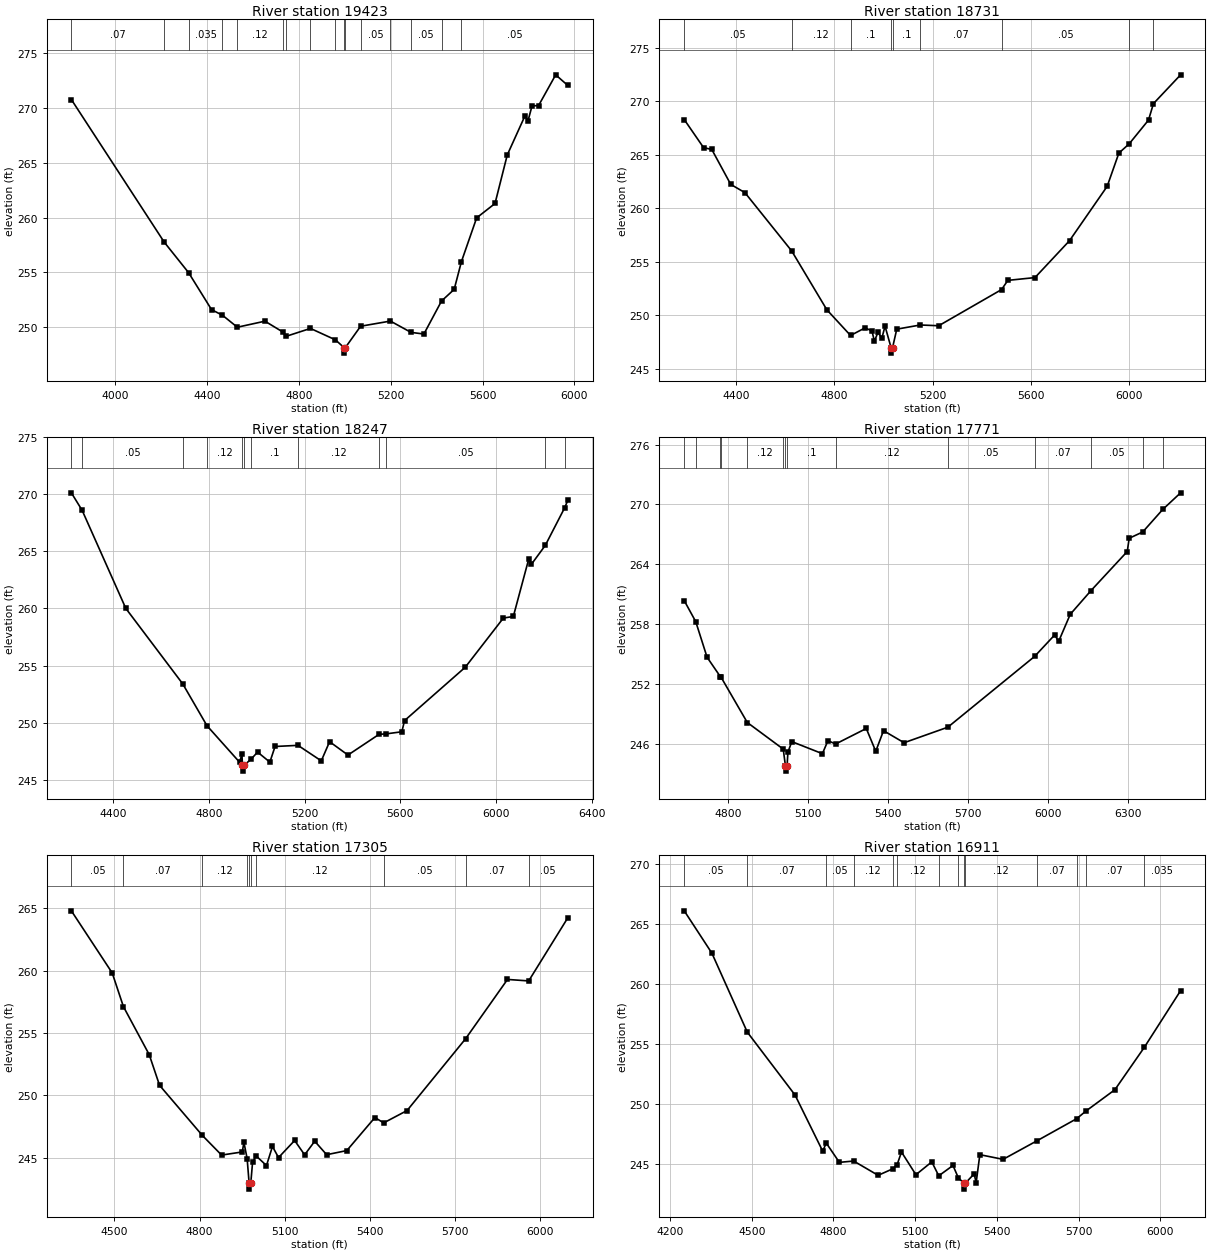
Type RM Length L Ch R = 1 ,19423   ,692,692,692
BEGIN DESCRIPTION:
Stream0718 33.0
END DESCRIPTION:
XS GIS Cut Line= 3
      2444830.65     13678847.32      2443829.65     13679218.32
      2442835.68     13679673.31
#Sta/Elev= 30
    3810  270.75  4214.2  257.76  4320.3  254.98  4420.3  251.61  4467.8   251.1
  4532.5  250.01  4652.7  250.56  4730.9  249.57  4744.7  249.18  4850.8   249.9
  4959.5  248.86  4997.2  248.15  4997.6  247.65  5002.6  248.15  5069.2   250.1
  5198.8  250.57  5288.6  249.54  5344.6  249.39  5421.5   252.4  5476.5  253.46
  5507.9  255.98  5574.2  259.97  5654.2  261.28  5707.5   265.7  5784.5  269.26
  5797.8  268.81  5815.3  270.17  5843.8   270.2  5918.3     273  5970.7  272.04
#Mann= 16 ,-1 , 0
    3810     .07       0  4214.2     .12       0  4320.3    .035       0
  4467.8      .1       0  4532.5     .12       0  4730.9      .1       0
  4744.7     .12       0  4850.8      .1       0  4959.5     .07       0
  4997.2     .05       0  5002.6     .07       0  5069.2     .05       0
  5198.8    .035       0  5288.6     .05       0  5421.5    .035       0
  5507.9     .05       0
Bank Sta=4997.2,5002.6
XS Rating Curve= 0 ,0
Exp/Cntr=0.3,0.1

Type RM Length L Ch R = 1 ,18731   ,484,484,484
BEGIN DESCRIPTION:
Stream0718 32.0
END DESCRIPTION:
XS GIS Cut Line= 3
      2444574.98       13678575.        2443775.       13678725.
      2442574.98       13678825.
#Sta/Elev= 30
  4190.5  268.31  4269.3  265.68  4302.4  265.52  4379.6  262.25  4437.2  261.48
  4627.4  256.03  4770.4  250.53  4866.7  248.13  4925.6  248.84  4953.6  248.56
  4963.7   247.6  4978.1  248.41  4994.3   247.9  5006.9     249  5031.6  246.98
  5032.1  246.48  5037.4  246.98  5054.6  248.72  5150.3  249.11  5225.2  249.04
  5480.7  252.42  5506.2  253.28  5616.5  253.54    5757  256.99  5910.1  262.07
  5957.7  265.18  5999.2  266.03  6078.1  268.26  6098.2   269.8  6208.6  272.49
#Mann= 9 ,-1 , 0
  4190.5     .05       0  4627.4     .12       0  4866.7      .1       0
  5031.6     .05       0  5037.4      .1       0  5150.3     .07       0
  5480.7     .05       0  5999.2    .035       0  6098.2     .05       0
Bank Sta=5031.6,5037.4
XS Rating Curve= 0 ,0
Exp/Cntr=0.3,0.1

Type RM Length L Ch R = 1 ,18247   ,476,476,476
BEGIN DESCRIPTION:
Stream0718 31.0
END DESCRIPTION:
XS GIS Cut Line= 3
      2444624.97     13678474.99        2443875.       13678275.
      2442674.98     13678775.01
#Sta/Elev= 30
  4223.9  270.14  4269.1   268.6  4451.6  260.01  4690.1  253.38  4791.2  249.72
  4927.6  246.52  4937.3  247.22  4939.6  246.24  4940.1  245.74  4945.4  246.24
  4975.4  246.78  5002.8  247.41  5054.2  246.53  5075.9   247.9  5171.8     248
  5269.3  246.64    5304  248.32  5380.9  247.15  5511.3  248.97  5538.1     249
  5606.2  249.19  5617.6  250.17  5871.6  254.85  6030.9  259.16  6072.6   259.3
  6137.6  264.38  6148.4  263.88  6206.2  265.53  6287.8  268.85  6300.1  269.47
#Mann= 12 ,-1 , 0
  4223.9    .035       0  4269.1     .05       0  4690.1     .07       0
  4791.2     .12       0  4939.6     .05       0  4945.4     .12       0
  4975.4      .1       0  5171.8     .12       0  5511.3     .07       0
  5538.1     .05       0  6206.2    .035       0  6287.8     .05       0
Bank Sta=4939.6,4945.4
XS Rating Curve= 0 ,0
Exp/Cntr=0.3,0.1

Type RM Length L Ch R = 1 ,17771   ,466,466,466
BEGIN DESCRIPTION:
Stream0718 30.0
END DESCRIPTION:
XS GIS Cut Line= 3
        2443975.     13677574.99        2443775.       13677875.
      2442574.97     13678775.02
#Sta/Elev= 30
  4634.9  260.34  4678.1  258.23  4720.5  254.66  4770.1  252.72  4773.3  252.64
  4871.3  248.11    5006  245.44  5014.4  243.73  5014.9  243.23  5020.3  243.73
  5023.6  245.14  5038.2  246.19  5152.8  244.98  5173.6  246.29  5202.3  245.95
  5317.3  247.51  5352.8  245.22  5381.9  247.29    5459  246.08  5623.1  247.64
  5948.2  254.74  6023.6   256.9  6038.2  256.24  6081.9  258.97  6159.4  261.34
  6295.5  265.27  6302.8   266.6  6353.5  267.23  6428.9   269.5  6495.5  271.16
#Mann= 14 ,-1 , 0
  4634.9     .05       0  4678.1     .07       0  4770.1     .05       0
  4773.3     .07       0  4871.3     .12       0    5006      .1       0
  5014.4     .05       0  5020.3      .1       0  5202.3     .12       0
  5623.1     .05       0  5948.2     .07       0  6159.4     .05       0
  6353.5    .035       0  6428.9     .05       0
Bank Sta=5014.4,5020.3
XS Rating Curve= 0 ,0
Exp/Cntr=0.3,0.1

Type RM Length L Ch R = 1 ,17305   ,394,394,394
BEGIN DESCRIPTION:
Stream0718 29.0
END DESCRIPTION:
XS GIS Cut Line= 3
        2444025.       13677425.        2443475.       13677775.
      2442725.01     13678574.99
#Sta/Elev= 30
  4348.1  264.79    4492  259.81  4531.5  257.11  4622.4  253.26  4658.8   250.8
  4809.7  246.78  4877.3  245.21  4950.1  245.46    4956  246.22  4967.3  244.93
  4974.2  242.98  4974.7  242.48  4980.2  242.98  4986.5  244.64  4999.1  245.14
  5035.4  244.37  5056.5   245.9  5077.9  245.01  5134.6  246.38  5169.8  245.23
  5205.4  246.32  5247.4  245.24  5318.3  245.57  5417.4  248.22  5448.3  247.79
  5530.7  248.78    5737  254.54  5884.4  259.29  5959.1  259.17  6096.6  264.22
#Mann= 10 ,-1 , 0
  4348.1     .05       0  4531.5     .07       0  4809.7     .12       0
  4967.3      .1       0  4974.2     .05       0  4980.2      .1       0
  4999.1     .12       0  5448.3     .05       0    5737     .07       0
  5959.1     .05       0
Bank Sta=4974.2,4980.2
XS Rating Curve= 0 ,0
Exp/Cntr=0.3,0.1

Type RM Length L Ch R = 1 ,16911   ,496,496,496
BEGIN DESCRIPTION:
Stream0718 28.0
END DESCRIPTION:
XS GIS Cut Line= 3
      2444024.95     13677325.01      2443136.66     13677489.36
      2442524.99     13678175.01
#Sta/Elev= 30
  4252.2  266.07  4353.8  262.54  4483.6  255.97  4658.9  250.73  4760.6  246.05
  4773.5  246.73  4821.7  245.12  4874.2  245.23    4964  244.04  5017.6  244.58
  5033.9  244.94  5049.8  245.98  5102.7  244.09    5161  245.16  5186.6     244
  5238.8  244.86  5258.1  243.85  5278.4  243.39  5278.9  242.89  5284.4  243.39
  5316.5  244.16  5323.9  243.43  5337.4  245.76  5422.7  245.37  5547.5  246.92
  5692.4  248.75  5727.9  249.41  5833.2  251.17  5940.9  254.69  6074.4  259.42
#Mann= 14 ,-1 , 0
  4252.2     .05       0  4483.6     .07       0  4773.5     .05       0
  4874.2     .12       0  5017.6      .1       0  5033.9     .12       0
  5186.6      .1       0  5258.1     .12       0  5278.4     .05       0
  5284.4     .12       0  5547.5     .07       0  5692.4     .05       0
  5727.9     .07       0  5940.9    .035       0
Bank Sta=5278.4,5284.4
XS Rating Curve= 0 ,0
Exp/Cntr=0.3,0.1

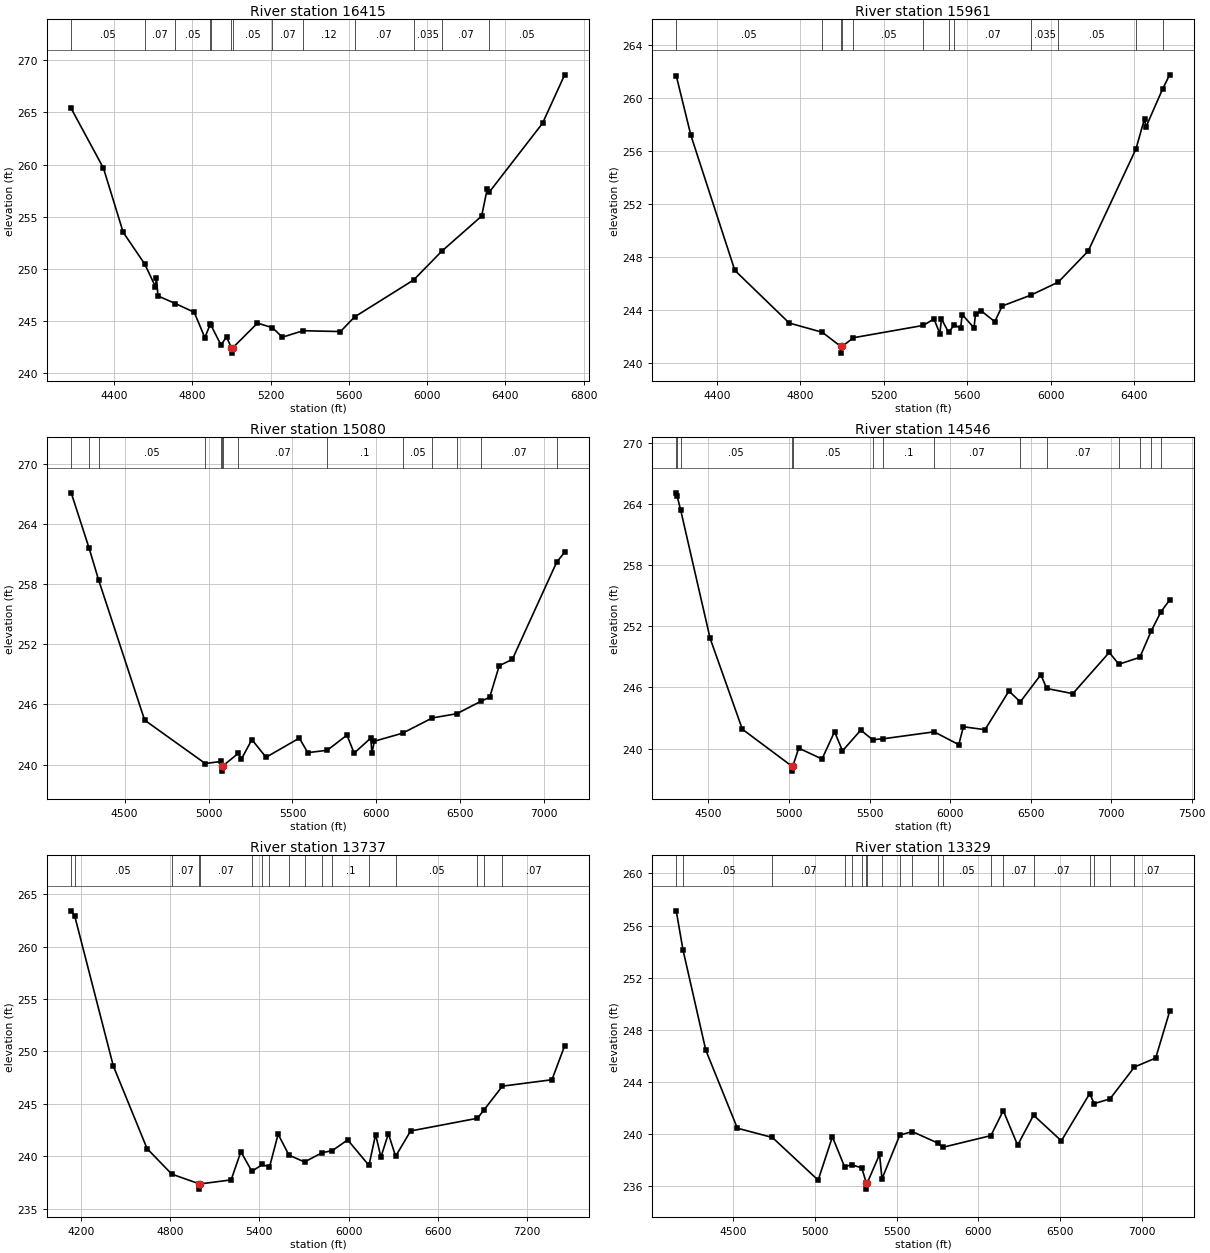
Type RM Length L Ch R = 1 ,16415   ,454,454,454
BEGIN DESCRIPTION:
Stream0718 27.0
END DESCRIPTION:
XS GIS Cut Line= 3
      2443974.97     13677224.99        2443175.       13677025.
      2441975.03     13678224.97
#Sta/Elev= 30
  4180.8  265.38  4345.7  259.65  4446.2  253.51  4557.3  250.43  4611.1  248.29
  4616.3  249.15    4624   247.4  4712.7  246.67  4809.5  245.83  4863.7  243.39
  4891.7  244.71  4893.2  244.65  4946.1   242.7  4974.5  243.47  4999.8  242.41
  5000.3  241.91  5005.8  242.41  5132.7  244.79  5209.2  244.35  5259.9  243.44
  5365.8  244.06  5556.9  243.98  5628.7  245.38  5930.7  248.93    6074  251.68
  6278.2  255.06  6306.5  257.65  6316.1  257.33  6589.3  263.96  6702.4  268.61
#Mann= 13 ,-1 , 0
  4180.8     .05       0  4557.3     .07       0  4712.7     .05       0
  4891.7     .07       0  4893.2     .05       0  4999.8     .05       0
  5005.8     .05       0  5209.2     .07       0  5365.8     .12       0
  5628.7     .07       0  5930.7    .035       0    6074     .07       0
  6316.1     .05       0
Bank Sta=4999.8,5005.8
XS Rating Curve= 0 ,0
Exp/Cntr=0.3,0.1

Type RM Length L Ch R = 1 ,15961   ,881,881,881
BEGIN DESCRIPTION:
Stream0718 26.0
END DESCRIPTION:
XS GIS Cut Line= 3
      2443925.01       13676575.        2443125.       13676625.
      2441925.01     13677624.99
#Sta/Elev= 30
  4205.6  261.66  4275.7  257.16  4486.2  246.98  4746.7  243.01  4905.6  242.31
  4994.1  241.24  4994.6  240.74  5000.2  241.24    5054   241.9  5389.4  242.83
    5440  243.32  5468.6  242.21  5475.8  243.32  5510.3  242.31  5538.1  242.88
  5567.6   242.6  5575.4  243.65    5632  242.64  5639.1   243.7  5667.8  243.91
  5731.6  243.11  5766.7  244.29    5904  245.11  6035.3  246.09  6178.7  248.43
  6407.7  256.13  6448.8  258.42  6455.3  257.78  6535.3  260.65  6569.2  261.72
#Mann= 12 ,-1 , 0
  4205.6     .05       0  4905.6      .1       0  4994.1     .05       0
  5000.2      .1       0    5054     .05       0  5389.4    .033       0
  5510.3      .1       0  5538.1     .07       0    5904    .035       0
  6035.3     .05       0  6407.7     .07       0  6535.3     .05       0
Bank Sta=4994.1,5000.2
XS Rating Curve= 0 ,0
Exp/Cntr=0.3,0.1

Type RM Length L Ch R = 1 ,15080   ,534,534,534
BEGIN DESCRIPTION:
Stream0718 25.0
END DESCRIPTION:
XS GIS Cut Line= 3
      2444125.02       13675725.        2443325.       13675875.
      2441724.99     13677275.01
#Sta/Elev= 30
  4181.8  267.08  4288.7  261.55  4344.5  258.43  4619.3  244.43  4980.3  240.11
  5074.2  240.31  5077.6  239.85  5078.1  239.35  5083.8  239.85  5178.4  241.14
  5194.6  240.51  5258.2  242.49  5342.7  240.73    5541  242.64  5591.3  241.19
  5707.5  241.43  5824.8  242.94  5867.5  241.14  5966.2  242.64  5973.8  241.16
  5988.1  242.33  6155.7  243.13  6333.3  244.65  6479.2  245.07    6624  246.32
  6675.2  246.71  6732.2  249.86    6810  250.48  7074.6  260.18  7121.8  261.16
#Mann= 14 ,-1 , 0
  4181.8     .05       0  4288.7    .035       0  4344.5     .05       0
  4980.3     .07       0  5074.2     .05       0  5077.6     .05       0
  5083.8     .05       0  5178.4     .07       0  5707.5      .1       0
  6155.7     .05       0  6333.3     .07       0  6479.2    .035       0
    6624     .07       0  7074.6     .05       0
Bank Sta=5077.6,5083.8
XS Rating Curve= 0 ,0
Exp/Cntr=0.3,0.1

Type RM Length L Ch R = 1 ,14546   ,809,809,809
BEGIN DESCRIPTION:
Stream0718 24.0
END DESCRIPTION:
XS GIS Cut Line= 3
      2444025.05       13675425.      2443164.66     13675452.39
      2441675.02     13677074.98
#Sta/Elev= 30
    4300  265.12  4304.9  264.82  4327.2  263.45  4510.2  250.83  4710.3   241.9
  5016.8  238.28  5017.3  237.78  5024.1  238.28  5060.4  240.04  5205.1  238.97
  5282.9  241.65  5332.2  239.77  5445.7  241.81  5518.7  240.87  5581.8  240.95
  5901.2  241.64  6054.2  240.38  6082.6  242.14    6217  241.85  6365.6  245.65
    6436  244.58  6563.5  247.25  6600.1   245.9  6762.1  245.39  6988.3  249.44
  7048.1  248.28  7178.4  248.96  7248.1  251.52  7308.7  253.41  7363.5   254.6
#Mann= 14 ,-1 , 0
    4300     .05       0  4304.9    .035       0  4327.2     .05       0
  5016.8     .05       0  5024.1     .05       0  5518.7     .07       0
  5581.8      .1       0  5901.2     .07       0    6436     .05       0
  6600.1     .07       0  7048.1    .035       0  7178.4     .07       0
  7248.1     .12       0  7308.7     .05       0
Bank Sta=5016.8,5024.1
XS Rating Curve= 0 ,0
Exp/Cntr=0.3,0.1

Type RM Length L Ch R = 1 ,13737   ,408,408,408
BEGIN DESCRIPTION:
Stream0718 23.0
END DESCRIPTION:
XS GIS Cut Line= 3
      2444024.99     13675074.99        2443225.       13674725.
        2441825.     13676724.99
#Sta/Elev= 30
  4136.1   263.4  4159.8   262.9  4418.7  248.63  4645.6  240.75  4811.4  238.32
  4996.7  237.39  4997.2  236.89    5004  237.39  5210.3  237.77  5275.7  240.45
    5350  238.58  5420.3  239.24  5467.9  238.98  5525.9  242.12  5599.2  240.12
  5703.6  239.48  5821.4  240.36  5888.9  240.55  5993.2  241.58  6136.1  239.15
  6180.7  242.09  6216.4  239.94  6266.6  242.18    6315  240.02  6416.1  242.43
  6864.9  243.64  6909.2  244.44  7032.5   246.7  7365.2  247.31  7450.6  250.54
#Mann= 17 ,-1 , 0
  4136.1    .035       0  4159.8     .05       0  4811.4     .07       0
  4996.7     .05       0    5004     .07       0    5350     .05       0
  5420.3      .1       0  5467.9     .07       0  5599.2    .033       0
  5703.6     .07       0  5821.4     .05       0  5888.9      .1       0
  6136.1     .07       0    6315     .05       0  6864.9     .07       0
  6909.2     .05       0  7032.5     .07       0
Bank Sta=4996.7,5004
XS Rating Curve= 0 ,0
Exp/Cntr=0.3,0.1

Type RM Length L Ch R = 1 ,13329   ,454,454,454
BEGIN DESCRIPTION:
Stream0718 22.0
END DESCRIPTION:
XS GIS Cut Line= 3
      2443924.97     13674674.99        2443125.       13674375.
        2441925.       13676175.
#Sta/Elev= 30
  4151.7  257.13  4192.7  254.15  4332.3  246.43  4525.5  240.43  4739.6  239.72
  5019.6  236.44  5106.7  239.77  5181.1  237.47  5224.6  237.62  5286.6  237.38
  5313.3  236.25  5313.8  235.75  5320.7  236.25  5395.2  238.42    5410  236.54
  5518.9   239.9  5595.4  240.17  5751.2  239.29  5780.8  238.96    6076  239.86
  6151.6  241.78  6239.5  239.13    6337  241.43  6506.9  239.46  6680.4  243.09
  6707.7  242.32  6804.2  242.68  6953.8  245.13  7083.8  245.82  7169.4  249.41
#Mann= 20 ,-1 , 0
  4151.7    .035       0  4192.7     .05       0  4739.6     .07       0
  5181.1      .1       0  5224.6     .15       0  5286.6      .1       0
  5313.3     .05       0  5320.7      .1       0    5410     .05       0
  5518.9      .1       0  5595.4     .05       0  5751.2      .1       0
  5780.8     .05       0    6076      .1       0  6151.6     .07       0
    6337     .07       0  6680.4     .05       0  6707.7     .07       0
  6804.2     .05       0  6953.8     .07       0
Bank Sta=5313.3,5320.7
XS Rating Curve= 0 ,0
Exp/Cntr=0.3,0.1

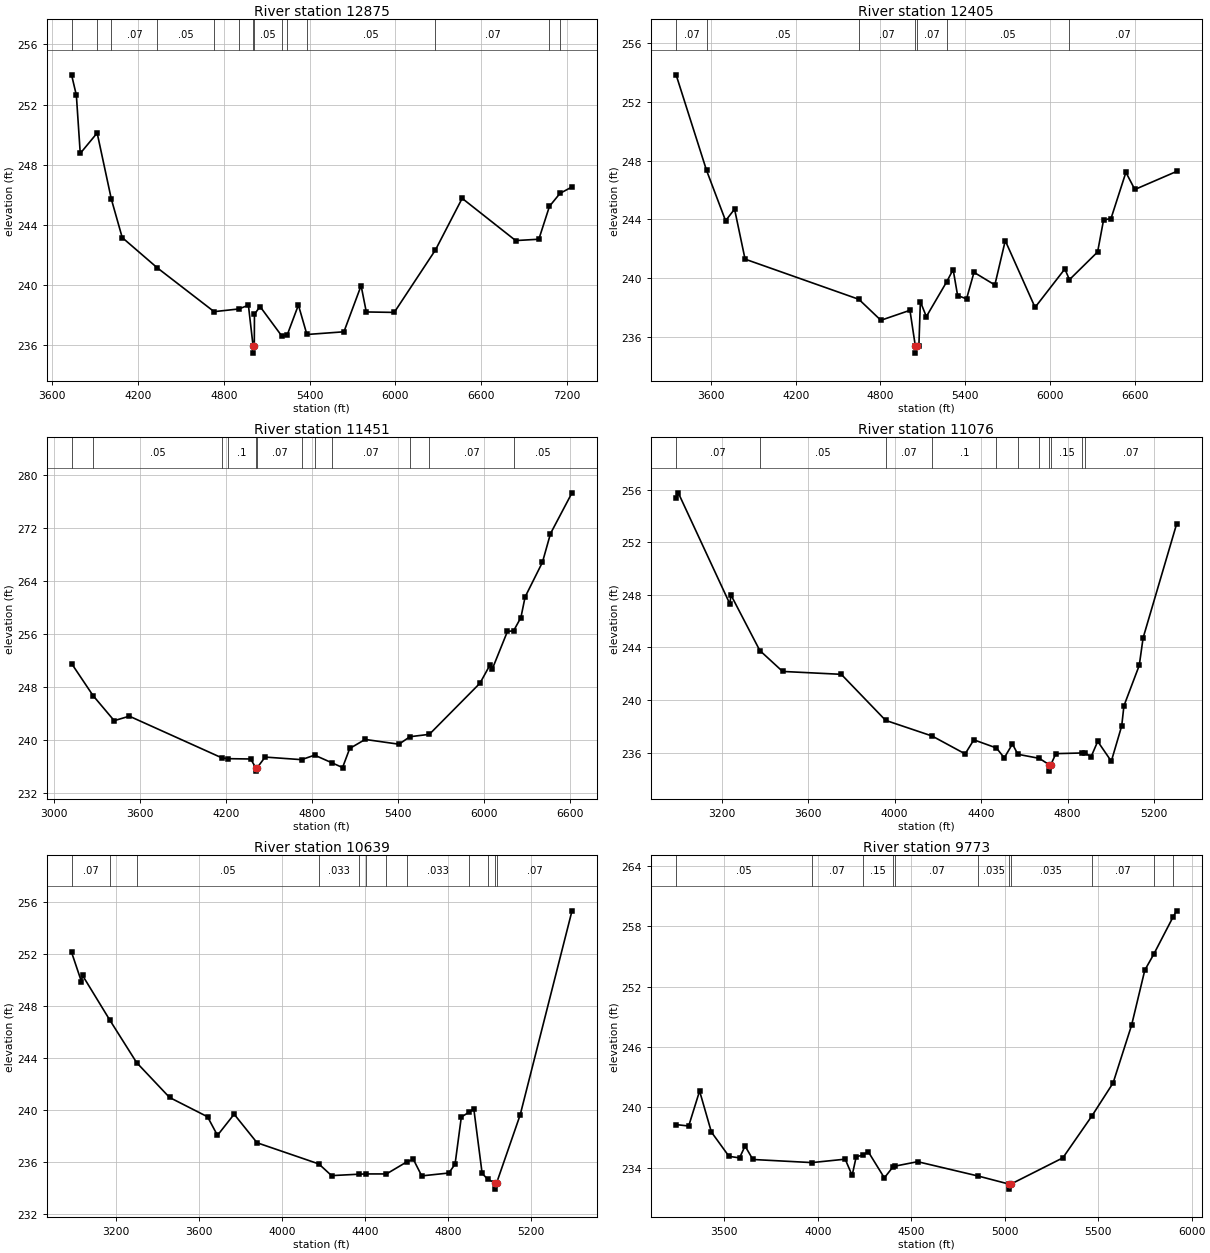
Type RM Length L Ch R = 1 ,12875   ,470,470,470
BEGIN DESCRIPTION:
Stream0718 21.0
END DESCRIPTION:
XS GIS Cut Line= 3
      2444175.04     13674225.01        2442925.       13674025.
        2441925.     13676024.99
#Sta/Elev= 30
  3734.5  253.98  3768.1  252.62  3795.3  248.75  3913.6  250.11  4012.8  245.71
    4089  243.15  4335.2  241.13    4732  238.22  4905.7   238.4    4972  238.65
  5004.5  235.96    5005  235.46  5013.2  235.96  5014.4  238.05  5053.5  238.56
  5207.9  236.57  5244.4  236.69  5321.9  238.66  5381.4   236.7  5640.5  236.88
  5760.7  239.95    5797   238.2  5992.7  238.17  6281.2  242.33  6467.9  245.76
  6842.4  242.95  7004.5  243.04  7078.8  245.23  7152.4  246.09  7236.5  246.52
#Mann= 14 ,-1 , 0
  3734.5     .05       0  3913.6    .035       0  4012.8     .07       0
  4335.2     .05       0    4732     .07       0  4905.7     .05       0
  5004.5     .05       0  5013.2     .05       0  5207.9     .07       0
  5244.4     .15       0  5381.4     .05       0  6281.2     .07       0
  7078.8     .05       0  7152.4     .07       0
Bank Sta=5004.5,5013.2
XS Rating Curve= 0 ,0
Exp/Cntr=0.3,0.1

Type RM Length L Ch R = 1 ,12405   ,954,954,954
BEGIN DESCRIPTION:
Stream0718 20.0
END DESCRIPTION:
XS GIS Cut Line= 3
        2444225.       13673125.        2442675.       13673675.
      2442074.98     13675475.05
#Sta/Elev= 30
  3353.9  253.86  3569.5  247.34  3704.1  243.91  3767.7   244.7    3842  241.29
  4647.5  238.55  4803.2  237.12  5009.1   237.8  5046.9  235.38  5047.4  234.88
  5055.7  235.38  5072.4   235.4  5082.9  238.39  5125.1  237.37  5268.3  239.73
  5314.8  240.58  5346.4  238.81  5409.7  238.58  5462.4  240.39    5610  239.53
  5683.7  242.55  5894.6     238  6105.4  240.62    6138  239.89  6337.3  241.78
  6379.4  243.96  6432.2  244.06  6537.6  247.21  6600.8  246.04    6896  247.27
#Mann= 7 ,-1 , 0
  3353.9     .07       0  3569.5     .05       0  4647.5     .07       0
  5046.9     .05       0  5055.7     .07       0  5268.3     .05       0
    6138     .07       0
Bank Sta=5046.9,5055.7
XS Rating Curve= 0 ,0
Exp/Cntr=0.3,0.1

Type RM Length L Ch R = 1 ,11451   ,375,375,375
BEGIN DESCRIPTION:
Stream0718 19.0
END DESCRIPTION:
XS GIS Cut Line= 3
      2444124.98       13673075.      2442492.68     13673268.44
      2441386.69     13674745.42
#Sta/Elev= 30
  3124.4  251.59    3274  246.76  3421.6  242.97  3527.2  243.65  4172.4  237.36
  4214.5  237.24  4373.1  237.19  4408.8  235.86  4409.3  235.36  4417.9  235.86
  4473.8  237.48  4727.7  237.09  4818.9  237.77    4939  236.62  5013.7   235.9
  5063.7  238.78  5171.4  240.14  5406.9  239.42  5483.3  240.55  5618.8  240.91
  5971.6  248.62  6042.4  251.41    6057  250.73  6163.3  256.44    6206  256.52
  6257.1  258.53  6286.3  261.63  6407.1  266.86  6463.4  271.19  6613.3  277.34
#Mann= 12 ,-1 , 0
  3124.4     .07       0    3274     .05       0  4172.4     .07       0
  4214.5      .1       0  4408.8     .05       0  4417.9     .07       0
  4727.7     .07       0  4818.9      .1       0    4939     .07       0
  5483.3     .05       0  5618.8     .07       0    6206     .05       0
Bank Sta=4408.8,4417.9
XS Rating Curve= 0 ,0
Exp/Cntr=0.3,0.1

Type RM Length L Ch R = 1 ,11076   ,437,437,437
BEGIN DESCRIPTION:
Stream0718 18.0
END DESCRIPTION:
XS GIS Cut Line= 3
      2444224.97       13672925.        2442225.       13673125.
      2441924.98       13673175.
#Sta/Elev= 30
  2989.6  255.34  2999.6  255.75  3238.3   247.3  3243.3  247.98  3376.7  243.76
    3482  242.17  3753.4  241.95  3958.4  238.45  4173.3  237.26  4326.2   235.9
  4366.4  236.97  4470.9  236.35  4507.1   235.6  4544.8  236.65  4570.1  235.87
  4669.3  235.56  4713.6  235.09  4714.1  234.59  4722.7  235.09  4745.8  235.92
  4867.7  235.97    4881  235.94  4909.1   235.7  4939.2  236.85  5002.1  235.34
  5050.2  238.03  5060.4  239.55  5131.3  242.63  5149.1  244.72  5303.7  253.36
#Mann= 11 ,-1 , 0
  2989.6     .07       0  3376.7     .05       0  3958.4     .07       0
  4173.3      .1       0  4470.9     .07       0  4570.1    .033       0
  4669.3     .15       0  4713.6     .05       0  4722.7     .15       0
  4867.7    .033       0    4881     .07       0
Bank Sta=4713.6,4722.7
XS Rating Curve= 0 ,0
Exp/Cntr=0.3,0.1

Type RM Length L Ch R = 1 ,10639   ,866,866,866
BEGIN DESCRIPTION:
Stream0718 17.0
END DESCRIPTION:
XS GIS Cut Line= 3
      2444075.02       13672575.        2442075.       13672775.
      2441875.01     13673124.99
#Sta/Elev= 30
  2985.6  252.15  3033.4  249.88  3038.4  250.37  3169.5  246.94  3299.5  243.65
    3458  240.97  3641.4  239.48  3689.1  238.05  3769.5  239.68  3880.1  237.48
  4177.9  235.85  4239.3  234.95  4371.8  235.06  4404.9  235.08  4504.1  235.08
  4603.3  236.02  4633.8   236.2    4674  234.93  4804.7  235.15  4834.8  235.83
    4865  239.46  4900.8  239.82  4925.2  240.09  4965.4  235.12  4992.4  234.67
  5026.1  234.41  5026.6  233.91  5035.7  234.41  5148.9  239.63  5398.7  255.34
#Mann= 12 ,-1 , 0
  2985.6     .07       0  3169.5    .035       0  3299.5     .05       0
  4177.9    .033       0  4371.8     .15       0  4404.9     .07       0
  4504.1     .15       0  4603.3    .033       0  4900.8      .1       0
  4992.4     .07       0  5026.1     .05       0  5035.7     .07       0
Bank Sta=5026.1,5035.7
XS Rating Curve= 0 ,0
Exp/Cntr=0.3,0.1

Type RM Length L Ch R = 1 ,9773    ,470,470,470
BEGIN DESCRIPTION:
Stream0718 16.0
END DESCRIPTION:
XS GIS Cut Line= 3
      2442946.63     13671142.01        2441525.       13672175.
      2440875.03     13672824.97
#Sta/Elev= 30
  3242.7  238.28    3310  238.14  3368.3  241.62  3431.4  237.54  3525.7  235.12
  3582.1  234.97  3611.5  236.15  3653.2  234.81  3968.9   234.5  4147.1  234.84
  4184.2  233.22  4205.8  235.07  4240.5  235.25  4270.7  235.57  4356.5  232.98
  4401.7  234.05  4413.8  234.15  4534.3  234.59  4858.8  233.16  5023.4  232.36
  5023.9  231.86  5033.1  232.36  5311.1  234.97  5466.9  239.15  5579.8  242.42
  5678.8  248.17  5749.5  253.65  5796.7  255.21  5900.1  258.92  5919.2  259.55
#Mann= 11 ,-1 , 0
  3242.7     .05       0  3968.9     .07       0  4240.5     .15       0
  4401.7      .1       0  4413.8     .07       0  4858.8    .035       0
  5023.4    .035       0  5033.1    .035       0  5466.9     .07       0
  5796.7     .12       0  5900.1     .07       0
Bank Sta=5023.4,5033.1
XS Rating Curve= 0 ,0
Exp/Cntr=0.3,0.1

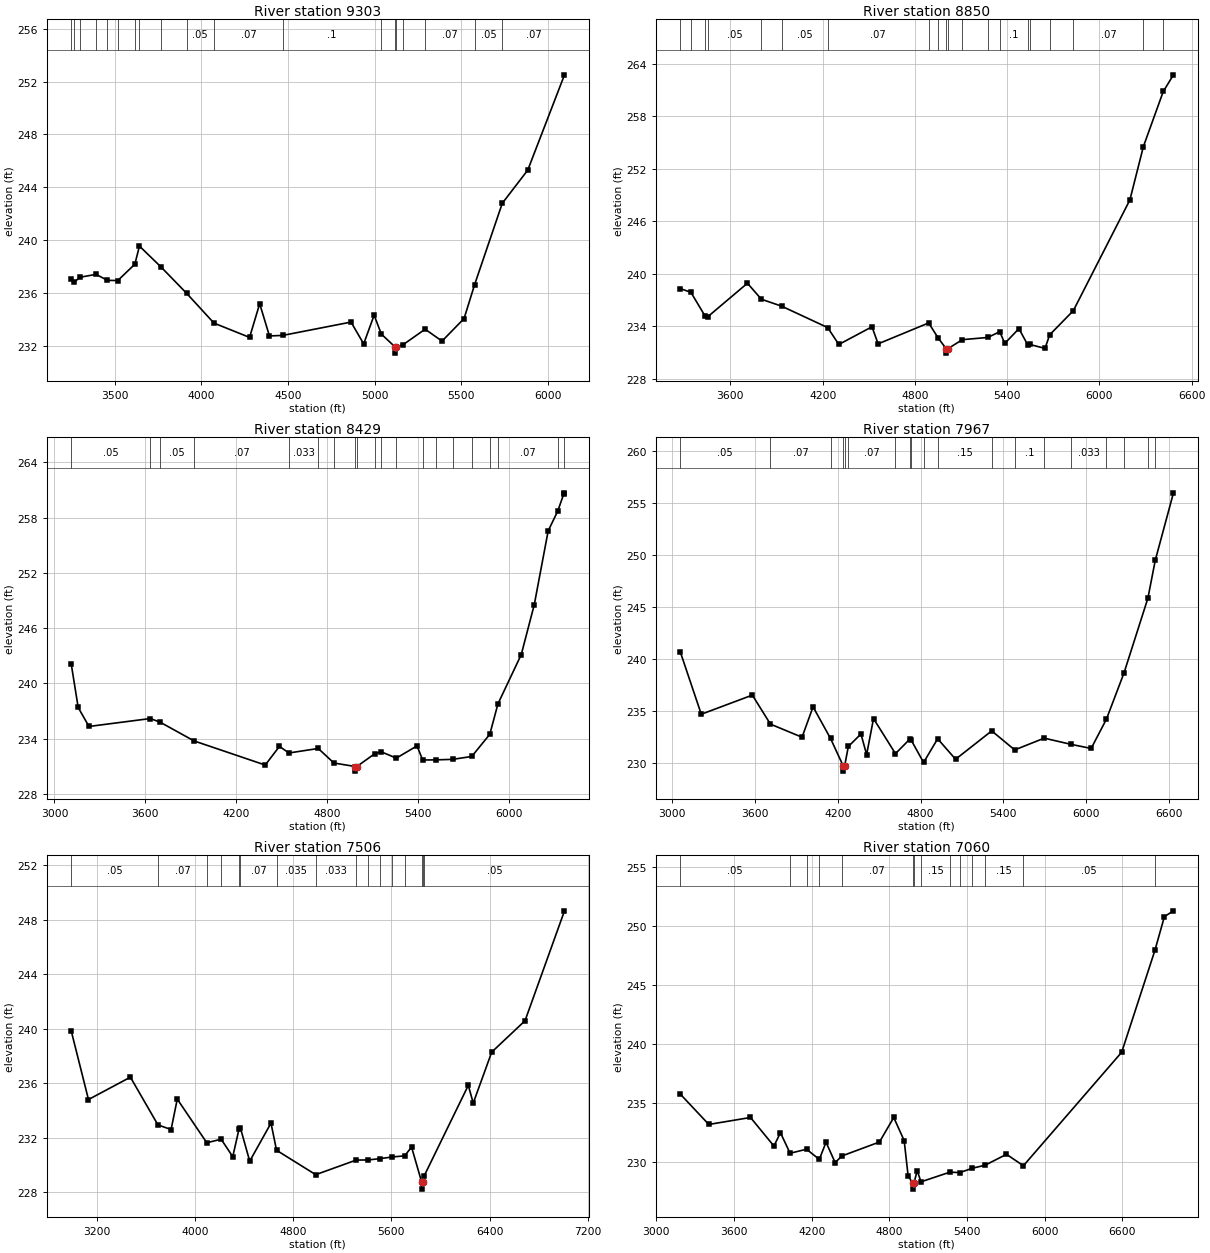
Type RM Length L Ch R = 1 ,9303    ,453,453,453
BEGIN DESCRIPTION:
Stream0718 15.0
END DESCRIPTION:
XS GIS Cut Line= 3
      2442731.05       13670828.        2441325.       13671875.
      2440525.02     13672624.98
#Sta/Elev= 30
  3247.5  237.04  3265.6  236.82  3297.6  237.19    3391  237.41  3456.4  236.96
  3516.4  236.94  3615.2  238.18  3641.7  239.55  3767.7  237.95    3914  235.98
  4072.4  233.72  4277.9  232.64  4336.3  235.19  4392.6  232.75    4469  232.79
  4863.9   233.8    4937  232.15  4997.4  234.32  5039.1  232.89  5115.8  231.95
  5116.3  231.45    5126  231.95  5161.6  232.06    5292  233.26  5389.6  232.36
  5517.1  234.07  5577.5  236.62  5737.7  242.79  5884.9   245.3  6097.1  252.51
#Mann= 19 ,-1 , 0
  3247.5    .063       0  3265.6     .05       0  3297.6    .063       0
    3391     .05       0  3456.4    .063       0  3516.4     .05       0
  3615.2    .063       0  3641.7     .05       0  3767.7    .035       0
    3914     .05       0  4072.4     .07       0    4469      .1       0
  5039.1     .07       0  5115.8     .05       0    5126     .07       0
  5161.6    .033       0    5292     .07       0  5577.5     .05       0
  5737.7     .07       0
Bank Sta=5115.8,5126
XS Rating Curve= 0 ,0
Exp/Cntr=0.3,0.1

Type RM Length L Ch R = 1 ,8850    ,421,421,421
BEGIN DESCRIPTION:
Stream0718 14.0
END DESCRIPTION:
XS GIS Cut Line= 3
      2442780.23     13670786.39        2441225.       13671525.
      2440125.01     13672524.99
#Sta/Elev= 30
  3273.4  238.31  3343.2  237.88  3436.3  235.14  3453.7   235.1  3710.9  238.92
  3801.5  237.09  3932.9   236.3  4232.6  233.85  4305.3  231.92  4520.9  233.94
  4560.8  231.99  4889.5  234.38  4951.9  232.64  5003.9  231.43  5004.4  230.93
  5014.1  231.43  5108.7  232.47  5274.3  232.72  5351.8  233.38  5384.7  232.04
  5476.6  233.73  5534.5  231.85  5547.4  231.92  5646.2  231.47  5676.5  233.02
  5830.3  235.78  6198.2  248.44  6286.1  254.54  6415.4  260.84  6481.7  262.74
#Mann= 20 ,-1 , 0
  3273.4    .063       0  3343.2     .05       0  3436.3    .063       0
  3453.7     .05       0  3801.5    .035       0  3932.9     .05       0
  4232.6     .07       0  4889.5    .035       0  4951.9    .033       0
  5003.9    .033       0  5014.1    .033       0  5108.7     .07       0
  5274.3    .033       0  5351.8      .1       0  5534.5    .033       0
  5547.4      .1       0  5676.5     .05       0  5830.3     .07       0
  6286.1     .05       0  6415.4     .05       0
Bank Sta=5003.9,5014.1
XS Rating Curve= 0 ,0
Exp/Cntr=0.3,0.1

Type RM Length L Ch R = 1 ,8429    ,462,462,462
BEGIN DESCRIPTION:
Stream0718 13.0
END DESCRIPTION:
XS GIS Cut Line= 3
      2442791.59     13670725.87        2440975.       13671275.
      2440175.01     13672374.98
#Sta/Elev= 30
  3110.8  242.12  3156.9  237.38  3228.1  235.32  3633.1  236.18  3698.6  235.78
  3922.2  233.75  4392.2  231.13  4486.2  233.16  4548.4  232.44  4742.2  232.93
  4845.9  231.35    4987  230.97  4987.5  230.47  4997.2  230.97  5115.6  232.36
  5159.6  232.56  5257.9  231.88  5394.6  233.21    5432  231.68  5517.5  231.69
  5630.3  231.75  5756.1  232.06  5875.4  234.47  5929.1  237.77  6083.2  243.13
    6169  248.54  6260.9  256.56  6323.9   258.7  6364.4  260.59  6368.7  260.69
#Mann= 20 ,-1 , 0
  3110.8     .05       0  3633.1    .035       0  3698.6     .05       0
  3922.2     .07       0  4548.4    .033       0  4742.2    .035       0
  4845.9    .033       0    4987    .033       0  4997.2    .033       0
  5115.6     .15       0  5159.6     .07       0  5257.9      .1       0
    5432     .07       0  5517.5    .033       0  5630.3    .033       0
  5756.1     .07       0  5875.4     .05       0  5929.1     .07       0
  6323.9     .05       0  6364.4     .07       0
Bank Sta=4987,4997.2
XS Rating Curve= 0 ,0
Exp/Cntr=0.3,0.1

Type RM Length L Ch R = 1 ,7967    ,461,461,461
BEGIN DESCRIPTION:
Stream0718 12.0
END DESCRIPTION:
XS GIS Cut Line= 4
      2442787.79     13670703.19      2441731.23     13670668.35
        2440875.       13670875.      2440024.99     13672275.02
#Sta/Elev= 30
  3057.2  240.76  3210.1  234.73  3580.3  236.57  3711.5  233.78  3940.5  232.52
  4020.5  235.44  4147.1   232.4    4239  229.76  4239.5  229.26  4249.3  229.76
  4276.2  231.63  4367.6  232.83  4408.8  230.85  4458.7  234.31  4617.8  230.94
  4719.8  232.31  4731.9  232.24  4821.7  230.09  4923.6  232.37  5053.6   230.4
  5315.6  233.13  5481.9   231.3  5696.2  232.43  5888.7  231.84  6036.3  231.44
  6147.2  234.26  6274.7  238.71  6447.7  245.89  6501.2  249.54    6633  256.02
#Mann= 19 ,-1 , 0
  3057.2     .05       0  3711.5     .07       0  4147.1    .033       0
    4239     .05       0  4249.3    .033       0  4276.2     .07       0
  4617.8    .035       0  4719.8     .07       0  4731.9    .035       0
  4821.7    .033       0  4923.6     .15       0  5315.6     .07       0
  5481.9      .1       0  5696.2    .035       0  5888.7    .033       0
  6147.2     .07       0  6274.7     .05       0  6447.7     .07       0
  6501.2     .05       0
Bank Sta=4239,4249.3
XS Rating Curve= 0 ,0
Exp/Cntr=0.3,0.1

Type RM Length L Ch R = 1 ,7506    ,446,446,446
BEGIN DESCRIPTION:
Stream0718 11.0
END DESCRIPTION:
XS GIS Cut Line= 3
        2442775.       13670675.        2440775.       13670475.
      2438774.95       13670275.
#Sta/Elev= 30
  2990.4  239.85  3131.1  234.81  3472.8  236.45  3697.2  232.95  3804.4  232.61
  3854.7  234.84  4095.4  231.64  4212.4   231.9  4306.9  230.62  4357.8  232.64
  4369.6  232.72  4445.1  230.29  4618.5  233.08  4663.8  231.09  4983.1   229.3
  5312.6  230.37  5411.3  230.38  5509.9  230.48  5608.5   230.6  5707.1  230.68
  5764.2  231.32    5847  228.74  5847.5  228.24  5857.3  228.74  5866.8  229.21
  6226.5  235.85  6266.7  234.55  6417.4  238.29  6688.8  240.59  7010.4  248.65
#Mann= 16 ,-1 , 0
  2990.4     .05       0  3697.2     .07       0  4095.4    .033       0
  4212.4     .07       0  4357.8     .05       0  4369.6     .07       0
  4663.8    .035       0  4983.1    .033       0  5312.6     .15       0
  5411.3    .033       0  5509.9     .15       0  5608.5    .035       0
  5707.1      .1       0    5847    .033       0  5857.3      .1       0
  5866.8     .05       0
Bank Sta=5847,5857.3
XS Rating Curve= 0 ,0
Exp/Cntr=0.3,0.1

Type RM Length L Ch R = 1 ,7060    ,447,447,447
BEGIN DESCRIPTION:
Stream0718 10.0
END DESCRIPTION:
XS GIS Cut Line= 3
      2442524.99       13670275.        2440725.       13670075.
      2438724.96       13670075.
#Sta/Elev= 30
  3184.4  235.73  3405.7  233.15  3727.7  233.74  3908.8  231.32  3959.1  232.45
  4033.6  230.71  4160.6  231.05  4259.3  230.19  4311.3  231.64  4381.7  229.92
  4433.9  230.48  4723.8  231.66  4834.5  233.74    4915  231.78  4945.2  228.82
  4980.2  228.17  4980.7  227.67  4990.7  228.17  5015.5  229.24  5044.9  228.29
  5268.9  229.11    5344  229.07  5442.4  229.44  5540.8   229.7  5705.5  230.62
  5836.1  229.65  6595.5  239.27  6851.9  247.89  6925.5  250.76  6995.5  251.25
#Mann= 14 ,-1 , 0
  3184.4     .05       0  4033.6     .15       0  4160.6     .07       0
  4259.3     .05       0  4433.9     .07       0  4980.2     .05       0
  4990.7     .07       0  5044.9     .15       0  5268.9      .1       0
    5344     .15       0  5442.4    .033       0  5540.8     .15       0
  5836.1     .05       0  6851.9     .07       0
Bank Sta=4980.2,4990.7
XS Rating Curve= 0 ,0
Exp/Cntr=0.3,0.1