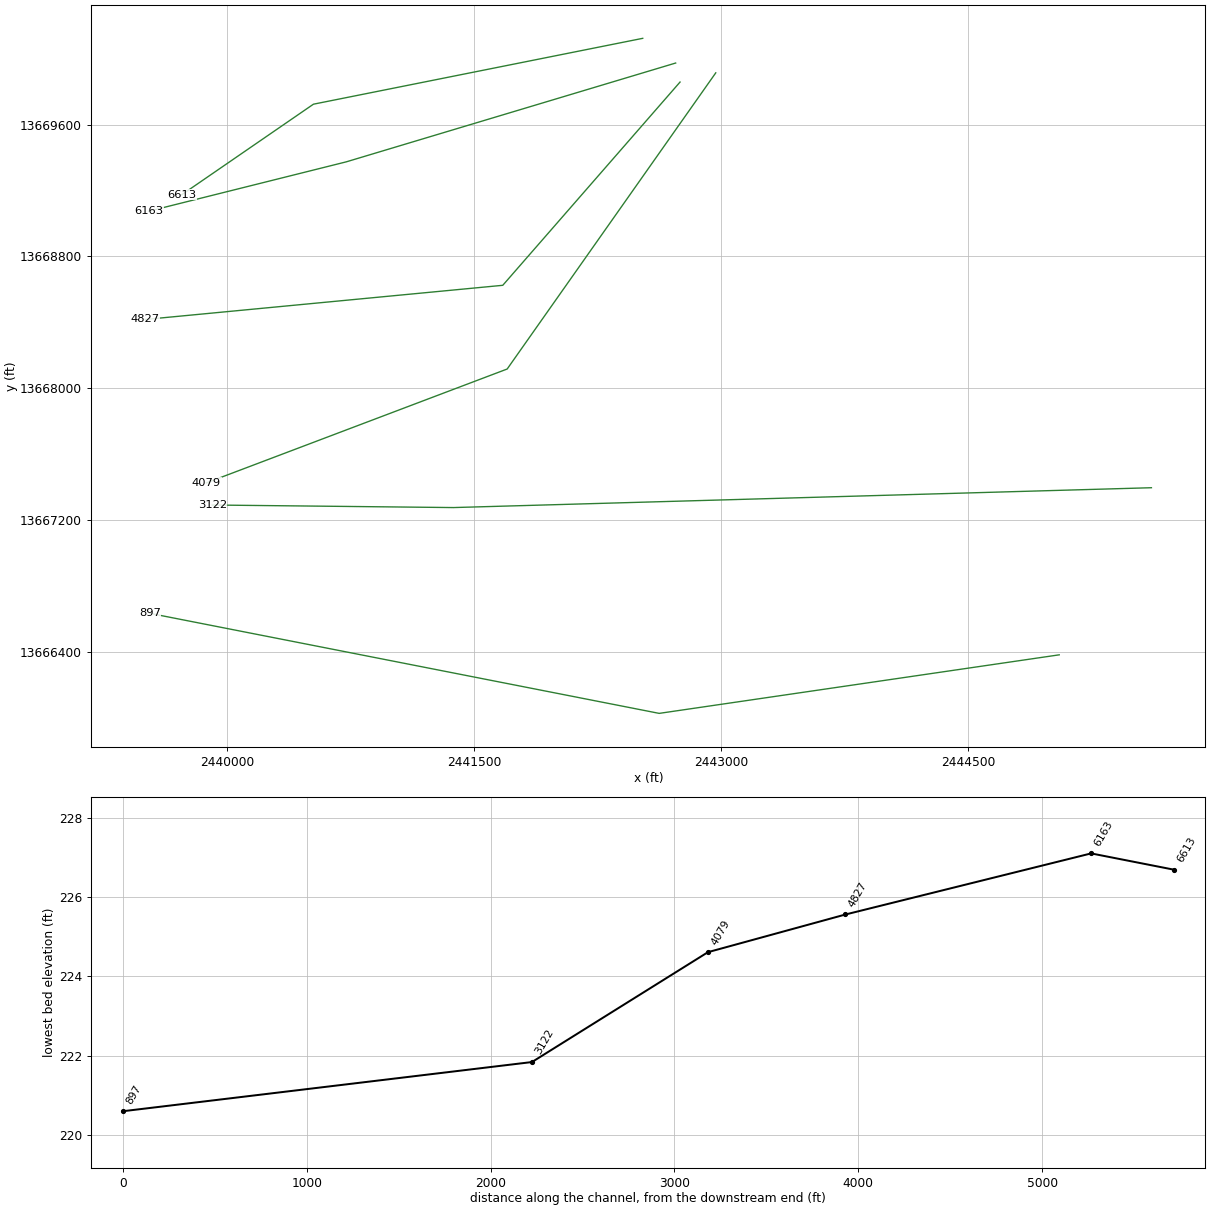
HEC-RAS study Stream0718.prj: Stream0718 Base Level Engineering

--- Stream0718.g01 (geometry) --- (continued)

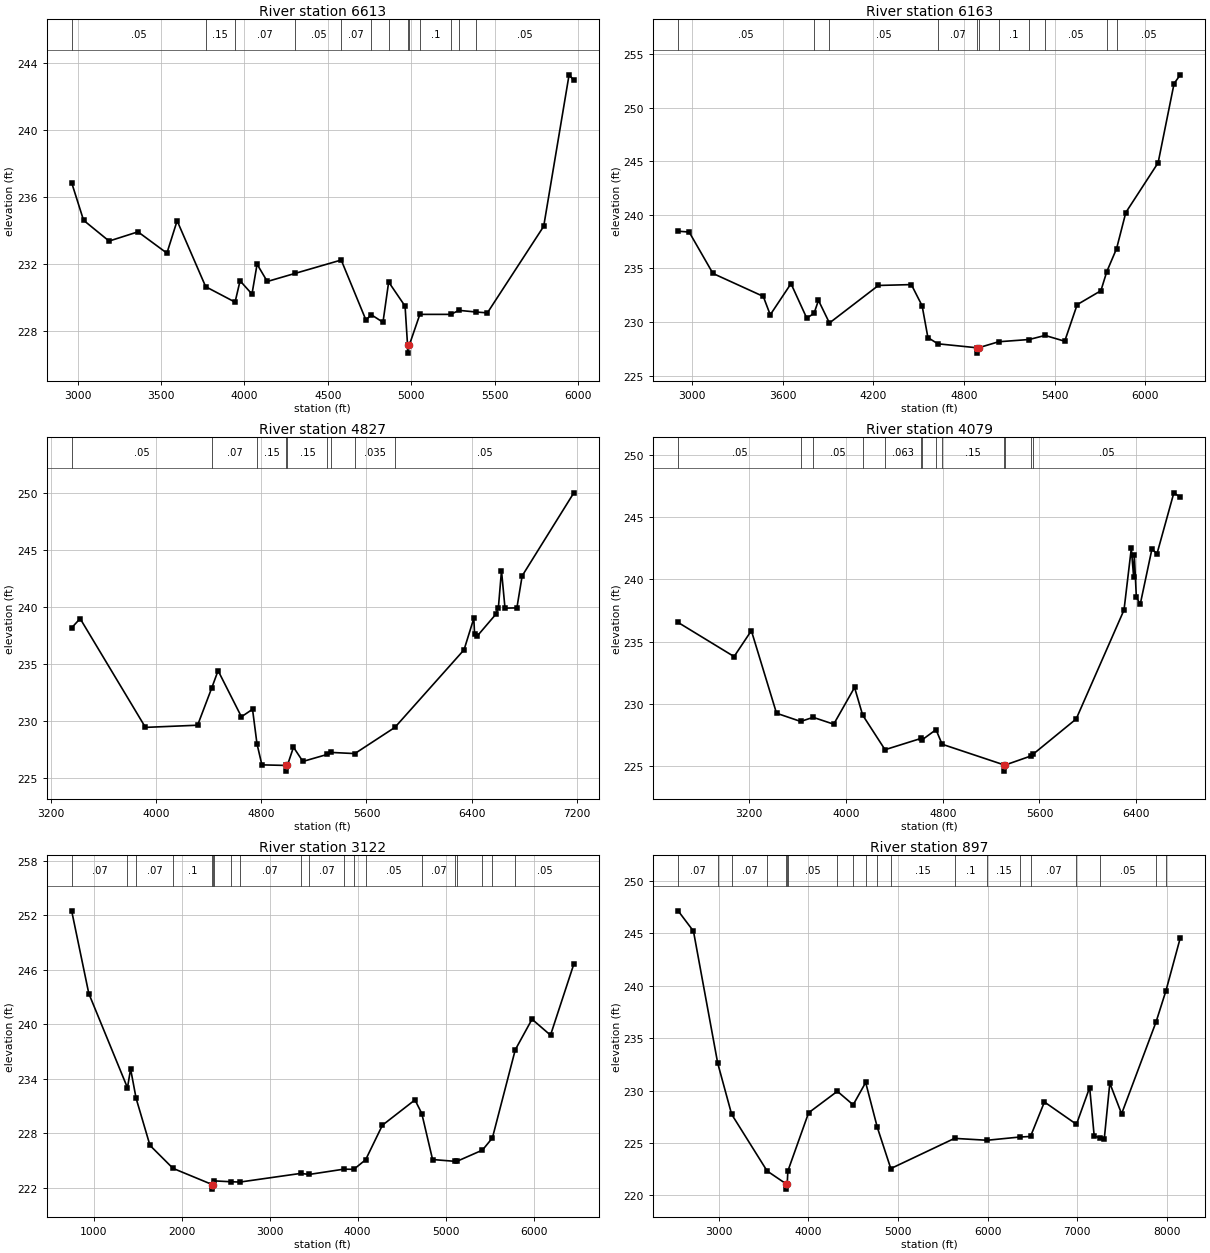
Type RM Length L Ch R = 1 ,6613    ,450,450,450
BEGIN DESCRIPTION:
Stream0718 9.0
END DESCRIPTION:
XS GIS Cut Line= 3
      2442525.02       13670125.        2440525.       13669725.
      2439724.96     13669174.97
#Sta/Elev= 30
  2964.6  236.85    3036  234.61    3189  233.37  3362.3  233.92  3535.7  232.65
  3596.9  234.58  3768.1  230.65  3944.2  229.73  3974.2     231  4045.6  230.21
  4076.2  231.99  4137.4  230.96  4306.4  231.45  4580.5  232.24  4728.9  228.66
  4760.7  228.98  4830.9  228.53    4865  230.93  4963.4  229.49  4978.1  227.19
  4978.6  226.69  4989.5  227.19    5052     229  5237.9     229  5286.2  229.24
  5390.1  229.14  5456.8  229.09  5794.4  234.25  5946.6  243.28  5975.1  242.95
#Mann= 13 ,-1 , 0
  2964.6     .05       0  3768.1     .15       0  3944.2     .07       0
  4306.4     .05       0  4580.5     .07       0  4760.7     .15       0
    4865     .07       0  4978.1     .05       0  4989.5     .07       0
    5052      .1       0  5237.9     .05       0  5286.2      .1       0
  5390.1     .05       0
Bank Sta=4978.1,4989.5
XS Rating Curve= 0 ,0
Exp/Cntr=0.3,0.1

Type RM Length L Ch R = 1 ,6163    ,1336,1336,1336
BEGIN DESCRIPTION:
Stream0718 8.0
END DESCRIPTION:
XS GIS Cut Line= 3
      2442725.01       13669975.        2440725.       13669375.
        2439525.       13669075.
#Sta/Elev= 30
  2907.7  238.47  2980.8  238.39  3138.3  234.53  3471.5  232.39  3517.6  230.67
  3655.1  233.58  3759.5  230.36  3807.7  230.81  3836.9  232.02  3909.6  229.91
  4233.6  233.41    4452  233.49  4523.3  231.51  4561.6  228.55  4627.3  227.97
  4885.7   227.6  4886.2   227.1  4897.1   227.6  5029.8  228.16  5232.1  228.37
  5337.3  228.75  5467.3  228.21  5549.8  231.62    5707  232.92  5745.7  234.69
  5810.9  236.85  5871.9  240.21  6085.8  244.85  6191.5  252.24  6232.7  253.05
#Mann= 11 ,-1 , 0
  2907.7     .05       0  3807.7     .15       0  3909.6     .05       0
  4627.3     .07       0  4885.7     .05       0  4897.1     .07       0
  5029.8      .1       0  5232.1    .035       0  5337.3     .05       0
  5745.7    .035       0  5810.9     .05       0
Bank Sta=4885.7,4897.1
XS Rating Curve= 0 ,0
Exp/Cntr=0.3,0.1

Type RM Length L Ch R = 1 ,4827    ,748,748,748
BEGIN DESCRIPTION:
Stream0718 7.0
END DESCRIPTION:
XS GIS Cut Line= 3
      2442751.69     13669859.52        2441675.       13668625.
      2439503.77     13668417.53
#Sta/Elev= 30
  3357.9  238.14  3422.5  238.95    3919   229.4  4315.8  229.59  4424.6   232.9
  4471.5  234.38    4649  230.33  4733.5  230.99  4767.4  227.96  4804.7  226.11
  4986.9  226.06  4987.4  225.56  4998.5  226.06  5044.9  227.66  5116.5  226.41
  5302.9  227.03  5333.9   227.2  5511.5   227.1  5816.3   229.4  6342.1  236.21
  6416.3  238.97  6422.4  237.57  6442.5  237.42  6583.2  239.32  6603.3  239.92
  6626.9  243.16  6653.5  239.87  6743.9  239.89  6784.1   242.7  7177.1  249.99
#Mann= 9 ,-1 , 0
  3357.9     .05       0  4424.6     .07       0  4767.4     .15       0
  4986.9     .05       0  4998.5     .15       0  5302.9    .035       0
  5333.9     .15       0  5511.5    .035       0  5816.3     .05       0
Bank Sta=4986.9,4998.5
XS Rating Curve= 0 ,0
Exp/Cntr=0.3,0.1

Type RM Length L Ch R = 1 ,4079    ,957,957,957
BEGIN DESCRIPTION:
Stream0718 5.0
END DESCRIPTION:
XS GIS Cut Line= 3
      2442968.65     13669915.48      2441701.69     13668116.53
      2439875.02     13667425.01
#Sta/Elev= 30
  2611.1  236.55    3074  233.81  3216.9  235.89    3425  229.26  3624.8   228.6
    3728  228.93    3898  228.38  4070.4  231.33  4137.4  229.11  4322.5  226.33
  4621.3  227.24  4630.1  227.13  4744.2  227.94  4794.3  226.77  5307.1  225.11
  5307.6  224.61  5318.7  225.11  5527.4  225.82  5549.8  225.99  5903.5   228.8
    6299  237.55  6359.4   242.5  6378.8  240.17  6384.2  241.96  6401.1  238.58
  6433.2  238.01  6529.6  242.43  6572.2  242.08  6711.2  246.96  6764.6  246.61
#Mann= 13 ,-1 , 0
  2611.1     .05       0  3624.8     .07       0    3728     .05       0
  4137.4     .15       0  4322.5    .063       0  4621.3     .15       0
  4630.1    .063       0  4744.2    .035       0  4794.3     .15       0
  5307.1     .05       0  5318.7     .15       0  5527.4     .07       0
  5549.8     .05       0
Bank Sta=5307.1,5318.7
XS Rating Curve= 0 ,0
Exp/Cntr=0.3,0.1

Type RM Length L Ch R = 1 ,3122    ,2225,2225,2225
BEGIN DESCRIPTION:
Stream0718 3.0
END DESCRIPTION:
XS GIS Cut Line= 3
      2445614.61     13667395.55        2441375.       13667275.
      2439909.91     13667290.55
#Sta/Elev= 30
   751.3   252.5   946.2  243.39  1385.5  233.01  1421.2  235.08  1483.8  231.84
  1641.3  226.66  1902.7  224.13  2349.3  222.34  2349.8  221.84  2361.1  222.34
  2370.1  222.75  2565.9  222.65  2664.3  222.62  3352.9  223.57  3451.6  223.46
  3844.8  224.04  3957.5  224.02  4092.2  225.08  4282.3  228.88  4652.5  231.67
  4729.9  230.17  4852.6   225.1  5110.8   224.9  5135.6  224.93  5419.1  226.14
  5532.4  227.48  5792.2  237.19  5982.7  240.56  6192.7   238.8  6457.8  246.64
#Mann= 20 ,-1 , 0
   751.3     .07       0  1385.5    .035       0  1483.8     .07       0
  1902.7      .1       0  2349.3     .05       0  2361.1      .1       0
  2370.1    .035       0  2565.9      .1       0  2664.3     .07       0
  3352.9    .033       0  3451.6     .07       0  3844.8     .05       0
  3957.5    .033       0  4092.2     .05       0  4729.9     .07       0
  5110.8     .15       0  5135.6     .15       0  5419.1     .05       0
  5532.4    .035       0  5792.2     .05       0
Bank Sta=2349.3,2361.1
XS Rating Curve= 0 ,0
Exp/Cntr=0.3,0.1

Type RM Length L Ch R = 1 ,897     ,0,0,0
BEGIN DESCRIPTION:
Stream0718 2.0
END DESCRIPTION:
XS GIS Cut Line= 3
      2445054.61     13666380.56        2442625.       13666025.
      2439531.69     13666632.57
#Sta/Elev= 30
  2544.5  247.14  2715.9   245.2  2986.4  232.62    3142  227.74  3538.3  222.33
  3750.8   221.1  3751.3   220.6  3762.9   221.1  3769.8  222.32  4001.6  227.88
  4322.6  229.93  4499.2  228.64  4638.9  230.77  4769.2  226.48  4919.5  222.56
  5631.2  225.44  5994.4  225.26  6360.6  225.57  6479.6  225.62    6635  228.91
  6992.8  226.78  7140.1  230.29  7191.1  225.64  7252.5  225.52  7303.2  225.38
  7365.1  230.71  7496.8  227.78  7881.9  236.55  7992.5  239.53  8152.4  244.57
#Mann= 20 ,-1 , 0
  2544.5     .07       0  2986.4     .05       0    3142     .07       0
  3538.3      .1       0  3750.8     .05       0  3762.9     .07       0
  3769.8     .05       0  4322.6     .05       0  4499.2    .035       0
  4638.9     .07       0  4769.2     .15       0  4919.5     .15       0
  5631.2      .1       0  5994.4     .15       0  6360.6     .15       0
  6479.6     .07       0  6992.8    .035       0  7252.5     .05       0
  7881.9    .035       0  7992.5     .05       0
Bank Sta=3750.8,3762.9
XS Rating Curve= 0 ,0
Exp/Cntr=0.3,0.1

Chan Stop Cuts=-1
Use User Specified Reach Order=0
Composite Channel Slope=5