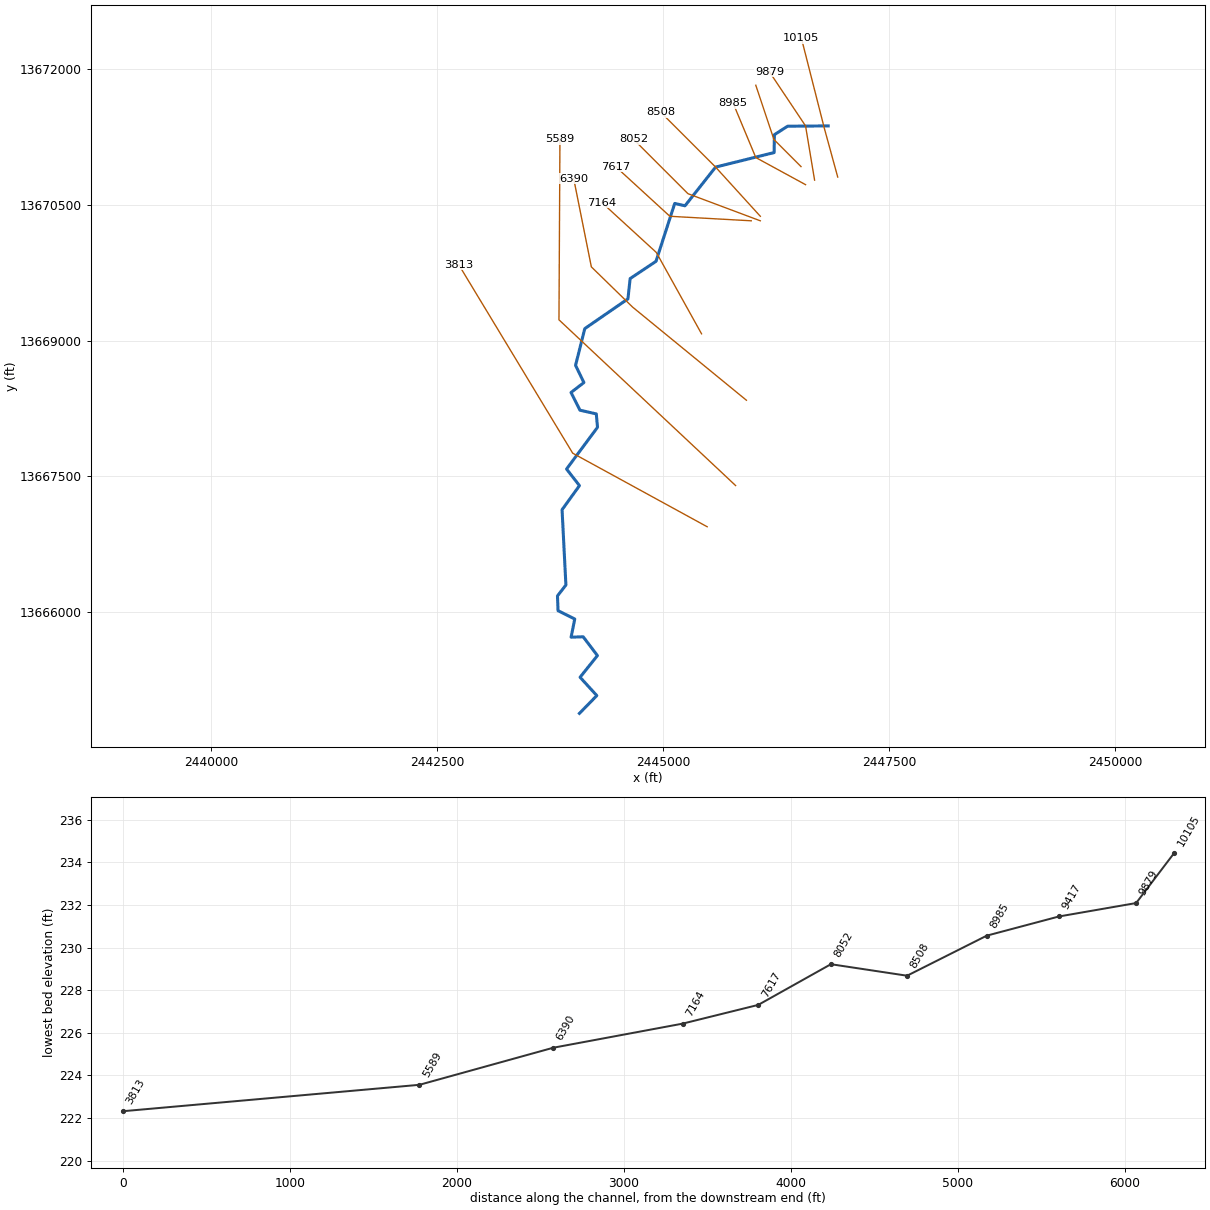
--- Stream0719.prj (project) ---

Proj Title=Stream0719 Base Level Engineering
Current Plan=p01
Default Exp/Contr=0.3,0.1
English Units
Geom File=g01
Flow File=f01
Plan File=p01
BEGIN DESCRIPTION:
Stream0719
END DESCRIPTION:

--- Stream0719.p01 (plan) ---

Plan Title=Multiple Run
Short Identifier=Multiple
Geom File=g01
Flow File=f01
Subcritical Flow
K Sum by GR= 0
Std Step Tol= 0.01
Critical Tol= 0.01
Num of Std Step Trials= 20
Max Error Tol= 0.3
Flow Tol Ratio= 0.001
Split Flow NTrial= 30
Split Flow Tol= 0.02
Split Flow Ratio= 0.02
Log Output Level= 0
Friction Slope Method= 1
Unsteady Friction Slope Method= 2
Unsteady Bridges Friction Slope Method= 1
Parabolic Critical Depth
Global Vel Dist=  1 , 1 , 1
Global Log Level= 0
CheckData=True
Encroach Param= -1, 0, 0, 0
BEGIN DESCRIPTION:
Multiple Run
END DESCRIPTION:

--- Stream0719.f01 (steady flow) ---

Flow Title=Multiple
Number of Profiles=7
Profile Names=10-year,25-year,50-year,1pct_min,100-year,1pct_plu,500-year
River Rch & RM= Stream0719,Reach-1,10105
     483     758     999     637    1272    2537    2040
Boundary for River Rch & Prof#=Stream0719,Reach-1,1
Up Type=0
Dn Type=3
Dn Slope=0.005
Boundary for River Rch & Prof#=Stream0719,Reach-1,2
Up Type=0
Dn Type=3
Dn Slope=0.005
Boundary for River Rch & Prof#=Stream0719,Reach-1,3
Up Type=0
Dn Type=3
Dn Slope=0.005
Boundary for River Rch & Prof#=Stream0719,Reach-1,4
Up Type=0
Dn Type=3
Dn Slope=0.005
Boundary for River Rch & Prof#=Stream0719,Reach-1,5
Up Type=0
Dn Type=3
Dn Slope=0.005
Boundary for River Rch & Prof#=Stream0719,Reach-1,6
Up Type=0
Dn Type=3
Dn Slope=0.005
Boundary for River Rch & Prof#=Stream0719,Reach-1,7
Up Type=0
Dn Type=3
Dn Slope=0.005

--- Stream0719.g01 (geometry) ---

Geom Title=Existing Conditions

River Reach=Stream0719,Reach-1
Reach XY= 30
      2446825.00     13671375.00      2446376.72     13671371.66
      2446230.30     13671277.67      2446227.85     13671080.11
      2445580.62     13670919.38      2445242.15     13670491.12
      2445128.51     13670517.25      2444921.46     13669876.46
      2444635.52     13669685.49      2444611.44     13669461.33
      2444134.01     13669132.06      2444032.23     13668725.29
      2444124.47     13668535.47      2443982.20     13668425.30
      2444080.59     13668229.79      2444261.36     13668188.39
      2444274.99     13668040.36      2443932.59     13667578.33
      2444075.47     13667395.16      2443883.01     13667128.33
      2443925.39     13666295.13      2443832.36     13666175.08
      2443838.37     13666011.21      2444023.47     13665919.17
      2443982.75     13665718.19      2444116.50     13665722.33
      2444274.07     13665514.51      2444081.98     13665274.80
      2444267.23     13665071.59      2444075.00     13664875.00

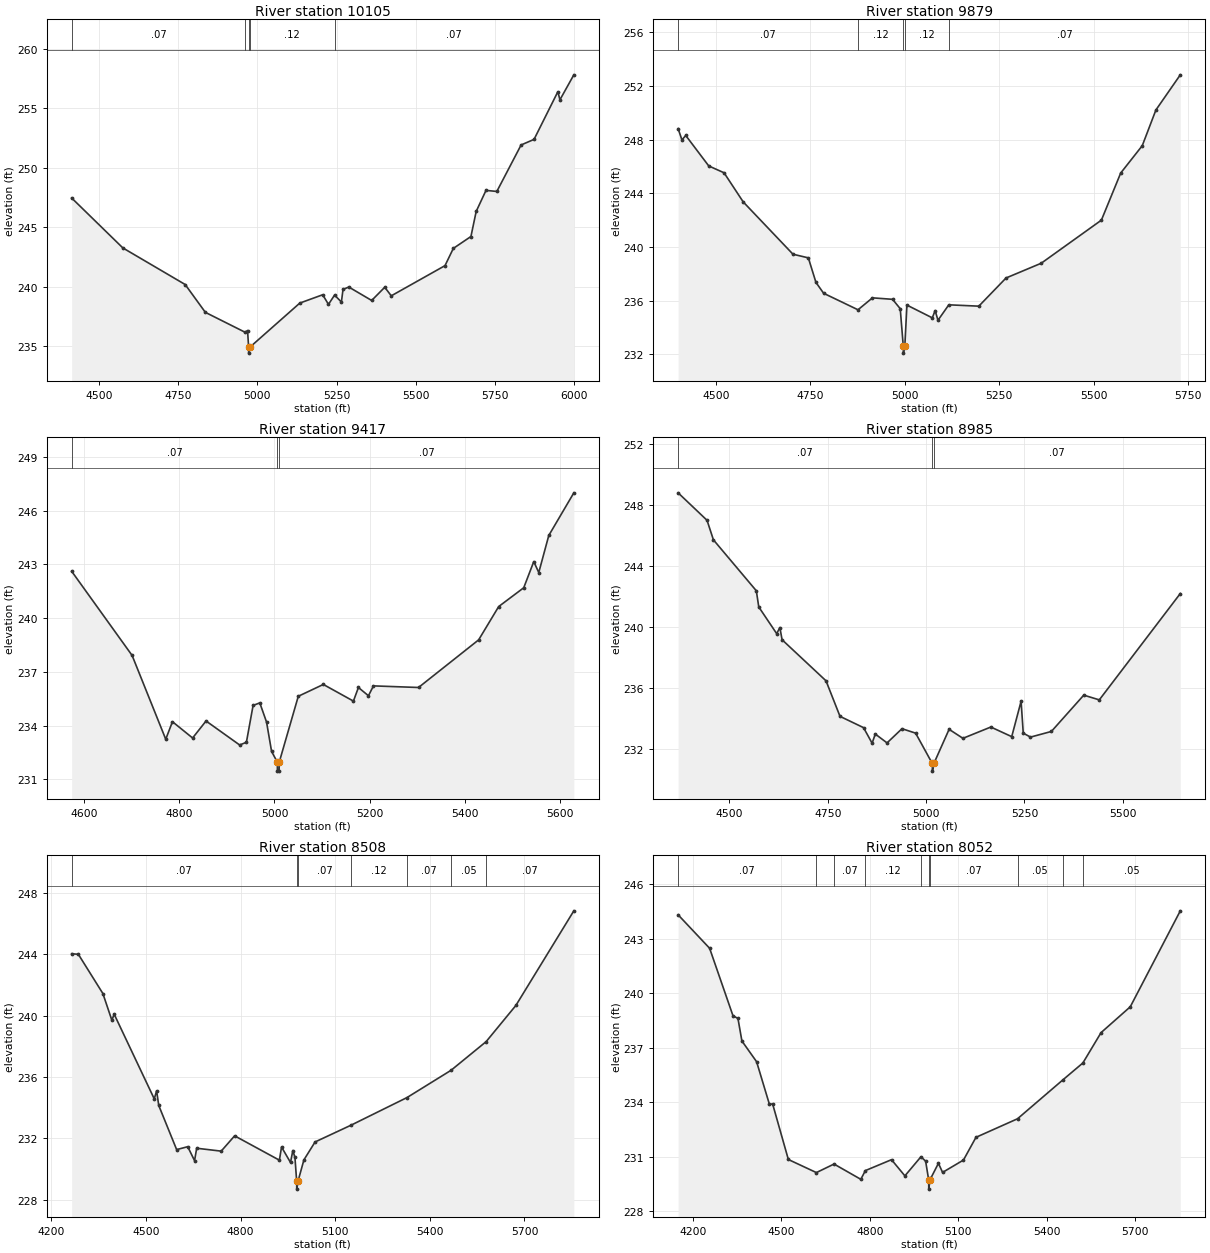
Type RM Length L Ch R = 1,10105,226,226,226
BEGIN DESCRIPTION:
Z21510
END DESCRIPTION:
XS GIS Cut Line= 3
      2446930.72     13670809.07      2446782.30     13671350.37
      2446529.54     13672343.95
#Sta/Elev= 30
  4413.2  247.47  4574.9  243.27  4771.9  240.19  4835.6  237.85  4961.6  236.17
  4968.9  236.32  4972.3  234.92  4972.5  234.42  4976.3  234.92  5134.0  238.63
  5206.3  239.33  5224.5  238.52  5243.8  239.30  5265.4  238.72  5270.5  239.78
  5288.8  239.98  5361.0  238.85  5402.3  239.96  5422.9  239.24  5592.7  241.78
  5619.0  243.23  5674.6  244.23  5691.2  246.34  5722.2  248.11  5756.4  248.02
  5833.1  251.93  5874.0  252.40  5949.2  256.41  5955.8  255.73  5999.7  257.83
#Mann=5,-1,0
  4413.2    0.07       0  4961.6    0.12       0  4972.3    0.05       0
  4976.3    0.12       0  5243.8    0.07       0
Bank Sta=4972.3,4976.3
Exp/Cntr=0.3,0.1

Type RM Length L Ch R = 1,9879,462,462,462
BEGIN DESCRIPTION:
Stream0719 16.0
END DESCRIPTION:
XS GIS Cut Line= 3
      2446674.99     13670775.03      2446575.00     13671375.00
      2446174.98     13671975.04
#Sta/Elev= 30
  4399.9  248.82  4410.0  247.98  4420.1  248.31  4481.0  246.04  4521.5  245.53
  4572.2  243.36  4704.0  239.46  4744.6  239.19  4764.8  237.36  4785.1  236.55
  4876.1  235.32  4914.4  236.21  4967.6  236.10  4987.9  235.40  4996.0  232.59
  4996.3  232.09  5000.0  232.59  5005.6  235.67  5072.7  234.72  5080.3  235.26
  5087.8  234.54  5116.5  235.69  5195.9  235.59  5268.0  237.69  5361.2  238.79
  5520.4  242.00  5571.5  245.51  5628.6  247.55  5664.7  250.21  5729.3  252.83
#Mann=5,-1,0
  4399.9    0.07       0  4876.1    0.12       0  4996.0    0.05       0
  5000.0    0.12       0  5116.5    0.07       0
Bank Sta=4996,5000
Exp/Cntr=0.3,0.1

Type RM Length L Ch R = 1,9417,432,432,432
BEGIN DESCRIPTION:
Stream0719 15.0
END DESCRIPTION:
XS GIS Cut Line= 3
      2446524.98     13670925.02      2446225.00     13671225.00
      2446025.00     13671825.01
#Sta/Elev= 30
  4573.2  242.62  4700.4  237.92  4771.2  233.24  4785.3  234.22  4827.7  233.31
  4856.0  234.26  4926.7  232.92  4940.9  233.07  4955.0  235.13  4969.1  235.27
  4983.3  234.20  4993.9  232.56  5006.0  231.96  5006.2  231.46  5009.7  231.46
  5010.0  231.96  5050.1  235.64  5102.8  236.30  5166.1  235.37  5176.6  236.13
  5197.7  235.67  5208.3  236.22  5303.1  236.13  5429.6  238.79  5471.8  240.65
  5524.5  241.70  5545.6  243.16  5556.1  242.55  5577.2  244.62  5629.9  247.00
#Mann=3,-1,0
  4573.2    0.07       0  5006.0    0.05       0  5010.0    0.07       0
Bank Sta=5006,5010
Exp/Cntr=0.3,0.1

Type RM Length L Ch R = 1,8985,477,477,477
BEGIN DESCRIPTION:
Stream0719 14.0
END DESCRIPTION:
XS GIS Cut Line= 3
      2446574.97     13670725.01      2446025.00     13671025.00
      2445774.99     13671625.03
#Sta/Elev= 30
  4369.6  248.80  4443.1  247.00  4459.3  245.72  4568.4  242.38  4574.6  241.32
  4620.2  239.57  4628.2  239.97  4633.9  239.17  4745.5  236.48  4781.1  234.15
  4840.9  233.41  4862.7  232.39  4870.8  232.99  4900.7  232.41  4938.6  233.34
  4973.3  233.05  5015.7  231.06  5016.0  230.56  5019.7  231.06  5058.4  233.30
  5093.6  232.71  5164.5  233.45  5217.6  232.82  5241.4  235.14  5246.9  233.05
  5265.3  232.79  5318.4  233.16  5400.7  235.54  5440.2  235.23  5646.1  242.20
#Mann=3,-1,0
  4369.6    0.07       0  5015.7    0.05       0  5019.7    0.07       0
Bank Sta=5015.7,5019.7
Exp/Cntr=0.3,0.1

Type RM Length L Ch R = 1,8508,456,456,456
BEGIN DESCRIPTION:
Stream0719 13.0
END DESCRIPTION:
XS GIS Cut Line= 3
      2446075.01     13670374.99      2445575.00     13670925.00
      2444975.03     13671524.97
#Sta/Elev= 30
  4264.7  244.05  4286.0  244.01  4363.7  241.45  4392.1  239.71  4399.5  240.10
  4526.6  234.57  4534.0  235.10  4540.8  234.14  4597.5  231.26  4632.6  231.45
  4654.3  230.54  4661.0  231.35  4738.7  231.16  4781.3  232.16  4923.2  230.57
  4930.0  231.43  4958.4  230.42  4965.8  231.20  4972.5  230.75  4978.0  229.18
  4978.2  228.68  4982.0  229.18  5000.9  230.59  5036.3  231.76  5150.8  232.86
  5327.8  234.66  5467.4  236.44  5578.5  238.31  5672.7  240.67  5856.5  246.85
#Mann=7,-1,0
  4264.7    0.07       0  4978.0    0.05       0  4982.0    0.07       0
  5150.8    0.12       0  5327.8    0.07       0  5467.4    0.05       0
  5578.5    0.07       0
Bank Sta=4978,4982
Exp/Cntr=0.3,0.1

Type RM Length L Ch R = 1,8052,435,435,435
BEGIN DESCRIPTION:
Stream0719 12.0
END DESCRIPTION:
XS GIS Cut Line= 3
      2446075.01     13670324.99      2445275.00     13670625.00
      2444675.03     13671224.97
#Sta/Elev= 30
  4149.5  244.31  4256.3  242.47  4335.5  238.76  4352.4  238.61  4365.8  237.37
  4415.6  236.23  4459.2  233.88  4469.9  233.91  4523.3  230.85  4618.4  230.13
  4678.2  230.60  4769.0  229.76  4784.5  230.24  4873.1  230.84  4918.5  229.95
  4972.9  231.00  4988.8  230.76  4999.2  229.72  4999.5  229.22  5003.2  229.72
  5032.2  230.64  5046.3  230.14  5117.1  230.82  5159.5  232.07  5300.4  233.09
  5454.9  235.24  5522.0  236.16  5583.7  237.83  5682.7  239.25  5852.4  244.53
#Mann=10,-1,0
  4149.5    0.07       0  4618.4    0.12       0  4678.2    0.07       0
  4784.5    0.12       0  4972.9    0.07       0  4999.2    0.05       0
  5003.2    0.07       0  5300.4    0.05       0  5454.9    0.07       0
  5522.0    0.05       0
Bank Sta=4999.2,5003.2
Exp/Cntr=0.3,0.1

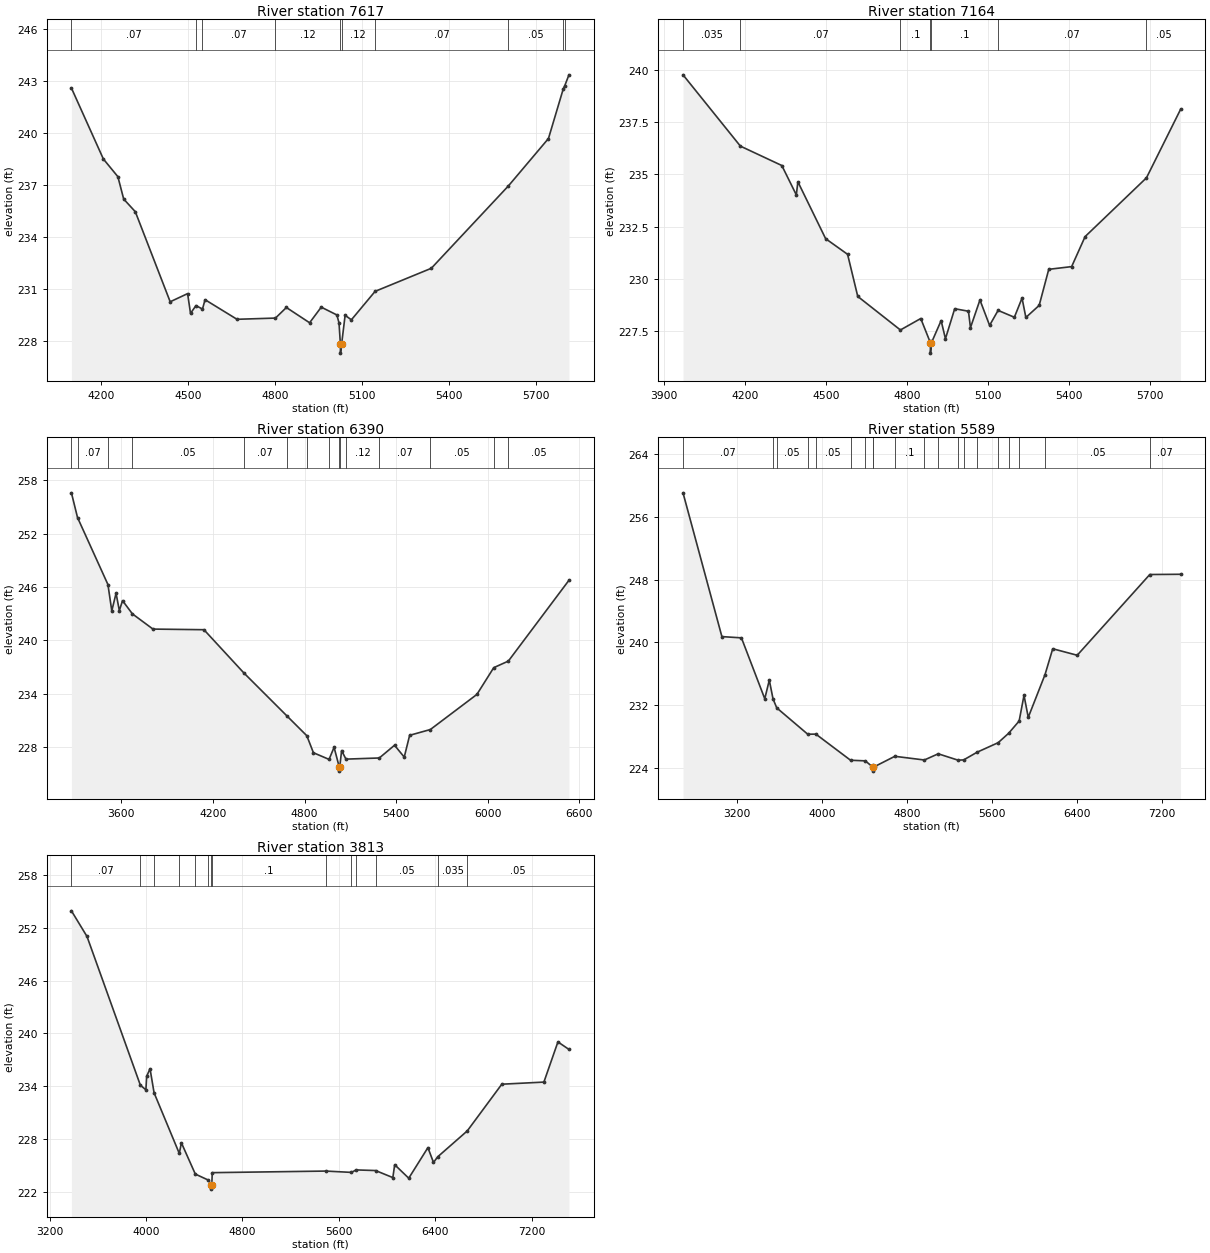
Type RM Length L Ch R = 1,7617,453,453,453
BEGIN DESCRIPTION:
Stream0719 11.0
END DESCRIPTION:
XS GIS Cut Line= 3
      2445974.95     13670325.00      2445075.00     13670375.00
      2444474.99     13670925.01
#Sta/Elev= 30
  4098.2  242.59  4208.3  238.50  4258.4  237.48  4278.4  236.19  4318.5  235.46
  4438.7  230.27  4498.8  230.74  4508.8  229.60  4527.6  230.05  4550.1  229.85
  4558.9  230.39  4669.0  229.26  4801.7  229.33  4839.3  229.94  4919.4  229.06
  4959.5  229.96  5013.4  229.51  5020.8  229.05  5025.6  227.81  5025.8  227.31
  5029.6  227.81  5041.8  229.49  5063.4  229.23  5145.2  230.87  5339.0  232.20
  5604.9  236.95  5742.9  239.68  5794.1  242.55  5798.8  242.71  5813.5  243.35
#Mann=10,-1,0
  4098.2    0.07       0  4527.6    0.12       0  4550.1    0.07       0
  4801.7    0.12       0  5025.6    0.05       0  5029.6    0.12       0
  5145.2    0.07       0  5604.9    0.05       0  5794.1    0.07       0
  5798.8    0.05       0
Bank Sta=5025.6,5029.6
Exp/Cntr=0.3,0.1

Type RM Length L Ch R = 1,7164,774,774,774
BEGIN DESCRIPTION:
Stream0719 10.0
END DESCRIPTION:
XS GIS Cut Line= 3
      2445425.02     13669074.97      2444925.00     13669975.00
      2444325.03     13670524.97
#Sta/Elev= 30
  3970.4  239.78  4183.0  236.36  4336.5  235.43  4390.3  234.02  4396.0  234.65
  4498.9  231.92  4580.2  231.17  4617.9  229.15  4775.9  227.54  4851.3  228.09
  4887.0  226.93  4887.3  226.43  4891.0  226.93  4926.8  227.99  4942.8  227.12
  4977.1  228.56  5028.1  228.44  5035.5  227.65  5070.6  228.98  5106.4  227.76
  5137.9  228.48  5198.2  228.15  5226.6  229.07  5240.8  228.14  5290.1  228.72
  5325.6  230.45  5410.4  230.58  5460.3  232.02  5687.7  234.84  5813.9  238.12
#Mann=7,-1,0
  3970.4   0.035       0  4183.0    0.07       0  4775.9     0.1       0
  4887.0    0.05       0  4891.0     0.1       0  5137.9    0.07       0
  5687.7    0.05       0
Bank Sta=4887,4891
Exp/Cntr=0.3,0.1

Type RM Length L Ch R = 1,6390,801,801,801
BEGIN DESCRIPTION:
XS7538
END DESCRIPTION:
XS GIS Cut Line= 4
      2445921.19     13668339.74      2444662.54     13669370.53
      2444206.81     13669815.41      2444011.71     13670790.95
#Sta/Elev= 30
  3273.0  256.61  3313.0  253.83  3512.2  246.29  3537.4  243.33  3565.4  245.31
  3586.9  243.36  3607.7  244.48  3672.6  242.99  3807.2  241.28  4141.0  241.21
  4400.6  236.38  4684.5  231.51  4814.8  229.28  4858.0  227.37  4960.4  226.62
  4993.3  227.98  5026.6  225.80  5026.8  225.30  5030.6  225.80  5042.7  227.61
  5071.1  226.65  5289.6  226.78  5389.2  228.21  5452.9  226.88  5488.2  229.33
  5623.9  229.98  5928.7  233.93  6039.0  236.94  6134.8  237.68  6531.6  246.77
#Mann=15,-1,0
  3273.0    0.12       0  3313.0    0.07       0  3512.2   0.035       0
  3672.6    0.05       0  4400.6    0.07       0  4684.5    0.05       0
  4814.8    0.07       0  4960.4     0.1       0  5026.6    0.05       0
  5030.6     0.1       0  5071.1    0.12       0  5289.6    0.07       0
  5623.9    0.05       0  6039.0   0.035       0  6134.8    0.05       0
Bank Sta=5026.6,5030.6
Exp/Cntr=0.3,0.1

Type RM Length L Ch R = 1,5589,1776,1776,1776
BEGIN DESCRIPTION:
XS7537
END DESCRIPTION:
XS GIS Cut Line= 3
      2445801.89     13667395.68      2443848.74     13669229.47
      2443859.59     13671226.04
#Sta/Elev= 30
  2696.3  259.06  3061.7  240.72  3245.4  240.56  3464.7  232.79  3507.2  235.17
  3542.2  232.78  3577.1  231.63  3868.3  228.27  3945.1  228.28  4270.7  224.95
  4409.4  224.87  4481.5  224.06  4481.8  223.56  4485.5  224.06  4686.9  225.45
  4964.3  224.98  5094.8  225.77  5280.5  224.96  5333.5  224.99  5461.2  225.98
  5658.2  227.19  5756.7  228.39  5855.2  229.95  5900.9  233.23  5940.9  230.42
  6098.4  235.87  6170.9  239.17  6400.9  238.34  7083.1  248.64  7372.0  248.67
#Mann=20,-1,0
  2696.3    0.07       0  3542.2   0.035       0  3577.1    0.05       0
  3868.3   0.035       0  3945.1    0.05       0  4270.7    0.07       0
  4409.4     0.1       0  4481.5    0.05       0  4485.5     0.1       0
  4686.9     0.1       0  4964.3    0.05       0  5094.8    0.05       0
  5280.5   0.035       0  5333.5    0.05       0  5461.2   0.035       0
  5658.2    0.05       0  5756.7   0.035       0  5855.2   0.063       0
  6098.4    0.05       0  7083.1    0.07       0
Bank Sta=4481.5,4485.5
Exp/Cntr=0.3,0.1

Type RM Length L Ch R = 1,3813,0,0,0
BEGIN DESCRIPTION:
XS7536
END DESCRIPTION:
XS GIS Cut Line= 3
      2445487.21     13666939.96      2444000.65     13667753.78
      2442741.96     13669837.12
#Sta/Elev= 30
  3381.4  253.91  3510.7  251.00  3953.5  234.12  3999.5  233.59  4005.7  235.12
  4033.7  235.99  4067.5  233.25  4276.7  226.37  4294.0  227.58  4409.5  224.03
  4516.7  223.35  4542.4  222.82  4542.6  222.32  4546.4  222.82  4550.1  224.19
  5492.8  224.37  5705.6  224.22  5743.3  224.50  5905.4  224.43  6048.7  223.63
  6064.2  225.09  6180.7  223.56  6339.8  227.03  6386.1  225.35  6422.0  226.00
  6666.5  228.93  6953.0  234.23  7302.3  234.47  7418.7  239.03  7510.2  238.18
#Mann=14,-1,0
  3381.4    0.07       0  3953.5   0.035       0  4067.5    0.07       0
  4276.7   0.035       0  4409.5    0.07       0  4516.7     0.1       0
  4542.4    0.05       0  4546.4     0.1       0  5492.8    0.12       0
  5705.6     0.1       0  5743.3    0.12       0  5905.4    0.05       0
  6422.0   0.035       0  6666.5    0.05       0
Bank Sta=4542.4,4546.4
Exp/Cntr=0.3,0.1

Chan Stop Cuts=-1