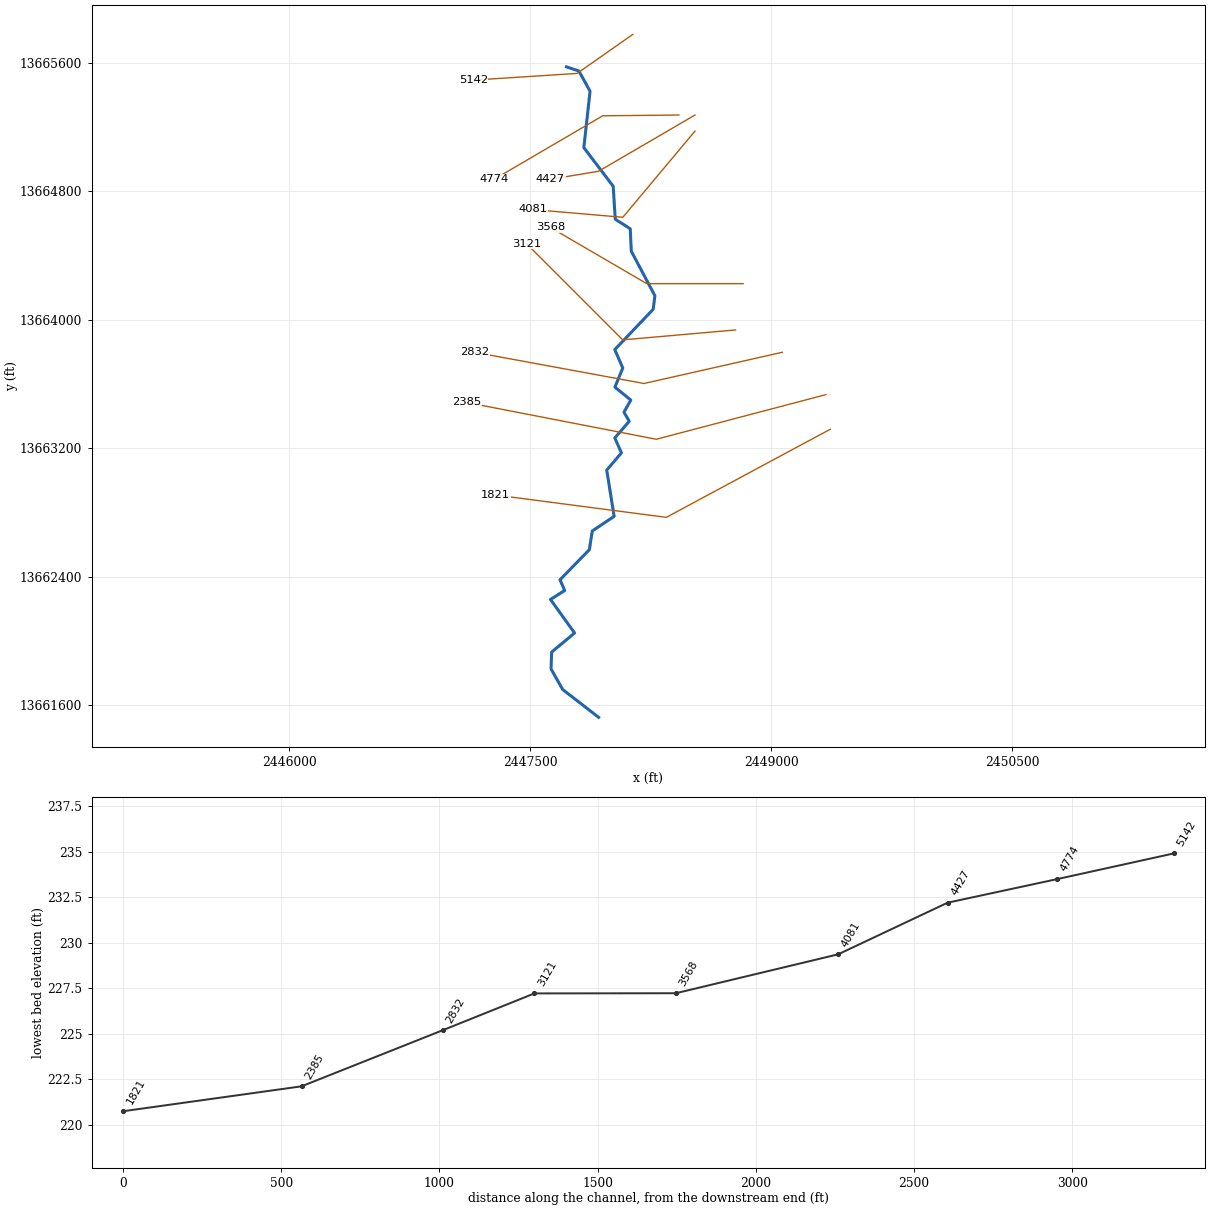
--- Stream0720.prj (project) ---

Proj Title=Stream0720 Base Level Engineering
Current Plan=p01
Default Exp/Contr=0.3,0.1
English Units
Geom File=g01
Flow File=f01
Plan File=p01
BEGIN DESCRIPTION:
Stream0720
END DESCRIPTION:

--- Stream0720.p01 (plan) ---

Plan Title=Multiple Run
Short Identifier=Multiple
Geom File=g01
Flow File=f01
Subcritical Flow
K Sum by GR= 0
Std Step Tol= 0.01
Critical Tol= 0.01
Num of Std Step Trials= 20
Max Error Tol= 0.3
Flow Tol Ratio= 0.001
Split Flow NTrial= 30
Split Flow Tol= 0.02
Split Flow Ratio= 0.02
Log Output Level= 0
Friction Slope Method= 1
Unsteady Friction Slope Method= 2
Unsteady Bridges Friction Slope Method= 1
Parabolic Critical Depth
Global Vel Dist=  1 , 1 , 1
Global Log Level= 0
CheckData=True
Encroach Param= -1, 0, 0, 0
BEGIN DESCRIPTION:
Multiple Run
END DESCRIPTION:

--- Stream0720.f01 (steady flow) ---

Flow Title=Multiple
Number of Profiles=7
Profile Names=10-year,25-year,50-year,1pct_min,100-year,1pct_plu,500-year
River Rch & RM= Stream0720,Reach-1,5142
     443     692     911     580    1158    2311    1854
Boundary for River Rch & Prof#=Stream0720,Reach-1,1
Up Type=0
Dn Type=3
Dn Slope=0.005
Boundary for River Rch & Prof#=Stream0720,Reach-1,2
Up Type=0
Dn Type=3
Dn Slope=0.005
Boundary for River Rch & Prof#=Stream0720,Reach-1,3
Up Type=0
Dn Type=3
Dn Slope=0.005
Boundary for River Rch & Prof#=Stream0720,Reach-1,4
Up Type=0
Dn Type=3
Dn Slope=0.005
Boundary for River Rch & Prof#=Stream0720,Reach-1,5
Up Type=0
Dn Type=3
Dn Slope=0.005
Boundary for River Rch & Prof#=Stream0720,Reach-1,6
Up Type=0
Dn Type=3
Dn Slope=0.005
Boundary for River Rch & Prof#=Stream0720,Reach-1,7
Up Type=0
Dn Type=3
Dn Slope=0.005

--- Stream0720.g01 (geometry) ---

Geom Title=Existing Conditions

River Reach=Stream0720,Reach-1
Reach XY= 30
      2447725.00     13665575.00      2447802.28     13665548.85
      2447871.63     13665423.27      2447833.04     13665071.68
      2448015.70     13664831.67      2448028.55     13664626.30
      2448121.89     13664566.68      2448128.56     13664426.48
      2448275.41     13664150.00      2448264.57     13664065.21
      2448025.60     13663814.38      2448075.38     13663700.00
      2448026.57     13663580.86      2448125.43     13663500.08
      2448082.85     13663424.94      2448115.68     13663368.34
      2448025.66     13663264.36      2448067.16     13663171.60
      2447975.61     13663064.38      2448021.55     13662776.25
      2447885.39     13662685.10      2447867.25     13662568.55
      2447684.59     13662381.54      2447713.83     13662314.70
      2447625.20     13662258.96      2447775.63     13662049.92
      2447632.64     13661931.45      2447628.67     13661826.59
      2447701.29     13661698.18      2447925.00     13661525.00

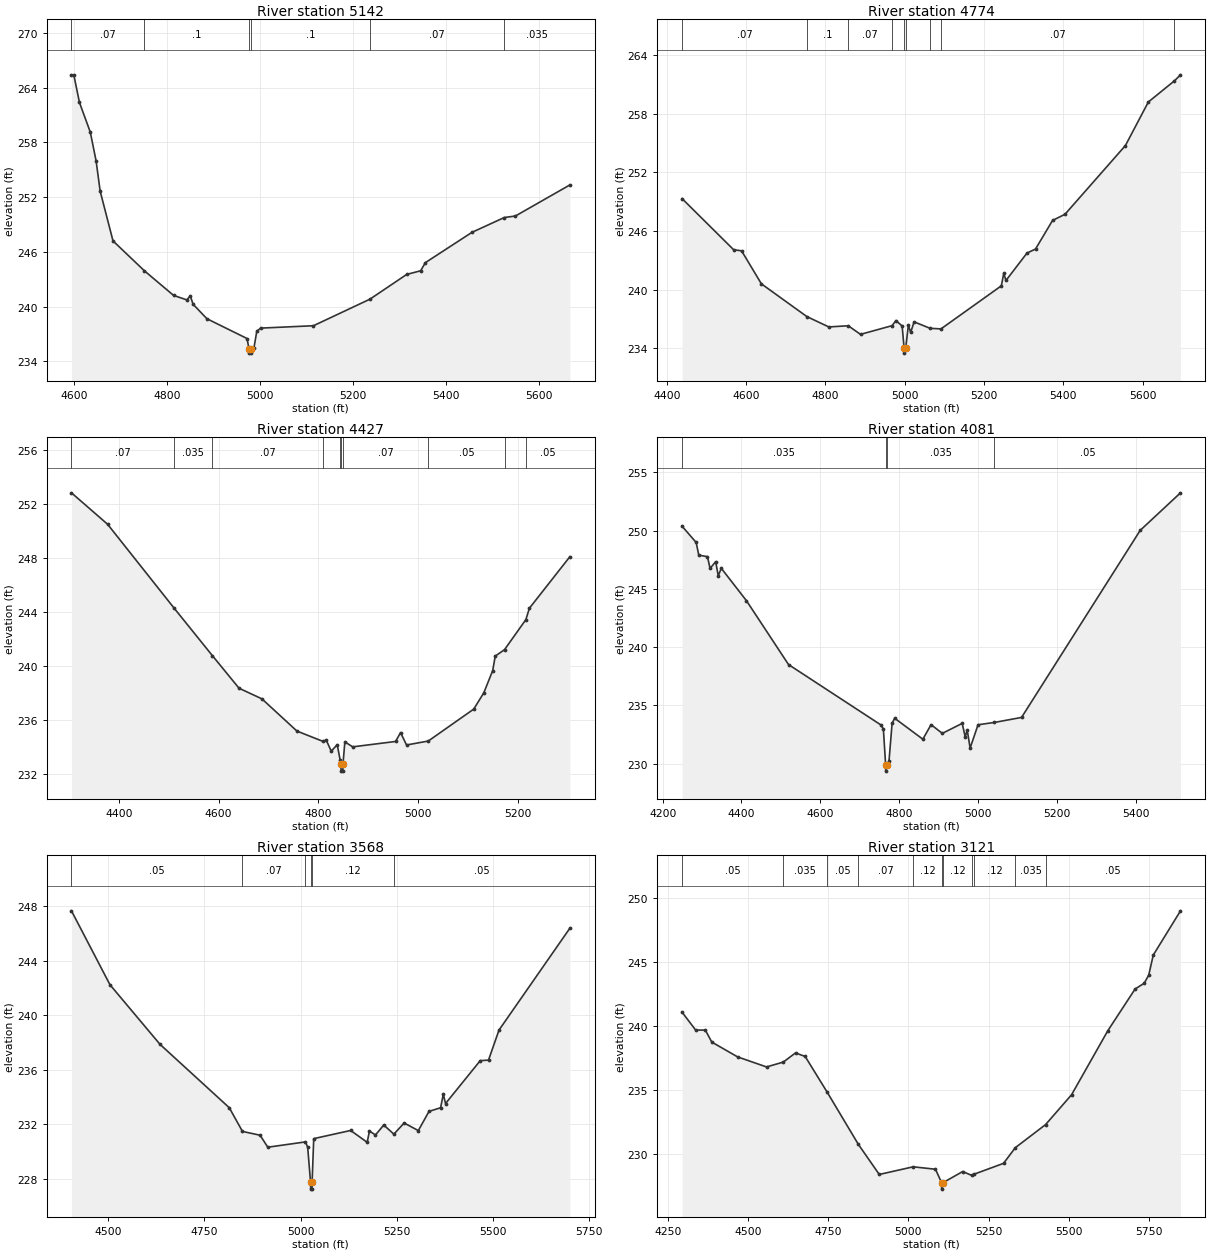
Type RM Length L Ch R = 1,5142,368,368,368
BEGIN DESCRIPTION:
XS7542
END DESCRIPTION:
XS GIS Cut Line= 3
      2448138.16     13665777.06      2447790.97     13665534.03
      2447145.11     13665492.36
#Sta/Elev= 30
  4594.8  265.39  4599.8  265.39  4612.0  262.36  4635.3  259.11  4647.8  255.95
  4656.5  252.64  4684.1  247.20  4751.7  243.92  4814.3  241.23  4842.8  240.74
  4850.1  241.19  4856.2  240.26  4885.8  238.68  4972.1  236.51  4976.2  235.41
  4976.5  234.91  4980.0  234.91  4980.2  235.41  4987.0  235.50  4993.1  237.32
  5001.5  237.65  5114.8  237.91  5236.2  240.82  5315.2  243.53  5345.2  243.93
  5355.3  244.82  5455.5  248.14  5524.8  249.76  5548.9  249.93  5665.8  253.33
#Mann=6,-1,0
  4594.8    0.07       0  4751.7     0.1       0  4976.2    0.05       0
  4980.2     0.1       0  5236.2    0.07       0  5524.8   0.035       0
Bank Sta=4976.2,4980.2
Exp/Cntr=0.3,0.1

Type RM Length L Ch R = 1,4774,347,347,347
BEGIN DESCRIPTION:
Stream0720 10.0
END DESCRIPTION:
XS GIS Cut Line= 3
      2448425.00     13665275.00      2447950.69     13665270.14
      2447274.98     13664874.99
#Sta/Elev= 30
  4438.5  249.31  4568.5  244.08  4588.5  243.97  4638.5  240.59  4753.2  237.24
  4808.5  236.18  4857.6  236.30  4888.5  235.42  4968.1  236.31  4977.8  236.83
  4993.5  236.28  4998.5  234.00  4998.8  233.50  5002.5  234.00  5009.2  236.37
  5015.0  235.62  5023.7  236.70  5063.9  236.04  5091.5  235.98  5243.8  240.39
  5249.7  241.66  5255.5  240.94  5308.4  243.74  5329.9  244.15  5372.9  247.08
  5404.3  247.71  5556.6  254.74  5614.5  259.20  5680.4  261.37  5695.6  261.98
#Mann=9,-1,0
  4438.5    0.07       0  4753.2     0.1       0  4857.6    0.07       0
  4968.1     0.1       0  4998.5    0.05       0  5002.5     0.1       0
  5063.9    0.05       0  5091.5    0.07       0  5680.4    0.05       0
Bank Sta=4998.5,5002.5
Exp/Cntr=0.3,0.1

Type RM Length L Ch R = 1,4427,346,346,346
BEGIN DESCRIPTION:
Stream0720 9.0
END DESCRIPTION:
XS GIS Cut Line= 3
      2448525.03     13665275.01      2447925.00     13664925.00
      2447624.99     13664875.00
#Sta/Elev= 30
  4305.1  252.84  4377.5  250.51  4511.2  244.27  4587.4  240.77  4640.9  238.35
  4686.8  237.56  4757.0  235.17  4808.2  234.42  4815.8  234.49  4825.7  233.68
  4837.7  234.16  4843.4  233.05  4845.2  232.70  4845.4  232.20  4848.9  232.20
  4849.2  232.70  4853.0  234.37  4868.7  234.00  4954.7  234.40  4964.6  235.06
  4976.6  234.14  5020.1  234.43  5111.3  236.80  5131.5  238.01  5149.3  239.66
  5154.4  240.73  5173.0  241.21  5215.8  243.44  5222.8  244.28  5303.9  248.10
#Mann=10,-1,0
  4305.1    0.07       0  4511.2   0.035       0  4587.4    0.07       0
  4808.2     0.1       0  4843.4    0.07       0  4845.2    0.05       0
  4849.2    0.07       0  5020.1    0.05       0  5173.0    0.07       0
  5215.8    0.05       0
Bank Sta=4845.2,4849.2
Exp/Cntr=0.3,0.1

Type RM Length L Ch R = 1,4081,513,513,513
BEGIN DESCRIPTION:
Stream0720 8.0
END DESCRIPTION:
XS GIS Cut Line= 3
      2448524.98     13665174.98      2448075.69     13664638.19
      2447513.19     13664686.81
#Sta/Elev= 30
  4249.4  250.38  4285.1  248.99  4291.7  247.90  4313.8  247.77  4320.3  246.76
  4334.6  247.34  4341.1  246.13  4348.9  246.77  4412.7  243.99  4519.4  238.51
  4753.6  233.33  4760.1  232.98  4765.9  229.86  4766.1  229.36  4769.9  229.86
  4774.4  230.23  4782.2  233.46  4788.7  233.90  4860.3  232.10  4881.1  233.35
  4909.7  232.60  4960.1  233.46  4967.8  232.29  4972.8  232.90  4980.2  231.34
  5000.3  233.34  5041.9  233.54  5110.7  233.97  5411.8  250.03  5514.0  253.25
#Mann=4,-1,0
  4249.4   0.035       0  4765.9    0.05       0  4769.9   0.035       0
  5041.9    0.05       0
Bank Sta=4765.9,4769.9
Exp/Cntr=0.3,0.1

Type RM Length L Ch R = 1,3568,447,447,447
BEGIN DESCRIPTION:
Stream0720 7.0
END DESCRIPTION:
XS GIS Cut Line= 3
      2448824.96     13664225.00      2448225.00     13664225.00
      2447624.99     13664575.01
#Sta/Elev= 30
  4404.7  247.67  4504.7  242.24  4634.7  237.86  4814.7  233.20  4848.9  231.46
  4894.7  231.18  4914.7  230.30  5012.5  230.69  5018.3  230.30  5025.8  227.72
  5026.1  227.22  5029.6  227.22  5029.8  227.72  5034.0  230.93  5129.9  231.53
  5172.9  230.66  5178.7  231.49  5194.4  231.20  5215.9  231.93  5242.2  231.26
  5268.9  232.08  5305.7  231.52  5333.4  232.93  5363.5  233.20  5370.6  234.19
  5376.4  233.51  5466.5  236.66  5488.0  236.70  5515.3  238.91  5699.3  246.39
#Mann=6,-1,0
  4404.7    0.05       0  4848.9    0.07       0  5012.5    0.12       0
  5025.8    0.05       0  5029.8    0.12       0  5242.2    0.05       0
Bank Sta=5025.8,5029.8
Exp/Cntr=0.3,0.1

Type RM Length L Ch R = 1,3121,289,289,289
BEGIN DESCRIPTION:
Stream0720 6.0
END DESCRIPTION:
XS GIS Cut Line= 3
      2448777.11     13663936.81      2448075.00     13663875.00
      2447474.97     13664475.03
#Sta/Elev= 30
  4294.9  241.08  4337.2  239.68  4367.3  239.68  4387.4  238.74  4467.7  237.58
  4558.0  236.79  4610.2  237.17  4648.4  237.89  4678.5  237.61  4745.9  234.86
  4844.5  230.71  4909.4  228.36  5015.2  228.96  5084.6  228.77  5103.8  227.71
  5104.0  227.21  5107.8  227.71  5169.4  228.59  5198.1  228.28  5203.8  228.37
  5296.7  229.23  5333.5  230.46  5427.8  232.27  5508.8  234.61  5622.0  239.64
  5706.8  242.90  5735.1  243.35  5749.3  243.99  5763.4  245.56  5848.3  249.03
#Mann=11,-1,0
  4294.9    0.05       0  4610.2   0.035       0  4745.9    0.05       0
  4844.5    0.07       0  5015.2    0.12       0  5103.8    0.05       0
  5107.8    0.12       0  5198.1    0.07       0  5203.8    0.12       0
  5333.5   0.035       0  5427.8    0.05       0
Bank Sta=5103.8,5107.8
Exp/Cntr=0.3,0.1

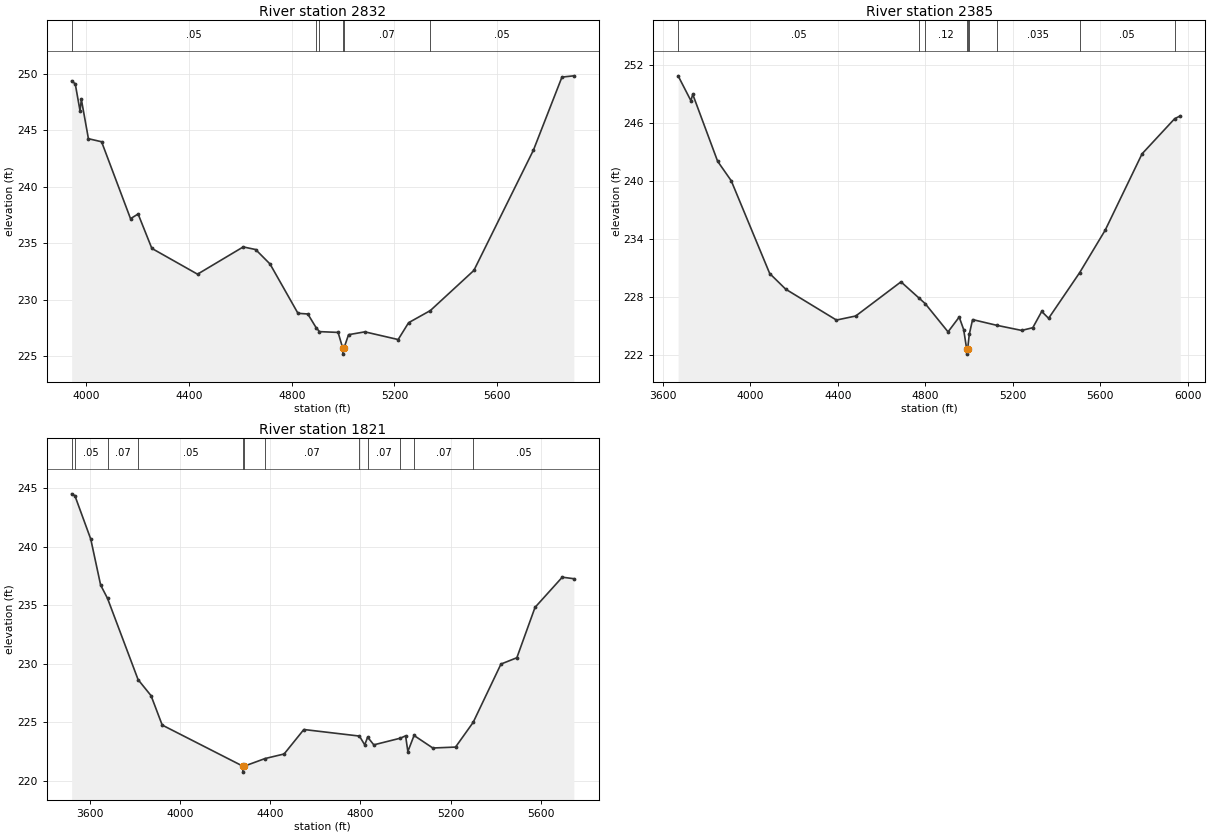
Type RM Length L Ch R = 1,2832,447,447,447
BEGIN DESCRIPTION:
XS7541
END DESCRIPTION:
XS GIS Cut Line= 3
      2449068.70     13663797.91      2448207.64     13663603.47
      2447152.04     13663797.92
#Sta/Elev= 30
  3942.8  249.35  3956.8  249.09  3975.5  246.70  3980.6  247.72  4008.1  244.24
  4059.4  243.97  4172.1  237.17  4201.7  237.58  4255.2  234.54  4433.1  232.26
  4611.1  234.67  4659.4  234.44  4715.5  233.16  4824.3  228.80  4862.7  228.74
  4895.3  227.52  4908.2  227.18  4980.7  227.11  4999.1  225.69  4999.3  225.19
  5003.1  225.69  5021.4  226.91  5084.9  227.16  5214.6  226.48  5255.3  227.97
  5339.8  229.04  5509.5  232.59  5741.5  243.23  5852.6  249.69  5898.9  249.80
#Mann=6,-1,0
  3942.8    0.05       0  4895.3   0.035       0  4908.2    0.07       0
  4999.1    0.05       0  5003.1    0.07       0  5339.8    0.05       0
Bank Sta=4999.1,5003.1
Exp/Cntr=0.3,0.1

Type RM Length L Ch R = 1,2385,564,564,564
BEGIN DESCRIPTION:
XS7540
END DESCRIPTION:
XS GIS Cut Line= 3
      2449339.58     13663534.03      2448284.03     13663256.25
      2447103.45     13663485.42
#Sta/Elev= 30
  3671.0  250.86  3729.4  248.29  3737.8  248.95  3851.5  242.03  3913.6  240.02
  4089.4  230.43  4162.6  228.81  4394.3  225.62  4482.3  226.04  4689.1  229.57
  4770.2  227.92  4799.7  227.32  4904.1  224.40  4955.0  225.93  4975.4  224.64
  4989.4  222.60  4989.6  222.10  4993.4  222.60  5001.3  224.17  5016.2  225.67
  5126.3  225.08  5240.3  224.55  5291.2  224.83  5332.0  226.51  5363.5  225.80
  5505.3  230.52  5622.0  234.91  5790.4  242.80  5939.3  246.43  5965.1  246.72
#Mann=9,-1,0
  3671.0    0.05       0  4770.2    0.07       0  4799.7    0.12       0
  4989.4    0.05       0  4993.4    0.12       0  5001.3    0.07       0
  5126.3   0.035       0  5505.3    0.05       0  5939.3    0.07       0
Bank Sta=4989.4,4993.4
Exp/Cntr=0.3,0.1

Type RM Length L Ch R = 1,1821,0,0,0
BEGIN DESCRIPTION:
XS7539
END DESCRIPTION:
XS GIS Cut Line= 3
      2449367.39     13663318.77      2448346.53     13662770.14
      2447284.02     13662909.03
#Sta/Elev= 30
  3517.3  244.50  3531.7  244.34  3602.2  240.63  3646.0  236.71  3676.6  235.57
  3812.4  228.63  3870.0  227.26  3919.5  224.75  4278.7  221.23  4279.0  220.73
  4282.7  221.23  4376.3  221.89  4461.0  222.28  4548.6  224.37  4795.4  223.81
  4819.0  223.06  4832.0  223.72  4859.3  223.06  4977.4  223.63  5000.5  223.83
  5010.6  222.49  5038.1  223.86  5121.5  222.79  5222.4  222.87  5300.6  224.98
  5424.1  229.96  5494.7  230.50  5575.4  234.80  5696.4  237.38  5747.8  237.25
#Mann=12,-1,0
  3517.3    0.07       0  3531.7    0.05       0  3676.6    0.07       0
  3812.4    0.05       0  4278.7    0.05       0  4282.7    0.05       0
  4376.3    0.07       0  4795.4    0.05       0  4832.0    0.07       0
  4977.4    0.12       0  5038.1    0.07       0  5300.6    0.05       0
Bank Sta=4278.7,4282.7
Exp/Cntr=0.3,0.1

Chan Stop Cuts=-1