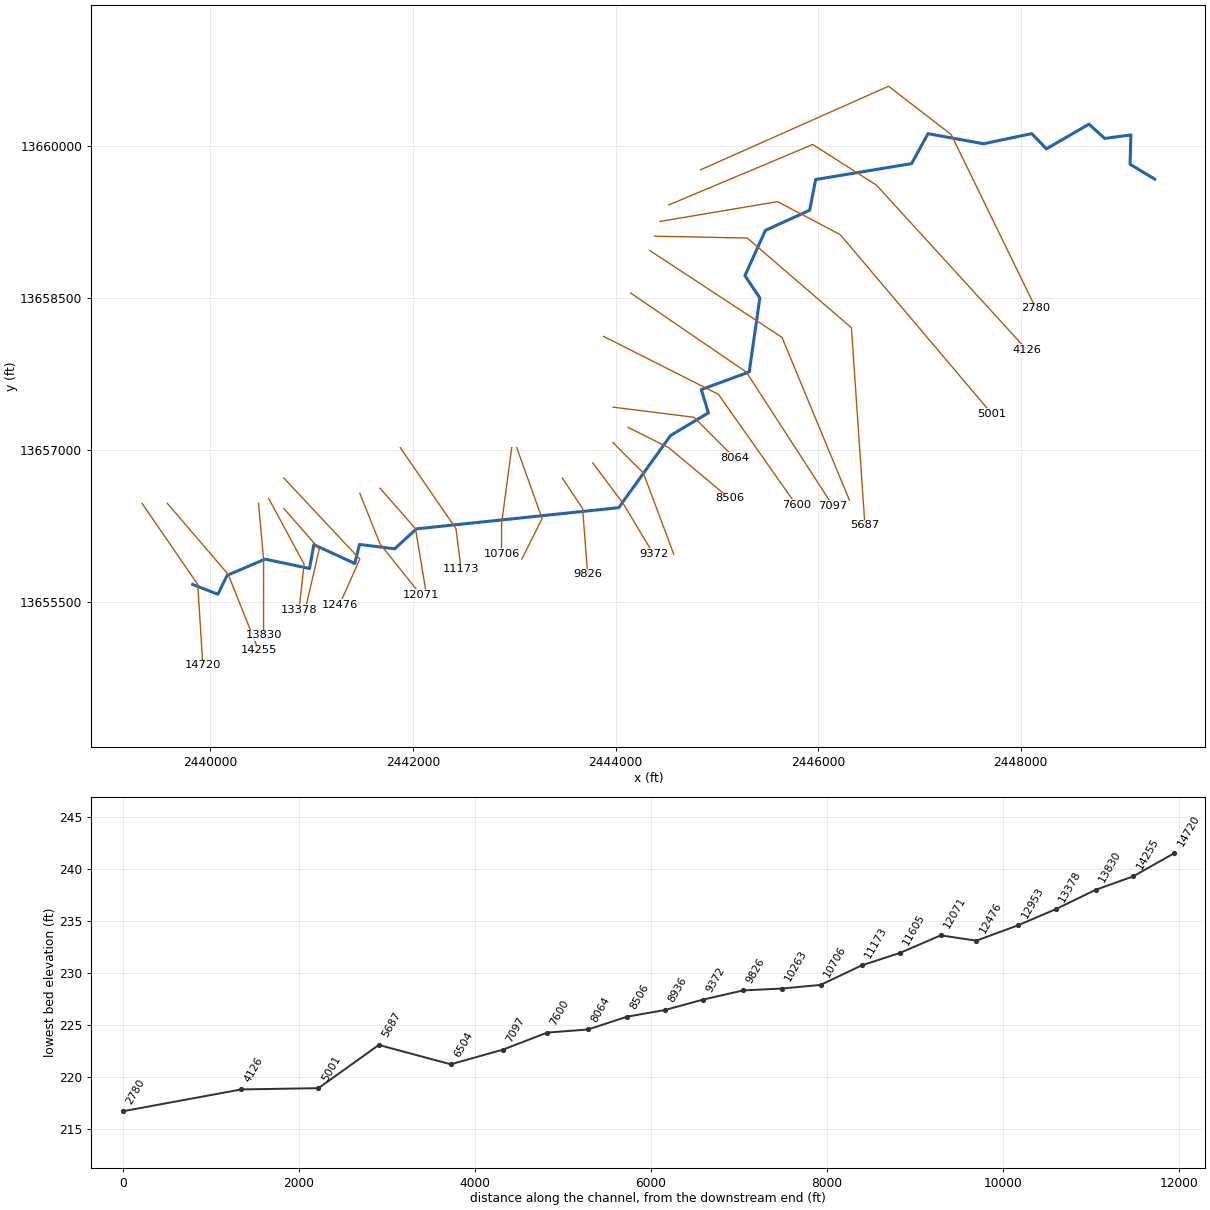
--- Stream0721.prj (project) ---

Proj Title=Stream0721 Base Level Engineering
Current Plan=p01
Default Exp/Contr=0.3,0.1
English Units
Geom File=g01
Flow File=f01
Plan File=p01
Y Axis Title=Elevation
X Axis Title(PF)=Main Channel Distance
X Axis Title(XS)=Station
BEGIN DESCRIPTION:
Stream0721
END DESCRIPTION:
DSS Export Rating Curves= 0
DSS Export Rating Curve Sorted= 0
DSS Export Volume Flow Curves= 0
DXF OffsetX= 0
DXF OffsetY= 0
DXF ScaleX= 1
DXF ScaleY= 10

--- Stream0721.p01 (plan) ---

Plan Title=Multiple Run
Short Identifier=Multiple
Geom File=g01
Flow File=f01
Subcritical Flow
K Sum by GR= 0
Std Step Tol= 0.01
Critical Tol= 0.01
Num of Std Step Trials= 20
Max Error Tol= 0.3
Flow Tol Ratio= 0.001
Split Flow NTrial= 30
Split Flow Tol= 0.02
Split Flow Ratio= 0.02
Log Output Level= 0
Friction Slope Method= 1
Unsteady Friction Slope Method= 2
Unsteady Bridges Friction Slope Method= 1
Parabolic Critical Depth
Global Vel Dist=  1 , 1 , 1
Global Log Level= 0
CheckData=True
Encroach Param= -1, 0, 0, 0
BEGIN DESCRIPTION:
Multiple Run
END DESCRIPTION:

--- Stream0721.f01 (steady flow) ---

Flow Title=Multiple
Number of Profiles=7
Profile Names=10-year,25-year,50-year,1pct_min,100-year,1pct_plu,500-year
River Rch & RM= Stream0721,Reach-1,14720
     587     935    1244     801    1599    3190    2616
River Rch & RM= Stream0721,Reach-1,13830
     826    1332    1786    1157    2309    4607    3825
River Rch & RM= Stream0721,Reach-1,7600
    1179    1917    2585    1681    3354    6692    5598
Boundary for River Rch & Prof#=Stream0721,Reach-1,1
Up Type=0
Dn Type=3
Dn Slope=0.005
Boundary for River Rch & Prof#=Stream0721,Reach-1,2
Up Type=0
Dn Type=3
Dn Slope=0.005
Boundary for River Rch & Prof#=Stream0721,Reach-1,3
Up Type=0
Dn Type=3
Dn Slope=0.005
Boundary for River Rch & Prof#=Stream0721,Reach-1,4
Up Type=0
Dn Type=3
Dn Slope=0.005
Boundary for River Rch & Prof#=Stream0721,Reach-1,5
Up Type=0
Dn Type=3
Dn Slope=0.005
Boundary for River Rch & Prof#=Stream0721,Reach-1,6
Up Type=0
Dn Type=3
Dn Slope=0.005
Boundary for River Rch & Prof#=Stream0721,Reach-1,7
Up Type=0
Dn Type=3
Dn Slope=0.005

--- Stream0721.g01 (geometry) ---

Geom Title=Existing Conditions
Program Version=4.10

River Reach=Stream0721      ,Reach-1
Reach XY= 30
        2439825.       13655675.      2440073.61     13655578.02
      2440164.94     13655764.39      2440540.22     13655924.75
      2440978.66     13655832.49      2441021.34     13656067.52
      2441425.38     13655882.23      2441472.15     13656069.89
      2441819.15     13656026.54      2442034.65     13656223.64
      2444031.57     13656432.69      2444544.45     13657145.55
      2444917.38      13657368.5      2444847.36     13657598.39
      2445320.01     13657772.45       2445425.2     13658502.35
      2445278.11     13658723.35       2445480.1     13659169.56
      2445917.19     13659368.81      2445976.25     13659671.64
      2446923.56     13659828.54      2447085.68     13660124.26
      2447634.28     13660024.46      2448109.97     13660124.67
      2448254.87     13659974.45        2448675.     13660217.93
      2448830.45     13660077.16      2449089.04     13660111.89
       2449080.8      13659822.7        2449325.       13659675.

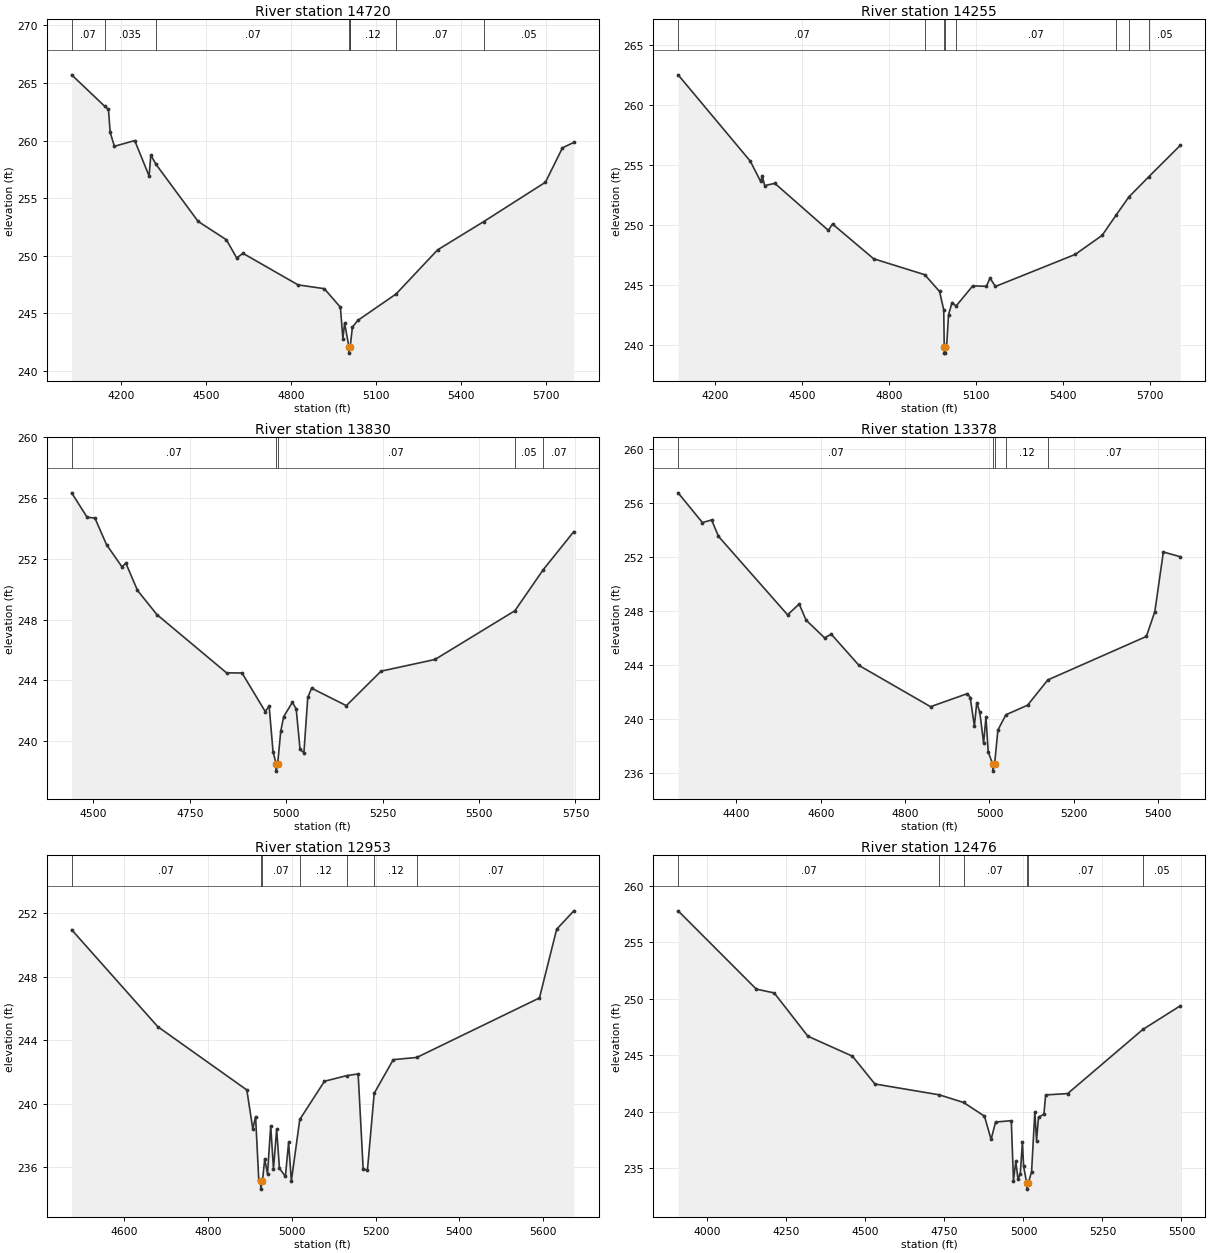
Type RM Length L Ch R = 1 ,14720   ,465,465,465
BEGIN DESCRIPTION:
Stream0721 25.0
END DESCRIPTION:
XS GIS Cut Line= 3
        2439325.     13656475.01        2439875.       13655675.
        2439925.     13654874.99
#Sta/Elev= 30
  4024.6  265.71  4141.2  262.98  4154.5   262.7  4160.6   260.7  4175.5   259.5
  4247.2     260  4297.9  256.92    4304  258.73  4322.4  257.93  4471.1  252.97
  4570.7  251.38  4607.1   249.8  4629.4   250.2  4823.6  247.46  4916.3  247.13
  4973.1  245.52  4981.9  242.79    4988  244.14  5003.5  242.03  5003.7  241.53
  5007.5  242.03  5007.9  242.12  5015.5   243.8  5035.5  244.39  5169.7  246.67
  5316.1   250.5    5479  252.96  5696.8  256.38  5756.9  259.37    5797  259.84
#Mann= 8 ,-1 , 0
  4024.6     .07       0  4141.2    .035       0  4322.4     .07       0
  5003.5     .05       0  5007.5     .07       0  5007.9     .12       0
  5169.7     .07       0    5479     .05       0
Bank Sta=5003.5,5007.5
XS Rating Curve= 0 ,0
Exp/Cntr=0.3,0.1

Type RM Length L Ch R = 1 ,14255   ,425,425,425
BEGIN DESCRIPTION:
Stream0721 24.0
END DESCRIPTION:
XS GIS Cut Line= 3
      2439574.97     13656475.04        2440175.       13655775.
      2440475.01     13655024.98
#Sta/Elev= 30
  4073.9  262.52  4322.5  255.32  4357.7  253.65  4364.3  254.05  4371.9  253.28
  4407.1  253.47  4591.4  249.55  4605.7  250.08  4747.3  247.18  4923.5  245.85
  4974.5  244.45  4988.8  242.92  4990.6  239.81  4990.9  239.31  4994.4  239.31
  4994.7  239.81  4998.6  239.81  5005.3   242.5  5017.4  243.53  5031.4  243.24
  5088.8  244.92  5135.9  244.88    5148  245.57  5166.9  244.87  5441.5  247.54
  5534.4  249.13  5582.8  250.83  5626.4  252.33  5694.7  254.01  5803.7  256.64
#Mann= 8 ,-1 , 0
  4073.9     .07       0  4923.5     .12       0  4990.6     .05       0
  4994.7     .12       0  5031.4     .07       0  5582.8     .05       0
  5626.4     .07       0  5694.7     .05       0
Bank Sta=4990.6,4994.7
XS Rating Curve= 0 ,0
Exp/Cntr=0.3,0.1

Type RM Length L Ch R = 1 ,13830   ,452,452,452
BEGIN DESCRIPTION:
Stream0721 23.0
END DESCRIPTION:
XS GIS Cut Line= 3
        2440475.     13656475.01        2440525.       13655925.
        2440525.     13655174.98
#Sta/Elev= 30
  4443.5  256.34  4483.7  254.73  4503.8  254.68  4533.9  252.93    4574  251.47
  4584.1  251.71  4614.2  249.92  4664.4  248.33  4845.2  244.49  4885.3  244.48
  4945.6  241.94  4955.6  242.31  4965.7  239.31  4973.6  238.52  4973.8  238.02
  4977.8  238.52  4985.7  240.64  4993.3   241.6  5015.8  242.55  5025.8  242.11
  5035.8  239.46  5045.8  239.23  5055.8  242.87  5065.8  243.48  5155.8  242.33
  5245.8   244.6  5385.8  245.37    5593  248.58  5666.1  251.27  5745.8  253.79
#Mann= 5 ,-1 , 0
  4443.5     .07       0  4973.6     .05       0  4977.8     .07       0
    5593     .05       0  5666.1     .07       0
Bank Sta=4973.6,4977.8
XS Rating Curve= 0 ,0
Exp/Cntr=0.3,0.1

Type RM Length L Ch R = 1 ,13378   ,425,425,425
BEGIN DESCRIPTION:
Stream0721 22.0
END DESCRIPTION:
XS GIS Cut Line= 3
        2440575.       13656525.        2440925.       13655875.
        2440875.     13655425.01
#Sta/Elev= 30
  4261.6  256.76  4319.2  254.56  4341.1  254.75  4357.3  253.54  4521.2  247.73
  4548.8  248.53    4565  247.34  4608.8  246.03    4625  246.29  4690.8  243.98
  4860.3  240.93  4947.9   241.9  4954.4   241.6  4964.2  239.49  4969.8  241.22
  4977.1  240.52  4986.1  238.23  4991.7  240.18    4997  237.59  5007.8  236.66
  5008.1  236.16  5012.1  236.66    5020   239.2  5038.9  240.33  5090.4  241.04
  5138.3  242.91  5372.1  246.13  5392.2  247.97  5412.4  252.38  5452.6  252.03
#Mann= 5 ,-1 , 0
  4261.6     .07       0  5007.8     .05       0  5012.1     .07       0
  5038.9     .12       0  5138.3     .07       0
Bank Sta=5007.8,5012.1
XS Rating Curve= 0 ,0
Exp/Cntr=0.3,0.1

Type RM Length L Ch R = 1 ,12953   ,477,477,477
BEGIN DESCRIPTION:
Stream0721 21.0
END DESCRIPTION:
XS GIS Cut Line= 3
      2440724.97     13656425.04        2441075.       13656025.
      2440925.01     13655375.04
#Sta/Elev= 30
  4474.6  250.97  4680.1  244.86  4892.7  240.87    4907  238.41  4913.6  239.19
  4921.2   235.2  4925.7  235.12    4926  234.62    4930  235.12  4935.4  236.52
  4942.1  235.58  4949.7  238.61  4956.3   235.9  4963.9   238.4  4970.6  235.93
  4984.8  235.42  4992.4  237.56    4999  235.14  5019.1  239.01    5078  241.42
  5132.3  241.78  5158.4  241.88  5170.4  235.88  5180.6  235.83  5196.7  240.66
  5242.2  242.78  5298.4  242.92  5591.1  246.67  5632.2     251  5673.2  252.16
#Mann= 7 ,-1 , 0
  4474.6     .07       0  4925.7     .05       0    4930     .07       0
  5019.1     .12       0  5132.3     .07       0  5196.7     .12       0
  5298.4     .07       0
Bank Sta=4925.7,4930
XS Rating Curve= 0 ,0
Exp/Cntr=0.3,0.1

Type RM Length L Ch R = 1 ,12476   ,405,405,405
BEGIN DESCRIPTION:
Stream0721 20.0
END DESCRIPTION:
XS GIS Cut Line= 3
      2440724.98     13656725.02        2441475.       13655925.
      2441274.98     13655474.96
#Sta/Elev= 30
  3907.2  257.77  4154.6  250.84  4211.3   250.5  4317.8  246.67  4458.9   244.9
  4529.8  242.44  4733.5  241.48  4810.7   240.8  4876.6  239.59  4897.6  237.53
  4911.7  239.07  4961.5  239.19  4968.4  233.87  4975.7  235.61  4982.6  234.02
  4989.9  234.48  4996.7   237.3  5000.4  235.16  5010.5  233.63  5010.8  233.13
    5015  233.63  5025.7  234.68    5036  239.98  5041.4  237.43  5047.6   239.5
  5064.7  239.76  5070.2  241.47  5139.9  241.59  5377.9  247.27  5496.3  249.36
#Mann= 6 ,-1 , 0
  3907.2     .07       0  4733.5     .12       0  4810.7     .07       0
  5010.5     .05       0    5015     .07       0  5377.9     .05       0
Bank Sta=5010.5,5015
XS Rating Curve= 0 ,0
Exp/Cntr=0.3,0.1

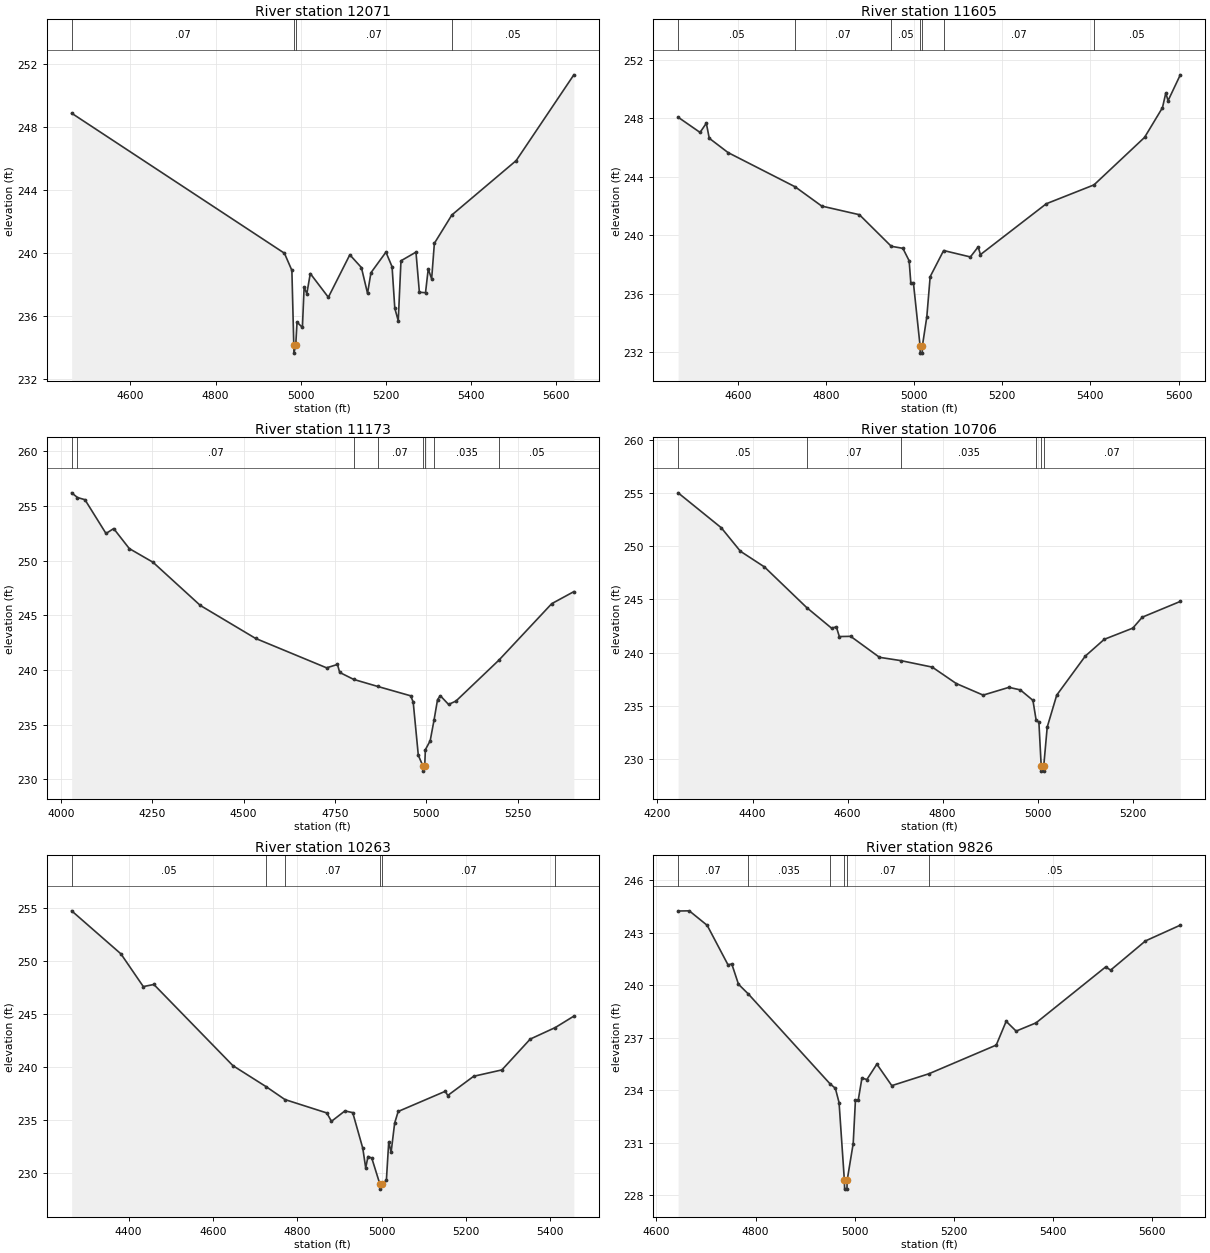
Type RM Length L Ch R = 1 ,12071   ,466,466,466
BEGIN DESCRIPTION:
Stream0721 19.0
END DESCRIPTION:
XS GIS Cut Line= 3
      2441474.99     13656575.02        2441675.       13656075.
      2442075.03     13655574.96
#Sta/Elev= 30
  4462.3  248.89  4961.8  239.99  4979.3   238.9  4983.8  234.14  4984.1  233.64
  4988.3  234.14  4991.4  235.61    5004  235.27    5008  237.82  5014.4  237.42
  5022.5   238.7  5064.9  237.19  5115.3  239.89  5142.5  239.08  5156.9  237.44
  5164.9  238.75  5200.1  240.06  5214.5  239.13  5220.9  236.49    5229   235.7
  5235.4  239.51  5270.6  240.06  5278.6  237.51    5293  237.48  5299.4  238.99
  5307.4  238.36  5313.8  240.62  5354.8  242.42  5505.9  245.88  5641.2  251.33
#Mann= 4 ,-1 , 0
  4462.3     .07       0  4983.8     .05       0  4988.3     .07       0
  5354.8     .05       0
Bank Sta=4983.8,4988.3
XS Rating Curve= 0 ,0
Exp/Cntr=0.3,0.1

Type RM Length L Ch R = 1 ,11605   ,432,432,432
BEGIN DESCRIPTION:
Stream0721 18.0
END DESCRIPTION:
XS GIS Cut Line= 3
      2441675.03     13656624.97        2442025.       13656225.
      2442124.99     13655625.04
#Sta/Elev= 30
  4464.3  248.08  4514.1  247.04  4528.3  247.67    4535  246.64  4577.7  245.66
  4729.8  243.32  4790.3     242  4875.7  241.41    4948  239.25  4974.4  239.11
  4988.6  238.26  4992.4  236.75  4998.3  236.75  5013.4  232.44  5013.8  231.94
  5018.3  231.94  5018.7  232.44  5028.7  234.42  5036.3  237.17  5066.9  238.96
  5127.6  238.52  5145.3  239.21  5150.4  238.68  5299.9  242.16  5408.1  243.45
  5522.9   246.7  5563.5  248.73  5571.1  249.74  5576.2  249.21    5604  250.98
#Mann= 7 ,-1 , 0
  4464.3     .05       0  4729.8     .07       0    4948     .05       0
  5013.4     .05       0  5018.7     .05       0  5066.9     .07       0
  5408.1     .05       0
Bank Sta=5013.4,5018.7
XS Rating Curve= 0 ,0
Exp/Cntr=0.3,0.1

Type RM Length L Ch R = 1 ,11173   ,467,467,467
BEGIN DESCRIPTION:
Stream0721 17.0
END DESCRIPTION:
XS GIS Cut Line= 3
      2441875.03     13657024.96        2442425.       13656225.
        2442475.     13655824.99
#Sta/Elev= 30
  4029.7  256.21  4045.7  255.78  4066.1  255.58  4123.7  252.49  4144.7  252.94
  4187.4  251.11  4252.2  249.86  4381.6  245.91    4533  242.89  4727.2   240.2
  4756.9  240.51    4763  239.78  4801.4  239.14  4866.8   238.5  4957.2  237.64
  4964.1  237.07  4978.1   232.2  4990.3  231.25  4990.8  230.75  4995.7  231.25
  4997.4  232.71  5010.6  233.53  5021.3  235.45  5030.7  237.29  5038.3  237.65
  5060.9  236.85  5081.1  237.16  5198.5   240.9  5343.1  246.07  5403.6  247.17
#Mann= 8 ,-1 , 0
  4029.7     .05       0  4045.7     .07       0  4801.4    .035       0
  4866.8     .07       0  4990.3     .05       0  4995.7     .07       0
  5021.3    .035       0  5198.5     .05       0
Bank Sta=4990.3,4995.7
XS Rating Curve= 0 ,0
Exp/Cntr=0.3,0.1

Type RM Length L Ch R = 1 ,10706   ,443,443,443
BEGIN DESCRIPTION:
Stream0721 16.0
END DESCRIPTION:
XS GIS Cut Line= 3
        2442975.     13657024.96        2442875.       13656275.
        2442875.       13655975.
#Sta/Elev= 30
  4243.4  255.01  4334.2  251.73  4374.5  249.52    4425  248.05    4514  244.23
  4566.2   242.3  4576.3  242.42  4582.6  241.51  4606.5  241.53  4667.1  239.56
    4712  239.25  4778.1  238.64  4828.5   237.1  4885.2  236.01  4939.5  236.74
  4963.4   236.5  4989.9  235.52  4996.5  233.71  5002.5  233.44  5007.3  229.37
  5007.7  228.87  5012.3  228.87  5012.7  229.37    5020  233.01    5040  236.01
    5100  239.67    5140  241.25    5200   242.3    5220  243.33    5300  244.81
#Mann= 6 ,-1 , 0
  4243.4     .05       0    4514     .07       0    4712    .035       0
  4996.5     .07       0  5007.3     .05       0  5012.7     .07       0
Bank Sta=5007.3,5012.7
XS Rating Curve= 0 ,0
Exp/Cntr=0.3,0.1

Type RM Length L Ch R = 1 ,10263   ,437,437,437
BEGIN DESCRIPTION:
Stream0721 15.0
END DESCRIPTION:
XS GIS Cut Line= 3
      2443024.99     13657025.03        2443275.       13656325.
      2443075.02     13655925.04
#Sta/Elev= 30
    4265  254.71  4381.8  250.66  4434.9  247.58  4459.9  247.78  4647.3  240.14
  4726.5  238.15  4770.6  236.95  4869.8  235.69  4880.9   234.9  4912.8  235.88
  4931.3  235.72  4955.2  232.36  4962.1  230.51  4967.5  231.59  4976.5  231.44
  4995.5  229.02  4995.9  228.52    5001  229.02  5011.1  229.34  5016.7  232.98
  5022.3  231.98  5030.7  234.73  5039.1  235.83  5150.9  237.73  5156.5  237.33
    5218  239.14    5285  239.74  5352.1  242.64  5411.7  243.73  5455.5   244.8
#Mann= 6 ,-1 , 0
    4265     .05       0  4726.5    .035       0  4770.6     .07       0
  4995.5     .05       0    5001     .07       0  5411.7     .05       0
Bank Sta=4995.5,5001
XS Rating Curve= 0 ,0
Exp/Cntr=0.3,0.1

Type RM Length L Ch R = 1 ,9826    ,454,454,454
BEGIN DESCRIPTION:
Stream0721 14.0
END DESCRIPTION:
XS GIS Cut Line= 3
      2443475.01     13656724.99        2443675.       13656425.
        2443725.     13655774.97
#Sta/Elev= 30
  4643.7  244.25  4666.2  244.26  4702.3  243.43  4744.3  241.17  4751.9  241.22
  4765.4  240.06  4785.4   239.5  4949.8  234.37  4960.7  234.11  4968.2  233.29
  4978.9  228.84  4979.4  228.34  4984.1  228.34  4984.5  228.84  4996.7  230.95
  5001.2  233.42  5006.8  233.42  5014.3  234.69  5024.3  234.61  5044.4  235.49
  5074.5  234.26  5149.4  234.94  5285.1  236.58  5305.1  237.94  5325.2  237.38
  5365.3  237.85  5505.7  241.05  5515.8  240.87    5586  242.54  5656.2  243.44
#Mann= 6 ,-1 , 0
  4643.7     .07       0  4785.4    .035       0  4949.8     .07       0
  4978.9     .05       0  4984.5     .07       0  5149.4     .05       0
Bank Sta=4978.9,4984.5
XS Rating Curve= 0 ,0
Exp/Cntr=0.3,0.1

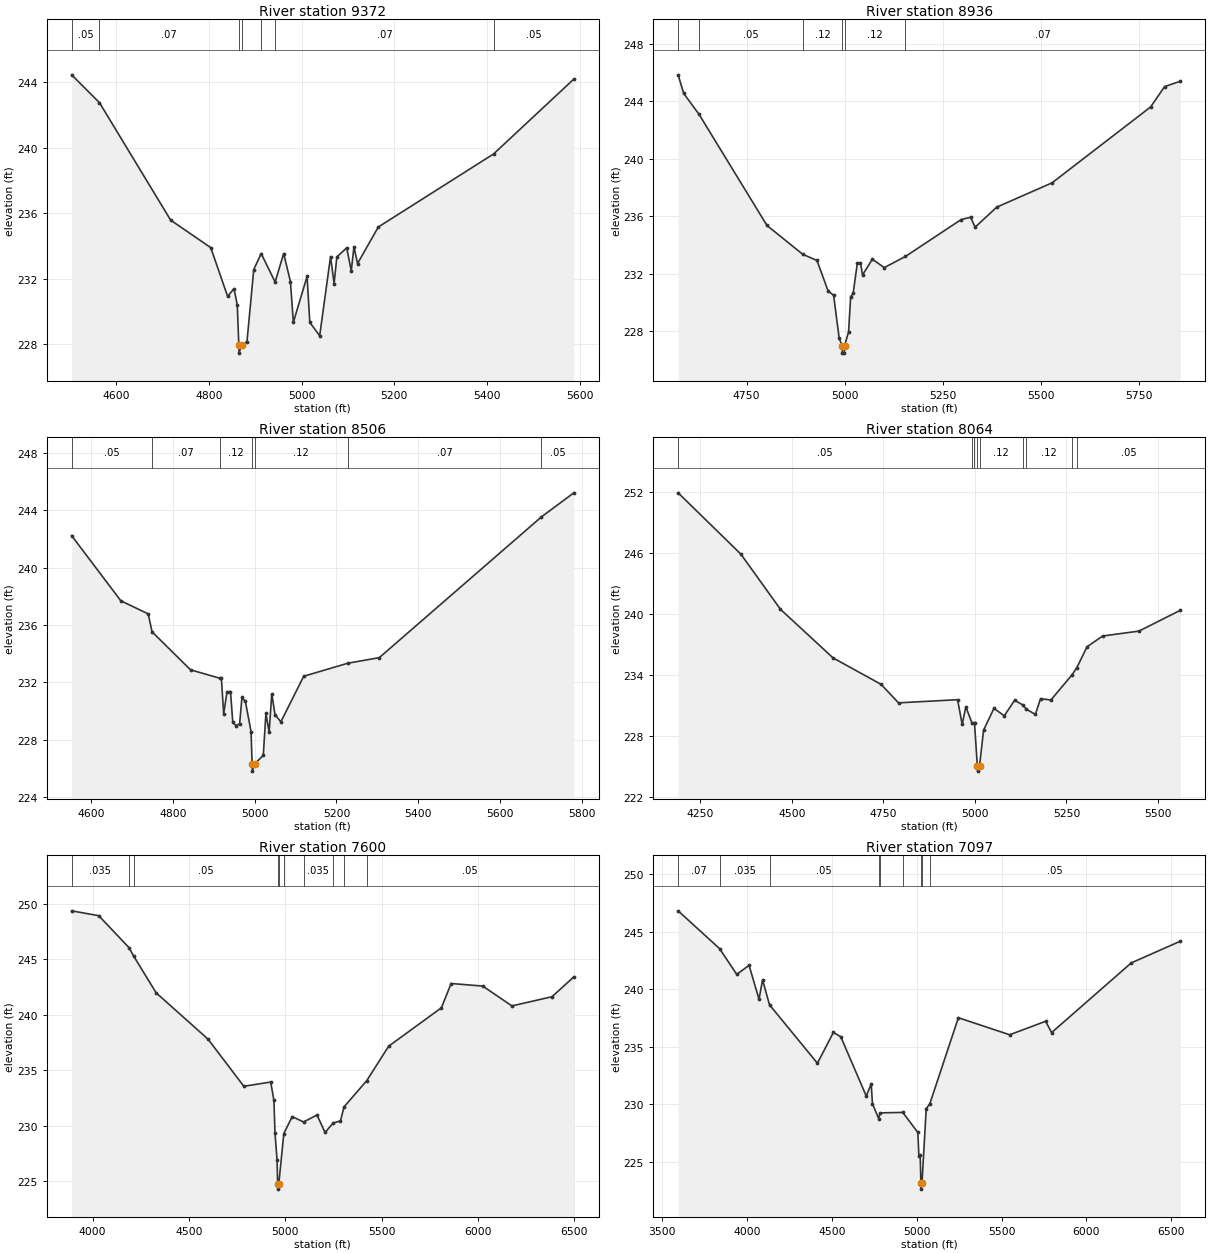
Type RM Length L Ch R = 1 ,9372    ,436,436,436
BEGIN DESCRIPTION:
Stream0721 13.0
END DESCRIPTION:
XS GIS Cut Line= 3
      2443775.03     13656874.96        2444075.       13656475.
      2444374.98     13655975.04
#Sta/Elev= 30
  4504.1  244.45  4564.1  242.75  4717.6  235.58  4804.1   233.9  4840.5  230.92
  4854.1   231.4  4861.3   230.4  4864.6  227.96  4865.1  227.46  4870.5  227.96
  4882.2  228.16  4896.8  232.56  4912.8  233.54  4942.9   231.8  4961.3  233.54
  4975.9  231.83  4982.2  229.34  5011.8  232.14  5017.7  229.34    5039  228.52
  5062.4  233.35  5070.1  231.71    5076  233.33  5097.3  233.89  5107.1  232.48
  5112.9  233.95  5120.7  232.93  5165.4  235.16    5414  239.62  5587.1  244.19
#Mann= 7 ,-1 , 0
  4504.1     .05       0  4564.1     .07       0  4864.6     .05       0
  4870.5     .07       0  4912.8    .035       0  4942.9     .07       0
    5414     .05       0
Bank Sta=4864.6,4870.5
XS Rating Curve= 0 ,0
Exp/Cntr=0.3,0.1

Type RM Length L Ch R = 1 ,8936    ,430,430,430
BEGIN DESCRIPTION:
Stream0721 12.0
END DESCRIPTION:
XS GIS Cut Line= 3
      2443975.03     13657074.97        2444275.       13656775.
      2444574.99     13655975.02
#Sta/Elev= 30
  4575.5  245.85  4589.6  244.56  4628.7   243.1  4801.7  235.35  4892.8  233.34
    4929  232.91  4957.3  230.79  4971.4  230.48  4985.6  227.49  4993.2  226.95
  4993.7  226.45  4998.7  226.45  4999.2  226.95  5009.5  227.94  5014.8  230.39
  5021.1  230.61  5031.8  232.72  5039.8  232.75  5045.1   231.9    5070     233
  5100.3  232.41  5154.3  233.19  5296.1  235.76  5320.1  235.92  5331.7  235.23
  5386.9  236.63  5527.5  238.32  5778.5  243.61  5814.1  245.03  5854.1   245.4
#Mann= 6 ,-1 , 0
  4575.5     .07       0  4628.7     .05       0  4892.8     .12       0
  4993.2     .05       0  4999.2     .12       0  5154.3     .07       0
Bank Sta=4993.2,4999.2
XS Rating Curve= 0 ,0
Exp/Cntr=0.3,0.1

Type RM Length L Ch R = 1 ,8506    ,442,442,442
BEGIN DESCRIPTION:
Stream0721 11.0
END DESCRIPTION:
XS GIS Cut Line= 3
      2444124.98     13657225.01        2444525.       13657025.
      2445125.03     13656524.97
#Sta/Elev= 30
  4552.3  242.24  4672.5   237.7  4739.6  236.78    4749  235.53    4843  232.88
  4916.1  232.28  4918.5  232.32  4924.1  229.81  4932.4  231.35  4940.8  231.36
  4946.4  229.22  4954.8  228.98  4963.2  229.12  4968.8  230.95  4977.2  230.68
  4991.1  228.57  4993.7  226.31  4994.2  225.81  4999.7  226.31    5021  226.91
  5027.5  229.84  5035.3  228.53  5041.8  231.21  5049.6  229.76    5064  229.25
  5119.9  232.43  5227.8  233.34  5304.8  233.73  5701.3  243.55  5780.6  245.23
#Mann= 7 ,-1 , 0
  4552.3     .05       0    4749     .07       0  4916.1     .12       0
  4993.7     .05       0  4999.7     .12       0  5227.8     .07       0
  5701.3     .05       0
Bank Sta=4993.7,4999.7
XS Rating Curve= 0 ,0
Exp/Cntr=0.3,0.1

Type RM Length L Ch R = 1 ,8064    ,464,464,464
BEGIN DESCRIPTION:
Stream0721 10.0
END DESCRIPTION:
XS GIS Cut Line= 3
      2443975.01       13657425.        2444775.       13657325.
        2445175.       13656925.
#Sta/Elev= 30
  4189.2  251.89  4360.5  245.88  4468.8  240.46  4612.5  235.69  4743.5   233.1
  4791.3  231.28  4952.6  231.59  4965.2  229.17  4975.3  230.89  4991.5  229.35
  4997.3   229.3  4998.9   229.3  5006.6  225.08  5007.1  224.58  5012.6  225.08
  5023.7  228.61    5052  230.74  5080.3  230.01  5108.5  231.54    5130  231.09
  5140.6  230.66  5165.1  230.14  5179.3  231.69  5207.5  231.56  5265.4  234.03
  5278.2  234.72  5306.5  236.79    5349  237.84    5448  238.32  5561.1  240.36
#Mann= 9 ,-1 , 0
  4189.2     .05       0  4991.5     .07       0  4997.3     .12       0
  5006.6     .05       0  5012.6     .12       0    5130     .07       0
  5140.6     .12       0  5265.4     .07       0  5278.2     .05       0
Bank Sta=5006.6,5012.6
XS Rating Curve= 0 ,0
Exp/Cntr=0.3,0.1

Type RM Length L Ch R = 1 ,7600    ,503,503,503
BEGIN DESCRIPTION:
XS7546
END DESCRIPTION:
XS GIS Cut Line= 3
      2443883.45     13658122.77      2445016.07      13657551.7
      2445786.01     13656458.57
#Sta/Elev= 30
  3891.8  249.36  4032.4  248.92    4190  246.03  4213.2  245.29  4330.3  241.97
  4599.1   237.8  4785.1  233.55  4924.6  233.93  4941.3  232.27  4946.9   229.3
  4957.5  226.94  4960.5  224.78    4961  224.28  4966.6  224.78  4992.6  229.29
  5036.1  230.82  5095.1  230.33  5164.7  230.96  5206.5  229.39  5248.9  230.24
  5286.6  230.43  5304.9  231.69    5423  234.06  5536.6  237.16  5810.1  240.62
  5860.6  242.81  6024.6  242.58  6175.9  240.79  6384.1  241.62  6497.3  243.41
#Mann= 10 ,-1 , 0
  3891.8    .035       0    4190     .07       0  4213.2     .05       0
  4960.5     .05       0  4966.6     .05       0  4992.6     .07       0
  5095.1    .035       0  5248.9     .07       0  5304.9    .035       0
    5423     .05       0
Bank Sta=4960.5,4966.6
XS Rating Curve= 0 ,0
Exp/Cntr=0.3,0.1

Type RM Length L Ch R = 1 ,7097    ,593,593,593
BEGIN DESCRIPTION:
XS7545
END DESCRIPTION:
XS GIS Cut Line= 3
      2444149.92     13658551.09      2445292.09     13657770.61
      2446147.91     13656448.85
#Sta/Elev= 30
  3595.1   246.8  3839.3  243.52  3940.4  241.28    4013  242.07  4071.6  239.12
  4092.5  240.81  4133.4  238.64  4415.6  233.57  4509.6  236.24  4553.1  235.87
  4703.4  230.72  4732.5  231.77  4739.8  230.05  4776.4  228.77    4785  229.26
  4918.4   229.3  5007.2  227.56  5013.2  225.51  5020.9   225.6  5025.2  223.14
  5025.7  222.64  5031.4  223.14  5056.6  229.63  5077.7  230.05  5245.9  237.52
    5548  236.04  5759.5  237.21  5795.2  236.23  6264.2  242.28  6553.1  244.16
#Mann= 9 ,-1 , 0
  3595.1     .07       0  3839.3    .035       0  4133.4     .05       0
  4776.4     .07       0    4785     .05       0  4918.4     .07       0
  5025.2     .05       0  5031.4     .07       0  5077.7     .05       0
Bank Sta=5025.2,5031.4
XS Rating Curve= 0 ,0
Exp/Cntr=0.3,0.1

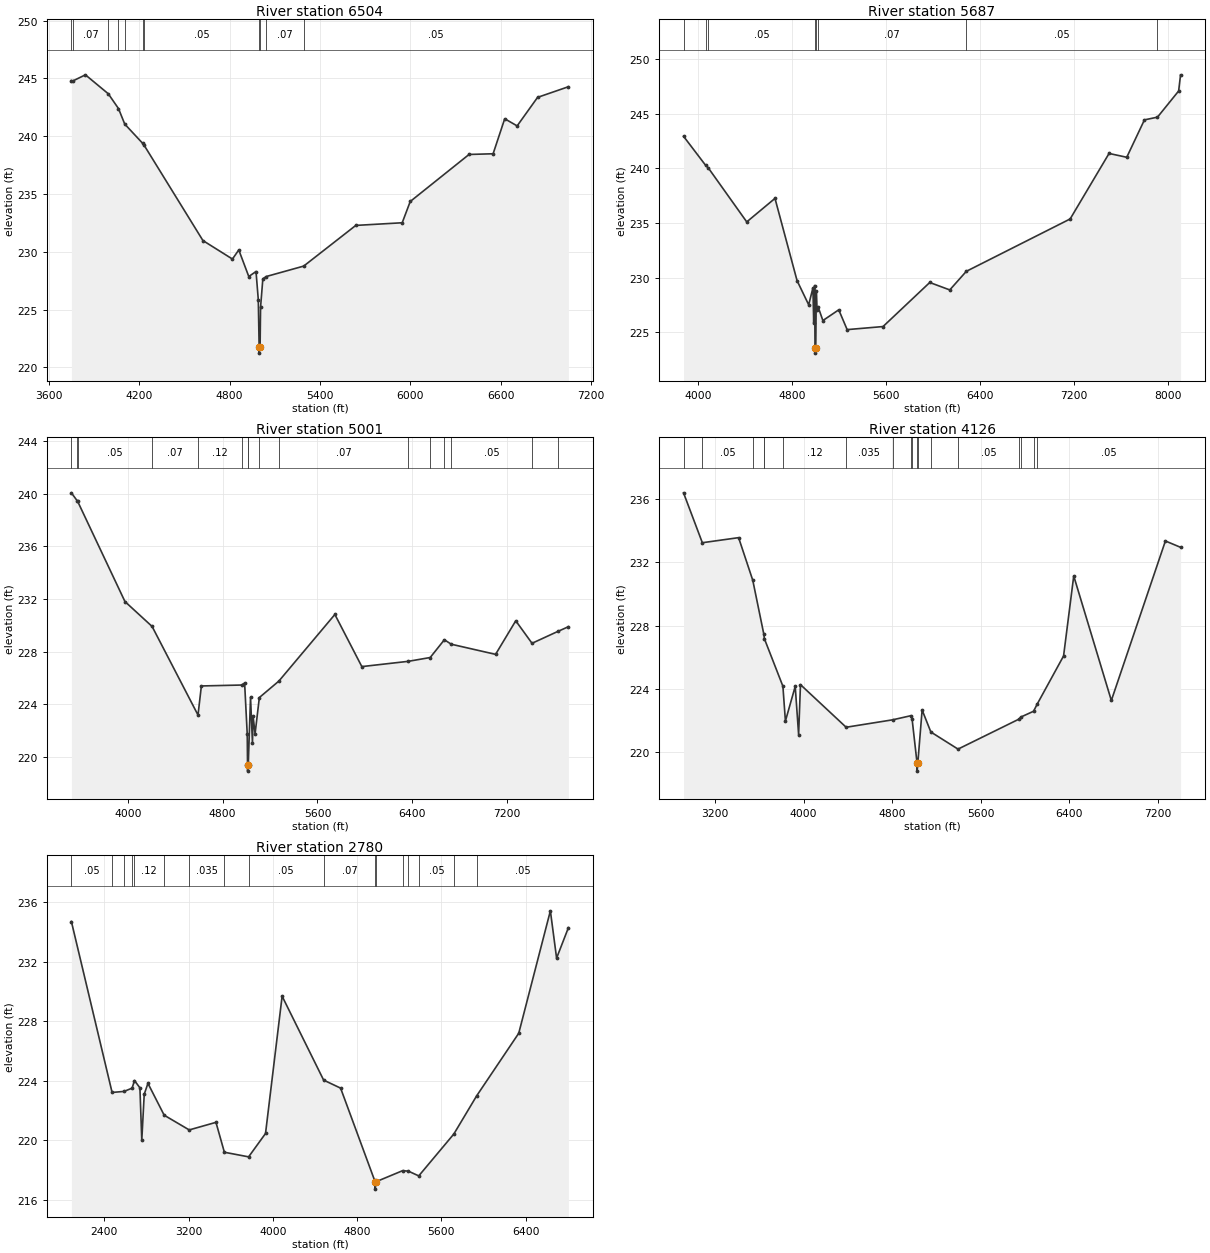
Type RM Length L Ch R = 1 ,6504    ,817,817,817
BEGIN DESCRIPTION:
XS7544
END DESCRIPTION:
XS GIS Cut Line= 3
      2444340.33     13658969.85      2445644.25     13658113.26
      2446310.25     13656505.34
#Sta/Elev= 30
    3750  244.81    3758  244.77  3843.1  245.31    3995  243.67  4062.8  242.39
  4104.2  241.05  4224.2  239.37  4230.9  239.26  4623.5  230.97  4819.4  229.37
  4861.5  230.16  4927.9  227.86    4976  228.29  4991.1  225.86  4996.8  221.73
  4997.3  221.23    5003  221.73  5006.2   225.2  5021.3  227.66  5044.3  227.86
  5292.5  228.76  5638.5  232.28  5946.8  232.51  6000.1  234.35  6390.6  238.42
  6550.4  238.48  6627.5  241.51    6710  240.89  6845.7  243.36  7050.5  244.28
#Mann= 11 ,-1 , 0
    3750     .05       0    3758     .07       0    3995     .05       0
  4062.8    .035       0  4104.2     .05       0  4224.2    .035       0
  4230.9     .05       0  4996.8     .05       0    5003     .05       0
  5044.3     .07       0  5292.5     .05       0
Bank Sta=4996.8,5003
XS Rating Curve= 0 ,0
Exp/Cntr=0.3,0.1

Type RM Length L Ch R = 1 ,5687    ,686,686,686
BEGIN DESCRIPTION:
XS7543
END DESCRIPTION:
XS GIS Cut Line= 4
      2444387.86     13659112.64      2445301.61      13659093.6
      2446329.54     13658208.44       2446462.7     13656258.65
#Sta/Elev= 30
  3878.9  242.92  4066.3  240.27  4089.9  240.02  4416.2  235.09  4656.2  237.24
  4843.9  229.72  4942.7  227.51  4978.9  229.06  4985.5  225.84  4993.1  229.27
  4996.6  223.59  4997.1  223.09  5002.9  223.59  5007.4  228.78    5014  227.02
  5022.4  227.33  5063.4  226.07  5198.3  227.05  5269.6  225.24  5574.6  225.52
  5971.8  229.55  6141.9  228.87  6282.6  230.57  7165.2  235.36  7495.9  241.35
  7646.3     241  7796.6  244.42  7907.5  244.67  8087.3  247.06  8103.7  248.54
#Mann= 8 ,-1 , 0
  3878.9     .05       0  4066.3     .07       0  4089.9     .05       0
  4996.6     .05       0  5002.9     .05       0  5022.4     .07       0
  6282.6     .05       0  7907.5    .035       0
Bank Sta=4996.6,5002.9
XS Rating Curve= 0 ,0
Exp/Cntr=0.3,0.1

Type RM Length L Ch R = 1 ,5001    ,875,875,875
BEGIN DESCRIPTION:
E21292
END DESCRIPTION:
XS GIS Cut Line= 4
      2444439.37     13659257.95      2445600.39     13659453.27
      2446218.88     13659127.74      2447715.91     13657359.51
#Sta/Elev= 30
  3524.2  240.07  3575.1  239.44    3576  239.44  3976.1  231.81    4205  229.92
  4592.4  223.19  4620.8   225.4  4960.8  225.47  4985.6  225.62  5007.7  221.73
  5010.2  219.43  5010.7  218.93  5016.5  219.43  5035.4  224.54  5051.7  221.08
  5057.4  223.08  5073.8  221.77  5109.9  224.52  5274.6  225.77    5747  230.83
  5974.4  226.87  6366.1  227.27  6551.2  227.56  6670.9  228.91  6728.7  228.57
  7102.7   227.8    7273  230.35  7410.2  228.64  7627.5  229.54  7717.3   229.9
#Mann= 16 ,-1 , 0
  3524.2     .05       0  3575.1     .07       0    3576     .05       0
    4205     .07       0  4592.4     .12       0  4960.8     .07       0
  5010.2     .05       0  5016.5     .07       0  5109.9     .05       0
  5274.6     .07       0  6366.1     .12       0  6551.2     .05       0
  6670.9     .07       0  6728.7     .05       0  7410.2    .035       0
  7627.5     .05       0
Bank Sta=5010.2,5016.5
XS Rating Curve= 0 ,0
Exp/Cntr=0.3,0.1

Type RM Length L Ch R = 1 ,4126    ,1346,1346,1346
BEGIN DESCRIPTION:
E21291
END DESCRIPTION:
XS GIS Cut Line= 4
      2444526.21     13659420.73      2445947.61      13660017.5
      2446576.95     13659616.03      2448062.77     13657989.22
#Sta/Elev= 30
  2914.5  236.38  3084.4  233.23  3412.1  233.55  3540.1  230.86  3639.9  227.46
  3645.6  227.16  3812.4  224.17  3835.1  221.97  3923.7  224.16  3954.4  221.12
  3971.2  224.27  4383.8  221.58  4804.7  222.05  4969.1  222.31    4980  222.09
  5024.8  219.31  5025.3  218.81  5031.4  219.31  5070.4  222.67  5149.4  221.28
  5394.9   220.2  5947.5   222.1  5961.2  222.22  6077.4  222.59  6111.8  223.06
  6348.6  226.08  6440.5  231.13  6780.3  223.27  7268.8  233.34  7405.8  232.94
#Mann= 18 ,-1 , 0
  2914.5     .07       0  3084.4     .05       0  3540.1     .07       0
  3639.9     .05       0  3645.6     .07       0  3812.4     .12       0
  4383.8    .035       0  4804.7     .07       0  4969.1    .035       0
    4980     .12       0  5024.8     .05       0  5031.4     .12       0
  5149.4     .07       0  5394.9     .05       0  5947.5     .12       0
  5961.2     .05       0  6077.4     .07       0  6111.8     .05       0
Bank Sta=5024.8,5031.4
XS Rating Curve= 0 ,0
Exp/Cntr=0.3,0.1

Type RM Length L Ch R = 1 ,2780    ,0,0,0
BEGIN DESCRIPTION:
E21290
END DESCRIPTION:
XS GIS Cut Line= 4
       2444840.8     13659767.92      2446696.31     13660592.59
       2447314.8     13660115.16      2448150.17     13658401.02
#Sta/Elev= 30
  2087.4   234.7  2473.8  223.21  2587.8  223.28  2663.7   223.5  2686.5  224.01
  2737.9  223.52  2755.7     220  2778.9  223.09  2814.2  223.82  2968.3  221.68
    3206  220.69  3459.9   221.2  3539.8  219.19  3769.9  218.88  3930.4  220.45
    4088  229.68  4482.1  224.04  4643.2   223.5  4970.6  217.21  4971.1  216.71
  4980.7  217.21  5231.7  217.95  5286.4  217.92  5385.2   217.6  5718.7  220.42
  5934.8  222.98  6334.5  227.19  6634.8  235.42  6693.8  232.24  6806.1  234.29
#Mann= 17 ,-1 , 0
  2087.4     .05       0  2473.8     .07       0  2587.8     .12       0
  2663.7     .07       0  2686.5     .12       0  2968.3     .07       0
    3206    .035       0  3539.8     .07       0  3769.9     .05       0
  4482.1     .07       0  4970.6     .05       0  4980.7     .07       0
  5231.7      .1       0  5286.4     .07       0  5385.2     .05       0
  5718.7     .07       0  5934.8     .05       0
Bank Sta=4970.6,4980.7
XS Rating Curve= 0 ,0
Exp/Cntr=0.3,0.1

Chan Stop Cuts=-1
Use User Specified Reach Order=0
Composite Channel Slope=5