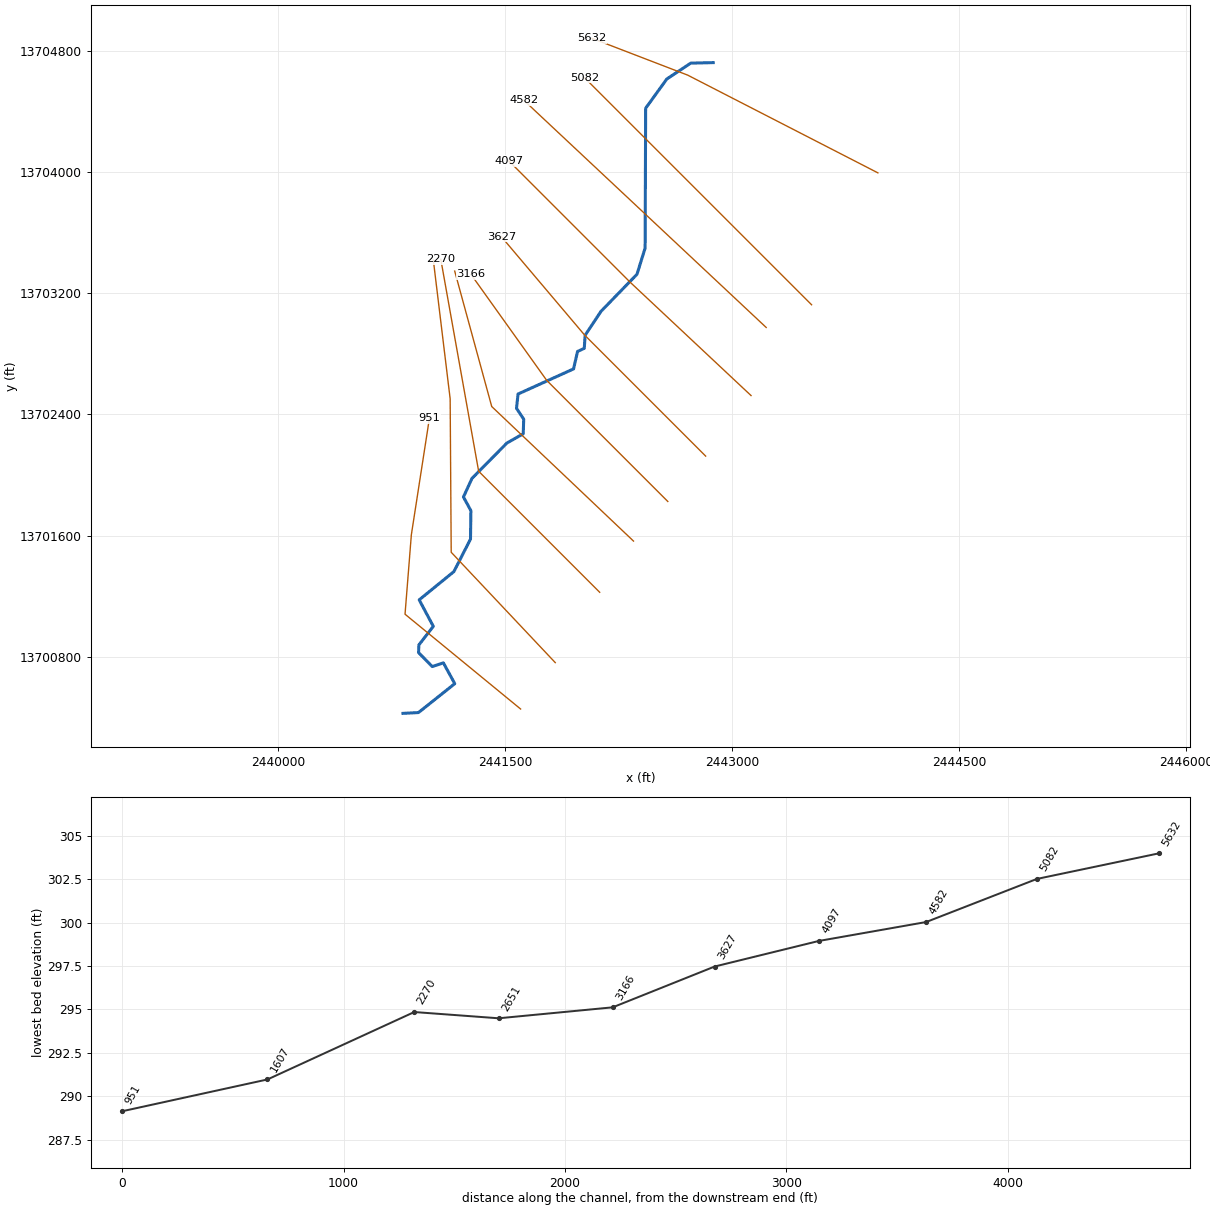
--- Stream0723.prj (project) ---

Proj Title=Stream0723 Base Level Engineering
Current Plan=p01
Default Exp/Contr=0.3,0.1
English Units
Geom File=g01
Flow File=f01
Plan File=p01
BEGIN DESCRIPTION:
Stream0723
END DESCRIPTION:

--- Stream0723.p01 (plan) ---

Plan Title=Multiple Run
Short Identifier=Multiple
Geom File=g01
Flow File=f01
Subcritical Flow
K Sum by GR= 0
Std Step Tol= 0.01
Critical Tol= 0.01
Num of Std Step Trials= 20
Max Error Tol= 0.3
Flow Tol Ratio= 0.001
Split Flow NTrial= 30
Split Flow Tol= 0.02
Split Flow Ratio= 0.02
Log Output Level= 0
Friction Slope Method= 1
Unsteady Friction Slope Method= 2
Unsteady Bridges Friction Slope Method= 1
Parabolic Critical Depth
Global Vel Dist=  1 , 1 , 1
Global Log Level= 0
CheckData=True
Encroach Param= -1, 0, 0, 0
BEGIN DESCRIPTION:
Multiple Run
END DESCRIPTION:

--- Stream0723.f01 (steady flow) ---

Flow Title=Multiple
Number of Profiles=7
Profile Names=10-year,25-year,50-year,1pct_min,100-year,1pct_plu,500-year
River Rch & RM= Stream0723,Reach-1,5632
     699    1117    1489     961    1917    3825    3146
Boundary for River Rch & Prof#=Stream0723,Reach-1,1
Up Type=0
Dn Type=3
Dn Slope=0.005
Boundary for River Rch & Prof#=Stream0723,Reach-1,2
Up Type=0
Dn Type=3
Dn Slope=0.005
Boundary for River Rch & Prof#=Stream0723,Reach-1,3
Up Type=0
Dn Type=3
Dn Slope=0.005
Boundary for River Rch & Prof#=Stream0723,Reach-1,4
Up Type=0
Dn Type=3
Dn Slope=0.005
Boundary for River Rch & Prof#=Stream0723,Reach-1,5
Up Type=0
Dn Type=3
Dn Slope=0.005
Boundary for River Rch & Prof#=Stream0723,Reach-1,6
Up Type=0
Dn Type=3
Dn Slope=0.005
Boundary for River Rch & Prof#=Stream0723,Reach-1,7
Up Type=0
Dn Type=3
Dn Slope=0.005

--- Stream0723.g01 (geometry) ---

Geom Title=Existing Conditions

River Reach=Stream0723,Reach-1
Reach XY= 30
      2442875.00     13704725.00      2442726.45     13704721.49
      2442568.67     13704616.96      2442428.55     13704423.53
      2442425.20     13703499.92      2442371.39     13703326.50
      2442133.16     13703081.05      2442028.65     13702923.43
      2442022.92     13702837.02      2441978.56     13702816.50
      2441952.27     13702701.12      2441585.30     13702535.11
      2441575.38     13702440.28      2441622.83     13702369.02
      2441619.70     13702272.33      2441511.80     13702211.36
      2441280.83     13701977.30      2441224.70     13701854.83
      2441273.76     13701764.50      2441271.25     13701576.55
      2441161.39     13701361.76      2440932.28     13701175.10
      2441025.50     13700999.97      2440930.08     13700877.28
      2440928.10     13700826.62      2441018.32     13700734.30
      2441092.05     13700758.76      2441167.33     13700621.35
      2440927.50     13700430.35      2440825.00     13700425.00

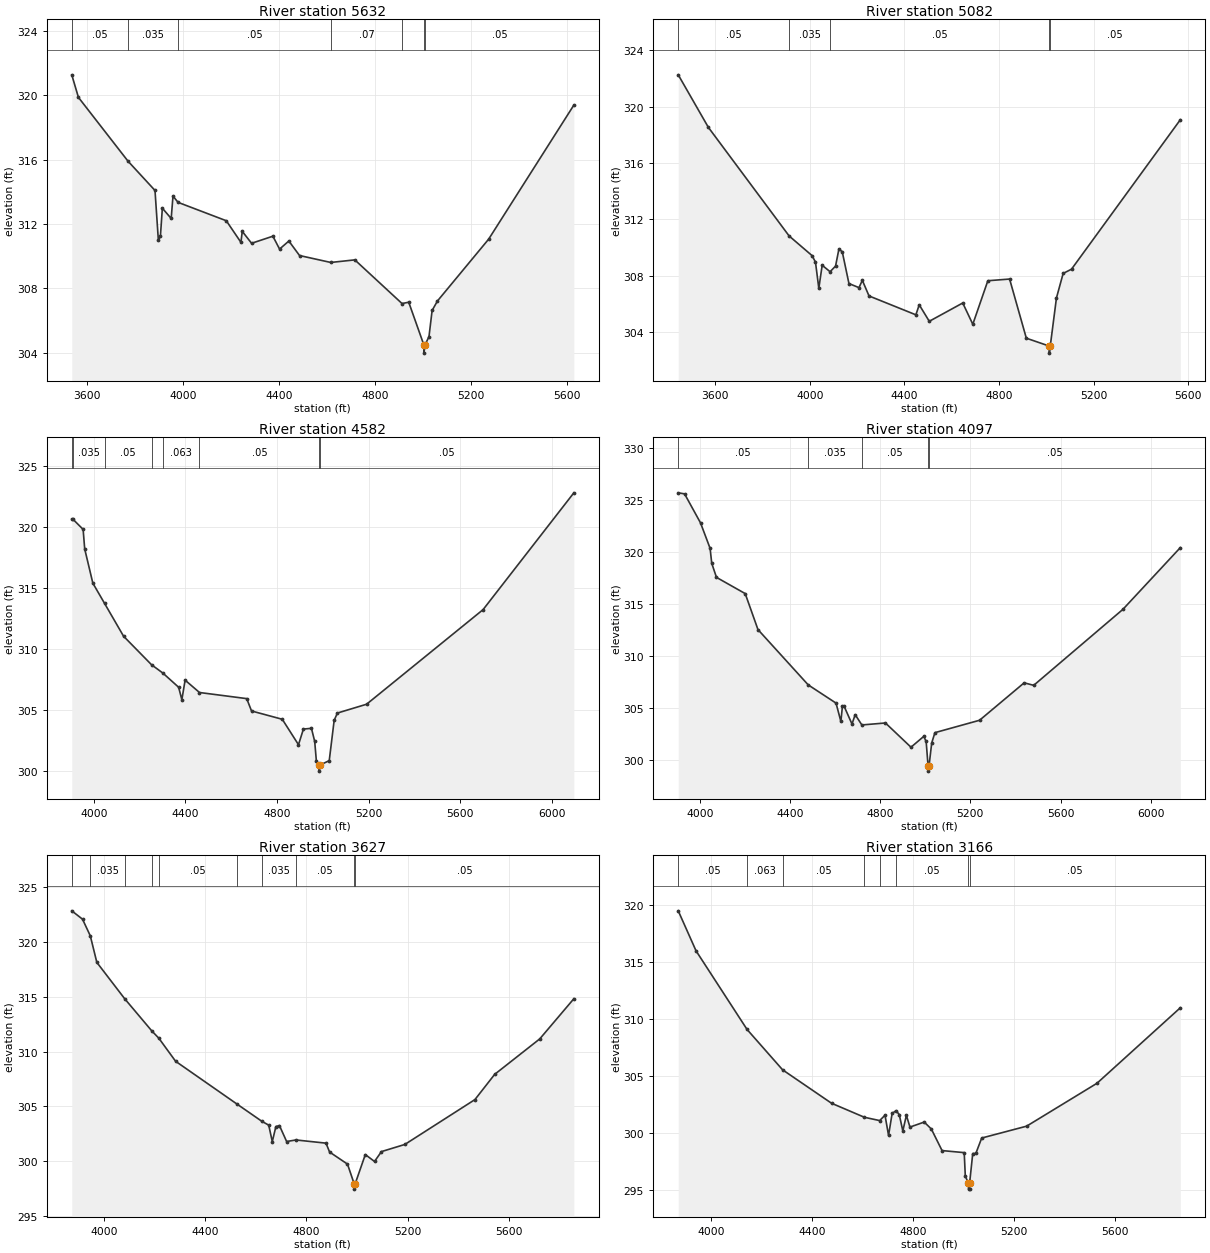
Type RM Length L Ch R = 1,5632,550,550,550
BEGIN DESCRIPTION:
Stream0723 7.0
END DESCRIPTION:
XS GIS Cut Line= 3
      2443963.17     13703996.54      2442706.25     13704642.36
      2442074.31     13704885.42
#Sta/Elev= 30
  3537.7  321.26  3565.4  319.86  3771.8  315.90  3884.2  314.08  3898.2  310.99
  3906.7  311.23  3914.8  312.98  3951.6  312.34  3959.1  313.73  3980.4  313.34
  4181.0  312.20  4241.9  310.86  4247.5  311.54  4286.3  310.80  4375.0  311.24
  4402.8  310.44  4441.5  310.94  4485.9  310.04  4615.9  309.61  4716.1  309.77
  4912.5  307.06  4940.5  307.14  5003.7  304.48  5003.9  303.98  5007.8  304.48
  5024.8  305.00  5037.9  306.63  5060.2  307.22  5273.4  311.06  5627.9  319.38
#Mann=7,-1,0
  3537.7    0.05       0  3771.8   0.035       0  3980.4    0.05       0
  4615.9    0.07       0  4912.5    0.05       0  5003.7    0.05       0
  5007.8    0.05       0
Bank Sta=5003.7,5007.8
Exp/Cntr=0.3,0.1

Type RM Length L Ch R = 1,5082,500,500,500
BEGIN DESCRIPTION:
Stream0723 6.0
END DESCRIPTION:
XS GIS Cut Line= 3
      2443525.03     13703124.97      2442425.00     13704225.00
      2442024.98     13704625.02
#Sta/Elev= 30
  3444.3  322.27  3571.6  318.54  3912.8  310.83  4010.0  309.43  4024.2  308.97
  4038.3  307.11  4052.5  308.75  4085.9  308.29  4109.0  308.69  4123.2  309.90
  4137.3  309.71  4165.6  307.45  4208.0  307.16  4222.2  307.68  4250.4  306.57
  4448.4  305.23  4462.6  305.94  4505.0  304.77  4646.4  306.07  4688.9  304.56
  4752.5  307.65  4844.4  307.77  4915.1  303.57  5012.1  303.01  5012.3  302.51
  5016.2  303.01  5042.4  306.43  5070.7  308.17  5106.0  308.47  5565.7  319.08
#Mann=5,-1,0
  3444.3    0.05       0  3912.8   0.035       0  4085.9    0.05       0
  5012.1    0.05       0  5016.2    0.05       0
Bank Sta=5012.1,5016.2
Exp/Cntr=0.3,0.1

Type RM Length L Ch R = 1,4582,485,485,485
BEGIN DESCRIPTION:
Stream0723 5.0
END DESCRIPTION:
XS GIS Cut Line= 3
      2443225.02     13702974.98      2442425.00     13703725.00
      2441625.00     13704475.00
#Sta/Elev= 30
  3903.4  320.66  3906.9  320.66  3953.0  319.80  3959.9  318.20  3995.5  315.40
  4046.6  313.75  4129.8  311.06  4251.9  308.73  4301.3  308.05  4370.2  306.89
  4384.3  305.87  4398.5  307.47  4461.3  306.46  4667.6  305.96  4688.6  304.95
  4823.0  304.27  4893.8  302.19  4915.3  303.47  4950.4  303.53  4964.6  302.46
  4971.9  300.85  4984.0  300.53  4984.2  300.03  4988.2  300.53  5028.1  300.89
  5049.6  304.18  5063.7  304.78  5191.2  305.50  5700.2  313.24  6096.6  322.79
#Mann=8,-1,0
  3903.4    0.05       0  3906.9   0.035       0  4046.6    0.05       0
  4251.9   0.035       0  4301.3   0.063       0  4461.3    0.05       0
  4984.0    0.05       0  4988.2    0.05       0
Bank Sta=4984,4988.2
Exp/Cntr=0.3,0.1

Type RM Length L Ch R = 1,4097,470,470,470
BEGIN DESCRIPTION:
Stream0723 4.0
END DESCRIPTION:
XS GIS Cut Line= 3
      2443124.97     13702525.02      2442325.00     13703275.00
      2441525.01     13704074.99
#Sta/Elev= 30
  3903.7  325.70  3931.8  325.60  4002.6  322.81  4045.1  320.36  4052.4  318.92
  4073.4  317.57  4200.9  316.01  4257.5  312.55  4480.6  307.23  4603.9  305.48
  4625.4  303.72  4632.2  305.16  4639.5  305.19  4674.7  303.47  4688.9  304.37
  4718.5  303.38  4823.2  303.57  4936.5  301.24  4993.2  302.28  5003.8  301.79
  5012.3  299.44  5012.5  298.94  5016.5  299.44  5028.5  301.65  5042.7  302.64
  5240.7  303.83  5438.7  307.43  5481.1  307.19  5877.1  314.50  6131.6  320.43
#Mann=5,-1,0
  3903.7    0.05       0  4480.6   0.035       0  4718.5    0.05       0
  5012.3    0.05       0  5016.5    0.05       0
Bank Sta=5012.3,5016.5
Exp/Cntr=0.3,0.1

Type RM Length L Ch R = 1,3627,461,461,461
BEGIN DESCRIPTION:
Stream0723 3.0
END DESCRIPTION:
XS GIS Cut Line= 3
      2442824.97     13702125.03      2442025.00     13702925.00
      2441475.00     13703575.00
#Sta/Elev= 30
  3873.1  322.83  3915.5  322.07  3946.3  320.55  3972.1  318.13  4081.7  314.83
  4188.7  311.90  4217.0  311.22  4283.2  309.12  4526.3  305.21  4623.2  303.66
  4650.9  303.30  4665.0  301.80  4679.2  303.17  4693.3  303.26  4721.6  301.81
  4758.6  301.95  4877.1  301.66  4891.3  300.85  4962.0  299.75  4988.1  297.97
  4988.4  297.47  4992.5  297.97  5032.4  300.62  5068.7  299.99  5096.1  300.89
  5188.4  301.54  5465.3  305.63  5543.3  307.93  5721.3  311.16  5855.9  314.82
#Mann=10,-1,0
  3873.1    0.05       0  3946.3   0.035       0  4081.7    0.05       0
  4188.7   0.035       0  4217.0    0.05       0  4526.3   0.063       0
  4623.2   0.035       0  4758.6    0.05       0  4988.1    0.05       0
  4992.5    0.05       0
Bank Sta=4988.1,4992.5
Exp/Cntr=0.3,0.1

Type RM Length L Ch R = 1,3166,515,515,515
BEGIN DESCRIPTION:
Stream0723 2.0
END DESCRIPTION:
XS GIS Cut Line= 3
      2442574.97     13701825.03      2441775.00     13702625.00
      2441274.97     13703325.04
#Sta/Elev= 30
  3868.7  319.52  3939.4  316.01  4141.7  309.12  4282.7  305.58  4476.8  302.65
  4607.1  301.42  4667.7  301.13  4688.9  301.60  4703.0  299.83  4717.2  301.76
  4733.0  302.00  4745.5  301.65  4759.6  300.22  4773.7  301.59  4787.9  300.56
  4844.5  301.00  4872.7  300.39  4915.2  298.50  5003.1  298.32  5007.4  296.27
  5019.9  295.62  5020.2  295.12  5024.1  295.12  5024.4  295.62  5036.9  298.24
  5049.2  298.25  5072.5  299.60  5250.7  300.64  5529.7  304.40  5860.3  311.02
#Mann=8,-1,0
  3868.7    0.05       0  4141.7   0.063       0  4282.7    0.05       0
  4607.1   0.063       0  4667.7   0.035       0  4733.0    0.05       0
  5019.9    0.05       0  5024.4    0.05       0
Bank Sta=5019.9,5024.4
Exp/Cntr=0.3,0.1

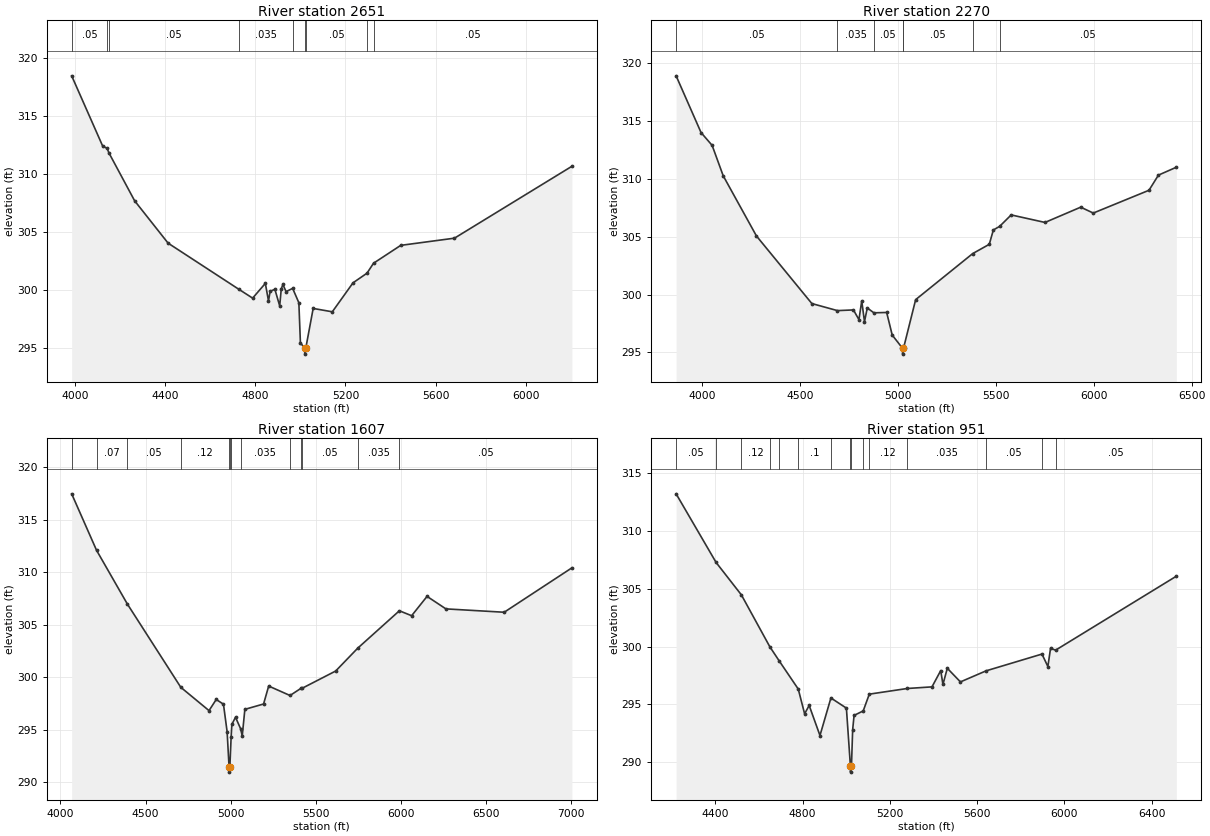
Type RM Length L Ch R = 1,2651,381,381,381
BEGIN DESCRIPTION:
E21294
END DESCRIPTION:
XS GIS Cut Line= 3
      2442348.24     13701563.52      2441411.46     13702452.57
      2441166.83     13703347.54
#Sta/Elev= 30
  3985.4  318.49  4123.2  312.42  4142.8  312.24  4150.2  311.86  4264.8  307.71
  4413.2  304.06  4728.0  300.07  4788.2  299.32  4844.6  300.59  4858.6  299.08
  4865.9  299.91  4886.9  300.08  4908.3  298.65  4915.2  300.11  4922.5  300.50
  4936.6  299.88  4965.8  300.16  4993.3  298.92  5000.2  295.47  5019.3  294.99
  5019.6  294.49  5023.9  294.99  5056.8  298.43  5141.7  298.14  5233.6  300.64
  5295.6  301.47  5324.6  302.33  5445.3  303.87  5683.7  304.49  6204.7  310.69
#Mann=9,-1,0
  3985.4    0.05       0  4142.8   0.035       0  4150.2    0.05       0
  4728.0   0.035       0  4965.8    0.05       0  5019.3    0.05       0
  5023.9    0.05       0  5295.6   0.035       0  5324.6    0.05       0
Bank Sta=5019.3,5023.9
Exp/Cntr=0.3,0.1

Type RM Length L Ch R = 1,2270,663,663,663
BEGIN DESCRIPTION:
Stream0723 1.0
END DESCRIPTION:
XS GIS Cut Line= 3
      2442124.97     13701225.03      2441325.00     13702025.00
      2441075.00     13703425.02
#Sta/Elev= 30
  3868.4  318.90  3995.6  314.00  4052.2  312.89  4108.8  310.26  4278.5  305.06
  4561.3  299.22  4692.0  298.61  4773.5  298.67  4801.7  297.83  4815.9  299.45
  4830.0  297.66  4844.2  298.84  4877.9  298.42  4943.2  298.45  4971.5  296.50
  5024.4  295.35  5024.7  294.85  5029.0  295.35  5091.2  299.56  5382.5  303.54
  5467.0  304.34  5487.8  305.58  5519.8  305.89  5578.8  306.88  5751.4  306.23
  5933.8  307.55  5997.8  307.04  6282.2  309.01  6330.5  310.32  6421.9  311.00
#Mann=7,-1,0
  3868.4    0.05       0  4692.0   0.035       0  4877.9    0.05       0
  5024.4    0.05       0  5029.0    0.05       0  5382.5   0.035       0
  5519.8    0.05       0
Bank Sta=5024.4,5029
Exp/Cntr=0.3,0.1

Type RM Length L Ch R = 1,1607,656,656,656
BEGIN DESCRIPTION:
XS7547
END DESCRIPTION:
XS GIS Cut Line= 4
      2441831.27     13700760.40      2441143.75     13701489.58
      2441136.81     13702503.47      2441025.70     13703420.06
#Sta/Elev= 30
  4066.1  317.48  4212.3  312.10  4393.0  306.99  4707.3  299.05  4873.1  296.83
  4915.5  297.89  4958.0  297.44  4979.5  294.82  4990.9  291.47  4991.3  290.97
  4995.6  291.47  5003.0  294.30  5007.4  295.52  5028.8  296.20  5059.1  295.09
  5068.3  294.41  5083.7  296.95  5193.7  297.46  5223.7  299.17  5349.1  298.27
  5413.3  298.95  5420.6  298.96  5617.3  300.60  5747.1  302.78  5991.7  306.34
  6063.7  305.87  6154.3  307.71  6265.1  306.52  6607.6  306.20  7005.5  310.43
#Mann=13,-1,0
  4066.1    0.05       0  4212.3    0.07       0  4393.0    0.05       0
  4707.3    0.12       0  4990.9    0.05       0  4995.6    0.12       0
  5003.0    0.05       0  5059.1   0.035       0  5349.1   0.063       0
  5413.3   0.035       0  5420.6    0.05       0  5747.1   0.035       0
  5991.7    0.05       0
Bank Sta=4990.9,4995.6
Exp/Cntr=0.3,0.1

Type RM Length L Ch R = 1,951,0,0,0
BEGIN DESCRIPTION:
E21293
END DESCRIPTION:
XS GIS Cut Line= 4
      2441602.36     13700453.79      2440838.67     13701080.26
      2440880.43     13701605.32      2440999.77     13702375.03
#Sta/Elev= 30
  4219.9  313.23  4403.2  307.29  4519.2  304.48  4649.6  299.99  4693.5  298.74
  4779.9  296.33  4809.0  294.19  4829.9  294.91  4879.4  292.31  4929.6  295.56
  5000.6  294.68  5019.1  289.64  5019.5  289.14  5023.8  289.64  5029.3  292.81
  5035.8  294.05  5077.7  294.44  5105.6  295.89  5279.8  296.38  5393.0  296.52
  5433.1  297.93  5443.2  296.73  5463.2  298.13  5523.4  296.95  5641.4  297.91
  5897.2  299.36  5924.3  298.28  5936.5  299.85  5959.9  299.70  6513.3  306.10
#Mann=15,-1,0
  4219.9    0.05       0  4403.2    0.07       0  4519.2    0.12       0
  4649.6     0.1       0  4693.5    0.12       0  4779.9     0.1       0
  4929.6    0.12       0  5019.1    0.05       0  5023.8    0.12       0
  5077.7    0.12       0  5105.6    0.12       0  5279.8   0.035       0
  5641.4    0.05       0  5897.2   0.035       0  5959.9    0.05       0
Bank Sta=5019.1,5023.8
Exp/Cntr=0.3,0.1

Chan Stop Cuts=-1