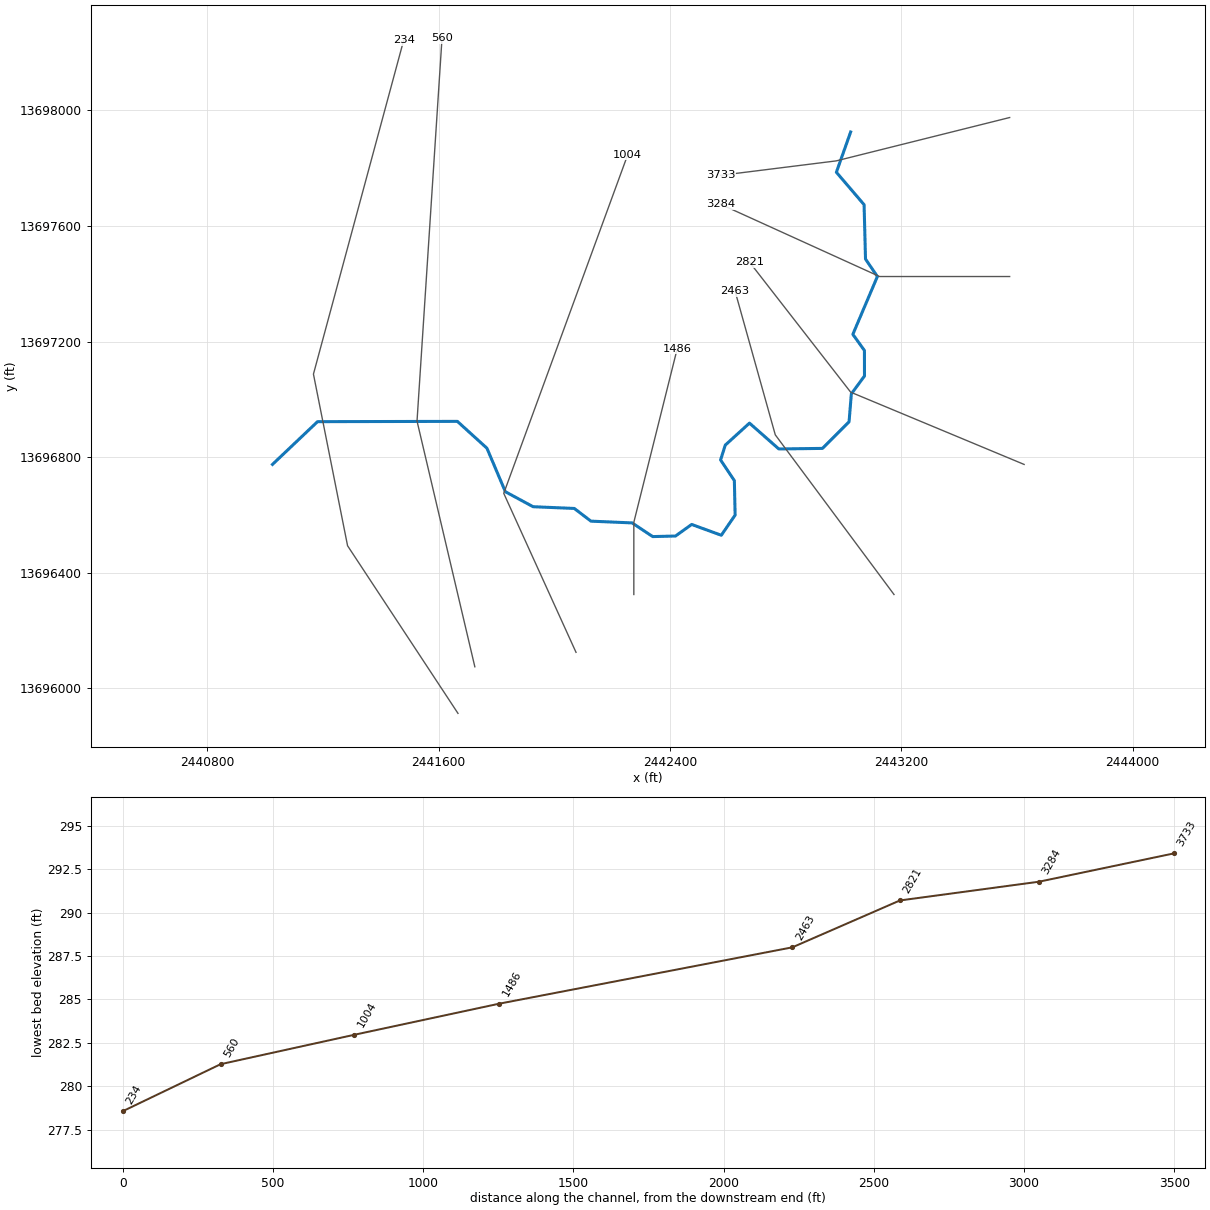
--- Stream0724.prj (project) ---

Proj Title=Stream0724 Base Level Engineering
Current Plan=p01
Default Exp/Contr=0.3,0.1
English Units
Geom File=g01
Flow File=f01
Plan File=p01
BEGIN DESCRIPTION:
Stream0724
END DESCRIPTION:

--- Stream0724.p01 (plan) ---

Plan Title=Multiple Run
Short Identifier=Multiple
Geom File=g01
Flow File=f01
Subcritical Flow
K Sum by GR= 0
Std Step Tol= 0.01
Critical Tol= 0.01
Num of Std Step Trials= 20
Max Error Tol= 0.3
Flow Tol Ratio= 0.001
Split Flow NTrial= 30
Split Flow Tol= 0.02
Split Flow Ratio= 0.02
Log Output Level= 0
Friction Slope Method= 1
Unsteady Friction Slope Method= 2
Unsteady Bridges Friction Slope Method= 1
Parabolic Critical Depth
Global Vel Dist=  1 , 1 , 1
Global Log Level= 0
CheckData=True
Encroach Param= -1, 0, 0, 0
BEGIN DESCRIPTION:
Multiple Run
END DESCRIPTION:

--- Stream0724.f01 (steady flow) ---

Flow Title=Multiple
Number of Profiles=7
Profile Names=10-year,25-year,50-year,1pct_min,100-year,1pct_plu,500-year
River Rch & RM= Stream0724,Reach-1,3733
     513     804    1059     675    1347    2688    2159
Boundary for River Rch & Prof#=Stream0724,Reach-1,1
Up Type=0
Dn Type=3
Dn Slope=0.005
Boundary for River Rch & Prof#=Stream0724,Reach-1,2
Up Type=0
Dn Type=3
Dn Slope=0.005
Boundary for River Rch & Prof#=Stream0724,Reach-1,3
Up Type=0
Dn Type=3
Dn Slope=0.005
Boundary for River Rch & Prof#=Stream0724,Reach-1,4
Up Type=0
Dn Type=3
Dn Slope=0.005
Boundary for River Rch & Prof#=Stream0724,Reach-1,5
Up Type=0
Dn Type=3
Dn Slope=0.005
Boundary for River Rch & Prof#=Stream0724,Reach-1,6
Up Type=0
Dn Type=3
Dn Slope=0.005
Boundary for River Rch & Prof#=Stream0724,Reach-1,7
Up Type=0
Dn Type=3
Dn Slope=0.005

--- Stream0724.g01 (geometry) ---

Geom Title=Existing Conditions

River Reach=Stream0724,Reach-1
Reach XY= 30
      2443025.00     13697925.00      2442975.57     13697785.61
      2443071.45     13697673.53      2443076.38     13697485.44
      2443117.44     13697425.00      2443032.56     13697225.00
      2443072.64     13697169.11      2443072.83     13697080.98
      2443027.36     13697019.02      2443019.48     13696922.56
      2442927.46     13696830.45      2442776.47     13696828.55
      2442674.98     13696917.92      2442591.22     13696841.75
      2442575.03     13696790.42      2442622.72     13696719.07
      2442625.36     13696599.78      2442577.58     13696530.00
      2442475.01     13696567.40      2442419.11     13696527.36
      2442340.28     13696525.39      2442269.06     13696572.73
      2442126.57     13696578.79      2442069.06     13696622.73
      2441926.53     13696628.74      2441830.58     13696680.58
      2441766.87     13696831.07      2441664.57     13696923.96
      2441180.85     13696922.95      2441025.00     13696775.00

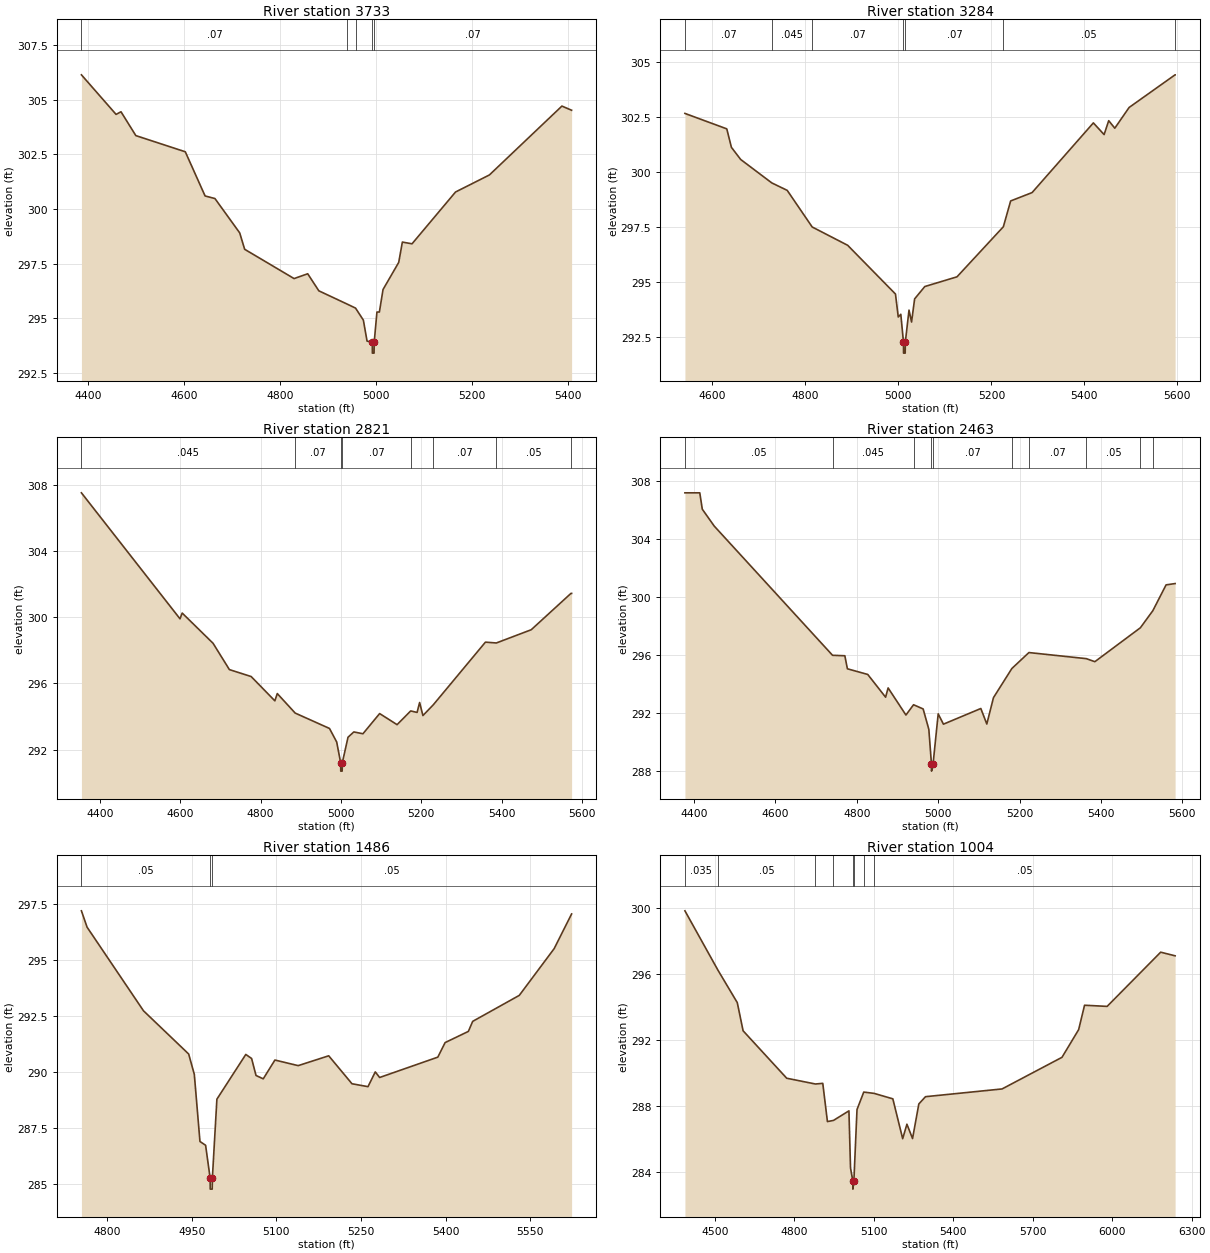
Type RM Length L Ch R = 1,3733,449,449,449
BEGIN DESCRIPTION:
Stream0724 7.0
END DESCRIPTION:
XS GIS Cut Line= 3
      2443575.01     13697975.00      2442975.00     13697825.00
      2442574.99     13697775.00
#Sta/Elev= 30
  4386.2  306.14  4458.4  304.33  4468.7  304.45  4499.6  303.36  4602.7  302.62
  4643.9  300.60  4664.5  300.48  4716.1  298.91  4726.4  298.16  4829.4  296.82
  4857.8  297.04  4881.0  296.26  4940.3  295.65  4957.5  295.47  4973.8  294.92
  4981.5  293.96  4992.4  293.91  4992.6  293.41  4996.1  293.41  4996.4  293.91
  5002.1  295.29  5007.2  295.29  5014.8  296.32  5047.5  297.56  5055.1  298.49
  5075.2  298.41  5165.9  300.78  5236.5  301.56  5387.6  304.71  5407.8  304.52
#Mann=5,-1,0
  4386.2    0.07       0  4940.3    0.05       0  4957.5    0.07       0
  4992.4    0.05       0  4996.4    0.07       0
Bank Sta=4992.4,4996.4
Exp/Cntr=0.3,0.1

Type RM Length L Ch R = 1,3284,463,463,463
BEGIN DESCRIPTION:
Stream0724 6.0
END DESCRIPTION:
XS GIS Cut Line= 3
      2443575.01     13697425.00      2443125.00     13697425.00
      2442574.97     13697675.01
#Sta/Elev= 30
  4540.9  302.65  4630.9  301.95  4640.9  301.11  4660.9  300.56  4727.6  299.50
  4760.9  299.16  4814.6  297.50  4890.9  296.67  4993.7  294.46  4999.7  293.42
  5005.2  293.54  5010.9  292.28  5011.1  291.78  5014.6  291.78  5014.9  292.28
  5022.8  293.73  5028.3  293.19  5034.9  294.24  5056.8  294.80  5126.0  295.24
  5225.7  297.51  5241.4  298.68  5287.5  299.06  5419.3  302.22  5442.4  301.69
  5452.3  302.32  5465.4  301.98  5496.2  302.92  5595.0  304.40  5595.1  304.40
#Mann=7,-1,0
  4540.9    0.07       0  4727.6   0.045       0  4814.6    0.07       0
  5010.9    0.05       0  5014.9    0.07       0  5225.7    0.05       0
  5595.0    0.07       0
Bank Sta=5010.9,5014.9
Exp/Cntr=0.3,0.1

Type RM Length L Ch R = 1,2821,358,358,358
BEGIN DESCRIPTION:
Stream0724 5.0
END DESCRIPTION:
XS GIS Cut Line= 3
      2443624.98     13696775.01      2443025.00     13697025.00
      2442674.98     13697475.03
#Sta/Elev= 30
  4354.2  307.53  4599.6  299.91  4605.0  300.26  4681.9  298.43  4722.5  296.84
  4776.7  296.42  4835.7  294.95  4841.7  295.39  4886.3  294.21  4971.7  293.28
  4989.6  292.46  4999.5  291.20  4999.7  290.70  5003.2  290.70  5003.5  291.20
  5017.8  292.75  5032.2  293.07  5054.9  292.96  5096.5  294.18  5139.9  293.51
  5173.8  294.34  5189.7  294.25  5196.0  294.85  5204.2  294.06  5230.0  294.71
  5359.8  298.50  5387.0  298.45  5473.8  299.25  5572.8  301.45  5574.3  301.45
#Mann=8,-1,0
  4354.2   0.045       0  4886.3    0.07       0  4999.5    0.05       0
  5003.5    0.07       0  5173.8    0.05       0  5230.0    0.07       0
  5387.0    0.05       0  5572.8    0.07       0
Bank Sta=4999.5,5003.5
Exp/Cntr=0.3,0.1

Type RM Length L Ch R = 1,2463,977,977,977
BEGIN DESCRIPTION:
Stream0724 4.0
END DESCRIPTION:
XS GIS Cut Line= 3
      2443174.97     13696325.04      2442764.24     13696877.43
      2442625.01     13697374.96
#Sta/Elev= 30
  4377.5  307.20  4414.0  307.20  4420.2  306.07  4449.4  304.91  4740.4  295.99
  4770.6  295.96  4776.9  295.06  4826.9  294.67  4870.8  293.10  4877.0  293.74
  4920.8  291.87  4939.5  292.58  4963.1  292.29  4977.1  290.88  4983.5  288.50
  4983.7  288.00  4987.5  288.50  5000.1  291.95  5013.0  291.24  5104.9  292.32
  5119.6  291.25  5136.0  293.07  5181.2  295.08  5223.1  296.18  5364.2  295.76
  5385.2  295.55  5497.1  297.89  5527.8  299.07  5560.3  300.85  5582.5  300.94
#Mann=10,-1,0
  4377.5    0.05       0  4740.4   0.045       0  4939.5    0.07       0
  4983.5    0.05       0  4987.5    0.07       0  5181.2    0.05       0
  5223.1    0.07       0  5364.2    0.05       0  5497.1    0.07       0
  5527.8    0.05       0
Bank Sta=4983.5,4987.5
Exp/Cntr=0.3,0.1

Type RM Length L Ch R = 1,1486,482,482,482
BEGIN DESCRIPTION:
Stream0724 3.0
END DESCRIPTION:
XS GIS Cut Line= 3
      2442275.00     13696325.02      2442275.00     13696575.00
      2442424.99     13697174.95
#Sta/Elev= 30
  4754.6  297.19  4764.6  296.46  4864.6  292.72  4944.6  290.79  4954.6  289.88
  4964.6  286.88  4974.6  286.71  4982.6  285.25  4982.8  284.75  4986.3  284.75
  4986.6  285.25  4994.6  288.77  5045.8  290.77  5056.1  290.59  5063.9  289.83
  5076.7  289.68  5097.4  290.52  5138.6  290.27  5192.7  290.71  5233.9  289.46
  5262.3  289.33  5275.2  289.99  5282.9  289.74  5386.0  290.65  5398.9  291.30
  5440.1  291.80  5447.8  292.25  5530.3  293.41  5592.1  295.50  5623.0  297.05
#Mann=3,-1,0
  4754.6    0.05       0  4982.6    0.05       0  4986.6    0.05       0
Bank Sta=4982.6,4986.6
Exp/Cntr=0.3,0.1

Type RM Length L Ch R = 1,1004,444,444,444
BEGIN DESCRIPTION:
Stream0724 2.0
END DESCRIPTION:
XS GIS Cut Line= 3
      2442074.99     13696125.02      2441825.00     13696675.00
      2442253.80     13697846.13
#Sta/Elev= 30
  4386.3  299.85  4510.6  296.26  4584.0  294.28  4606.0  292.57  4770.7  289.69
  4879.1  289.34  4906.9  289.38  4924.5  287.06  4947.3  287.13  5005.7  287.71
  5011.7  284.24  5020.4  283.46  5020.6  282.96  5024.4  283.46  5036.2  287.79
  5061.7  288.85  5101.0  288.77  5171.5  288.44  5208.7  286.02  5224.7  286.90
  5246.0  286.03  5269.7  288.13  5294.9  288.57  5584.1  289.04  5810.4  290.96
  5873.3  292.64  5895.6  294.12  5980.8  294.05  6183.1  297.34  6237.6  297.12
#Mann=8,-1,0
  4386.3   0.035       0  4510.6    0.05       0  4879.1    0.07       0
  4947.3    0.05       0  5020.4    0.05       0  5024.4    0.05       0
  5061.7    0.07       0  5101.0    0.05       0
Bank Sta=5020.4,5024.4
Exp/Cntr=0.3,0.1

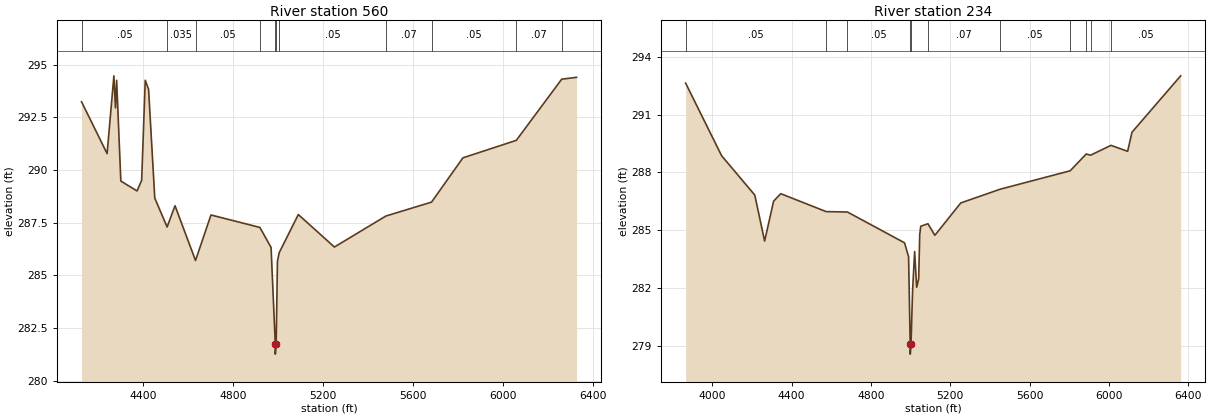
Type RM Length L Ch R = 1,560,326,326,326
BEGIN DESCRIPTION:
Stream0724 1.0
END DESCRIPTION:
XS GIS Cut Line= 3
      2441724.99     13696075.05      2441525.00     13696925.00
      2441611.46     13698248.92
#Sta/Elev= 30
  4126.8  293.24  4240.4  290.78  4270.6  294.47  4277.6  292.95  4282.8  294.26
  4301.4  289.48  4373.3  289.01  4393.9  289.51  4409.9  294.26  4424.7  293.83
  4452.3  288.67  4507.1  287.30  4542.2  288.31  4633.3  285.71  4702.0  287.87
  4919.2  287.28  4969.1  286.33  4987.7  281.77  4987.9  281.27  4991.7  281.77
  4997.4  285.67  5005.2  286.08  5090.2  287.89  5250.5  286.35  5479.5  287.82
  5682.2  288.48  5821.7  290.58  6058.9  291.41  6260.6  294.31  6326.7  294.40
#Mann=11,-1,0
  4126.8    0.05       0  4507.1   0.035       0  4633.3    0.05       0
  4919.2    0.07       0  4987.7    0.05       0  4991.7    0.07       0
  5005.2    0.05       0  5479.5    0.07       0  5682.2    0.05       0
  6058.9    0.07       0  6260.6    0.05       0
Bank Sta=4987.7,4991.7
Exp/Cntr=0.3,0.1

Type RM Length L Ch R = 1,234,0,0,0
BEGIN DESCRIPTION:
E21295
END DESCRIPTION:
XS GIS Cut Line= 4
      2441666.68     13695913.88      2441284.76     13696493.70
      2441166.71     13697087.45      2441478.71     13698241.85
#Sta/Elev= 30
  3865.7  292.63  4047.1  288.86  4214.3  286.82  4263.9  284.43  4309.1  286.50
  4345.3  286.89  4573.9  285.96  4681.2  285.94  4969.2  284.34  4989.6  283.62
  4997.8  279.06  4998.0  278.56  5001.8  279.06  5009.9  281.89  5020.1  283.89
  5030.3  282.03  5040.5  282.47  5045.8  284.77  5050.9  285.20  5087.1  285.33
  5122.1  284.73  5252.8  286.41  5450.6  287.12  5804.4  288.08  5885.1  288.95
  5907.2  288.89  6010.0  289.40  6093.9  289.09  6115.8  290.08  6361.2  293.01
#Mann=11,-1,0
  3865.7    0.05       0  4573.9   0.035       0  4681.2    0.05       0
  4997.8    0.05       0  5001.8    0.05       0  5087.1    0.07       0
  5450.6    0.05       0  5804.4    0.07       0  5885.1    0.05       0
  5907.2    0.07       0  6010.0    0.05       0
Bank Sta=4997.8,5001.8
Exp/Cntr=0.3,0.1

Chan Stop Cuts=-1