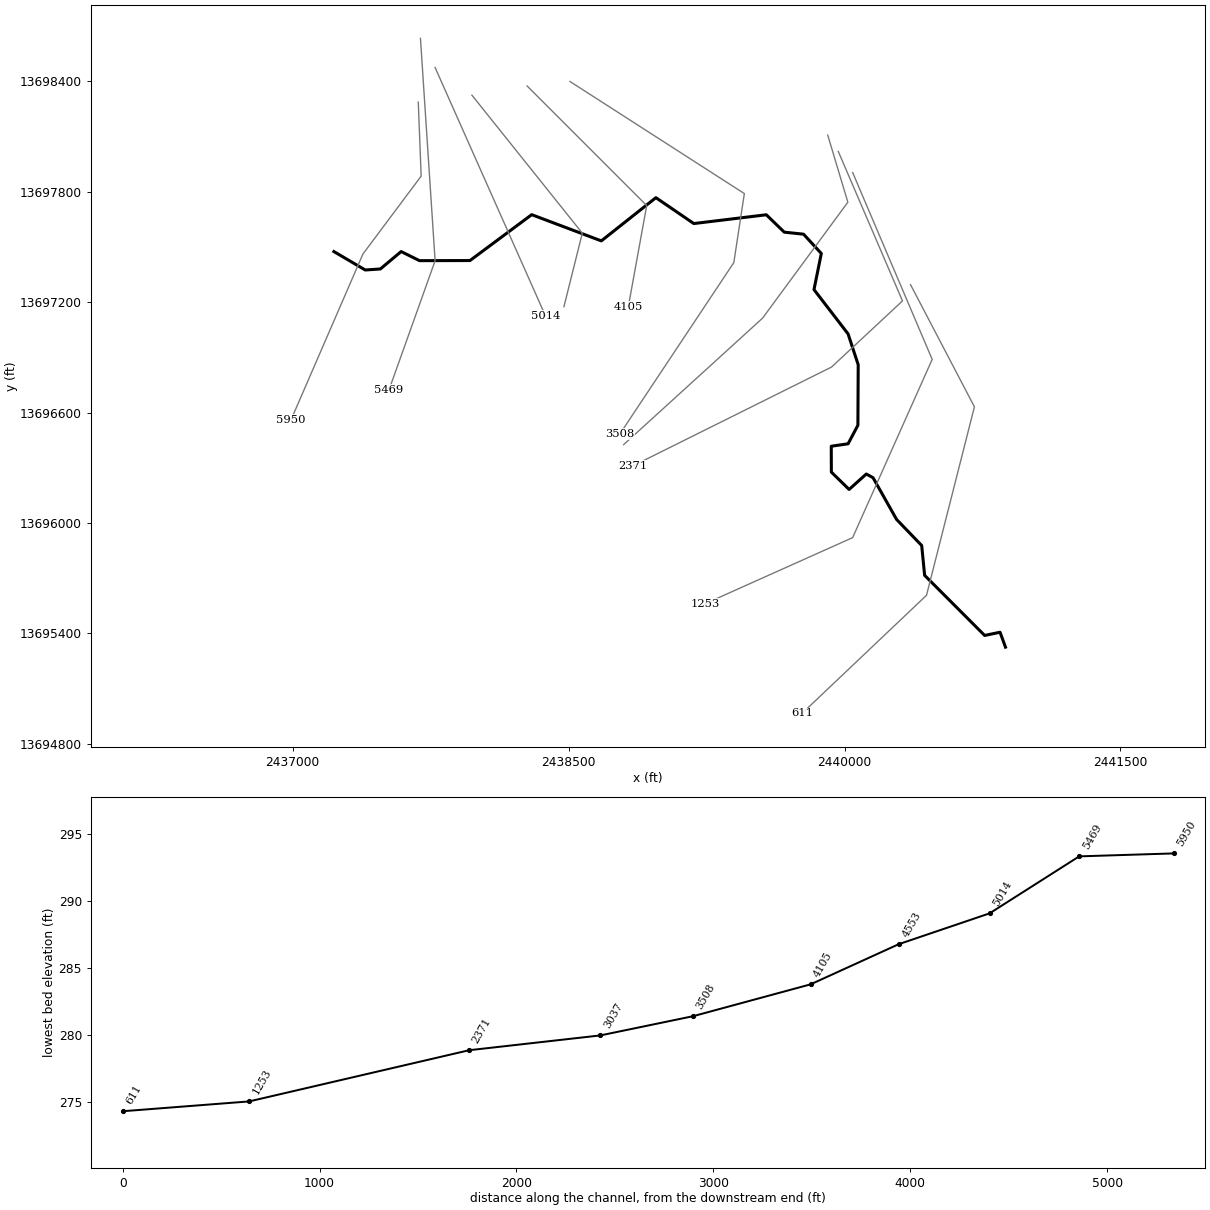
--- Stream0725.prj (project) ---

Proj Title=Stream0725 Base Level Engineering
Current Plan=p01
Default Exp/Contr=0.3,0.1
English Units
Geom File=g01
Flow File=f01
Plan File=p01
BEGIN DESCRIPTION:
Stream0725
END DESCRIPTION:

--- Stream0725.p01 (plan) ---

Plan Title=Multiple Run
Short Identifier=Multiple
Geom File=g01
Flow File=f01
Subcritical Flow
K Sum by GR= 0
Std Step Tol= 0.01
Critical Tol= 0.01
Num of Std Step Trials= 20
Max Error Tol= 0.3
Flow Tol Ratio= 0.001
Split Flow NTrial= 30
Split Flow Tol= 0.02
Split Flow Ratio= 0.02
Log Output Level= 0
Friction Slope Method= 1
Unsteady Friction Slope Method= 2
Unsteady Bridges Friction Slope Method= 1
Parabolic Critical Depth
Global Vel Dist=  1 , 1 , 1
Global Log Level= 0
CheckData=True
Encroach Param= -1, 0, 0, 0
BEGIN DESCRIPTION:
Multiple Run
END DESCRIPTION:

--- Stream0725.f01 (steady flow) ---

Flow Title=Multiple
Number of Profiles=7
Profile Names=10-year,25-year,50-year,1pct_min,100-year,1pct_plu,500-year
River Rch & RM= Stream0725,Reach-1,5950
     685    1101    1474     956    1907    3804    3160
River Rch & RM= Stream0725,Reach-1,3037
     980    1607    2181    1431    2855    5696    4849
River Rch & RM= Stream0725,Reach-1,1253
    1031    1693    2300    1510    3012    6010    5121
Boundary for River Rch & Prof#=Stream0725,Reach-1,1
Up Type=0
Dn Type=3
Dn Slope=0.005
Boundary for River Rch & Prof#=Stream0725,Reach-1,2
Up Type=0
Dn Type=3
Dn Slope=0.005
Boundary for River Rch & Prof#=Stream0725,Reach-1,3
Up Type=0
Dn Type=3
Dn Slope=0.005
Boundary for River Rch & Prof#=Stream0725,Reach-1,4
Up Type=0
Dn Type=3
Dn Slope=0.005
Boundary for River Rch & Prof#=Stream0725,Reach-1,5
Up Type=0
Dn Type=3
Dn Slope=0.005
Boundary for River Rch & Prof#=Stream0725,Reach-1,6
Up Type=0
Dn Type=3
Dn Slope=0.005
Boundary for River Rch & Prof#=Stream0725,Reach-1,7
Up Type=0
Dn Type=3
Dn Slope=0.005

--- Stream0725.g01 (geometry) ---

Geom Title=Existing Conditions

River Reach=Stream0725,Reach-1
Reach XY= 30
      2437225.00     13697475.00      2437395.10     13697374.88
      2437477.42     13697380.41      2437590.34     13697475.04
      2437690.21     13697425.54      2437964.50     13697426.20
      2438299.96     13697675.50      2438678.31     13697533.02
      2438975.00     13697767.92      2439180.93     13697627.23
      2439575.00     13697675.00      2439672.55     13697580.46
      2439777.44     13697569.48      2439873.97     13697464.57
      2439834.15     13697268.27      2440019.46     13697027.42
      2440074.48     13696859.78      2440072.77     13696530.90
      2440019.48     13696430.28      2439927.98     13696417.00
      2439928.52     13696276.45      2440024.99     13696182.09
      2440118.34     13696266.01      2440155.07     13696246.01
      2440283.14     13696018.94      2440419.53     13695877.45
      2440435.48     13695715.20      2440761.67     13695388.64
      2440845.32     13695406.10      2440875.00     13695325.00

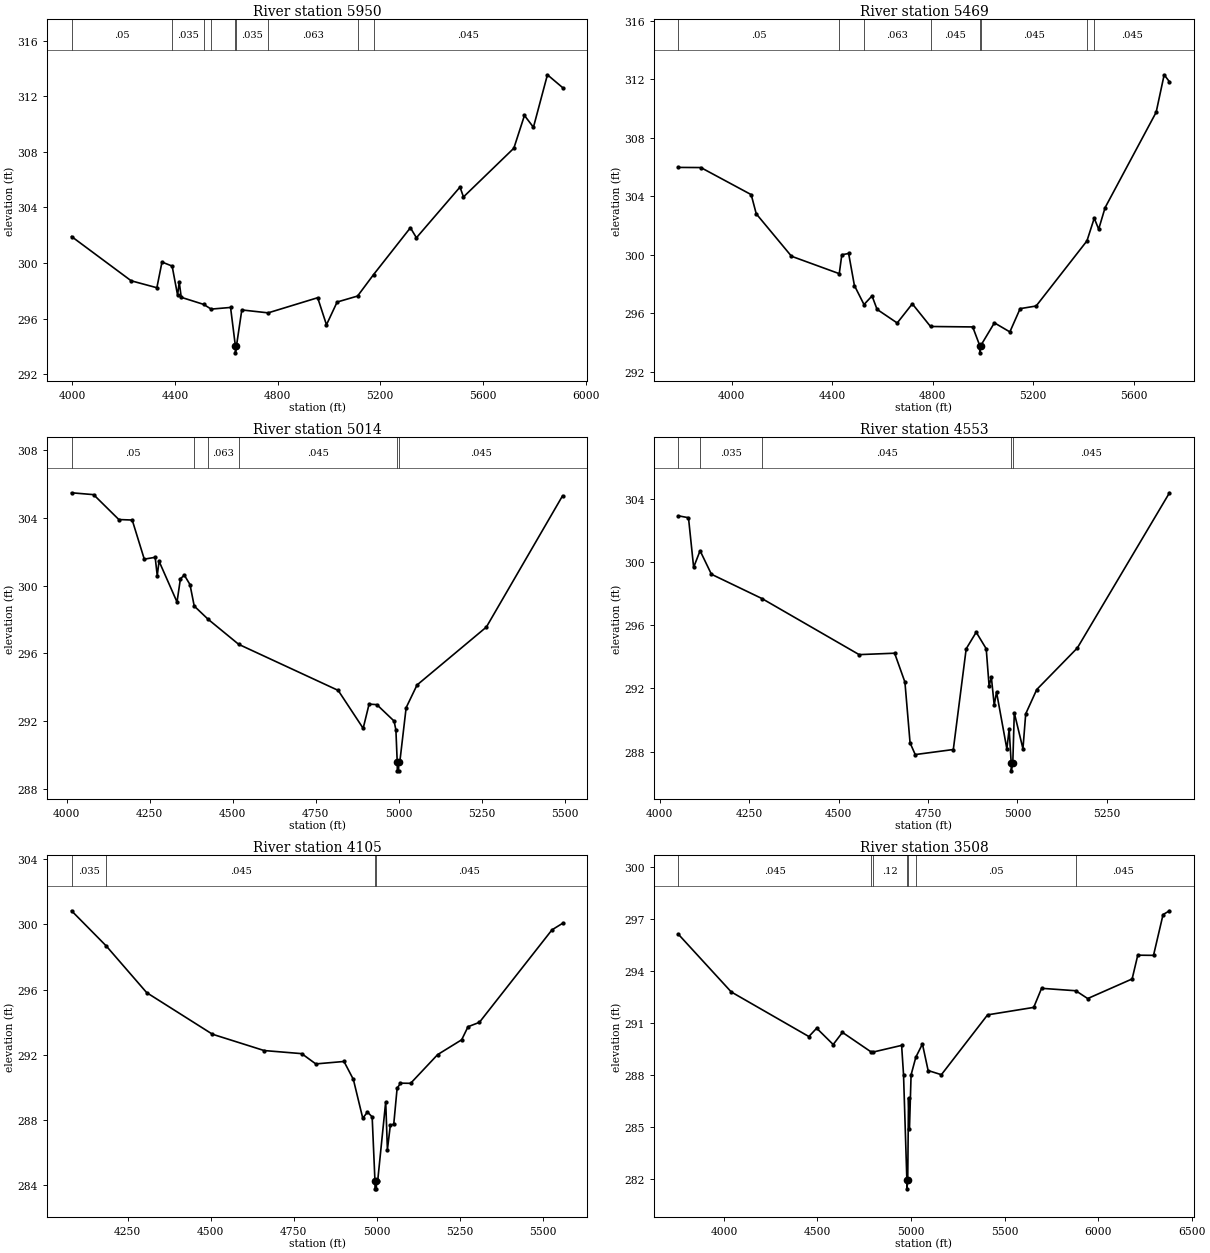
Type RM Length L Ch R = 1,5950,481,481,481
BEGIN DESCRIPTION:
Stream0725 8.0
END DESCRIPTION:
XS GIS Cut Line= 4
      2437683.46     13698287.13      2437699.17     13697884.98
      2437382.81     13697461.98      2436992.20     13696560.97
#Sta/Elev= 30
  3997.2  301.91  4229.5  298.72  4329.6  298.22  4349.6  300.07  4389.1  299.78
  4410.4  297.68  4416.7  298.63  4424.6  297.53  4511.8  297.02  4541.2  296.68
  4616.7  296.80  4635.4  294.03  4635.7  293.53  4639.7  294.03  4660.5  296.62
  4763.1  296.41  4956.0  297.50  4990.3  295.55  5031.8  297.19  5111.4  297.62
  5173.9  299.17  5317.2  302.54  5340.7  301.82  5510.4  305.47  5524.0  304.76
  5720.2  308.27  5761.5  310.63  5796.5  309.78  5851.0  313.56  5909.9  312.64
#Mann=9,-1,0
  3997.2    0.05       0  4389.1   0.035       0  4511.8   0.063       0
  4541.2   0.035       0  4635.4    0.05       0  4639.7   0.035       0
  4763.1   0.063       0  5111.4   0.035       0  5173.9   0.045       0
Bank Sta=4635.4,4639.7
Exp/Cntr=0.3,0.1

Type RM Length L Ch R = 1,5469,455,455,455
BEGIN DESCRIPTION:
Stream0725 7.0
END DESCRIPTION:
XS GIS Cut Line= 3
      2437695.31     13698633.88      2437775.00     13697425.00
      2437525.00     13696725.01
#Sta/Elev= 30
  3788.4  305.98  3877.5  305.97  4077.9  304.12  4098.0  302.81  4238.3  299.91
  4428.5  298.72  4438.7  300.01  4465.8  300.10  4488.8  297.91  4527.0  296.61
  4559.0  297.20  4579.0  296.28  4659.2  295.35  4719.3  296.66  4791.8  295.11
  4959.8  295.08  4987.7  293.81  4988.0  293.31  4992.0  293.81  5046.1  295.36
  5107.7  294.74  5148.6  296.33  5212.3  296.51  5414.6  300.96  5443.6  302.51
  5461.3  301.76  5486.8  303.23  5690.1  309.75  5722.0  312.31  5743.2  311.83
#Mann=8,-1,0
  3788.4    0.05       0  4428.5   0.035       0  4527.0   0.063       0
  4791.8   0.045       0  4987.7   0.045       0  4992.0   0.045       0
  5414.6   0.035       0  5443.6   0.045       0
Bank Sta=4987.7,4992
Exp/Cntr=0.3,0.1

Type RM Length L Ch R = 1,5014,461,461,461
BEGIN DESCRIPTION:
Stream0725 6.0
END DESCRIPTION:
XS GIS Cut Line= 3
      2437774.99     13698475.02      2438175.00     13697575.00
      2438375.02     13697124.96
#Sta/Elev= 30
  4015.1  305.49  4081.5  305.38  4157.4  303.91  4197.7  303.88  4234.0  301.57
  4266.8  301.68  4273.0  300.59  4278.4  301.45  4332.5  299.04  4342.7  300.41
  4354.4  300.63  4371.5  300.07  4384.3  298.80  4426.1  298.02  4518.1  296.54
  4817.4  293.82  4892.6  291.58  4910.4  293.01  4933.7  292.98  4985.6  292.01
  4991.1  291.48  4995.1  289.57  4995.4  289.07  4999.2  289.07  4999.5  289.57
  5002.7  289.57  5021.9  292.80  5054.7  294.14  5263.3  297.56  5492.5  305.31
#Mann=6,-1,0
  4015.1    0.05       0  4384.3   0.035       0  4426.1   0.063       0
  4518.1   0.045       0  4995.1   0.045       0  4999.5   0.045       0
Bank Sta=4995.1,4999.5
Exp/Cntr=0.3,0.1

Type RM Length L Ch R = 1,4553,448,448,448
BEGIN DESCRIPTION:
Stream0725 5.0
END DESCRIPTION:
XS GIS Cut Line= 3
      2437974.99     13698325.01      2438575.00     13697575.00
      2438475.00     13697174.99
#Sta/Elev= 30
  4052.3  302.93  4080.3  302.81  4094.7  299.67  4112.7  300.72  4144.4  299.23
  4285.8  297.69  4557.4  294.14  4656.6  294.23  4685.4  292.40  4699.8  288.55
  4714.2  287.81  4820.7  288.13  4856.7  294.51  4884.7  295.56  4912.7  294.51
  4920.7  292.16  4927.1  292.70  4935.1  290.94  4941.5  291.77  4970.4  288.17
  4976.8  289.42  4982.5  287.28  4982.8  286.78  4987.0  287.28  4991.2  290.45
  5015.4  288.18  5023.1  290.39  5054.0  291.93  5167.4  294.56  5425.1  304.39
#Mann=5,-1,0
  4052.3    0.05       0  4112.7   0.035       0  4285.8   0.045       0
  4982.5   0.045       0  4987.0   0.045       0
Bank Sta=4982.5,4987
Exp/Cntr=0.3,0.1

Type RM Length L Ch R = 1,4105,597,597,597
BEGIN DESCRIPTION:
Stream0725 4.0
END DESCRIPTION:
XS GIS Cut Line= 3
      2438274.99     13698375.01      2438925.00     13697725.00
      2438824.99     13697174.96
#Sta/Elev= 30
  4081.1  300.84  4185.3  298.69  4307.4  295.82  4505.4  293.27  4660.9  292.27
  4774.1  292.08  4816.5  291.45  4901.4  291.60  4929.6  290.50  4957.9  288.12
  4972.1  288.50  4986.2  288.20  4994.6  284.29  4994.9  283.79  4998.8  283.79
  4999.1  284.29  5002.9  284.29  5027.0  289.13  5032.1  286.20  5041.0  287.70
  5051.2  287.75  5061.3  289.95  5071.5  290.27  5102.0  290.26  5183.3  292.02
  5255.7  292.93  5274.8  293.73  5309.1  294.00  5527.6  299.67  5559.4  300.07
#Mann=4,-1,0
  4081.1   0.035       0  4185.3   0.045       0  4994.6   0.045       0
  4999.1   0.045       0
Bank Sta=4994.6,4999.1
Exp/Cntr=0.3,0.1

Type RM Length L Ch R = 1,3508,471,471,471
BEGIN DESCRIPTION:
XS7551
END DESCRIPTION:
XS GIS Cut Line= 4
      2438507.81     13698399.48      2439455.73     13697790.10
      2439398.44     13697415.10      2438779.34     13696483.86
#Sta/Elev= 30
  3757.0  296.09  4039.2  292.77  4453.9  290.20  4495.7  290.68  4584.0  289.74
  4633.4  290.44  4787.0  289.31  4799.0  289.31  4949.7  289.69  4959.9  288.01
  4977.8  281.92  4978.1  281.42  4982.3  281.92  4986.6  286.66  4991.7  284.89
  5000.3  287.99  5025.7  289.01  5061.0  289.77  5091.4  288.24  5162.2  288.00
  5409.2  291.45  5655.7  291.88  5697.8  292.98  5880.5  292.84  5944.3  292.39
  6181.8  293.52  6211.9  294.89  6296.1  294.88  6347.1  297.23  6381.5  297.45
#Mann=7,-1,0
  3757.0   0.045       0  4787.0    0.05       0  4799.0    0.12       0
  4977.8    0.05       0  4982.3    0.12       0  5025.7    0.05       0
  5880.5   0.045       0
Bank Sta=4977.8,4982.3
Exp/Cntr=0.3,0.1

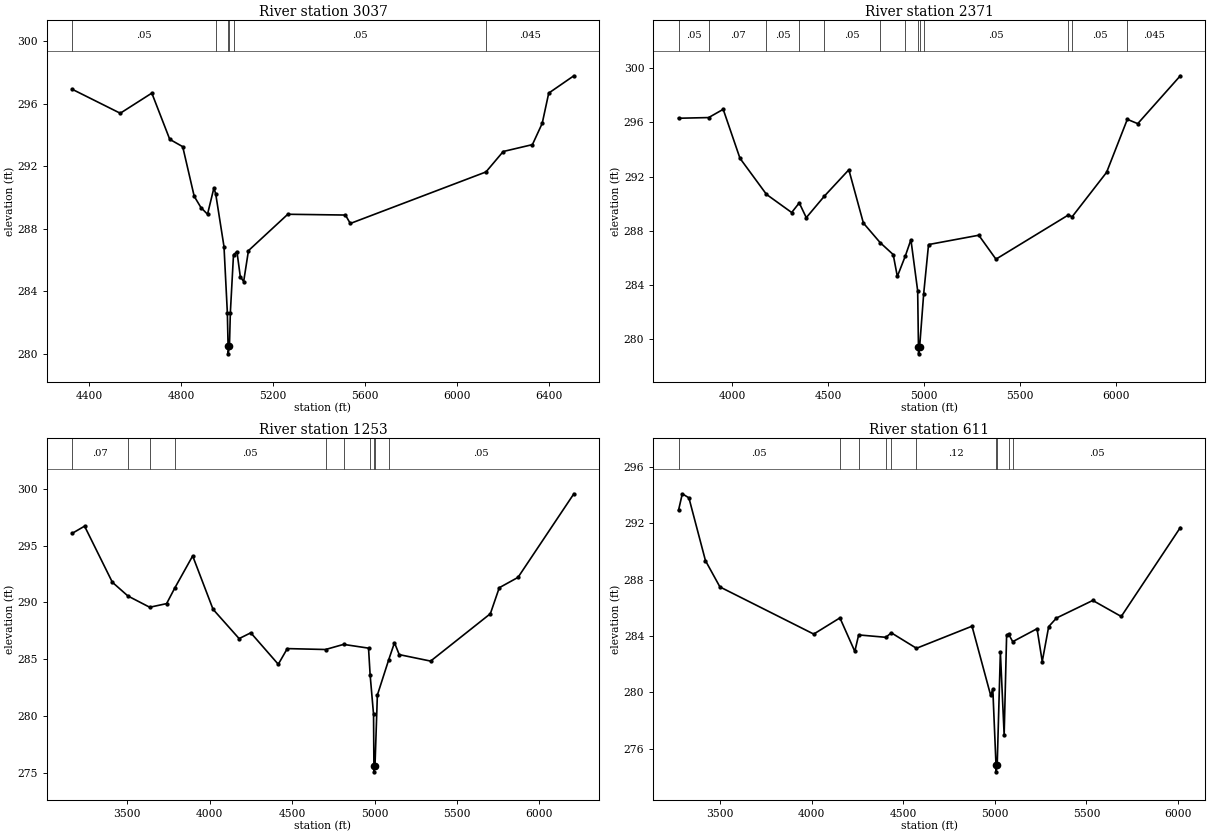
Type RM Length L Ch R = 1,3037,666,666,666
BEGIN DESCRIPTION:
XS7550
END DESCRIPTION:
XS GIS Cut Line= 4
      2439908.85     13698107.83      2440018.23     13697743.23
      2439554.69     13697113.02      2438799.74     13696425.76
#Sta/Elev= 30
  4325.6  296.94  4535.3  295.40  4672.7  296.69  4750.7  293.73  4807.1  293.26
  4857.2  290.08  4886.5  289.36  4915.1  288.93  4942.8  290.61  4950.6  290.25
  4986.8  286.86  5001.4  282.63  5004.6  280.49  5005.1  279.99  5010.6  280.49
  5014.4  282.61  5028.2  286.34  5043.1  286.54  5057.8  284.93  5072.4  284.62
  5093.3  286.60  5264.5  288.93  5515.2  288.88  5536.6  288.34  6126.9  291.64
  6202.1  292.95  6329.1  293.39  6371.7  294.75  6400.1  296.69  6509.5  297.80
#Mann=6,-1,0
  4325.6    0.05       0  4950.6    0.07       0  5004.6    0.05       0
  5010.6    0.07       0  5028.2    0.05       0  6126.9   0.045       0
Bank Sta=5004.6,5010.6
Exp/Cntr=0.3,0.1

Type RM Length L Ch R = 1,2371,1118,1118,1118
BEGIN DESCRIPTION:
XS7549
END DESCRIPTION:
XS GIS Cut Line= 4
      2439966.16     13698019.25      2440315.10     13697206.77
      2439929.69     13696847.40      2438851.59     13696310.95
#Sta/Elev= 30
  3720.6  296.31  3877.5  296.36  3953.4  296.97  4040.8  293.35  4179.0  290.68
  4310.3  289.34  4349.8  290.05  4386.4  288.96  4481.3  290.56  4608.3  292.50
  4684.1  288.56  4771.7  287.11  4839.5  286.23  4861.0  284.61  4902.8  286.13
  4931.8  287.33  4967.0  283.55  4971.1  279.39  4971.6  278.89  4977.2  279.39
  4998.2  283.31  5023.7  286.97  5285.5  287.66  5375.0  285.89  5752.8  289.16
  5771.8  289.02  5951.7  292.31  6059.8  296.23  6114.0  295.91  6336.0  299.45
#Mann=13,-1,0
  3720.6    0.05       0  3877.5    0.07       0  4179.0    0.05       0
  4349.8    0.07       0  4481.3    0.05       0  4771.7    0.07       0
  4902.8    0.12       0  4971.1    0.05       0  4977.2    0.12       0
  4998.2    0.05       0  5752.8   0.045       0  5771.8    0.05       0
  6059.8   0.045       0
Bank Sta=4971.1,4977.2
Exp/Cntr=0.3,0.1

Type RM Length L Ch R = 1,1253,642,642,642
BEGIN DESCRIPTION:
XS7548
END DESCRIPTION:
XS GIS Cut Line= 4
      2440044.25     13697904.73      2440476.56     13696889.06
      2440044.27     13695920.31      2439242.18     13695560.93
#Sta/Elev= 30
  3165.6  296.07  3241.4  296.71  3410.0  291.77  3504.5  290.56  3636.5  289.57
  3739.0  289.89  3788.1  291.25  3897.1  294.09  4020.7  289.39  4178.8  286.81
  4249.7  287.32  4416.3  284.55  4471.0  285.93  4703.1  285.85  4812.4  286.30
  4963.8  285.97  4973.5  283.61  4994.2  280.14  4996.4  275.58  4996.9  275.08
  5002.9  275.58  5017.4  281.84  5086.7  284.97  5121.2  286.45  5149.9  285.40
  5340.4  284.83  5702.7  289.00  5756.8  291.29  5870.5  292.20  6209.2  299.56
#Mann=10,-1,0
  3165.6    0.07       0  3504.5    0.05       0  3636.5    0.07       0
  3788.1    0.05       0  4703.1   0.035       0  4812.4    0.05       0
  4973.5    0.12       0  4996.4    0.05       0  5002.9    0.12       0
  5086.7    0.05       0
Bank Sta=4996.4,5002.9
Exp/Cntr=0.3,0.1

Type RM Length L Ch R = 1,611,0,0,0
BEGIN DESCRIPTION:
E21296
END DESCRIPTION:
XS GIS Cut Line= 4
      2440358.84     13697295.16      2440706.07     13696631.09
      2440445.65     13695606.79      2439769.26     13694965.09
#Sta/Elev= 30
  3273.6  292.94  3294.2  294.11  3330.2  293.82  3420.5  289.36  3499.5  287.49
  4011.4  284.14  4154.4  285.29  4235.6  282.91  4256.7  284.08  4405.3  283.91
  4434.7  284.23  4572.2  283.13  4875.3  284.70  4977.2  279.78  4988.8  280.23
  5006.2  274.85  5006.7  274.35  5012.8  274.85  5030.1  282.86  5050.7  276.97
  5064.2  284.09  5075.5  284.12  5097.5  283.60  5230.2  284.52  5258.6  282.19
  5293.8  284.67  5336.2  285.28  5534.4  286.53  5689.8  285.39  6012.2  291.71
#Mann=10,-1,0
  3273.6    0.05       0  4154.4   0.035       0  4256.7    0.05       0
  4405.3    0.12       0  4434.7    0.05       0  4572.2    0.12       0
  5006.2    0.05       0  5012.8    0.12       0  5075.5    0.07       0
  5097.5    0.05       0
Bank Sta=5006.2,5012.8
Exp/Cntr=0.3,0.1

Chan Stop Cuts=-1