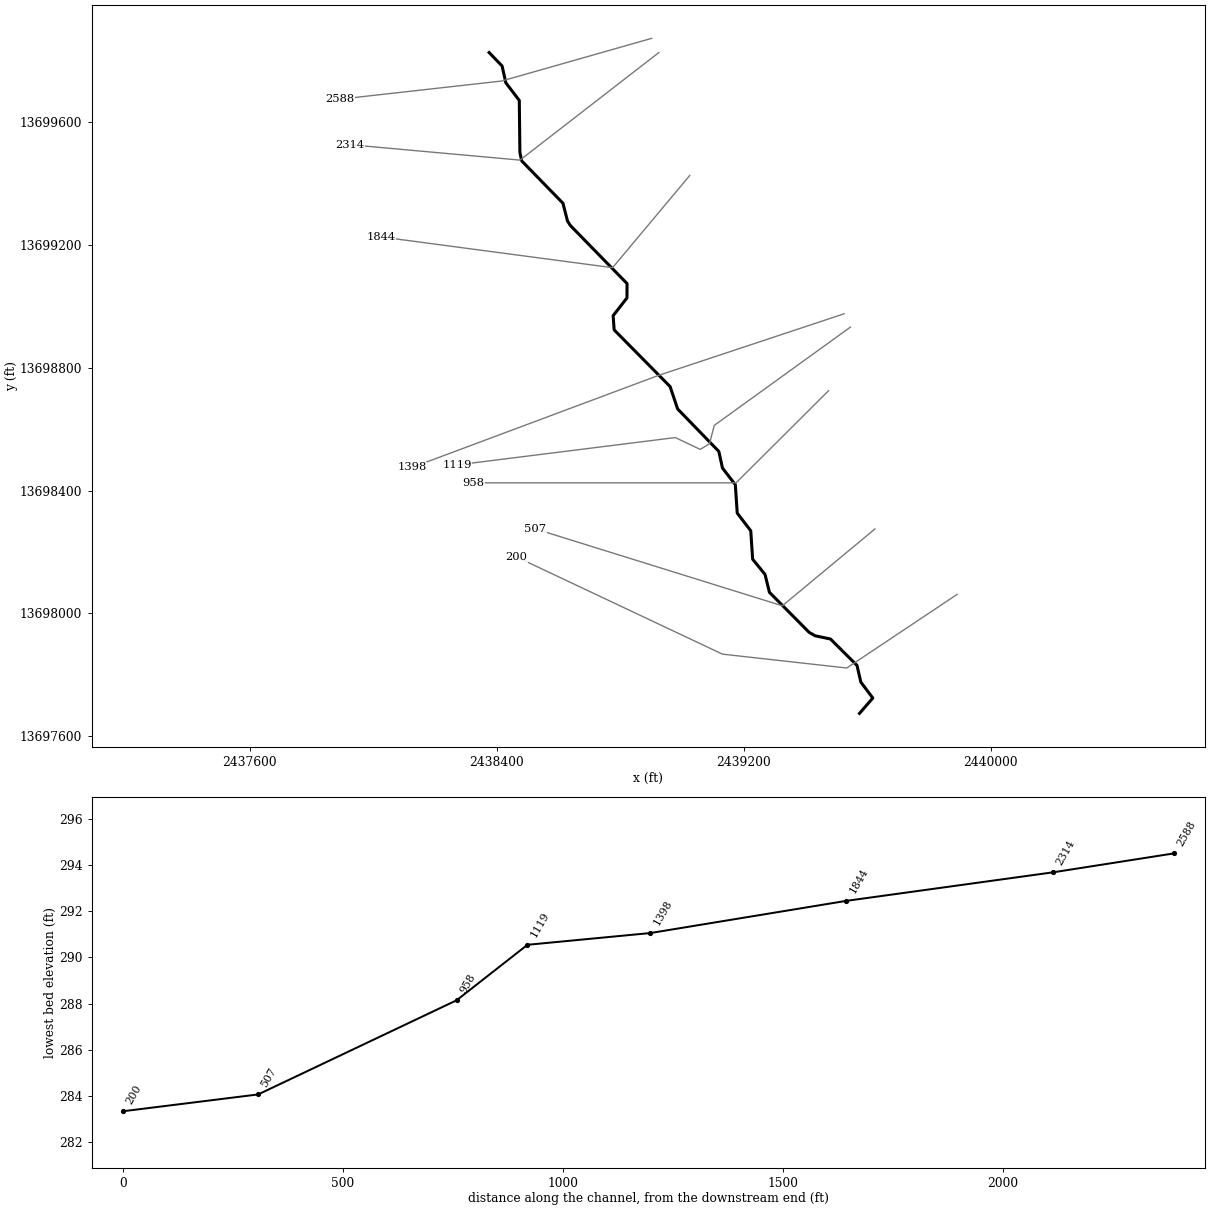
--- Stream0726.prj (project) ---

Proj Title=Stream0726 Base Level Engineering
Current Plan=p01
Default Exp/Contr=0.3,0.1
English Units
Geom File=g01
Flow File=f01
Plan File=p01
BEGIN DESCRIPTION:
Stream0726
END DESCRIPTION:

--- Stream0726.p01 (plan) ---

Plan Title=Multiple Run
Short Identifier=Multiple
Geom File=g01
Flow File=f01
Subcritical Flow
K Sum by GR= 0
Std Step Tol= 0.01
Critical Tol= 0.01
Num of Std Step Trials= 20
Max Error Tol= 0.3
Flow Tol Ratio= 0.001
Split Flow NTrial= 30
Split Flow Tol= 0.02
Split Flow Ratio= 0.02
Log Output Level= 0
Friction Slope Method= 1
Unsteady Friction Slope Method= 2
Unsteady Bridges Friction Slope Method= 1
Parabolic Critical Depth
Global Vel Dist=  1 , 1 , 1
Global Log Level= 0
CheckData=True
Encroach Param= -1, 0, 0, 0
BEGIN DESCRIPTION:
Multiple Run
END DESCRIPTION:

--- Stream0726.f01 (steady flow) ---

Flow Title=Multiple
Number of Profiles=7
Profile Names=10-year,25-year,50-year,1pct_min,100-year,1pct_plu,500-year
River Rch & RM= Stream0726,Reach-1,2588
     470     741     979     627    1251    2497    2024
Boundary for River Rch & Prof#=Stream0726,Reach-1,1
Up Type=0
Dn Type=3
Dn Slope=0.005
Boundary for River Rch & Prof#=Stream0726,Reach-1,2
Up Type=0
Dn Type=3
Dn Slope=0.005
Boundary for River Rch & Prof#=Stream0726,Reach-1,3
Up Type=0
Dn Type=3
Dn Slope=0.005
Boundary for River Rch & Prof#=Stream0726,Reach-1,4
Up Type=0
Dn Type=3
Dn Slope=0.005
Boundary for River Rch & Prof#=Stream0726,Reach-1,5
Up Type=0
Dn Type=3
Dn Slope=0.005
Boundary for River Rch & Prof#=Stream0726,Reach-1,6
Up Type=0
Dn Type=3
Dn Slope=0.005
Boundary for River Rch & Prof#=Stream0726,Reach-1,7
Up Type=0
Dn Type=3
Dn Slope=0.005

--- Stream0726.g01 (geometry) ---

Geom Title=Existing Conditions

River Reach=Stream0726,Reach-1
Reach XY= 30
      2438375.00     13699825.00      2438417.09     13699781.15
      2438429.08     13699726.69      2438472.77     13699669.08
      2438474.71     13699499.88      2438480.46     13699472.55
      2438614.22     13699334.68      2438628.98     13699276.65
      2438638.63     13699261.79      2438821.87     13699073.37
      2438821.63     13699026.74      2438776.81     13698968.88
      2438780.09     13698922.70      2438961.37     13698738.21
      2438985.78     13698665.32      2439119.17     13698527.30
      2439131.14     13698472.83      2439172.67     13698419.03
      2439178.85     13698326.60      2439222.65     13698269.03
      2439228.82     13698176.58      2439268.86     13698127.17
      2439283.14     13698068.94      2439411.79     13697938.63
      2439431.05     13697927.54      2439481.07     13697916.85
      2439566.89     13697831.07      2439579.36     13697776.64
      2439618.13     13697724.88      2439575.00     13697675.00

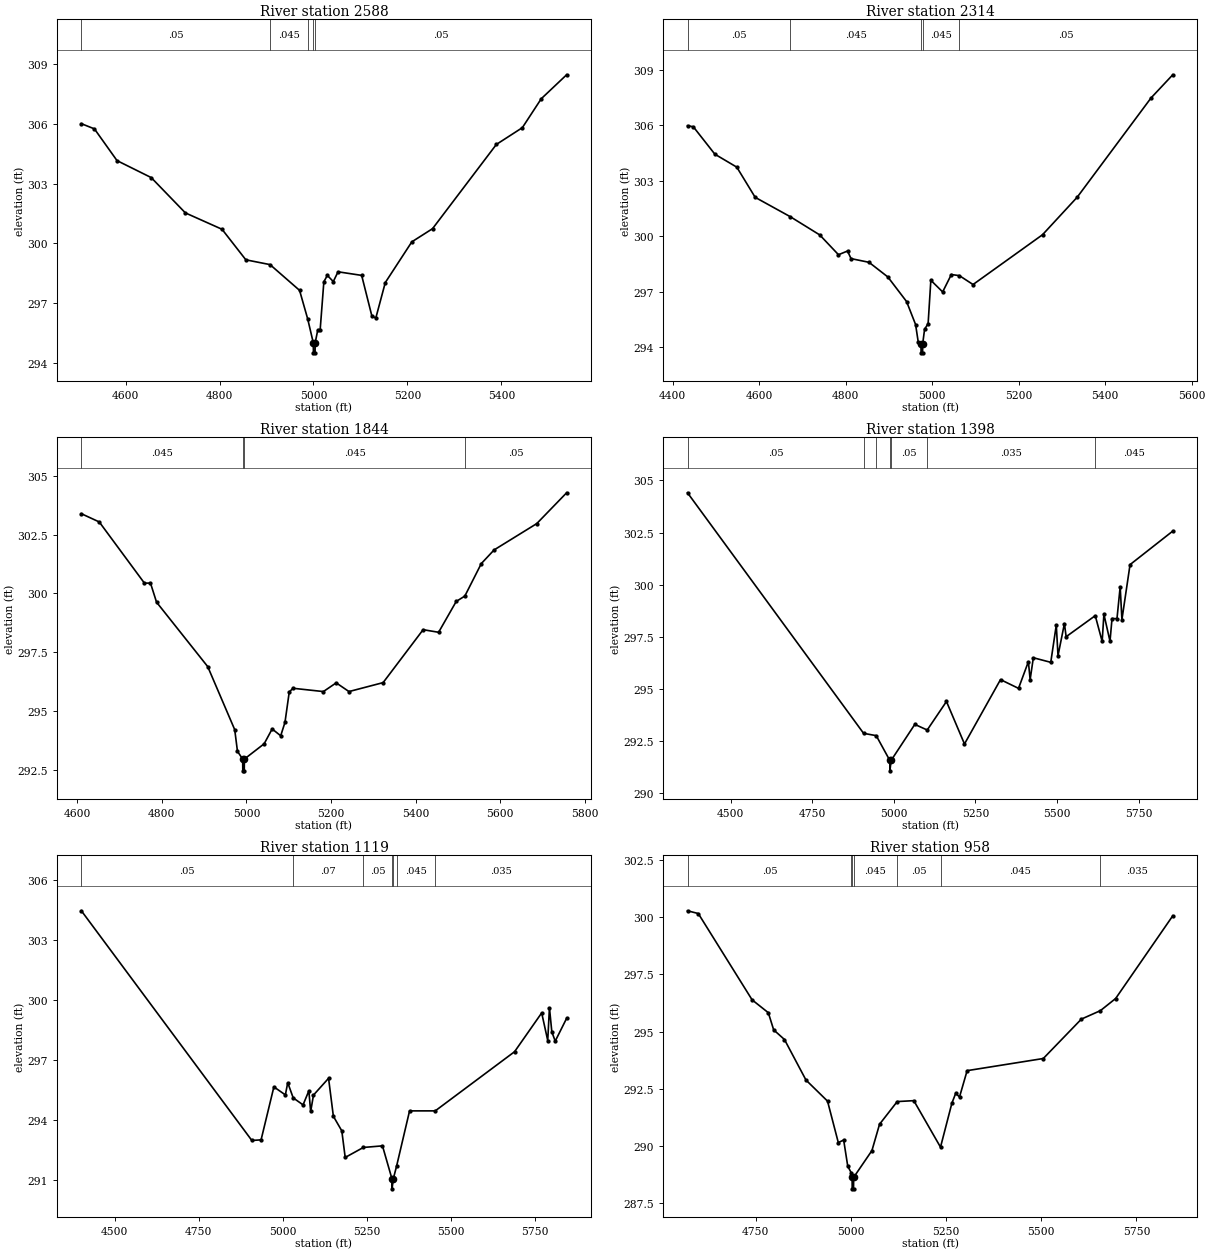
Type RM Length L Ch R = 1,2588,274,274,274
BEGIN DESCRIPTION:
XS7553
END DESCRIPTION:
XS GIS Cut Line= 3
      2438901.75     13699871.18      2438415.63     13699732.29
      2437891.31     13699673.26
#Sta/Elev= 30
  4505.8  306.00  4533.6  305.74  4581.7  304.15  4654.5  303.30  4727.3  301.53
  4805.3  300.71  4856.0  299.18  4907.5  298.94  4970.4  297.65  4987.8  296.21
  4999.6  295.02  4999.9  294.52  5003.4  294.52  5003.6  295.02  5009.1  295.66
  5014.2  295.66  5022.1  298.08  5029.5  298.40  5042.2  298.09  5052.3  298.58
  5102.6  298.40  5124.5  296.35  5132.8  296.27  5152.9  298.04  5209.4  300.08
  5253.5  300.74  5389.4  304.96  5444.7  305.80  5485.0  307.25  5539.0  308.45
#Mann=5,-1,0
  4505.8    0.05       0  4907.5   0.045       0  4987.8    0.05       0
  4999.6    0.05       0  5003.6    0.05       0
Bank Sta=4999.6,5003.6
Exp/Cntr=0.3,0.1

Type RM Length L Ch R = 1,2314,470,470,470
BEGIN DESCRIPTION:
Stream0726 5.0
END DESCRIPTION:
XS GIS Cut Line= 3
      2438924.97     13699824.97      2438475.00     13699475.00
      2437925.01     13699525.00
#Sta/Elev= 30
  4434.0  305.97  4447.5  305.91  4497.3  304.43  4548.0  303.73  4590.5  302.10
  4672.0  301.05  4739.8  300.07  4783.2  299.00  4804.1  299.20  4812.2  298.79
  4853.8  298.59  4897.3  297.80  4940.7  296.47  4961.5  295.23  4967.8  294.26
  4974.0  294.20  4974.2  293.70  4977.7  293.70  4978.0  294.20  4982.3  294.97
  4990.5  295.28  4996.8  297.62  5024.1  296.99  5044.2  297.93  5062.8  297.87
  5094.4  297.39  5255.1  300.08  5335.4  302.11  5506.1  307.47  5556.3  308.72
#Mann=5,-1,0
  4434.0    0.05       0  4672.0   0.045       0  4974.0   0.045       0
  4978.0   0.045       0  5062.8    0.05       0
Bank Sta=4974,4978
Exp/Cntr=0.3,0.1

Type RM Length L Ch R = 1,1844,446,446,446
BEGIN DESCRIPTION:
Stream0726 4.0
END DESCRIPTION:
XS GIS Cut Line= 3
      2439024.99     13699424.99      2438775.00     13699125.00
      2438025.04     13699225.00
#Sta/Elev= 30
  4609.8  303.39  4652.1  303.04  4758.8  300.44  4773.2  300.44  4787.5  299.63
  4908.5  296.89  4972.3  294.21  4978.8  293.29  4991.1  292.96  4991.4  292.46
  4994.9  292.46  4995.1  292.96  5041.9  293.61  5060.8  294.24  5081.0  293.95
  5091.1  294.52  5101.2  295.81  5110.0  295.97  5181.9  295.83  5212.2  296.20
  5242.4  295.83  5323.1  296.21  5417.7  298.46  5454.3  298.35  5495.9  299.66
  5516.3  299.89  5555.2  301.27  5585.4  301.85  5686.3  302.97  5756.9  304.28
#Mann=4,-1,0
  4609.8   0.045       0  4991.1   0.045       0  4995.1   0.045       0
  5516.3    0.05       0
Bank Sta=4991.1,4995.1
Exp/Cntr=0.3,0.1

Type RM Length L Ch R = 1,1398,279,279,279
BEGIN DESCRIPTION:
Stream0726 3.0
END DESCRIPTION:
XS GIS Cut Line= 3
      2439525.00     13698975.00      2438925.00     13698775.00
      2438124.96     13698474.98
#Sta/Elev= 30
  4367.8  304.41  4907.4  292.86  4946.1  292.75  4987.7  291.56  4988.0  291.06
  4991.7  291.56  5064.3  293.29  5102.3  293.02  5161.3  294.39  5216.5  292.35
  5326.9  295.44  5382.1  295.02  5412.3  296.30  5417.7  295.44  5427.5  296.49
  5480.9  296.27  5497.8  298.06  5503.1  296.59  5522.7  298.13  5528.0  297.50
  5617.2  298.51  5638.4  297.27  5643.7  298.58  5662.4  297.28  5668.6  298.37
  5683.8  298.37  5693.6  299.90  5698.9  298.32  5723.8  300.96  5854.7  302.57
#Mann=7,-1,0
  4367.8    0.05       0  4907.4    0.07       0  4946.1    0.05       0
  4987.7    0.05       0  4991.7    0.05       0  5102.3   0.035       0
  5617.2   0.045       0
Bank Sta=4987.7,4991.7
Exp/Cntr=0.3,0.1

Type RM Length L Ch R = 1,1119,161,161,161
BEGIN DESCRIPTION:
Stream0726 3.0a
END DESCRIPTION:
XS GIS Cut Line= 6
      2439545.70     13698931.77      2439104.51     13698611.99
      2439088.88     13698551.89      2439058.83     13698533.85
      2438978.28     13698572.32      2438271.36     13698483.36
#Sta/Elev= 30
  4401.0  304.46  4908.2  292.97  4935.7  293.00  4973.8  295.65  5008.0  295.25
  5015.0  295.86  5031.3  295.10  5060.6  294.75  5077.8  295.45  5083.3  294.42
  5091.6  295.24  5136.5  296.08  5150.8  294.18  5175.9  293.45  5186.0  292.12
  5240.0  292.62  5296.9  292.70  5325.1  291.05  5325.4  290.55  5329.1  291.05
  5338.8  291.68  5377.5  294.45  5453.9  294.45  5689.9  297.41  5770.6  299.35
  5788.6  297.97  5793.7  299.61  5800.8  298.40  5810.9  297.94  5844.8  299.08
#Mann=7,-1,0
  4401.0    0.05       0  5031.3    0.07       0  5240.0    0.05       0
  5325.1    0.05       0  5329.1    0.05       0  5338.8   0.045       0
  5453.9   0.035       0
Bank Sta=5325.1,5329.1
Exp/Cntr=0.3,0.1

Type RM Length L Ch R = 1,958,451,451,451
BEGIN DESCRIPTION:
Stream0726 2.0
END DESCRIPTION:
XS GIS Cut Line= 3
      2439475.02     13698725.02      2439175.00     13698425.00
      2438324.99     13698425.00
#Sta/Elev= 30
  4571.1  300.28  4599.4  300.16  4740.8  296.39  4783.3  295.83  4797.4  295.08
  4825.7  294.66  4882.2  292.89  4938.8  291.97  4967.1  290.16  4981.2  290.27
  4991.9  289.13  5001.1  288.84  5003.4  288.64  5003.6  288.14  5007.1  288.14
  5007.4  288.64  5055.4  289.81  5075.4  290.96  5121.8  291.95  5165.4  291.99
  5235.5  289.96  5265.4  291.88  5275.4  292.31  5285.4  292.15  5305.4  293.30
  5505.4  293.83  5605.4  295.55  5655.4  295.92  5695.4  296.45  5845.4  300.06
#Mann=7,-1,0
  4571.1    0.05       0  5001.1   0.045       0  5003.4    0.05       0
  5007.4   0.045       0  5121.8    0.05       0  5235.5   0.045       0
  5655.4   0.035       0
Bank Sta=5003.4,5007.4
Exp/Cntr=0.3,0.1

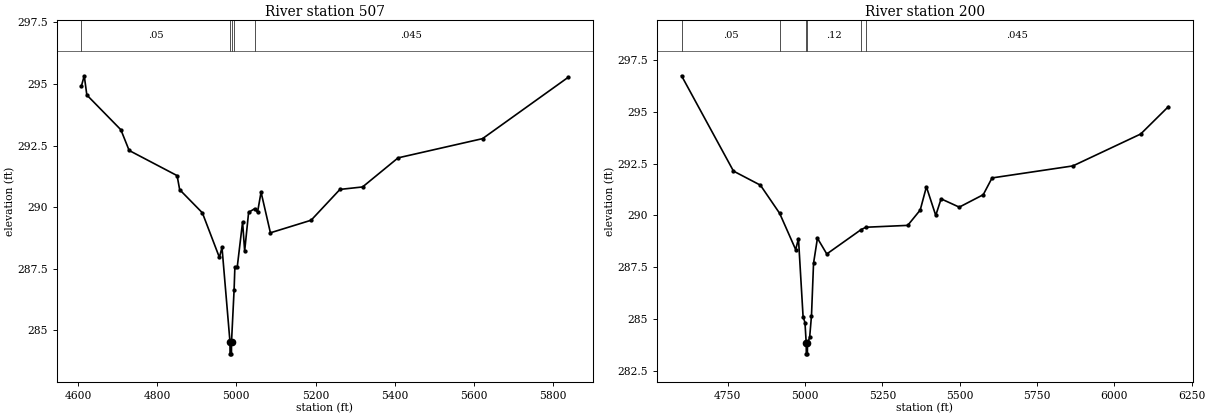
Type RM Length L Ch R = 1,507,307,307,307
BEGIN DESCRIPTION:
Stream0726 1.0
END DESCRIPTION:
XS GIS Cut Line= 3
      2439624.97     13698274.97      2439325.00     13698025.00
      2438525.02     13698274.99
#Sta/Elev= 30
  4609.0  294.92  4616.1  295.33  4622.6  294.55  4708.5  293.14  4729.4  292.30
  4850.4  291.28  4856.9  290.71  4914.2  289.77  4957.2  287.96  4963.7  288.37
  4983.8  284.55  4984.1  284.05  4987.6  284.05  4987.8  284.55  4994.3  286.66
  4996.2  287.56  5002.1  287.56  5015.7  289.40  5020.9  288.22  5030.9  289.79
  5046.3  289.94  5053.4  289.79  5062.3  290.61  5085.9  288.96  5188.6  289.47
  5261.4  290.72  5318.5  290.82  5408.1  292.00  5621.3  292.78  5837.6  295.27
#Mann=5,-1,0
  4609.0    0.05       0  4983.8    0.05       0  4987.8    0.05       0
  4994.3    0.12       0  5046.3   0.045       0
Bank Sta=4983.8,4987.8
Exp/Cntr=0.3,0.1

Type RM Length L Ch R = 1,200,0,0,0
BEGIN DESCRIPTION:
XS7552
END DESCRIPTION:
XS GIS Cut Line= 4
      2439891.30     13698062.14      2439533.68     13697822.57
      2439130.90     13697867.71      2438464.24     13698183.68
#Sta/Elev= 30
  4601.0  296.74  4768.8  292.14  4855.9  291.46  4918.1  290.10  4969.9  288.35
  4978.9  288.88  4993.8  285.11  4999.9  284.83  5004.0  283.82  5004.2  283.32
  5007.7  283.32  5008.0  283.82  5015.0  284.11  5021.0  285.17  5027.6  287.69
  5040.2  288.90  5070.4  288.14  5181.8  289.32  5197.0  289.43  5332.0  289.52
  5372.4  290.26  5392.4  291.38  5422.6  290.00  5439.9  290.80  5498.6  290.40
  5576.1  291.00  5604.6  291.81  5865.9  292.39  6085.1  293.93  6174.5  295.25
#Mann=6,-1,0
  4601.0    0.05       0  4918.1    0.12       0  5004.0    0.05       0
  5008.0    0.12       0  5181.8    0.05       0  5197.0   0.045       0
Bank Sta=5004,5008
Exp/Cntr=0.3,0.1

Chan Stop Cuts=-1