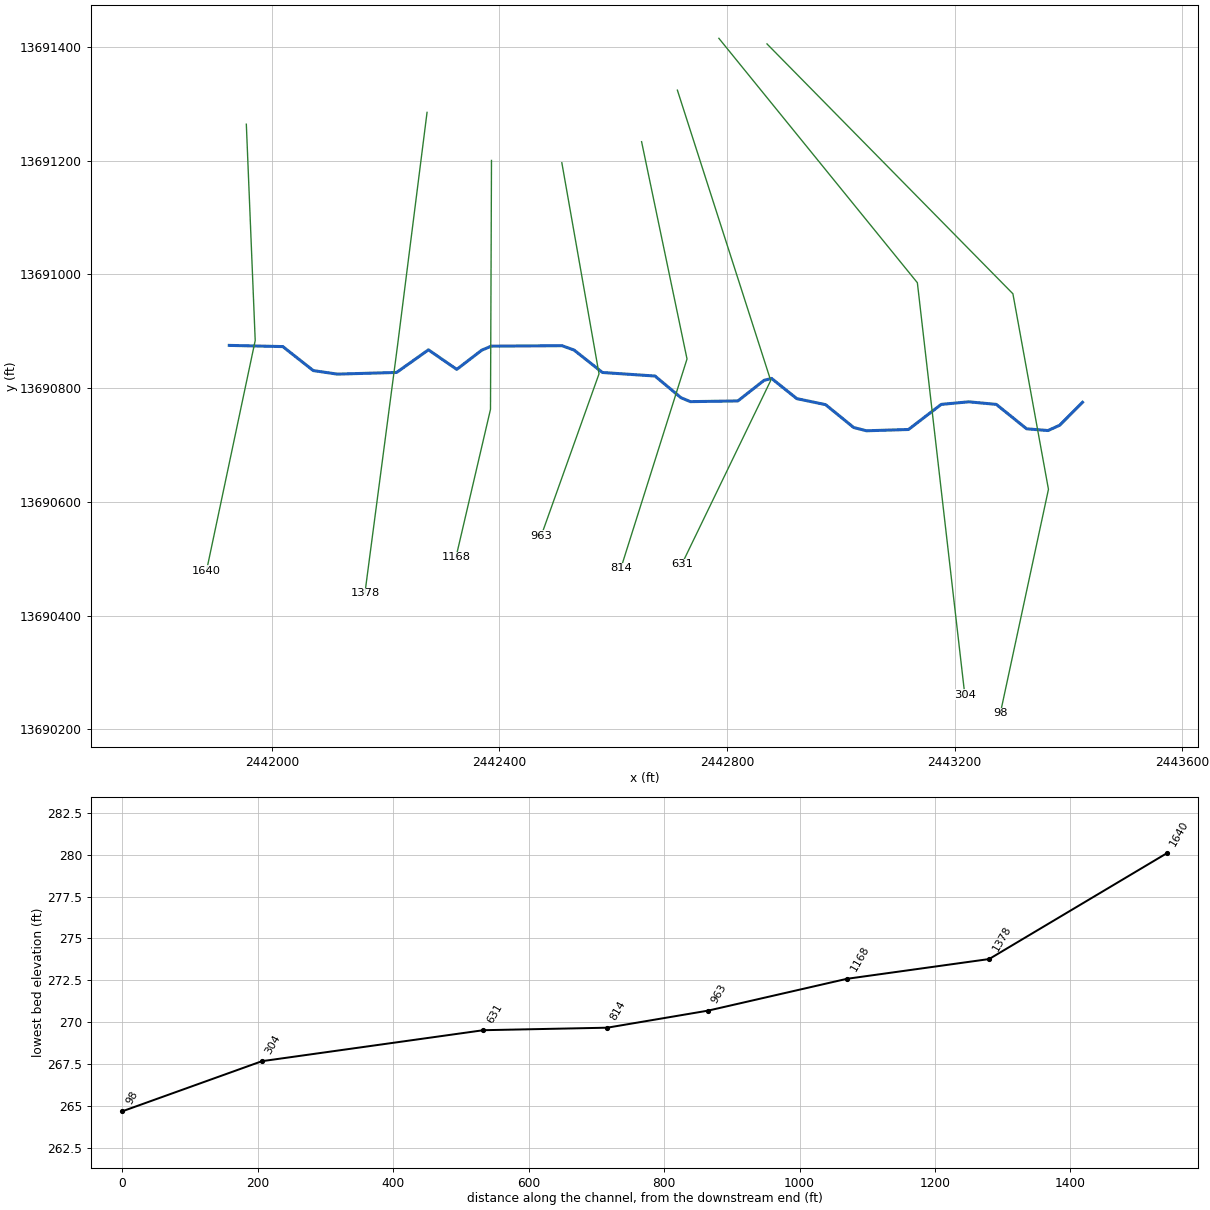
--- Stream0727.prj (project) ---

Proj Title=Stream0727 Base Level Engineering
Current Plan=p01
Default Exp/Contr=0.3,0.1
English Units
Geom File=g01
Flow File=f01
Plan File=p01
BEGIN DESCRIPTION:
Stream0727
END DESCRIPTION:

--- Stream0727.p01 (plan) ---

Plan Title=Multiple Run
Short Identifier=Multiple
Geom File=g01
Flow File=f01
Subcritical Flow
K Sum by GR= 0
Std Step Tol= 0.01
Critical Tol= 0.01
Num of Std Step Trials= 20
Max Error Tol= 0.3
Flow Tol Ratio= 0.001
Split Flow NTrial= 30
Split Flow Tol= 0.02
Split Flow Ratio= 0.02
Log Output Level= 0
Friction Slope Method= 1
Unsteady Friction Slope Method= 2
Unsteady Bridges Friction Slope Method= 1
Parabolic Critical Depth
Global Vel Dist=  1 , 1 , 1
Global Log Level= 0
CheckData=True
Encroach Param= -1, 0, 0, 0
BEGIN DESCRIPTION:
Multiple Run
END DESCRIPTION:

--- Stream0727.f01 (steady flow) ---

Flow Title=Multiple
Number of Profiles=7
Profile Names=10-year,25-year,50-year,1pct_min,100-year,1pct_plu,500-year
River Rch & RM= Stream0727,Reach-1,1640
     277     422     547     344     687    1371    1071
Boundary for River Rch & Prof#=Stream0727,Reach-1,1
Up Type=0
Dn Type=3
Dn Slope=0.005
Boundary for River Rch & Prof#=Stream0727,Reach-1,2
Up Type=0
Dn Type=3
Dn Slope=0.005
Boundary for River Rch & Prof#=Stream0727,Reach-1,3
Up Type=0
Dn Type=3
Dn Slope=0.005
Boundary for River Rch & Prof#=Stream0727,Reach-1,4
Up Type=0
Dn Type=3
Dn Slope=0.005
Boundary for River Rch & Prof#=Stream0727,Reach-1,5
Up Type=0
Dn Type=3
Dn Slope=0.005
Boundary for River Rch & Prof#=Stream0727,Reach-1,6
Up Type=0
Dn Type=3
Dn Slope=0.005
Boundary for River Rch & Prof#=Stream0727,Reach-1,7
Up Type=0
Dn Type=3
Dn Slope=0.005

--- Stream0727.g01 (geometry) ---

Geom Title=Existing Conditions

River Reach=Stream0727,Reach-1
Reach XY= 30
      2441925.00     13690875.00      2442019.13     13690872.90
      2442072.65     13690830.70      2442114.83     13690824.50
      2442219.14     13690827.44      2442275.10     13690867.20
      2442324.90     13690832.80      2442368.81     13690866.57
      2442385.44     13690873.64      2442509.78     13690874.49
      2442531.06     13690866.87      2442580.98     13690827.36
      2442673.40     13690821.14      2442718.96     13690783.09
      2442735.55     13690776.11      2442819.11     13690777.37
      2442865.10     13690813.54      2442878.32     13690816.95
      2442922.71     13690781.39      2442973.25     13690770.84
      2443022.68     13690730.65      2443045.09     13690724.89
      2443119.03     13690727.17      2443176.60     13690771.29
      2443225.00     13690775.81      2443273.42     13690771.28
      2443326.69     13690728.35      2443364.34     13690725.33
      2443384.80     13690734.62      2443425.00     13690775.00

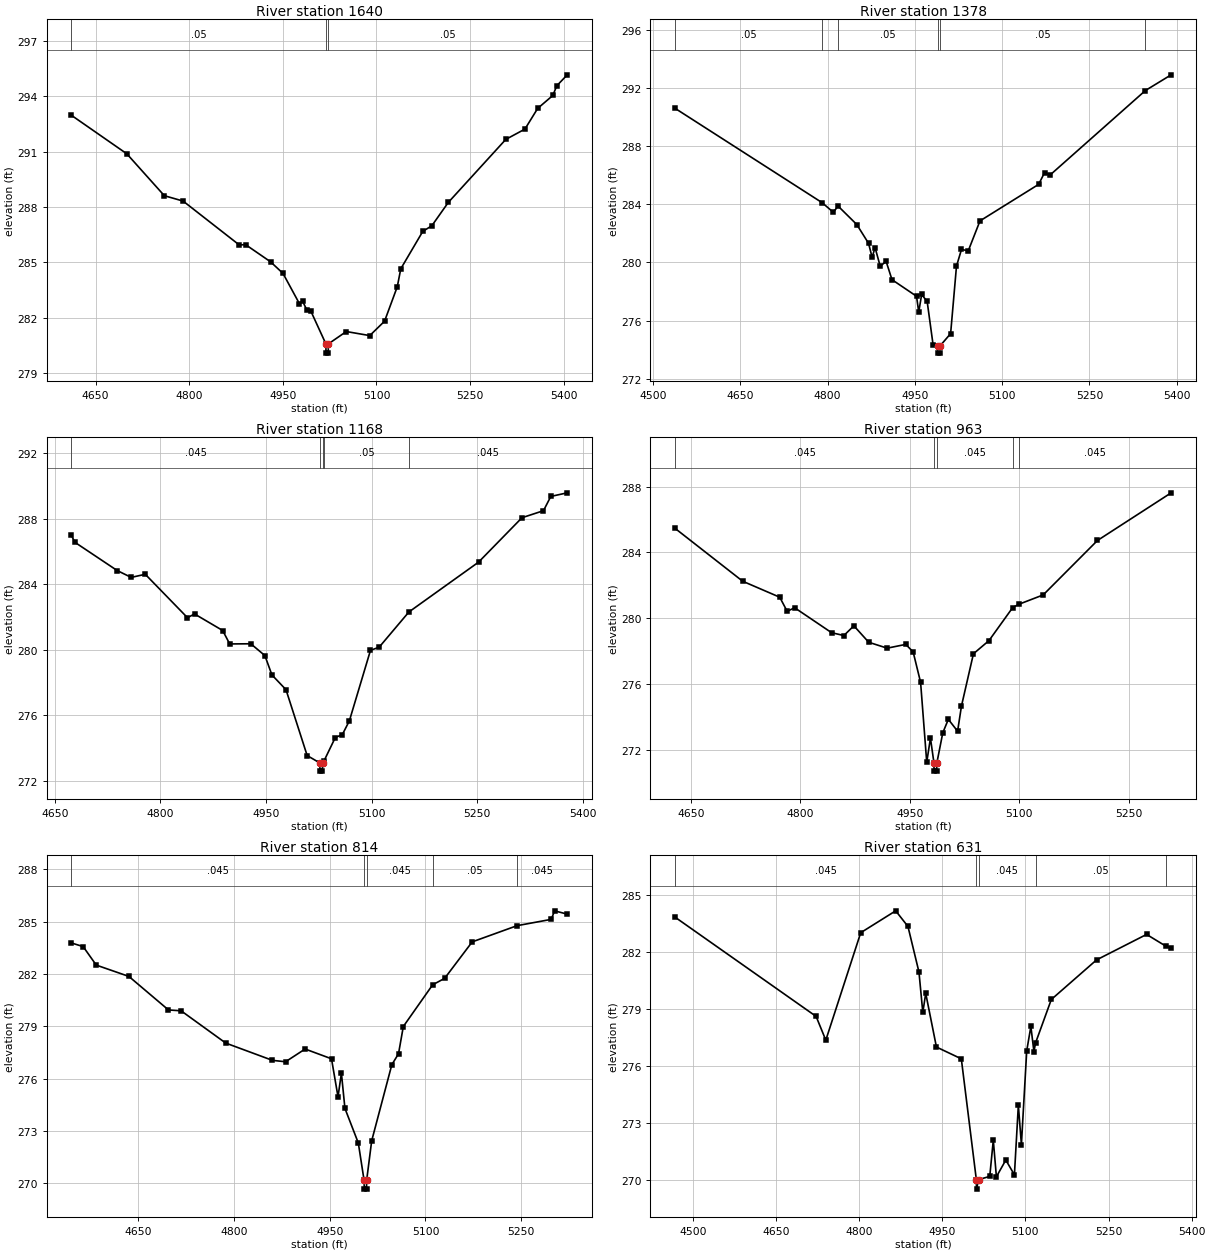
Type RM Length L Ch R = 1,1640,262,262,262
BEGIN DESCRIPTION:
XS7555
END DESCRIPTION:
XS GIS Cut Line= 3
      2441954.95     13691263.84      2441970.57     13690883.59
      2441884.91     13690478.62
#Sta/Elev= 30
  4611.2  292.97  4700.1  290.88  4760.2  288.61  4790.2  288.32  4880.3  285.94
  4890.3  285.96  4930.3  285.03  4950.3  284.40  4976.6  282.76  4981.6  282.90
  4988.6  282.41  4995.0  282.35  5019.0  280.58  5019.2  280.08  5022.7  280.08
  5023.0  280.58  5051.7  281.25  5089.3  281.03  5113.0  281.81  5133.4  283.68
  5139.0  284.65  5174.3  286.68  5188.7  286.98  5215.2  288.25  5307.2  291.66
  5337.9  292.22  5358.3  293.34  5382.5  294.04  5389.0  294.57  5405.7  295.16
#Mann=3,-1,0
  4611.2    0.05       0  5019.0    0.05       0  5023.0    0.05       0
Bank Sta=5019,5023
Exp/Cntr=0.3,0.1

Type RM Length L Ch R = 1,1378,210,210,210
BEGIN DESCRIPTION:
Stream0727 3.0
END DESCRIPTION:
XS GIS Cut Line= 3
      2442272.66     13691284.65      2442220.57     13690873.18
      2442163.40     13690439.18
#Sta/Elev= 30
  4538.0  290.59  4790.6  284.11  4809.8  283.45  4817.9  283.88  4850.1  282.61
  4870.3  281.32  4876.5  280.35  4881.5  281.03  4890.4  279.74  4900.5  280.08
  4910.6  278.82  4952.8  277.68  4956.6  276.59  4961.6  277.80  4971.1  277.32
  4981.2  274.36  4989.3  274.27  4989.5  273.77  4993.0  273.77  4993.3  274.27
  5011.4  275.11  5021.5  279.75  5030.1  280.90  5041.7  280.80  5061.9  282.86
  5162.7  285.37  5172.8  286.17  5182.3  286.01  5346.2  291.82  5390.5  292.90
#Mann=6,-1,0
  4538.0    0.05       0  4790.6   0.045       0  4817.9    0.05       0
  4989.3    0.05       0  4993.3    0.05       0  5346.2   0.045       0
Bank Sta=4989.3,4993.3
Exp/Cntr=0.3,0.1

Type RM Length L Ch R = 1,1168,205,205,205
BEGIN DESCRIPTION:
E21299
END DESCRIPTION:
XS GIS Cut Line= 3
      2442385.94     13691200.15      2442384.20     13690762.62
      2442323.45     13690502.25
#Sta/Elev= 30
  4673.3  286.98  4678.4  286.55  4738.4  284.83  4758.4  284.41  4778.4  284.60
  4838.4  281.95  4848.4  282.18  4888.4  281.17  4898.4  280.35  4928.4  280.36
  4948.4  279.64  4958.4  278.46  4978.4  277.56  5008.5  273.54  5026.5  273.09
  5026.7  272.59  5030.2  272.59  5030.5  273.09  5032.3  273.20  5048.5  274.64
  5058.5  274.82  5068.5  275.66  5098.5  279.96  5110.8  280.15  5153.1  282.30
  5252.1  285.34  5313.8  288.05  5344.4  288.48  5354.8  289.35  5378.2  289.57
#Mann=5,-1,0
  4673.3   0.045       0  5026.5   0.045       0  5030.5   0.045       0
  5032.3    0.05       0  5153.1   0.045       0
Bank Sta=5026.5,5030.5
Exp/Cntr=0.3,0.1

Type RM Length L Ch R = 1,963,149,149,149
BEGIN DESCRIPTION:
Stream0727 2.0
END DESCRIPTION:
XS GIS Cut Line= 3
      2442509.64     13691196.07      2442575.00     13690825.00
      2442473.20     13690539.91
#Sta/Elev= 30
  4628.4  285.45  4720.9  282.24  4771.6  281.27  4781.8  280.41  4792.0  280.63
  4842.7  279.11  4859.5  278.94  4873.2  279.53  4893.5  278.53  4918.8  278.17
  4944.3  278.40  4954.4  277.94  4964.6  276.09  4973.0  271.23  4978.1  272.70
  4982.9  271.19  4983.1  270.69  4986.6  270.69  4986.9  271.19  4995.0  273.02
  5002.6  273.84  5015.3  273.12  5020.6  274.65  5037.0  277.83  5058.3  278.63
  5090.8  280.64  5099.2  280.84  5132.6  281.41  5206.9  284.72  5307.9  287.62
#Mann=5,-1,0
  4628.4   0.045       0  4982.9   0.045       0  4986.9   0.045       0
  5090.8    0.05       0  5099.2   0.045       0
Bank Sta=4982.9,4986.9
Exp/Cntr=0.3,0.1

Type RM Length L Ch R = 1,814,183,183,183
BEGIN DESCRIPTION:
E21298
END DESCRIPTION:
XS GIS Cut Line= 3
      2442649.82     13691233.16      2442729.69     13690851.17
      2442613.38     13690483.16
#Sta/Elev= 30
  4545.7  283.78  4564.2  283.57  4584.7  282.51  4635.8  281.86  4697.7  279.94
  4717.5  279.89  4787.4  278.04  4860.5  277.05  4881.0  276.97  4911.6  277.70
  4952.9  277.14  4963.1  274.96  4968.4  276.32  4973.9  274.30  4994.9  272.31
  5003.9  270.17  5004.2  269.67  5007.7  269.67  5007.9  270.17  5015.8  272.44
  5047.3  276.80  5057.8  277.43  5065.3  278.99  5111.2  281.38  5130.0  281.75
  5173.1  283.84  5243.4  284.77  5296.8  285.13  5302.1  285.62  5321.9  285.43
#Mann=5,-1,0
  4545.7   0.045       0  5003.9   0.045       0  5007.9   0.045       0
  5111.2    0.05       0  5243.4   0.045       0
Bank Sta=5003.9,5007.9
Exp/Cntr=0.3,0.1

Type RM Length L Ch R = 1,631,327,327,327
BEGIN DESCRIPTION:
Stream0727 1.0
END DESCRIPTION:
XS GIS Cut Line= 3
      2442712.77     13691323.68      2442876.82     13690813.28
      2442720.59     13690490.41
#Sta/Elev= 30
  4468.2  283.81  4722.4  278.60  4739.9  277.35  4802.9  283.00  4866.0  284.15
  4888.1  283.33  4908.0  280.93  4914.9  278.81  4920.2  279.81  4939.5  276.99
  4984.4  276.37  5011.5  270.02  5011.8  269.52  5015.5  270.02  5035.7  270.19
  5042.1  272.09  5047.7  270.17  5064.7  271.05  5080.2  270.27  5087.3  273.93
  5092.8  271.86  5102.4  276.79  5109.9  278.07  5115.4  276.75  5118.4  277.21
  5146.8  279.49  5228.4  281.57  5318.7  282.91  5353.6  282.29  5363.0  282.18
#Mann=5,-1,0
  4468.2   0.045       0  5011.5   0.045       0  5015.5   0.045       0
  5118.4    0.05       0  5353.6   0.045       0
Bank Sta=5011.5,5015.5
Exp/Cntr=0.3,0.1

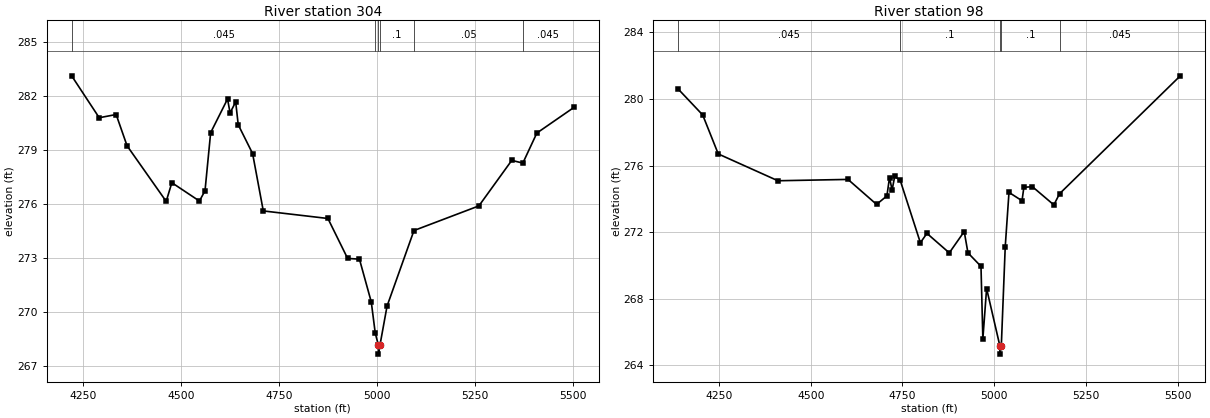
Type RM Length L Ch R = 1,304,206,206,206
BEGIN DESCRIPTION:
XS7554
END DESCRIPTION:
XS GIS Cut Line= 3
      2442785.70     13691414.81      2443134.64     13690985.16
      2443217.96     13690261.23
#Sta/Elev= 30
  4219.9  283.14  4290.3  280.81  4333.5  280.99  4361.4  279.25  4461.3  276.16
  4475.7  277.20  4546.1  276.18  4560.4  276.75  4574.8  279.98  4617.9  281.85
  4624.4  281.08  4638.7  281.69  4645.2  280.42  4681.9  278.82  4709.2  275.63
  4874.2  275.21  4924.5  272.99  4954.7  272.95  4984.9  270.57  4995.1  268.83
  5003.1  268.17  5003.3  267.67  5007.1  268.17  5025.2  270.34  5093.9  274.54
  5259.7  275.91  5343.6  278.44  5371.9  278.29  5407.7  279.96  5502.1  281.38
#Mann=6,-1,0
  4219.9   0.045       0  4995.1     0.1       0  5003.1    0.05       0
  5007.1     0.1       0  5093.9    0.05       0  5371.9   0.045       0
Bank Sta=5003.1,5007.1
Exp/Cntr=0.3,0.1

Type RM Length L Ch R = 1,98,0,0,0
BEGIN DESCRIPTION:
E21297
END DESCRIPTION:
XS GIS Cut Line= 4
      2442870.29     13691405.00      2443302.60     13690965.75
      2443365.10     13690622.00      2443280.45     13690228.09
#Sta/Elev= 30
  4138.5  280.60  4205.5  279.04  4247.9  276.70  4410.5  275.09  4601.5  275.17
  4679.3  273.67  4707.5  274.18  4714.6  275.28  4721.7  274.53  4728.7  275.35
  4743.7  275.12  4798.7  271.37  4816.6  271.93  4877.5  270.76  4918.2  272.04
  4928.4  270.76  4963.9  269.95  4969.0  265.59  4979.2  268.62  5015.3  265.18
  5015.5  264.68  5019.3  265.18  5030.0  271.14  5040.2  274.39  5075.7  273.89
  5080.8  274.70  5104.2  274.73  5162.5  273.64  5178.0  274.31  5507.1  281.39
#Mann=5,-1,0
  4138.5   0.045       0  4743.7     0.1       0  5015.3    0.05       0
  5019.3     0.1       0  5178.0   0.045       0
Bank Sta=5015.3,5019.3
Exp/Cntr=0.3,0.1

Chan Stop Cuts=-1