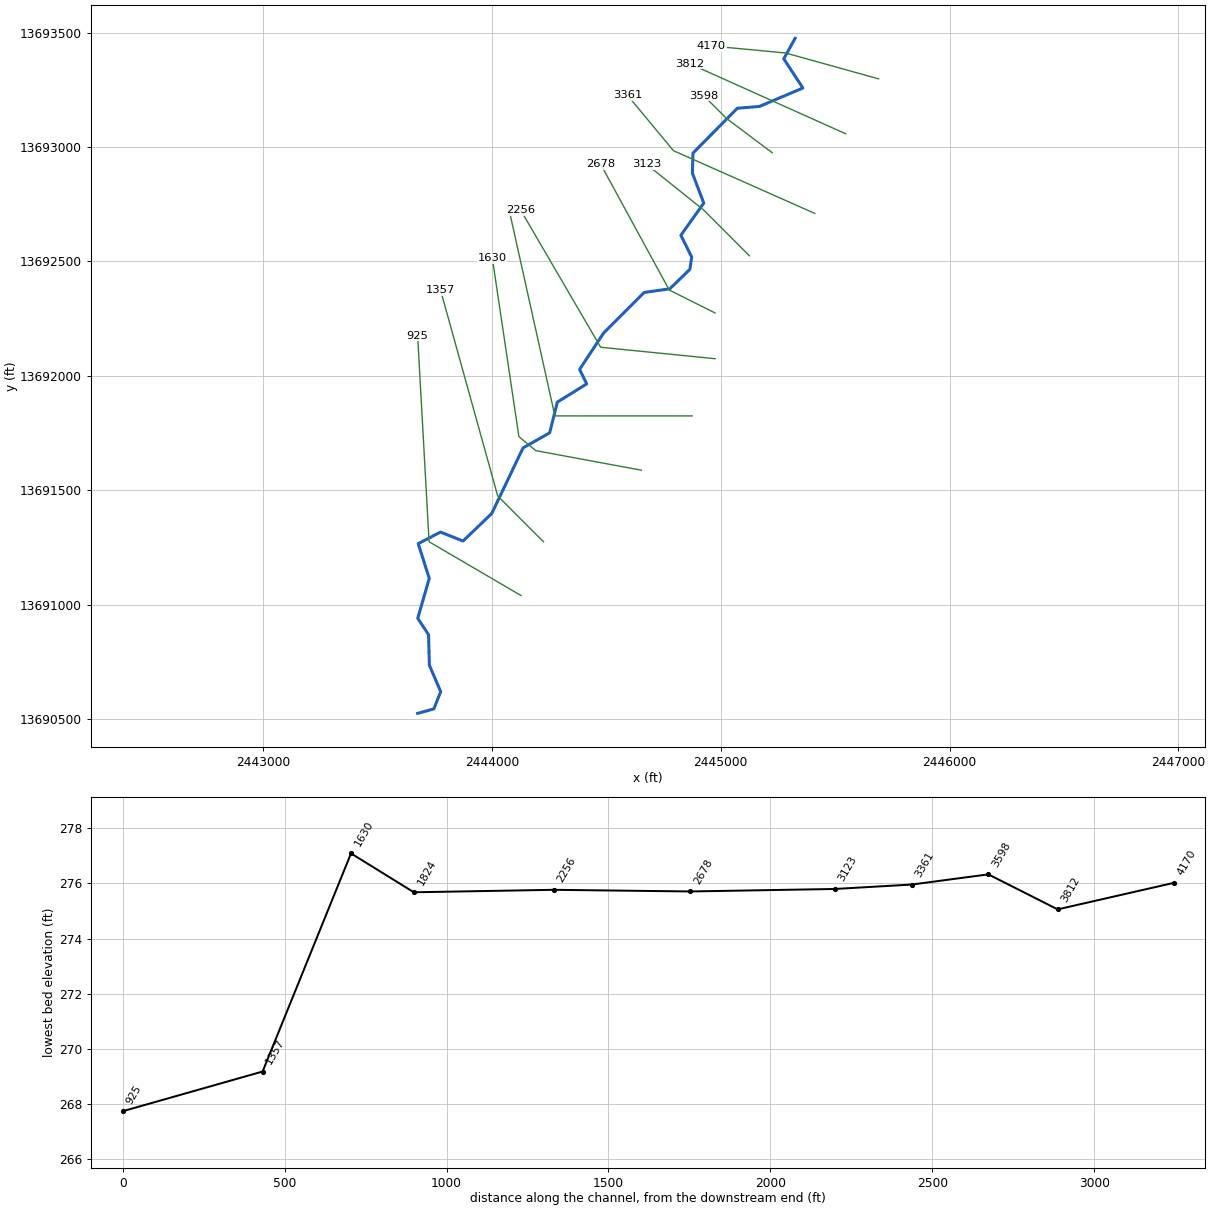
--- Stream0728.prj (project) ---

Proj Title=Stream0728 Base Level Engineering
Current Plan=p01
Default Exp/Contr=0.3,0.1
English Units
Geom File=g01
Flow File=f01
Plan File=p01
BEGIN DESCRIPTION:
Stream0728
END DESCRIPTION:

--- Stream0728.p01 (plan) ---

Plan Title=Multiple Run
Short Identifier=Multiple
Geom File=g01
Flow File=f01
Subcritical Flow
K Sum by GR= 0
Std Step Tol= 0.01
Critical Tol= 0.01
Num of Std Step Trials= 20
Max Error Tol= 0.3
Flow Tol Ratio= 0.001
Split Flow NTrial= 30
Split Flow Tol= 0.02
Split Flow Ratio= 0.02
Log Output Level= 0
Friction Slope Method= 1
Unsteady Friction Slope Method= 2
Unsteady Bridges Friction Slope Method= 1
Parabolic Critical Depth
Global Vel Dist=  1 , 1 , 1
Global Log Level= 0
CheckData=True
Encroach Param= -1, 0, 0, 0
BEGIN DESCRIPTION:
Multiple Run
END DESCRIPTION:

--- Stream0728.f01 (steady flow) ---

Flow Title=Multiple
Number of Profiles=7
Profile Names=10-year,25-year,50-year,1pct_min,100-year,1pct_plu,500-year
River Rch & RM= Stream0728,Reach-1,4170
     506     795    1050     671    1340    2673    2159
Boundary for River Rch & Prof#=Stream0728,Reach-1,1
Up Type=0
Dn Type=3
Dn Slope=0.005
Boundary for River Rch & Prof#=Stream0728,Reach-1,2
Up Type=0
Dn Type=3
Dn Slope=0.005
Boundary for River Rch & Prof#=Stream0728,Reach-1,3
Up Type=0
Dn Type=3
Dn Slope=0.005
Boundary for River Rch & Prof#=Stream0728,Reach-1,4
Up Type=0
Dn Type=3
Dn Slope=0.005
Boundary for River Rch & Prof#=Stream0728,Reach-1,5
Up Type=0
Dn Type=3
Dn Slope=0.005
Boundary for River Rch & Prof#=Stream0728,Reach-1,6
Up Type=0
Dn Type=3
Dn Slope=0.005
Boundary for River Rch & Prof#=Stream0728,Reach-1,7
Up Type=0
Dn Type=3
Dn Slope=0.005

--- Stream0728.g01 (geometry) ---

Geom Title=Existing Conditions

River Reach=Stream0728,Reach-1
Reach XY= 30
      2445325.00     13693475.00      2445275.51     13693385.55
      2445358.99     13693257.88      2445169.02     13693177.36
      2445072.57     13693169.48      2444878.46     13692973.50
      2444876.10     13692885.55      2444925.67     13692754.92
      2444825.61     13692614.37      2444873.19     13692518.87
      2444864.82     13692465.29      2444777.44     13692380.52
      2444665.21     13692364.48      2444488.63     13692188.21
      2444383.02     13692028.32      2444413.89     13691964.68
      2444285.39     13691885.10      2444252.27     13691751.11
      2444135.63     13691685.00      2443998.71     13691398.18
      2443873.35     13691278.16      2443774.97     13691317.45
      2443677.63     13691266.57      2443725.77     13691114.95
      2443675.38     13690940.27      2443722.73     13690869.06
      2443726.23     13690735.51      2443775.86     13690619.93
      2443745.79     13690544.50      2443675.00     13690525.00

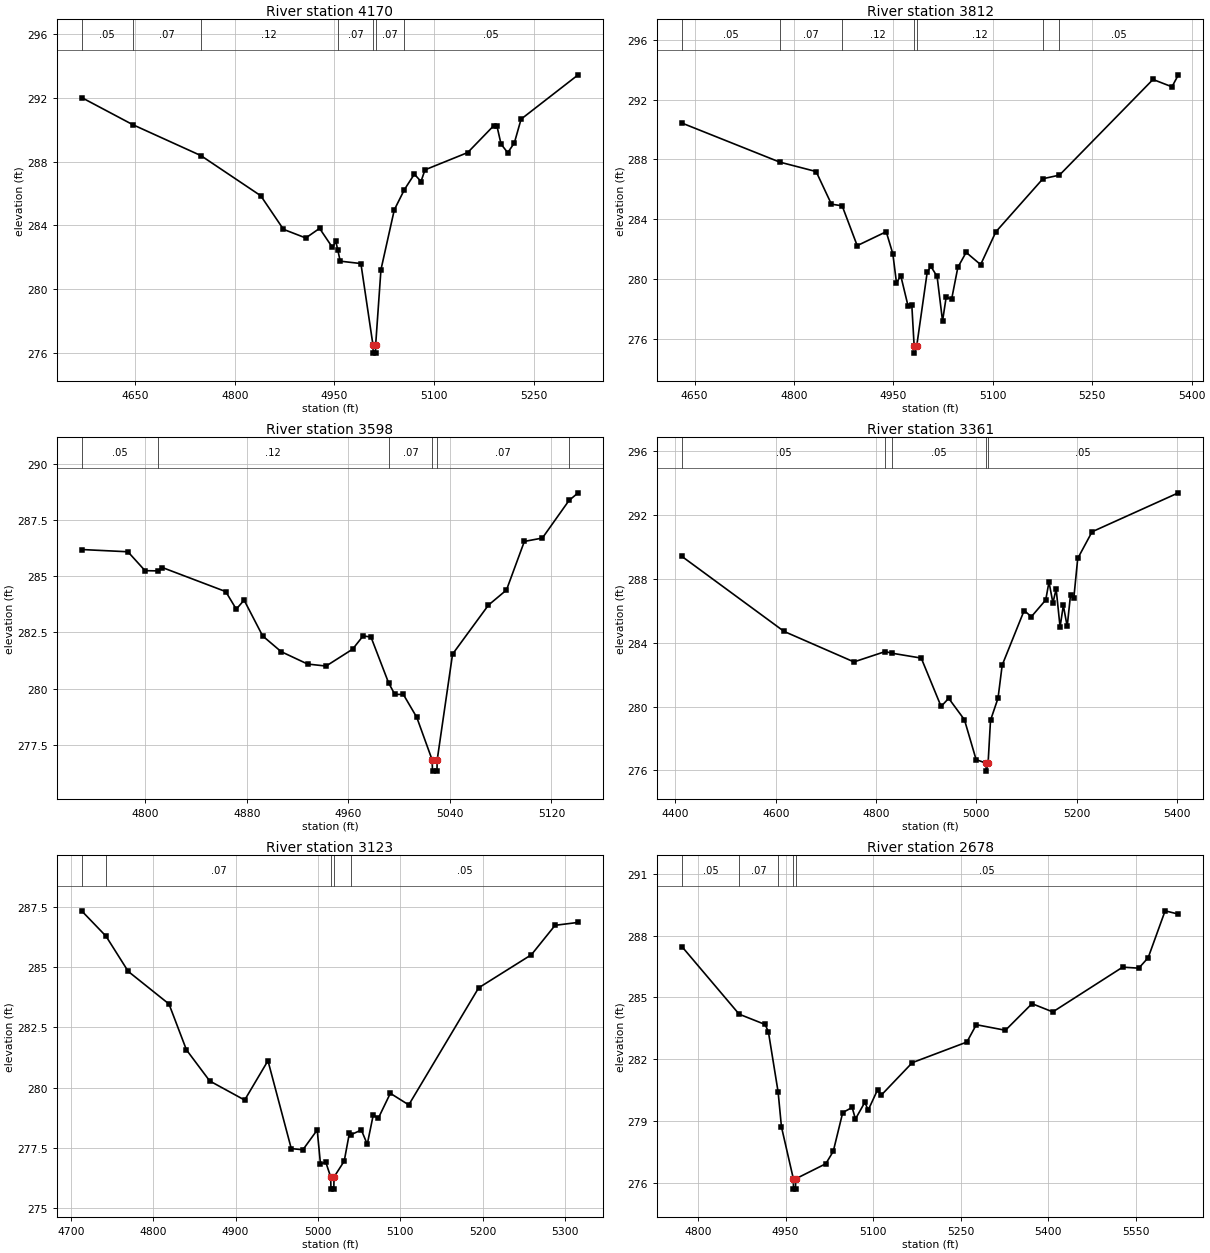
Type RM Length L Ch R = 1,4170,358,358,358
BEGIN DESCRIPTION:
Stream0728 8.0
END DESCRIPTION:
XS GIS Cut Line= 3
      2445690.17     13693297.81      2445283.24     13693411.02
      2444959.46     13693441.56
#Sta/Elev= 30
  4569.3  292.00  4646.0  290.31  4748.9  288.37  4839.0  285.86  4873.2  283.76
  4906.8  283.22  4927.6  283.82  4946.9  282.63  4952.1  283.00  4954.9  282.48
  4958.7  281.77  4989.8  281.62  5008.0  276.52  5008.3  276.02  5011.8  276.02
  5012.0  276.52  5020.0  281.24  5040.1  284.98  5055.4  286.25  5070.3  287.21
  5080.3  286.75  5086.3  287.48  5150.6  288.56  5189.8  290.24  5194.8  290.19
  5200.8  289.09  5210.9  288.55  5220.9  289.17  5231.0  290.65  5316.9  293.42
#Mann=7,-1,0
  4569.3    0.05       0  4646.0    0.07       0  4748.9    0.12       0
  4954.9    0.07       0  5008.0    0.05       0  5012.0    0.07       0
  5055.4    0.05       0
Bank Sta=5008,5012
Exp/Cntr=0.3,0.1

Type RM Length L Ch R = 1,3812,214,214,214
BEGIN DESCRIPTION:
E21301
END DESCRIPTION:
XS GIS Cut Line= 2
      2445546.35     13693057.72      2444862.82     13693364.69
#Sta/Elev= 30
  4630.7  290.43  4778.4  287.82  4833.3  287.19  4856.4  285.01  4872.6  284.90
  4895.3  282.24  4939.1  283.17  4949.1  281.69  4954.6  279.75  4961.0  280.24
  4972.0  278.22  4977.7  278.28  4981.2  275.56  4981.5  275.06  4985.2  275.56
  5000.9  280.45  5006.4  280.86  5015.9  280.18  5024.1  277.20  5029.6  278.81
  5037.8  278.66  5047.2  280.79  5059.7  281.79  5081.6  280.97  5104.5  283.16
  5175.6  286.71  5200.5  286.95  5341.7  293.34  5370.3  292.85  5380.0  293.65
#Mann=7,-1,0
  4630.7    0.05       0  4778.4    0.07       0  4872.6    0.12       0
  4981.2    0.05       0  4985.2    0.12       0  5175.6    0.07       0
  5200.5    0.05       0
Bank Sta=4981.2,4985.2
Exp/Cntr=0.3,0.1

Type RM Length L Ch R = 1,3598,237,237,237
BEGIN DESCRIPTION:
Stream0728 7.0
END DESCRIPTION:
XS GIS Cut Line= 3
      2445225.02     13692974.99      2445025.00     13693125.00
      2444925.03     13693224.97
#Sta/Elev= 30
  4749.7  286.18  4786.2  286.08  4799.7  285.24  4809.9  285.23  4813.3  285.38
  4863.3  284.31  4871.6  283.53  4877.8  283.93  4892.4  282.34  4907.0  281.64
  4927.8  281.09  4942.4  281.00  4963.3  281.75  4971.6  282.34  4977.8  282.29
  4991.7  280.25  4996.6  279.74  5003.3  279.74  5013.9  278.72  5026.0  276.83
  5026.3  276.33  5029.8  276.33  5030.0  276.83  5042.1  281.53  5070.4  283.71
  5084.6  284.38  5098.7  286.54  5112.9  286.69  5133.9  288.36  5141.1  288.70
#Mann=6,-1,0
  4749.7    0.05       0  4809.9    0.12       0  4991.7    0.07       0
  5026.0    0.05       0  5030.0    0.07       0  5133.9    0.05       0
Bank Sta=5026,5030
Exp/Cntr=0.3,0.1

Type RM Length L Ch R = 1,3361,238,238,238
BEGIN DESCRIPTION:
E21300
END DESCRIPTION:
XS GIS Cut Line= 3
      2445411.26     13692709.84      2444793.27     13692984.05
      2444592.72     13693225.54
#Sta/Elev= 30
  4412.7  289.41  4616.5  284.71  4755.8  282.80  4818.3  283.45  4830.7  283.35
  4890.0  283.04  4929.6  280.01  4944.7  280.52  4976.1  279.18  4999.4  276.68
  5019.3  276.46  5019.5  275.96  5023.3  276.46  5028.1  279.14  5043.1  280.53
  5051.4  282.60  5095.2  286.02  5109.5  285.63  5138.2  286.68  5144.7  287.81
  5152.5  286.50  5159.0  287.36  5166.8  284.98  5173.3  286.34  5181.0  285.02
  5187.7  287.02  5194.2  286.80  5202.0  289.28  5230.6  290.95  5402.7  293.39
#Mann=5,-1,0
  4412.7    0.05       0  4818.3    0.07       0  4830.7    0.05       0
  5019.3    0.05       0  5023.3    0.05       0
Bank Sta=5019.3,5023.3
Exp/Cntr=0.3,0.1

Type RM Length L Ch R = 1,3123,445,445,445
BEGIN DESCRIPTION:
Stream0728 6.0
END DESCRIPTION:
XS GIS Cut Line= 3
      2445125.03     13692524.97      2444925.00     13692725.00
      2444675.04     13692924.97
#Sta/Elev= 30
  4713.1  287.33  4742.7  286.28  4769.7  284.82  4819.2  283.47  4840.4  281.57
  4868.7  280.28  4911.1  279.49  4939.4  281.12  4967.7  277.48  4981.8  277.43
  4999.2  278.25  5003.2  276.84  5009.6  276.92  5015.6  276.30  5015.9  275.80
  5019.4  275.80  5019.6  276.30  5032.0  276.96  5038.4  278.14  5040.6  278.06
  5052.8  278.25  5060.0  277.66  5067.2  278.86  5073.6  278.75  5088.0  279.77
  5110.4  279.29  5195.3  284.14  5259.3  285.51  5288.1  286.73  5316.1  286.85
#Mann=5,-1,0
  4713.1    0.05       0  4742.7    0.07       0  5015.6    0.05       0
  5019.6    0.07       0  5040.6    0.05       0
Bank Sta=5015.6,5019.6
Exp/Cntr=0.3,0.1

Type RM Length L Ch R = 1,2678,422,422,422
BEGIN DESCRIPTION:
Stream0728 5.0
END DESCRIPTION:
XS GIS Cut Line= 3
      2444975.03     13692274.98      2444775.00     13692375.00
      2444475.02     13692924.96
#Sta/Elev= 30
  4772.4  287.47  4870.5  284.19  4915.0  283.69  4920.6  283.33  4937.2  280.42
  4942.9  278.73  4963.3  276.21  4963.5  275.71  4967.0  275.71  4967.3  276.21
  5018.8  276.94  5031.6  277.54  5047.8  279.42  5063.9  279.67  5069.6  279.11
  5085.7  279.92  5091.4  279.54  5107.6  280.53  5113.3  280.25  5166.9  281.84
  5260.4  282.84  5276.5  283.68  5326.4  283.41  5371.9  284.70  5407.5  284.30
  5527.1  286.47  5554.7  286.42  5570.8  286.93  5599.8  289.20  5622.5  289.04
#Mann=5,-1,0
  4772.4    0.05       0  4870.5    0.07       0  4937.2    0.05       0
  4963.3    0.05       0  4967.3    0.05       0
Bank Sta=4963.3,4967.3
Exp/Cntr=0.3,0.1

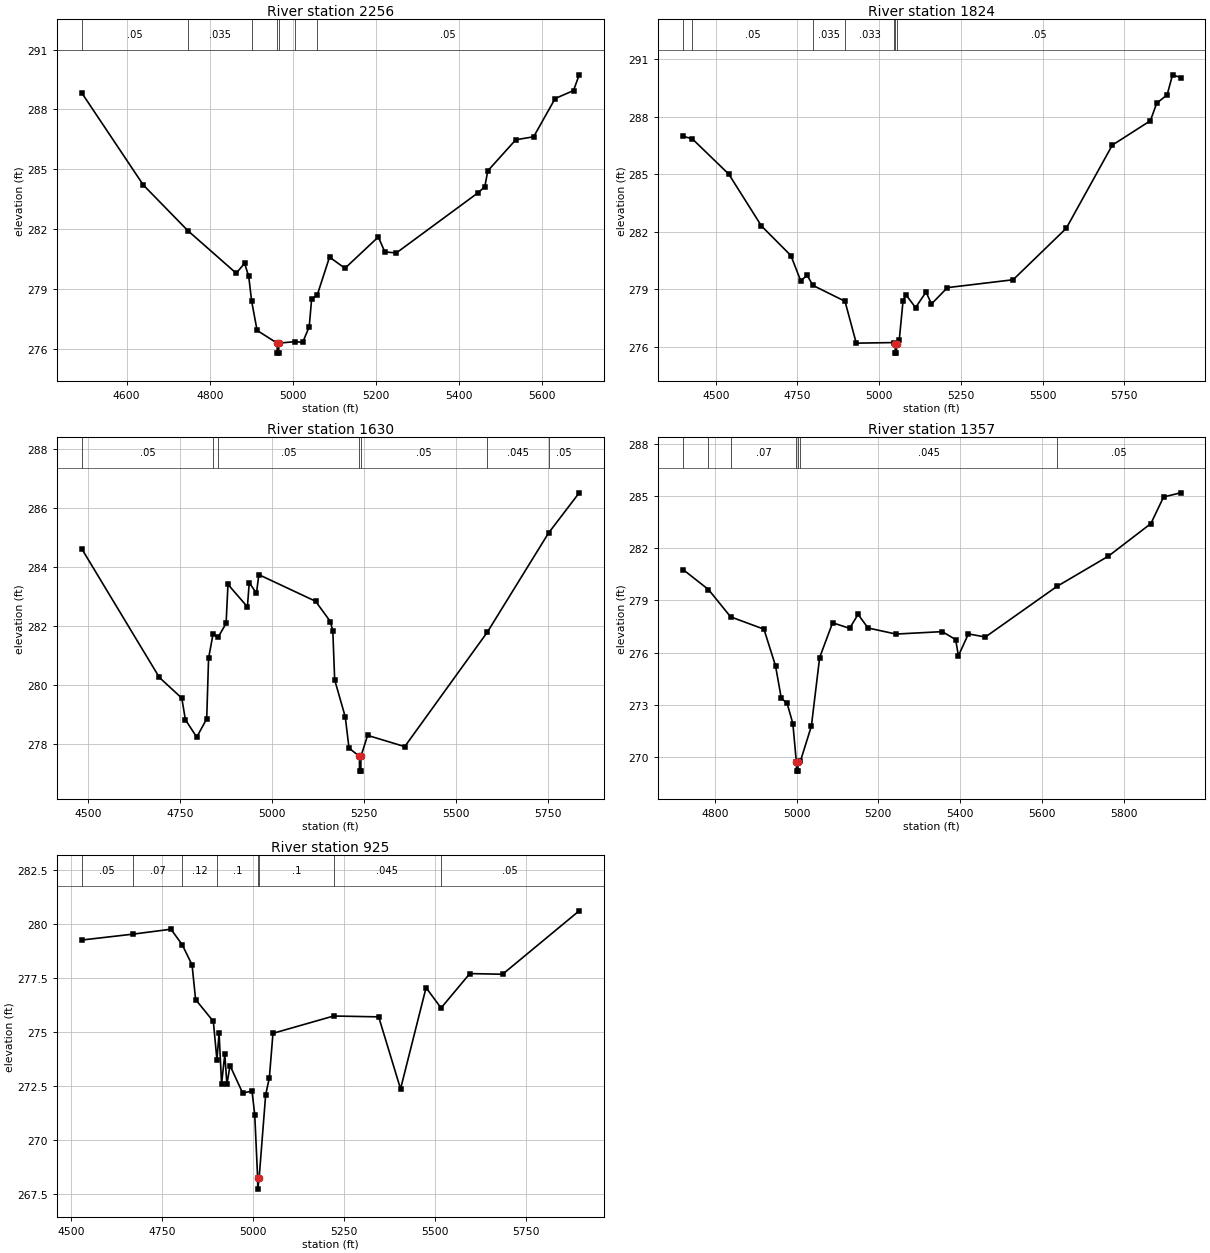
Type RM Length L Ch R = 1,2256,432,432,432
BEGIN DESCRIPTION:
Stream0728 4.0
END DESCRIPTION:
XS GIS Cut Line= 3
      2444975.04     13692075.00      2444475.00     13692125.00
      2444124.98     13692725.04
#Sta/Elev= 30
  4491.7  288.84  4640.0  284.21  4747.1  281.92  4863.6  279.78  4883.7  280.28
  4893.7  279.62  4900.7  278.38  4913.8  276.91  4962.1  276.27  4962.3  275.77
  4965.8  275.77  4966.1  276.27  5006.1  276.35  5023.6  276.31  5039.3  277.10
  5045.1  278.50  5058.3  278.67  5088.1  280.59  5125.3  280.03  5205.5  281.60
  5221.2  280.85  5248.9  280.80  5446.2  283.83  5461.9  284.13  5468.9  284.92
  5536.3  286.48  5579.3  286.63  5631.0  288.55  5675.2  288.95  5688.9  289.74
#Mann=7,-1,0
  4491.7    0.05       0  4747.1   0.035       0  4900.7    0.07       0
  4962.1    0.05       0  4966.1    0.07       0  5006.1   0.035       0
  5058.3    0.05       0
Bank Sta=4962.1,4966.1
Exp/Cntr=0.3,0.1

Type RM Length L Ch R = 1,1824,194,194,194
BEGIN DESCRIPTION:
Stream0728 3.0
END DESCRIPTION:
XS GIS Cut Line= 3
      2444875.02     13691825.00      2444275.00     13691825.00
      2444075.00     13692725.02
#Sta/Elev= 30
  4399.9  286.97  4428.1  286.84  4539.9  285.00  4639.9  282.30  4729.9  280.76
  4759.9  279.45  4779.9  279.73  4797.0  279.21  4895.4  278.38  4929.9  276.20
  5046.3  276.23  5049.1  276.18  5049.4  275.68  5052.9  275.68  5053.1  276.18
  5061.4  276.36  5072.9  278.38  5081.9  278.72  5111.3  278.05  5143.3  278.86
  5160.0  278.24  5208.6  279.09  5409.7  279.50  5572.3  282.18  5713.2  286.51
  5829.7  287.78  5848.9  288.69  5880.9  289.13  5897.5  290.17  5921.9  290.03
#Mann=7,-1,0
  4399.9   0.045       0  4428.1    0.05       0  4797.0   0.035       0
  4895.4   0.033       0  5046.3    0.05       0  5049.1   0.033       0
  5053.1    0.05       0
Bank Sta=5049.1,5053.1
Exp/Cntr=0.3,0.1

Type RM Length L Ch R = 1,1630,273,273,273
BEGIN DESCRIPTION:
XS7556
END DESCRIPTION:
XS GIS Cut Line= 4
      2444652.97     13691587.66      2444191.05     13691673.32
      2444117.63     13691734.50      2444001.38     13692514.62
#Sta/Elev= 30
  4481.5  284.62  4693.0  280.26  4754.0  279.56  4763.8  278.83  4794.7  278.24
  4821.8  278.86  4826.9  280.91  4838.9  281.72  4853.6  281.64  4874.6  282.09
  4879.7  283.41  4932.6  282.65  4937.6  283.47  4957.2  283.11  4963.7  283.74
  5118.1  282.84  5158.6  282.15  5165.1  281.82  5170.1  280.18  5199.0  278.92
  5209.1  277.87  5237.5  277.59  5237.7  277.09  5241.2  277.09  5241.5  277.59
  5259.7  278.30  5360.8  277.92  5585.9  281.80  5752.2  285.15  5835.6  286.51
#Mann=7,-1,0
  4481.5    0.05       0  4838.9   0.033       0  4853.6    0.05       0
  5237.5    0.05       0  5241.5    0.05       0  5585.9   0.045       0
  5752.2    0.05       0
Bank Sta=5237.5,5241.5
Exp/Cntr=0.3,0.1

Type RM Length L Ch R = 1,1357,432,432,432
BEGIN DESCRIPTION:
Stream0728 2.0
END DESCRIPTION:
XS GIS Cut Line= 3
      2444225.01     13691274.99      2444025.00     13691475.00
      2443775.01     13692374.97
#Sta/Elev= 30
  4722.2  280.77  4784.5  279.62  4838.6  278.05  4920.2  277.34  4948.5  275.23
  4962.6  273.37  4976.8  273.08  4990.9  271.91  4999.5  269.68  4999.8  269.18
  5003.3  269.18  5003.5  269.68  5009.2  269.74  5036.2  271.77  5056.4  275.71
  5088.1  277.71  5129.6  277.39  5150.4  278.19  5174.7  277.41  5243.2  277.06
  5356.4  277.20  5389.1  276.74  5395.8  275.81  5420.2  277.07  5461.7  276.89
  5636.8  279.80  5762.7  281.54  5866.5  283.41  5897.6  284.94  5939.1  285.18
#Mann=7,-1,0
  4722.2   0.045       0  4784.5    0.05       0  4838.6    0.07       0
  4999.5    0.05       0  5003.5    0.07       0  5009.2   0.045       0
  5636.8    0.05       0
Bank Sta=4999.5,5003.5
Exp/Cntr=0.3,0.1

Type RM Length L Ch R = 1,925,0,0,0
BEGIN DESCRIPTION:
Stream0728 1.0
END DESCRIPTION:
XS GIS Cut Line= 3
      2444126.82     13691040.03      2443725.00     13691275.00
      2443675.00     13692175.03
#Sta/Elev= 30
  4529.0  279.25  4668.7  279.52  4774.4  279.75  4805.7  279.02  4832.3  278.10
  4842.0  276.50  4890.8  275.49  4900.6  273.71  4906.5  274.95  4913.4  272.60
  4922.2  273.98  4928.0  272.58  4936.6  273.45  4971.3  272.18  4997.0  272.27
  5004.5  271.18  5012.5  268.24  5012.8  267.74  5016.5  268.24  5034.5  272.10
  5044.6  272.88  5054.6  274.94  5221.3  275.74  5345.0  275.70  5405.1  272.37
  5475.2  277.05  5516.4  276.11  5595.4  277.70  5685.5  277.67  5895.9  280.60
#Mann=8,-1,0
  4529.0    0.05       0  4668.7    0.07       0  4805.7    0.12       0
  4900.6     0.1       0  5012.5    0.05       0  5016.5     0.1       0
  5221.3   0.045       0  5516.4    0.05       0
Bank Sta=5012.5,5016.5
Exp/Cntr=0.3,0.1

Chan Stop Cuts=-1