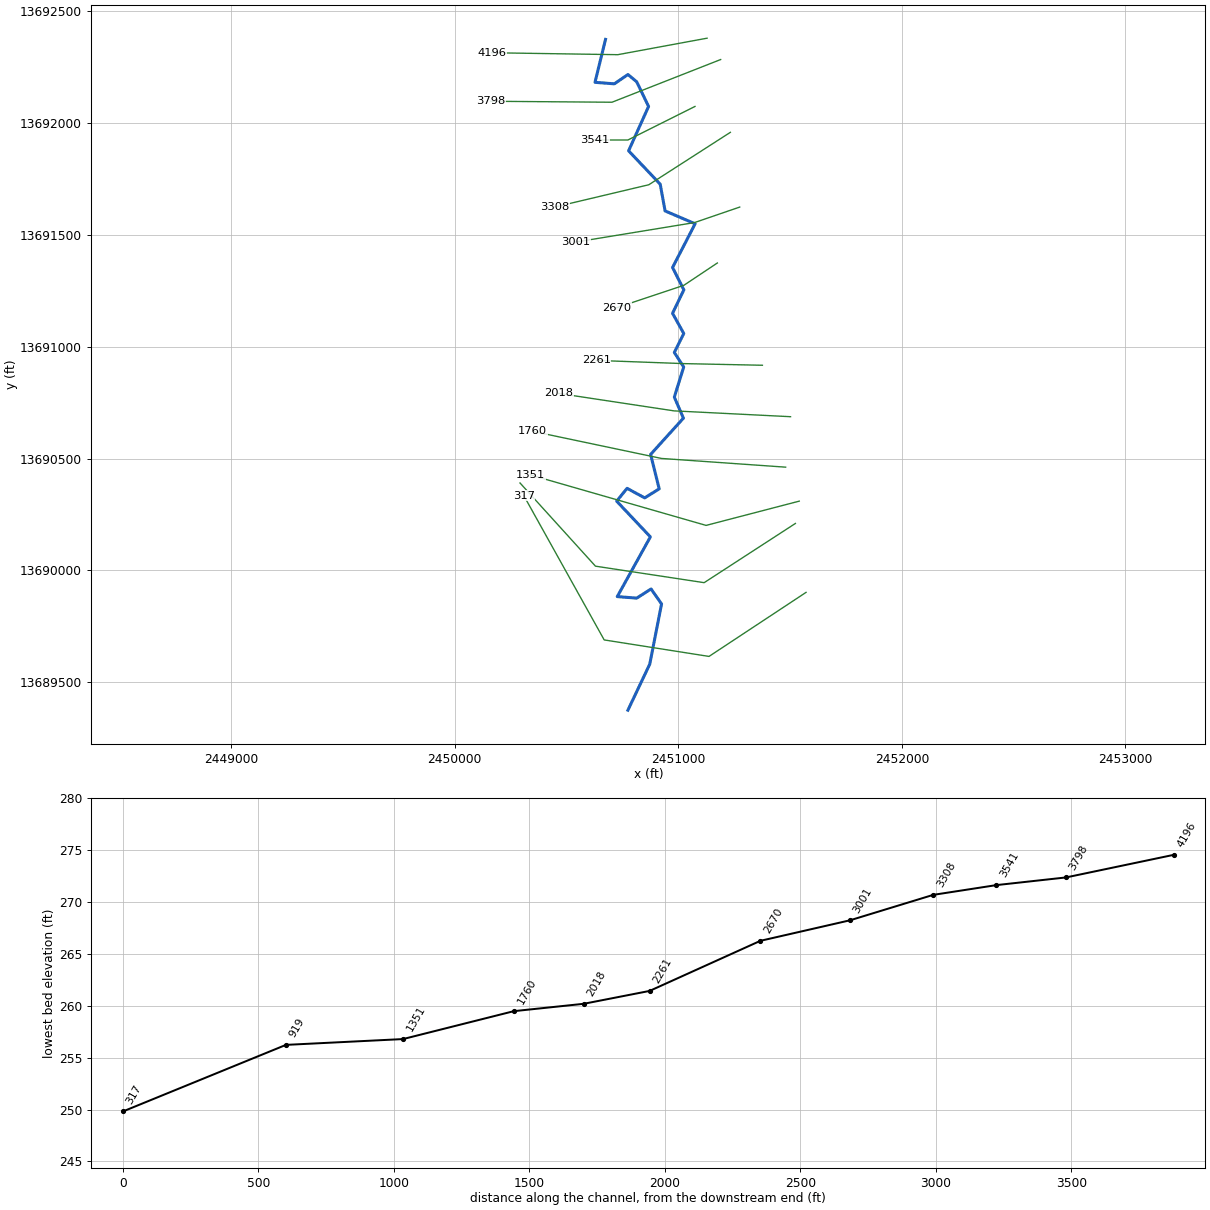
--- Stream0729.prj (project) ---

Proj Title=Stream0729 Base Level Engineering
Current Plan=p01
Default Exp/Contr=0.3,0.1
English Units
Geom File=g01
Flow File=f01
Plan File=p01
BEGIN DESCRIPTION:
Stream0729
END DESCRIPTION:

--- Stream0729.p01 (plan) ---

Plan Title=Multiple Run
Short Identifier=Multiple
Geom File=g01
Flow File=f01
Subcritical Flow
K Sum by GR= 0
Std Step Tol= 0.01
Critical Tol= 0.01
Num of Std Step Trials= 20
Max Error Tol= 0.3
Flow Tol Ratio= 0.001
Split Flow NTrial= 30
Split Flow Tol= 0.02
Split Flow Ratio= 0.02
Log Output Level= 0
Friction Slope Method= 1
Unsteady Friction Slope Method= 2
Unsteady Bridges Friction Slope Method= 1
Parabolic Critical Depth
Global Vel Dist=  1 , 1 , 1
Global Log Level= 0
CheckData=True
Encroach Param= -1, 0, 0, 0
BEGIN DESCRIPTION:
Multiple Run
END DESCRIPTION:

--- Stream0729.f01 (steady flow) ---

Flow Title=Multiple
Number of Profiles=7
Profile Names=10-year,25-year,50-year,1pct_min,100-year,1pct_plu,500-year
River Rch & RM= Stream0729,Reach-1,4196
     328     505     656     414     827    1650    1297
Boundary for River Rch & Prof#=Stream0729,Reach-1,1
Up Type=0
Dn Type=3
Dn Slope=0.005
Boundary for River Rch & Prof#=Stream0729,Reach-1,2
Up Type=0
Dn Type=3
Dn Slope=0.005
Boundary for River Rch & Prof#=Stream0729,Reach-1,3
Up Type=0
Dn Type=3
Dn Slope=0.005
Boundary for River Rch & Prof#=Stream0729,Reach-1,4
Up Type=0
Dn Type=3
Dn Slope=0.005
Boundary for River Rch & Prof#=Stream0729,Reach-1,5
Up Type=0
Dn Type=3
Dn Slope=0.005
Boundary for River Rch & Prof#=Stream0729,Reach-1,6
Up Type=0
Dn Type=3
Dn Slope=0.005
Boundary for River Rch & Prof#=Stream0729,Reach-1,7
Up Type=0
Dn Type=3
Dn Slope=0.005

--- Stream0729.g01 (geometry) ---

Geom Title=Existing Conditions

River Reach=Stream0729,Reach-1
Reach XY= 30
      2450675.00     13692375.00      2450627.84     13692182.88
      2450714.40     13692176.22      2450775.31     13692217.77
      2450814.26     13692185.41      2450867.50     13692075.00
      2450778.12     13691876.63      2450919.47     13691727.42
      2450941.28     13691607.80      2451075.62     13691550.30
      2450974.71     13691354.82      2451025.26     13691254.82
      2450974.62     13691150.00      2451024.83     13691059.59
      2450982.60     13690975.01      2451024.48     13690909.78
      2450982.60     13690774.99      2451023.34     13690681.05
      2450876.62     13690518.96      2450914.94     13690364.88
      2450850.10     13690324.56      2450771.27     13690367.28
      2450724.86     13690309.86      2450875.54     13690150.12
      2450727.46     13689883.05      2450814.39     13689876.23
      2450878.71     13689917.32      2450925.50     13689850.22
      2450872.73     13689580.94      2450775.00     13689375.00

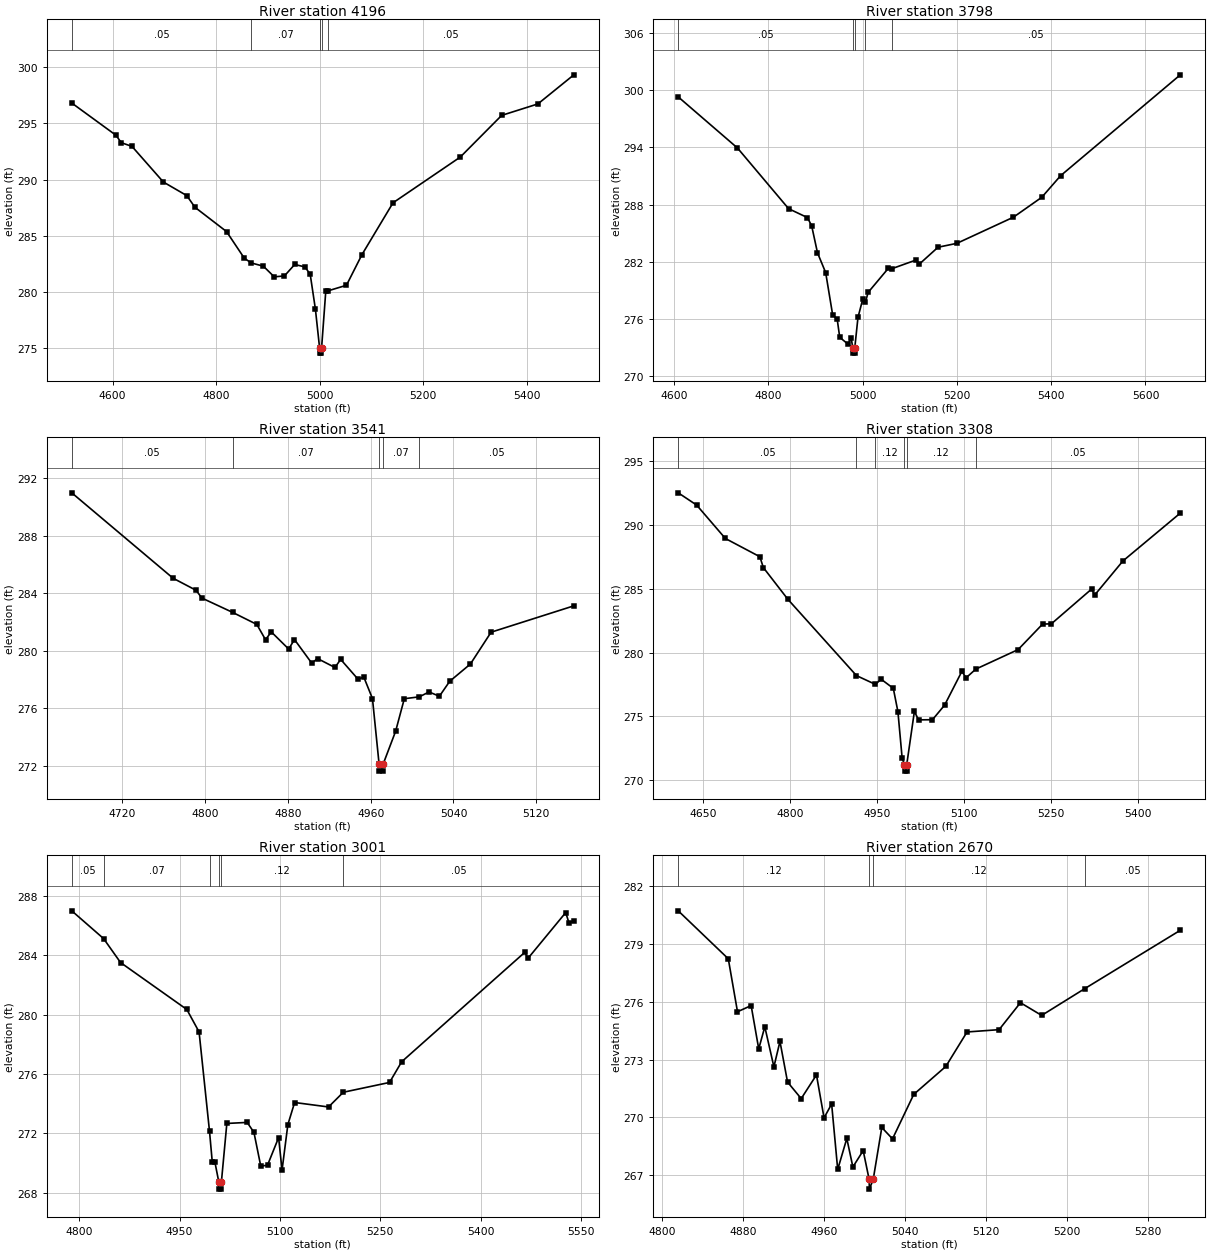
Type RM Length L Ch R = 1,4196,398,398,398
BEGIN DESCRIPTION:
Stream0729 8.0
END DESCRIPTION:
XS GIS Cut Line= 3
      2451129.10     13692380.30      2450729.77     13692306.51
      2450165.53     13692315.19
#Sta/Elev= 30
  4521.0  296.82  4606.5  293.95  4616.7  293.29  4637.4  292.96  4698.0  289.79
  4743.3  288.58  4759.1  287.54  4820.1  285.38  4854.3  283.02  4867.6  282.59
  4891.3  282.30  4912.3  281.35  4932.0  281.43  4951.9  282.45  4971.9  282.23
  4981.9  281.56  4991.9  278.47  4999.9  275.06  5000.1  274.56  5003.6  274.56
  5003.9  275.06  5011.9  280.05  5016.0  280.10  5051.9  280.60  5081.9  283.33
  5141.9  287.94  5271.9  292.01  5351.9  295.72  5421.9  296.74  5491.4  299.33
#Mann=5,-1,0
  4521.0    0.05       0  4867.6    0.07       0  4999.9    0.05       0
  5003.9    0.07       0  5016.0    0.05       0
Bank Sta=4999.9,5003.9
Exp/Cntr=0.3,0.1

Type RM Length L Ch R = 1,3798,257,257,257
BEGIN DESCRIPTION:
XS7563
END DESCRIPTION:
XS GIS Cut Line= 3
      2451189.83     13692284.80      2450703.73     13692093.84
      2450161.21     13692098.18
#Sta/Elev= 30
  4609.1  299.31  4734.7  293.94  4843.2  287.56  4882.9  286.63  4892.0  285.78
  4904.4  282.93  4921.8  280.84  4936.6  276.40  4946.2  275.95  4951.6  274.04
  4968.8  273.34  4976.0  273.94  4979.4  272.88  4979.6  272.38  4983.1  272.38
  4983.4  272.88  4990.3  276.14  5000.4  278.04  5006.2  277.75  5011.8  278.76
  5054.6  281.29  5061.4  281.24  5114.2  282.18  5119.6  281.70  5160.1  283.51
  5200.1  283.92  5320.1  286.67  5380.1  288.76  5420.1  291.03  5673.9  301.63
#Mann=5,-1,0
  4609.1    0.05       0  4979.4    0.05       0  4983.4    0.05       0
  5006.2    0.07       0  5061.4    0.05       0
Bank Sta=4979.4,4983.4
Exp/Cntr=0.3,0.1

Type RM Length L Ch R = 1,3541,233,233,233
BEGIN DESCRIPTION:
Stream0729 7.0
END DESCRIPTION:
XS GIS Cut Line= 3
      2451075.03     13692075.02      2450775.00     13691925.00
      2450625.05     13691925.00
#Sta/Elev= 30
  4671.0  290.97  4768.9  285.04  4791.2  284.20  4796.8  283.66  4826.4  282.67
  4849.9  281.83  4858.3  280.77  4863.9  281.31  4880.7  280.12  4886.3  280.78
  4903.0  279.14  4908.6  279.46  4925.4  278.84  4931.0  279.40  4947.8  278.02
  4953.3  278.18  4961.7  276.68  4968.1  272.14  4968.4  271.64  4971.9  271.64
  4972.1  272.14  4984.1  274.41  4992.5  276.67  5007.0  276.80  5016.4  277.14
  5026.4  276.84  5036.4  277.88  5056.4  279.08  5076.4  281.29  5156.4  283.12
#Mann=5,-1,0
  4671.0    0.05       0  4826.4    0.07       0  4968.1    0.05       0
  4972.1    0.07       0  5007.0    0.05       0
Bank Sta=4968.1,4972.1
Exp/Cntr=0.3,0.1

Type RM Length L Ch R = 1,3308,307,307,307
BEGIN DESCRIPTION:
XS7562
END DESCRIPTION:
XS GIS Cut Line= 3
      2451233.27     13691959.30      2450868.66     13691724.91
      2450448.85     13691625.37
#Sta/Elev= 30
  4607.8  292.52  4639.5  291.56  4689.0  288.94  4748.4  287.51  4754.4  286.66
  4796.7  284.17  4914.8  278.19  4947.5  277.50  4957.2  277.91  4978.3  277.19
  4986.2  275.37  4993.5  271.73  4997.4  271.20  4997.7  270.70  5001.2  270.70
  5001.4  271.20  5014.6  275.38  5021.8  274.72  5045.7  274.73  5066.6  275.87
  5096.4  278.52  5103.7  278.02  5120.5  278.70  5193.3  280.23  5235.5  282.23
  5250.6  282.25  5320.0  284.98  5325.1  284.50  5373.9  287.18  5472.7  290.93
#Mann=6,-1,0
  4607.8    0.05       0  4914.8    0.07       0  4947.5    0.12       0
  4997.4    0.05       0  5001.4    0.12       0  5120.5    0.05       0
Bank Sta=4997.4,5001.4
Exp/Cntr=0.3,0.1

Type RM Length L Ch R = 1,3001,331,331,331
BEGIN DESCRIPTION:
Stream0729 6.0
END DESCRIPTION:
XS GIS Cut Line= 3
      2451275.00     13691625.00      2451072.66     13691555.64
      2450543.12     13691468.83
#Sta/Elev= 30
  4788.8  286.98  4836.4  285.11  4861.7  283.50  4960.8  280.34  4979.1  278.83
  4994.7  272.14  4998.8  270.08  5002.7  270.08  5008.5  268.75  5008.7  268.25
  5012.2  268.25  5012.5  268.75  5020.6  272.67  5051.0  272.74  5061.1  272.07
  5071.3  269.80  5081.4  269.86  5098.0  271.72  5103.1  269.52  5111.8  272.59
  5121.9  274.08  5172.6  273.78  5194.7  274.77  5263.8  275.43  5281.9  276.82
  5465.8  284.18  5470.9  283.79  5527.1  286.86  5532.2  286.15  5539.3  286.32
#Mann=6,-1,0
  4788.8    0.05       0  4836.4    0.07       0  4994.7    0.12       0
  5008.5    0.05       0  5012.5    0.12       0  5194.7    0.05       0
Bank Sta=5008.5,5012.5
Exp/Cntr=0.3,0.1

Type RM Length L Ch R = 1,2670,409,409,409
BEGIN DESCRIPTION:
Stream0729 5.0
END DESCRIPTION:
XS GIS Cut Line= 3
      2451174.97     13691374.98      2451025.00     13691275.00
      2450724.97     13691174.99
#Sta/Elev= 30
  4815.9  280.72  4865.4  278.23  4874.5  275.48  4888.0  275.80  4895.5  273.55
  4901.5  274.70  4910.5  272.62  4916.5  273.94  4924.0  271.83  4937.5  270.97
  4952.6  272.20  4960.1  269.97  4967.6  270.69  4973.6  267.29  4982.6  268.90
  4988.6  267.42  4998.8  268.27  5004.7  266.77  5004.9  266.27  5008.7  266.77
  5017.2  269.47  5027.8  268.88  5048.8  271.19  5080.5  272.64  5101.5  274.43
  5133.2  274.55  5154.3  275.95  5175.3  275.29  5217.9  276.68  5312.4  279.71
#Mann=4,-1,0
  4815.9    0.12       0  5004.7    0.05       0  5008.7    0.12       0
  5217.9    0.05       0
Bank Sta=5004.7,5008.7
Exp/Cntr=0.3,0.1

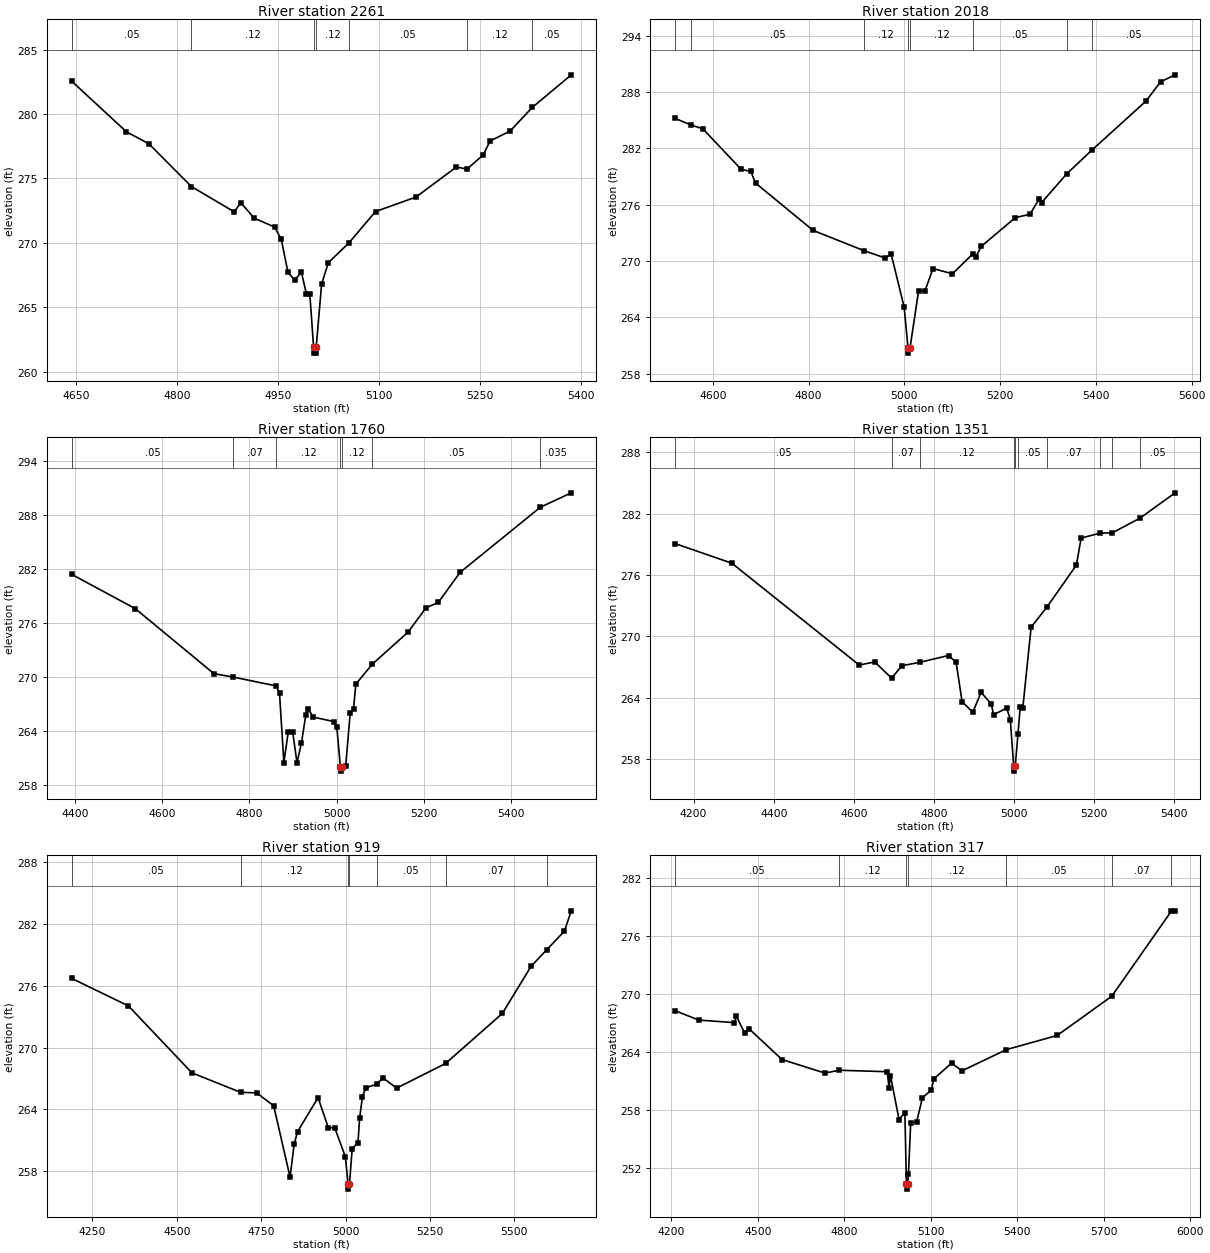
Type RM Length L Ch R = 1,2261,243,243,243
BEGIN DESCRIPTION:
Stream0729 4.0
END DESCRIPTION:
XS GIS Cut Line= 3
      2451376.52     13690917.62      2451025.00     13690925.00
      2450634.26     13690939.32
#Sta/Elev= 30
  4643.6  282.56  4725.1  278.62  4758.5  277.69  4821.7  274.37  4885.2  272.41
  4895.2  273.11  4915.2  271.91  4945.2  271.23  4955.2  270.28  4965.2  267.70
  4975.2  267.12  4985.2  267.72  4992.7  266.00  4997.7  266.00  5003.2  261.94
  5003.5  261.44  5007.0  261.44  5007.2  261.94  5015.2  266.81  5025.2  268.46
  5055.5  269.98  5095.3  272.43  5155.3  273.55  5215.3  275.88  5231.5  275.73
  5255.4  276.83  5265.4  277.90  5295.4  278.68  5328.2  280.51  5386.2  283.04
#Mann=7,-1,0
  4643.6    0.05       0  4821.7    0.12       0  5003.2    0.05       0
  5007.2    0.12       0  5055.5    0.05       0  5231.5    0.12       0
  5328.2    0.05       0
Bank Sta=5003.2,5007.2
Exp/Cntr=0.3,0.1

Type RM Length L Ch R = 1,2018,258,258,258
BEGIN DESCRIPTION:
XS7561
END DESCRIPTION:
XS GIS Cut Line= 3
      2451502.36     13690687.59      2450981.51     13690713.63
      2450464.98     13690791.76
#Sta/Elev= 30
  4521.6  285.19  4554.7  284.49  4579.0  284.09  4659.1  279.77  4679.2  279.55
  4689.2  278.31  4809.3  273.27  4915.3  271.12  4959.5  270.34  4972.5  270.72
  4999.6  265.09  5007.6  260.70  5007.8  260.20  5011.6  260.70  5029.6  266.81
  5043.1  266.85  5059.8  269.21  5100.3  268.65  5143.6  270.80  5149.2  270.46
  5160.9  271.58  5231.7  274.63  5262.1  274.99  5281.8  276.62  5286.8  276.24
  5339.0  279.29  5391.0  281.79  5504.8  287.05  5535.1  289.10  5565.5  289.84
#Mann=8,-1,0
  4521.6   0.035       0  4554.7    0.05       0  4915.3    0.12       0
  5007.6    0.05       0  5011.6    0.12       0  5143.6    0.05       0
  5339.0    0.12       0  5391.0    0.05       0
Bank Sta=5007.6,5011.6
Exp/Cntr=0.3,0.1

Type RM Length L Ch R = 1,1760,409,409,409
BEGIN DESCRIPTION:
XS7560
END DESCRIPTION:
XS GIS Cut Line= 3
      2451480.64     13690461.89      2450925.09     13690500.95
      2450348.94     13690622.25
#Sta/Elev= 30
  4392.1  281.36  4538.1  277.55  4718.5  270.32  4762.9  269.94  4861.7  268.95
  4868.9  268.12  4878.9  260.44  4889.0  263.89  4899.0  263.85  4909.0  260.43
  4919.0  262.57  4929.1  265.71  4934.7  266.39  4946.6  265.49  4994.0  264.99
  5000.2  264.42  5008.4  259.99  5008.7  259.49  5012.4  259.99  5020.6  260.06
  5030.9  265.92  5038.7  266.43  5043.8  269.15  5081.7  271.38  5163.7  274.94
  5204.6  277.63  5232.9  278.23  5282.7  281.57  5466.9  288.81  5537.8  290.41
#Mann=7,-1,0
  4392.1    0.05       0  4762.9    0.07       0  4861.7    0.12       0
  5008.4    0.05       0  5012.4    0.12       0  5081.7    0.05       0
  5466.9   0.035       0
Bank Sta=5008.4,5012.4
Exp/Cntr=0.3,0.1

Type RM Length L Ch R = 1,1351,432,432,432
BEGIN DESCRIPTION:
XS7559
END DESCRIPTION:
XS GIS Cut Line= 3
      2451541.41     13690309.98      2451124.74     13690201.48
      2450339.57     13690427.05
#Sta/Elev= 30
  4154.4  279.07  4295.4  277.16  4613.3  267.19  4652.2  267.49  4694.3  265.90
  4719.6  267.12  4764.1  267.45  4836.4  268.12  4855.2  267.46  4870.1  263.61
  4896.8  262.56  4917.6  264.51  4942.7  263.39  4948.9  262.33  4981.6  262.97
  4990.5  261.85  4998.9  257.30  4999.1  256.80  5002.9  257.30  5009.5  260.40
  5015.3  263.07  5021.7  262.99  5042.5  270.90  5081.5  272.84  5155.4  276.97
  5167.3  279.62  5214.4  280.10  5245.5  280.14  5313.8  281.56  5401.9  284.05
#Mann=10,-1,0
  4154.4    0.05       0  4694.3    0.07       0  4764.1    0.12       0
  4998.9    0.05       0  5002.9    0.12       0  5009.5    0.05       0
  5081.5    0.07       0  5214.4    0.05       0  5245.5   0.035       0
  5313.8    0.05       0
Bank Sta=4998.9,5002.9
Exp/Cntr=0.3,0.1

Type RM Length L Ch R = 1,919,602,602,602
BEGIN DESCRIPTION:
XS7558
END DESCRIPTION:
XS GIS Cut Line= 4
      2451524.05     13690210.16      2451116.06     13689945.40
      2450629.95     13690019.18      2450292.53     13690391.21
#Sta/Elev= 30
  4188.5  276.74  4357.2  274.05  4545.0  267.55  4689.4  265.65  4736.6  265.60
  4787.2  264.35  4835.8  257.41  4847.9  260.61  4858.0  261.83  4918.7  265.14
  4949.0  262.22  4968.1  262.20  4999.6  259.38  5007.7  256.74  5008.0  256.24
  5011.7  256.74  5019.8  260.17  5036.9  260.74  5041.9  263.18  5050.2  265.24
  5060.3  266.10  5092.4  266.44  5110.9  267.06  5151.3  266.06  5296.5  268.46
  5464.4  273.32  5549.6  277.90  5596.2  279.52  5648.2  281.32  5668.8  283.30
#Mann=7,-1,0
  4188.5    0.05       0  4689.4    0.12       0  5007.7    0.05       0
  5011.7    0.12       0  5092.4    0.05       0  5296.5    0.07       0
  5596.2    0.05       0
Bank Sta=5007.7,5011.7
Exp/Cntr=0.3,0.1

Type RM Length L Ch R = 1,317,0,0,0
BEGIN DESCRIPTION:
XS7557
END DESCRIPTION:
XS GIS Cut Line= 4
      2451571.76     13689901.98      2451137.76     13689615.54
      2450669.01     13689689.32      2450309.40     13690334.89
#Sta/Elev= 30
  4213.9  268.29  4295.0  267.33  4418.4  267.06  4425.7  267.71  4454.6  265.97
  4469.6  266.42  4584.0  263.24  4732.6  261.84  4782.3  262.13  4949.3  261.98
  4954.9  260.30  4960.0  261.57  4989.8  257.03  5010.0  257.73  5015.5  250.32
  5015.7  249.82  5019.5  250.32  5022.5  251.40  5030.3  256.70  5050.5  256.74
  5070.8  259.27  5101.1  260.06  5111.3  261.25  5172.0  262.87  5207.9  262.07
  5362.3  264.27  5538.2  265.73  5727.8  269.80  5934.6  278.62  5947.4  278.64
#Mann=7,-1,0
  4213.9    0.05       0  4782.3    0.12       0  5015.5    0.05       0
  5019.5    0.12       0  5362.3    0.05       0  5727.8    0.07       0
  5934.6    0.05       0
Bank Sta=5015.5,5019.5
Exp/Cntr=0.3,0.1

Chan Stop Cuts=-1