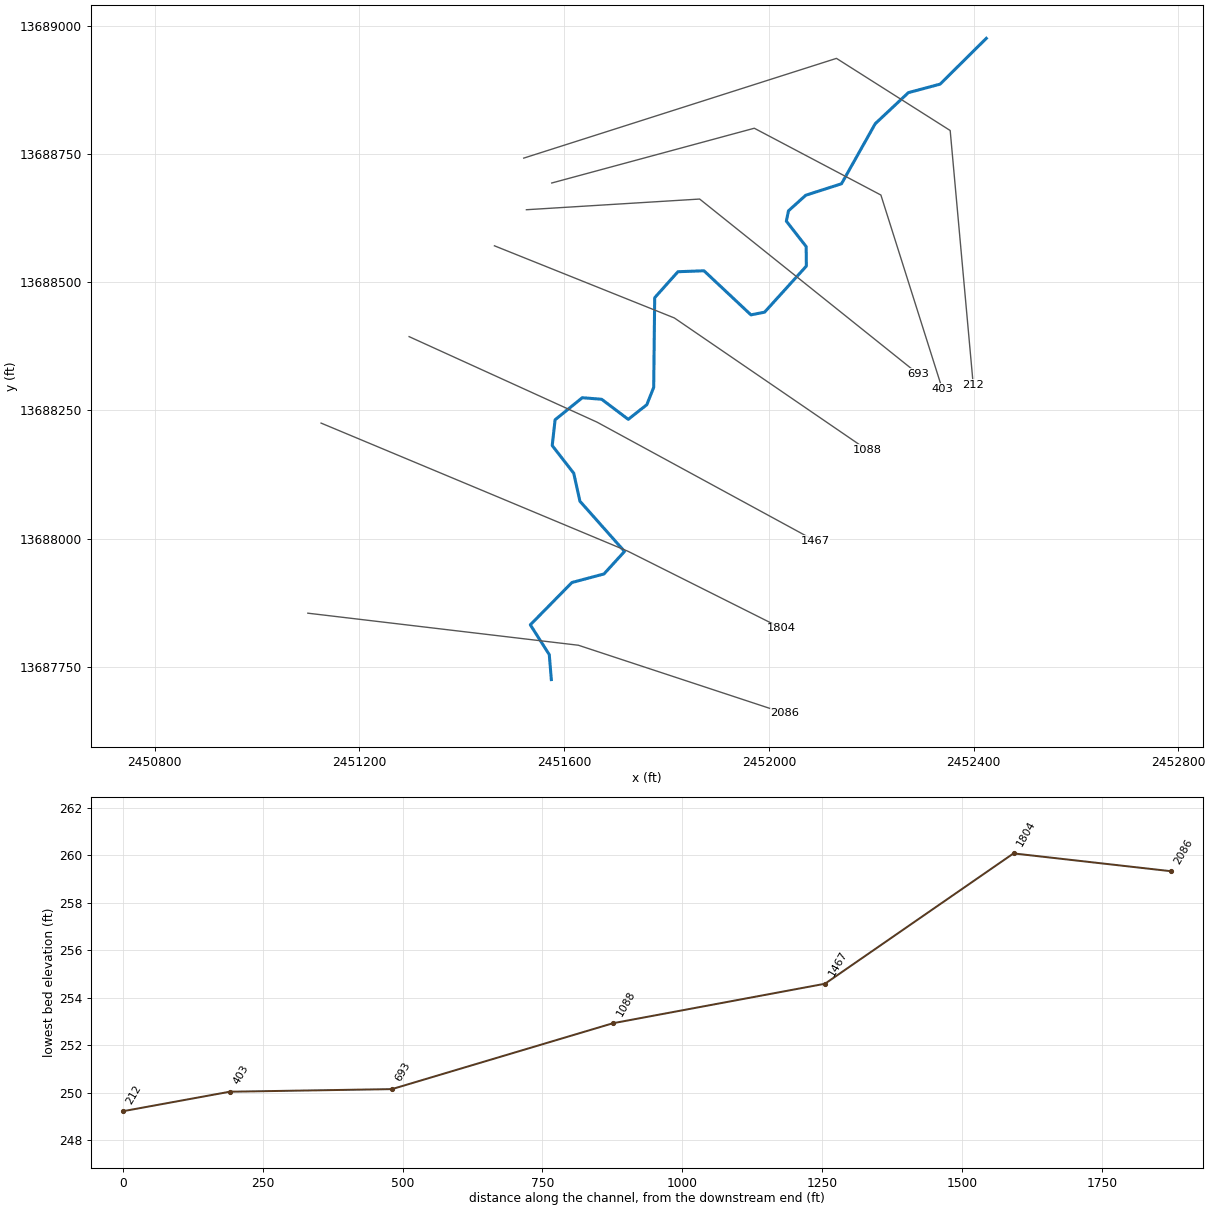
--- Stream0730.prj (project) ---

Proj Title=Stream0730 Base Level Engineering
Current Plan=p01
Default Exp/Contr=0.3,0.1
English Units
Geom File=g01
Flow File=f01
Plan File=p01
BEGIN DESCRIPTION:
Stream0730
END DESCRIPTION:

--- Stream0730.p01 (plan) ---

Plan Title=Multiple Run
Short Identifier=Multiple
Geom File=g01
Flow File=f01
Subcritical Flow
K Sum by GR= 0
Std Step Tol= 0.01
Critical Tol= 0.01
Num of Std Step Trials= 20
Max Error Tol= 0.3
Flow Tol Ratio= 0.001
Split Flow NTrial= 30
Split Flow Tol= 0.02
Split Flow Ratio= 0.02
Log Output Level= 0
Friction Slope Method= 1
Unsteady Friction Slope Method= 2
Unsteady Bridges Friction Slope Method= 1
Parabolic Critical Depth
Global Vel Dist=  1 , 1 , 1
Global Log Level= 0
CheckData=True
Encroach Param= -1, 0, 0, 0
BEGIN DESCRIPTION:
Multiple Run
END DESCRIPTION:

--- Stream0730.f01 (steady flow) ---

Flow Title=Multiple
Number of Profiles=7
Profile Names=10-year,25-year,50-year,1pct_min,100-year,1pct_plu,500-year
River Rch & RM= Stream0730,Reach-1,2086
     423     659     864     550    1098    2190    1750
Boundary for River Rch & Prof#=Stream0730,Reach-1,1
Up Type=0
Dn Type=3
Dn Slope=0.005
Boundary for River Rch & Prof#=Stream0730,Reach-1,2
Up Type=0
Dn Type=3
Dn Slope=0.005
Boundary for River Rch & Prof#=Stream0730,Reach-1,3
Up Type=0
Dn Type=3
Dn Slope=0.005
Boundary for River Rch & Prof#=Stream0730,Reach-1,4
Up Type=0
Dn Type=3
Dn Slope=0.005
Boundary for River Rch & Prof#=Stream0730,Reach-1,5
Up Type=0
Dn Type=3
Dn Slope=0.005
Boundary for River Rch & Prof#=Stream0730,Reach-1,6
Up Type=0
Dn Type=3
Dn Slope=0.005
Boundary for River Rch & Prof#=Stream0730,Reach-1,7
Up Type=0
Dn Type=3
Dn Slope=0.005

--- Stream0730.g01 (geometry) ---

Geom Title=Existing Conditions

River Reach=Stream0730,Reach-1
Reach XY= 30
      2451575.00     13687725.00      2451570.98     13687773.64
      2451533.97     13687831.73      2451615.31     13687914.22
      2451677.86     13687930.86      2451718.01     13687974.78
      2451630.86     13688072.70      2451618.82     13688127.19
      2451576.74     13688181.17      2451582.36     13688231.43
      2451635.45     13688274.42      2451673.33     13688271.42
      2451725.33     13688232.25      2451761.64     13688260.87
      2451775.04     13688294.76      2451776.98     13688469.38
      2451822.42     13688520.05      2451873.32     13688521.89
      2451965.02     13688435.97      2451991.71     13688441.18
      2452073.34     13688531.03      2452073.01     13688568.96
      2452034.27     13688618.60      2452038.40     13688638.73
      2452072.18     13688669.14      2452142.03     13688691.50
      2452207.92     13688808.57      2452272.69     13688869.16
      2452334.70     13688885.72      2452425.00     13688975.00

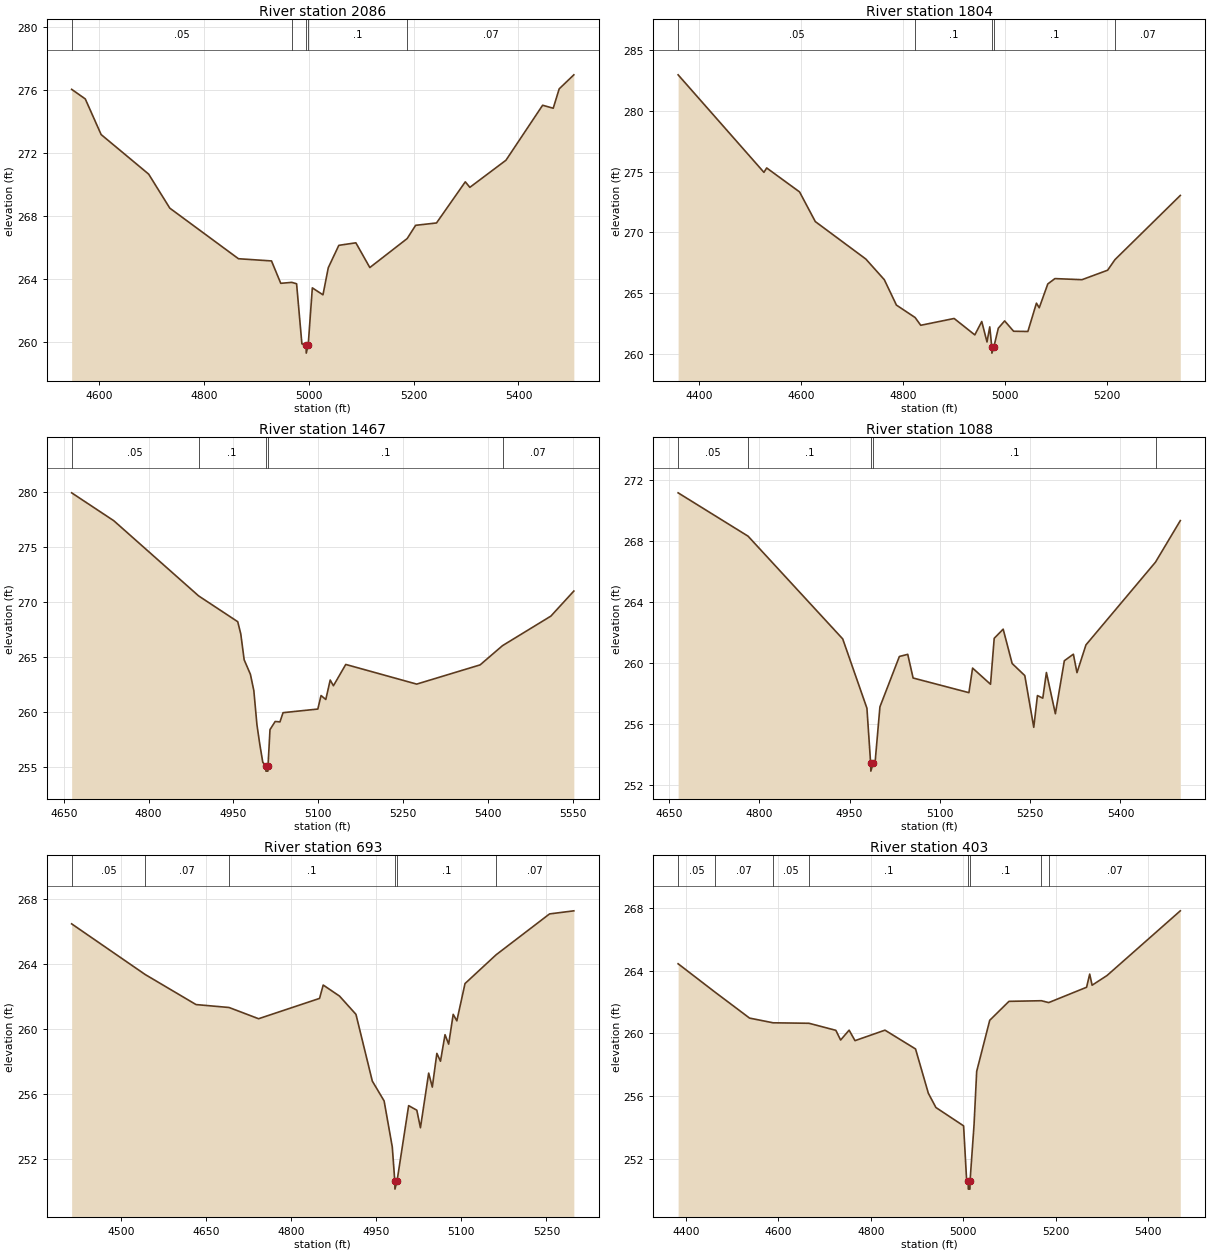
Type RM Length L Ch R = 1,2086,282,282,282
BEGIN DESCRIPTION:
XS7568
END DESCRIPTION:
XS GIS Cut Line= 3
      2451099.18     13687854.43      2451627.86     13687791.93
      2452031.51     13687659.11
#Sta/Elev= 30
  4548.3  276.06  4574.3  275.45  4604.5  273.19  4695.1  270.68  4735.4  268.52
  4866.3  265.31  4929.3  265.17  4946.9  263.75  4968.1  263.81  4977.1  263.72
  4987.2  259.91  4995.2  259.82  4995.5  259.32  4999.2  259.82  5007.1  263.46
  5027.4  263.02  5037.5  264.74  5057.6  266.16  5090.1  266.32  5116.7  264.75
  5187.9  266.59  5204.0  267.43  5243.8  267.58  5298.7  270.19  5307.4  269.84
  5376.2  271.56  5446.1  275.05  5466.3  274.86  5477.7  276.09  5505.6  276.98
#Mann=5,-1,0
  4548.3    0.05       0  4968.1     0.1       0  4995.2    0.05       0
  4999.2     0.1       0  5187.9    0.07       0
Bank Sta=4995.2,4999.2
Exp/Cntr=0.3,0.1

Type RM Length L Ch R = 1,1804,337,337,337
BEGIN DESCRIPTION:
Stream0730 3.0
END DESCRIPTION:
XS GIS Cut Line= 3
      2451125.05     13688224.98      2451725.00     13687975.00
      2452025.04     13687824.98
#Sta/Elev= 30
  4358.2  282.96  4526.6  274.94  4532.0  275.30  4596.5  273.33  4627.4  270.89
  4726.5  267.81  4762.8  266.11  4786.6  264.02  4823.2  263.00  4834.3  262.36
  4899.8  262.92  4940.4  261.57  4954.0  262.67  4964.3  260.99  4969.7  262.23
  4973.7  260.57  4973.9  260.07  4977.7  260.57  4986.5  262.12  4998.9  262.72
  5016.5  261.87  5044.5  261.85  5061.3  264.18  5066.8  263.80  5083.6  265.76
  5097.6  266.20  5150.7  266.11  5201.0  266.89  5215.4  267.76  5343.6  273.04
#Mann=5,-1,0
  4358.2    0.05       0  4823.2     0.1       0  4973.7    0.05       0
  4977.7     0.1       0  5215.4    0.07       0
Bank Sta=4973.7,4977.7
Exp/Cntr=0.3,0.1

Type RM Length L Ch R = 1,1467,379,379,379
BEGIN DESCRIPTION:
XS7567
END DESCRIPTION:
XS GIS Cut Line= 3
      2451297.11     13688393.50      2451664.32     13688226.82
      2452090.71     13687995.43
#Sta/Elev= 30
  4663.9  279.92  4738.5  277.38  4888.5  270.54  4957.7  268.19  4963.1  267.08
  4969.1  264.72  4980.1  263.41  4986.2  261.92  4991.7  258.81  4996.5  257.11
  5002.0  255.40  5007.3  255.09  5007.6  254.59  5011.1  254.59  5011.3  255.09
  5014.8  258.37  5024.0  259.11  5032.4  259.07  5037.9  259.91  5099.4  260.24
  5105.1  261.47  5113.5  261.11  5121.3  262.88  5127.0  262.36  5148.8  264.30
  5274.3  262.51  5386.5  264.26  5426.1  266.01  5511.7  268.70  5552.3  270.98
#Mann=5,-1,0
  4663.9    0.05       0  4888.5     0.1       0  5007.3    0.05       0
  5011.3     0.1       0  5426.1    0.07       0
Bank Sta=5007.3,5011.3
Exp/Cntr=0.3,0.1

Type RM Length L Ch R = 1,1088,395,395,395
BEGIN DESCRIPTION:
XS7566
END DESCRIPTION:
XS GIS Cut Line= 3
      2451463.81     13688570.57      2451815.36     13688429.95
      2452191.51     13688173.13
#Sta/Elev= 30
  4665.3  271.16  4781.5  268.32  4938.7  261.59  4978.9  257.05  4985.1  253.43
  4985.4  252.93  4989.1  253.43  4992.5  253.52  5000.5  257.14  5032.8  260.44
  5046.7  260.58  5055.6  259.03  5148.3  258.07  5154.4  259.68  5184.2  258.62
  5190.3  261.63  5205.2  262.23  5220.1  259.98  5241.1  259.19  5256.0  255.80
  5262.1  257.88  5271.0  257.71  5277.0  259.39  5291.9  256.69  5306.8  260.16
  5321.8  260.59  5327.8  259.38  5342.7  261.20  5458.2  266.62  5499.4  269.34
#Mann=5,-1,0
  4665.3    0.05       0  4781.5     0.1       0  4985.1    0.05       0
  4989.1     0.1       0  5458.2    0.07       0
Bank Sta=4985.1,4989.1
Exp/Cntr=0.3,0.1

Type RM Length L Ch R = 1,693,290,290,290
BEGIN DESCRIPTION:
XS7565
END DESCRIPTION:
XS GIS Cut Line= 3
      2451526.30     13688640.89      2451864.84     13688661.72
      2452290.99     13688321.32
#Sta/Elev= 30
  4413.6  266.46  4543.0  263.35  4632.7  261.50  4690.9  261.32  4742.9  260.63
  4850.3  261.88  4856.7  262.70  4885.5  262.02  4914.4  260.90  4943.2  256.80
  4964.0  255.58  4978.4  252.75  4982.8  250.66  4983.1  250.16  4986.8  250.66
  5007.2  255.29  5021.6  255.01  5028.0  253.93  5042.5  257.29  5048.9  256.43
  5056.9  258.50  5063.3  258.02  5071.3  259.65  5077.7  259.07  5085.7  260.90
  5092.1  260.50  5106.5  262.79  5161.3  264.56  5255.4  267.07  5298.2  267.26
#Mann=6,-1,0
  4413.6    0.05       0  4543.0    0.07       0  4690.9     0.1       0
  4982.8    0.05       0  4986.8     0.1       0  5161.3    0.07       0
Bank Sta=4982.8,4986.8
Exp/Cntr=0.3,0.1

Type RM Length L Ch R = 1,403,191,191,191
BEGIN DESCRIPTION:
XS7564
END DESCRIPTION:
XS GIS Cut Line= 4
      2451575.81     13688692.98      2451971.61     13688799.74
      2452219.01     13688669.53      2452338.81     13688291.90
#Sta/Elev= 30
  4383.5  264.44  4464.1  262.61  4538.0  260.97  4588.9  260.67  4666.4  260.64
  4724.5  260.19  4734.8  259.57  4753.2  260.20  4765.9  259.53  4830.7  260.20
  4896.8  259.00  4924.5  256.17  4940.9  255.26  5000.7  254.09  5007.0  250.74
  5010.6  250.55  5010.9  250.05  5014.4  250.05  5014.6  250.55  5023.3  254.17
  5029.0  257.57  5057.2  260.83  5098.8  262.04  5169.0  262.08  5184.6  261.96
  5266.6  262.94  5273.3  263.78  5278.5  263.07  5310.8  263.69  5469.2  267.82
#Mann=8,-1,0
  4383.5    0.05       0  4464.1    0.07       0  4588.9    0.05       0
  4666.4     0.1       0  5010.6    0.05       0  5014.6     0.1       0
  5169.0    0.12       0  5184.6    0.07       0
Bank Sta=5010.6,5014.6
Exp/Cntr=0.3,0.1

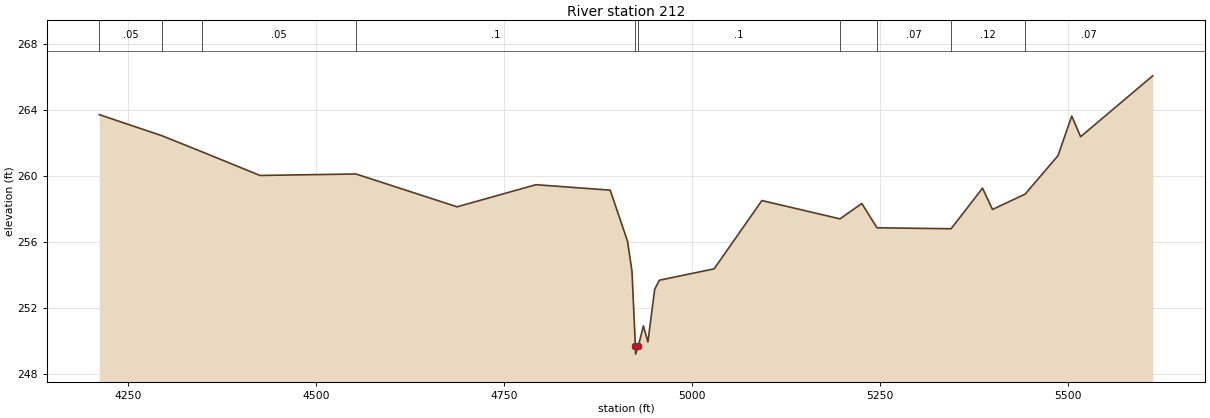
Type RM Length L Ch R = 1,212,0,0,0
BEGIN DESCRIPTION:
E21302
END DESCRIPTION:
XS GIS Cut Line= 4
      2451521.10     13688741.51      2452132.17     13688935.94
      2452354.39     13688795.31      2452399.47     13688299.39
#Sta/Elev= 30
  4211.2  263.75  4295.2  262.46  4348.2  261.49  4425.2  260.06  4552.9  260.15
  4687.5  258.16  4792.5  259.50  4891.3  259.17  4914.4  256.07  4920.3  254.25
  4924.8  249.73  4925.1  249.23  4928.8  249.73  4935.5  250.94  4941.5  249.97
  4950.5  253.16  4956.7  253.71  5029.6  254.40  5093.2  258.54  5197.1  257.43
  5226.2  258.36  5246.4  256.89  5345.0  256.83  5386.9  259.29  5400.1  258.00
  5443.6  258.93  5487.3  261.26  5505.6  263.66  5517.4  262.41  5613.4  266.10
#Mann=10,-1,0
  4211.2    0.05       0  4295.2    0.07       0  4348.2    0.05       0
  4552.9     0.1       0  4924.8    0.05       0  4928.8     0.1       0
  5197.1    0.12       0  5246.4    0.07       0  5345.0    0.12       0
  5443.6    0.07       0
Bank Sta=4924.8,4928.8
Exp/Cntr=0.3,0.1

Chan Stop Cuts=-1