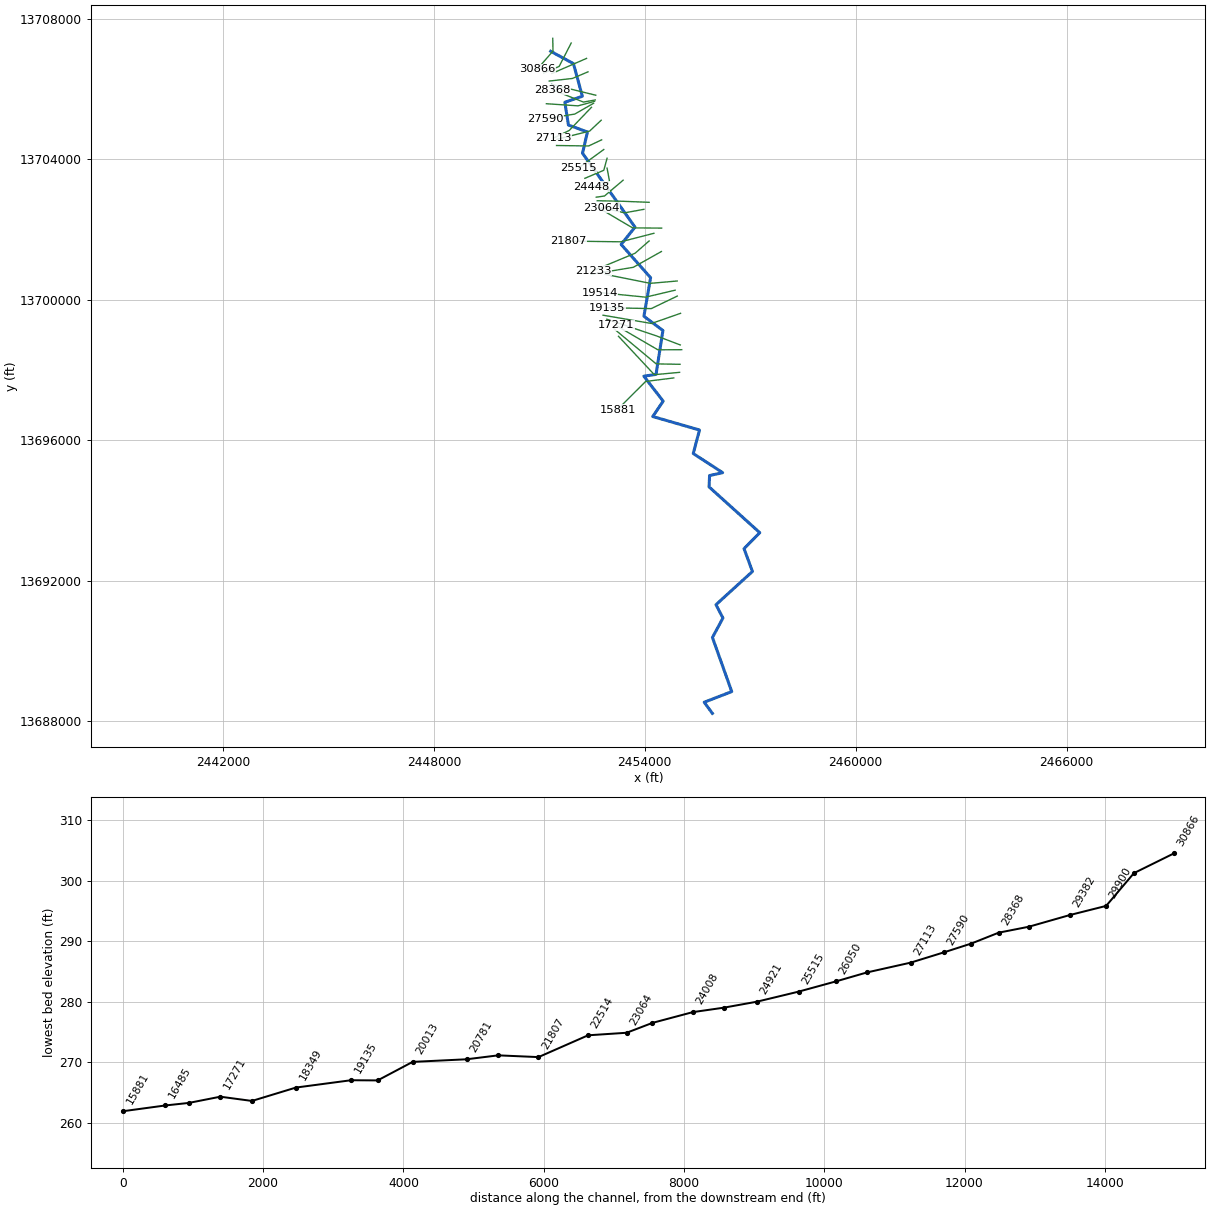
--- Stream0731.prj (project) ---

Proj Title=Stream0731 Base Level Engineering
Current Plan=p01
Default Exp/Contr=0.3,0.1
English Units
Geom File=g01
Flow File=f01
Plan File=p01
Y Axis Title=Elevation
X Axis Title(PF)=Main Channel Distance
X Axis Title(XS)=Station
BEGIN DESCRIPTION:
Stream0731
END DESCRIPTION:
DSS Export Rating Curves= 0
DSS Export Rating Curve Sorted= 0
DSS Export Volume Flow Curves= 0
DXF OffsetX= 0
DXF OffsetY= 0
DXF ScaleX= 1
DXF ScaleY= 10

--- Stream0731.p01 (plan) ---

Plan Title=Multiple Run
Short Identifier=Multiple
Geom File=g01
Flow File=f01
Subcritical Flow
K Sum by GR= 0
Std Step Tol= 0.01
Critical Tol= 0.01
Num of Std Step Trials= 20
Max Error Tol= 0.3
Flow Tol Ratio= 0.001
Split Flow NTrial= 30
Split Flow Tol= 0.02
Split Flow Ratio= 0.02
Log Output Level= 0
Friction Slope Method= 1
Unsteady Friction Slope Method= 2
Unsteady Bridges Friction Slope Method= 1
Parabolic Critical Depth
Global Vel Dist=  1 , 1 , 1
Global Log Level= 0
CheckData=True
Encroach Param= -1, 0, 0, 0
BEGIN DESCRIPTION:
Multiple Run
END DESCRIPTION:

--- Stream0731.f01 (steady flow) ---

Flow Title=Multiple
Number of Profiles=7
Profile Names=10-year,25-year,50-year,1pct_min,100-year,1pct_plu,500-year
River Rch & RM= Stream0731,Reach-1,30866
     617     983    1310     845    1687    3366    2769
River Rch & RM= Stream0731,Reach-1,23431
    1189    1966    2683    1769    3530    7044    6057
River Rch & RM= Stream0731,Reach-1,21807
    1465    2444    3356    2224    4438    8856    7696
River Rch & RM= Stream0731,Reach-1,20013
    1509    2509    3438    2273    4536    9050    7825
River Rch & RM= Stream0731,Reach-1,15881
    1795    2983    4085    2695    5378   10731    9242
River Rch & RM= Stream0731,Reach-1,8181
    1806    2995    4095    2698    5383   10740    9219
River Rch & RM= Stream0731,Reach-1,3650
    1939    3219    4403    2901    5788   11549    9915
Boundary for River Rch & Prof#=Stream0731,Reach-1,1
Up Type=0
Dn Type=3
Dn Slope=0.005
Boundary for River Rch & Prof#=Stream0731,Reach-1,2
Up Type=0
Dn Type=3
Dn Slope=0.005
Boundary for River Rch & Prof#=Stream0731,Reach-1,3
Up Type=0
Dn Type=3
Dn Slope=0.005
Boundary for River Rch & Prof#=Stream0731,Reach-1,4
Up Type=0
Dn Type=3
Dn Slope=0.005
Boundary for River Rch & Prof#=Stream0731,Reach-1,5
Up Type=0
Dn Type=3
Dn Slope=0.005
Boundary for River Rch & Prof#=Stream0731,Reach-1,6
Up Type=0
Dn Type=3
Dn Slope=0.005
Boundary for River Rch & Prof#=Stream0731,Reach-1,7
Up Type=0
Dn Type=3
Dn Slope=0.005

--- Stream0731.g01 (geometry) ---

Geom Title=Existing Conditions
Program Version=4.10

River Reach=Stream0731      ,Reach-1
Reach XY= 30
        2451325.       13707075.      2451971.64     13706723.75
      2452225.09     13705794.86      2451727.99      13705623.6
      2451828.45     13704976.48       2452369.6     13704777.43
      2452230.34     13704172.27      2453723.44     13702068.91
      2453328.53     13701576.45      2454167.21     13700628.43
      2453976.88     13699530.71       2454517.5       13699125.
      2454321.47     13697876.44        2453975.       13697825.
       2454524.3      13697114.3      2454228.04     13696676.42
      2455558.73     13696292.23      2455379.93     13695623.04
       2456217.5     13695078.17      2455844.44     13694995.76
      2455830.69     13694672.42      2457272.95     13693369.16
      2456825.53     13692914.55      2457064.05     13692264.98
      2456026.76     13691318.88      2456225.06     13690940.33
      2455926.22     13690385.51       2456475.4     13688845.12
      2455691.48     13688542.05        2455925.       13688225.

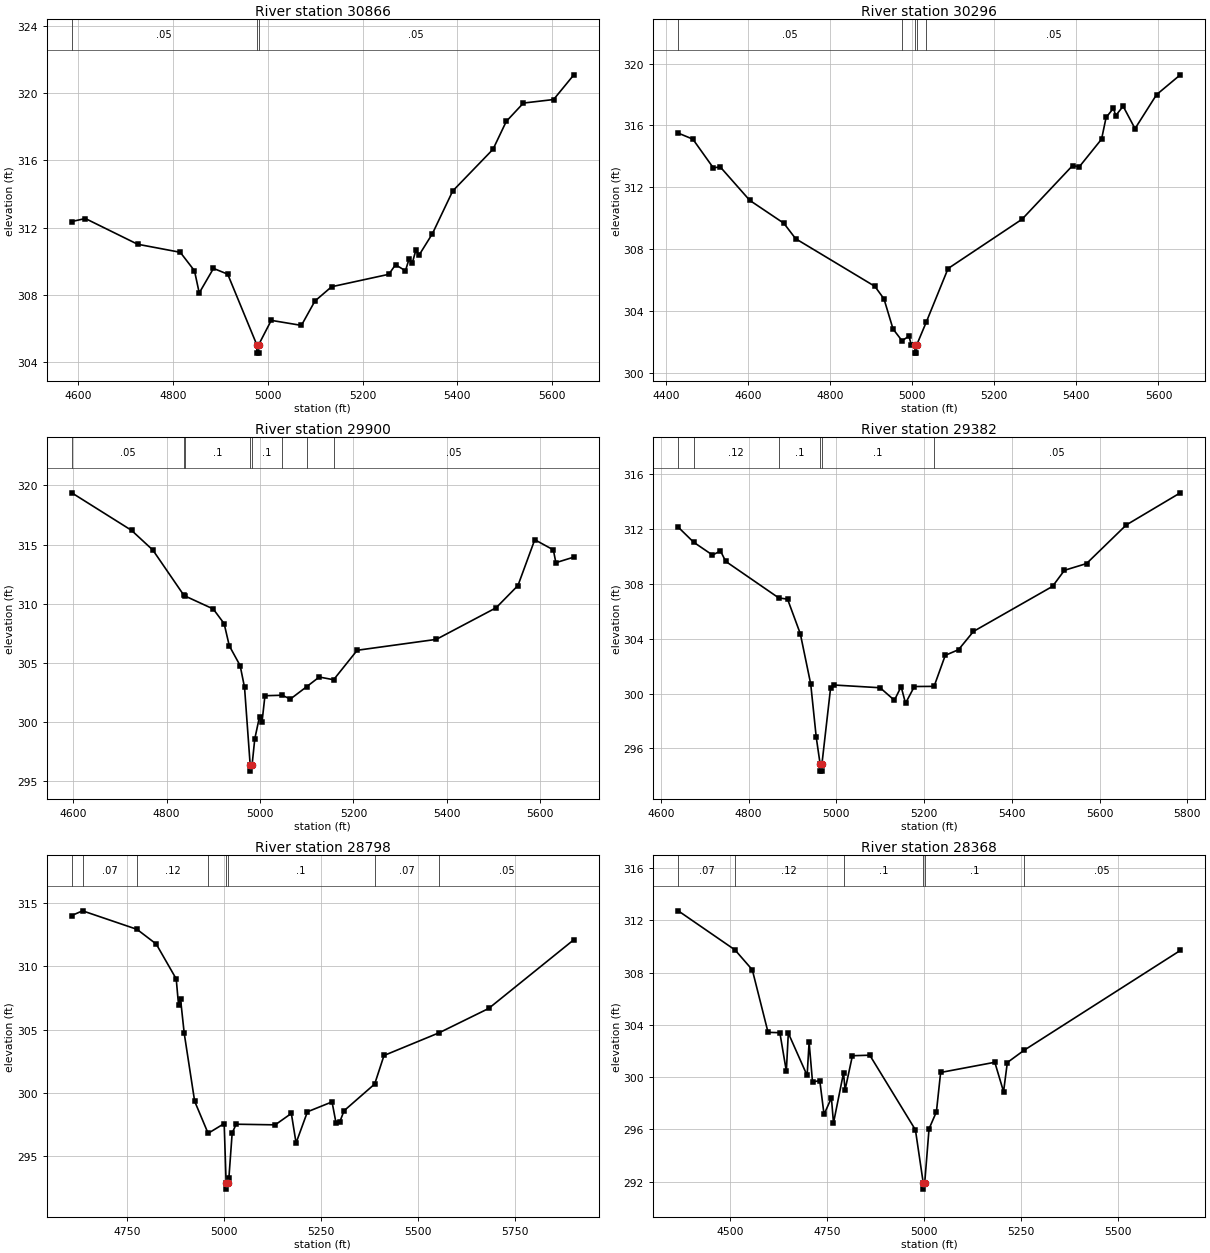
Type RM Length L Ch R = 1 ,30866   ,570,570,570
BEGIN DESCRIPTION:
XS7586
END DESCRIPTION:
XS GIS Cut Line= 3
      2451383.36     13707443.64      2451390.08     13707080.75
      2450933.08     13706556.54
#Sta/Elev= 30
    4587  312.36  4615.6  312.54  4725.7  311.01  4815.7  310.53  4845.7  309.43
  4855.7  308.11  4885.7  309.57  4915.7  309.23    4977  305.03  4977.2  304.53
  4980.7  304.53    4981  305.03  5007.5  306.48  5071.1  306.18  5099.6  307.63
  5134.7  308.48  5255.3  309.22  5269.5  309.79  5290.4  309.43    5298  310.13
  5304.6  309.87  5312.2  310.64  5318.9  310.35  5347.3  311.64  5390.1  314.18
    5475  316.66    5503  318.32  5539.1  319.41  5602.7  319.62  5645.4  321.09
#Mann= 3 ,-1 , 0
    4587     .05       0    4977     .05       0    4981     .05       0
Bank Sta=4977,4981
XS Rating Curve= 0 ,0
Exp/Cntr=0.3,0.1

Type RM Length L Ch R = 1 ,30296   ,396,396,396
BEGIN DESCRIPTION:
XS7585
END DESCRIPTION:
XS GIS Cut Line= 3
      2451907.53     13707309.22      2451564.81     13706643.94
      2451128.99      13706456.2
#Sta/Elev= 30
  4430.3   315.5  4465.9  315.11  4515.8  313.25  4532.4  313.32  4604.5  311.15
  4687.5  309.67  4716.3  308.67  4909.2  305.59  4931.4  304.78  4953.5  302.83
  4975.4  302.07  4992.3  302.37  4997.9   301.8  5006.7  301.77    5007  301.27
  5010.5  301.27  5010.7  301.77  5034.8   303.3  5087.5  306.74  5267.7  309.93
  5390.8   313.4  5407.1  313.32  5461.4  315.11  5472.4  316.51  5490.4  317.11
  5495.8  316.63  5513.9  317.24  5542.9  315.79  5595.4  317.99  5653.2  319.27
#Mann= 5 ,-1 , 0
  4430.3     .05       0  4975.4     .07       0  5006.7     .05       0
  5010.7     .07       0  5034.8     .05       0
Bank Sta=5006.7,5010.7
XS Rating Curve= 0 ,0
Exp/Cntr=0.3,0.1

Type RM Length L Ch R = 1 ,29900   ,518,518,518
BEGIN DESCRIPTION:
XS7584
END DESCRIPTION:
XS GIS Cut Line= 2
      2452344.37     13706872.43      2451358.28     13706443.11
#Sta/Elev= 30
  4596.7  319.37  4724.7   316.2  4770.5  314.53  4836.9  310.71  4839.5  310.65
  4899.7  309.56  4923.1  308.32  4934.1  306.45  4957.4  304.77  4966.8  302.93
  4978.9  296.36  4979.1  295.86  4982.9  296.36  4988.7  298.58  4998.9  300.47
  5004.3  300.03  5010.5  302.23  5047.3  302.27    5065  301.95  5099.8  302.99
  5126.9  303.81  5157.6  303.58  5208.1  306.07  5377.6  306.99  5505.7  309.66
  5552.5  311.54  5588.5  315.41  5628.3  314.55  5633.7  313.47  5672.2  313.94
#Mann= 8 ,-1 , 0
  4596.7     .05       0  4836.9     .07       0  4839.5      .1       0
  4978.9     .05       0  4982.9      .1       0  5047.3     .05       0
  5099.8     .07       0  5157.6     .05       0
Bank Sta=4978.9,4982.9
XS Rating Curve= 0 ,0
Exp/Cntr=0.3,0.1

Type RM Length L Ch R = 1 ,29382   ,584,584,584
BEGIN DESCRIPTION:
XS7583
END DESCRIPTION:
XS GIS Cut Line= 3
      2452384.64     13706489.35      2451941.14      13706301.2
      2451282.53     13706227.28
#Sta/Elev= 30
  4639.7  312.11  4674.6  311.02  4717.8  310.08    4736  310.38  4747.9  309.62
  4868.8  306.96  4888.9  306.87    4918  304.35  4941.7  300.69  4954.3  296.81
  4963.2  294.85  4963.4  294.35  4966.9  294.35  4967.2  294.85  4986.9  300.38
  4994.4  300.62  5099.9  300.42  5132.4  299.51  5147.8   300.5  5157.8  299.29
    5178  300.51  5222.9  300.52  5248.4  302.78  5278.6  303.19  5312.7  304.52
  5492.9   307.8  5520.1  308.97  5570.4  309.46    5661  312.27  5784.2  314.61
#Mann= 6 ,-1 , 0
  4639.7     .07       0  4674.6     .12       0  4868.8      .1       0
  4963.2     .05       0  4967.2      .1       0  5222.9     .05       0
Bank Sta=4963.2,4967.2
XS Rating Curve= 0 ,0
Exp/Cntr=0.3,0.1

Type RM Length L Ch R = 1 ,28798   ,430,430,430
BEGIN DESCRIPTION:
XS7582
END DESCRIPTION:
XS GIS Cut Line= 2
      2452606.41     13705824.07      2451349.87     13706133.17
#Sta/Elev= 30
  4607.6     314  4635.4  314.37  4775.7  312.91  4825.3  311.75  4876.8     309
  4882.8  306.94  4887.9  307.42  4897.4  304.71  4924.3  299.35    4959  296.82
  5000.4  297.59  5005.4  292.92  5005.6  292.42  5009.4  292.92  5012.5  293.27
    5021  296.85  5031.3  297.54  5131.9  297.49  5173.5  298.39  5185.7  296.06
    5215  298.52  5278.4   299.3  5288.7  297.63  5298.1   297.7  5309.3   298.6
  5388.3  300.71  5412.3  302.96    5555  304.76  5682.1  306.67  5901.6  312.09
#Mann= 8 ,-1 , 0
  4607.6     .05       0  4635.4     .07       0  4775.7     .12       0
    4959      .1       0  5005.4     .05       0  5009.4      .1       0
  5388.3     .07       0    5555     .05       0
Bank Sta=5005.4,5009.4
XS Rating Curve= 0 ,0
Exp/Cntr=0.3,0.1

Type RM Length L Ch R = 1 ,28368   ,391,391,391
BEGIN DESCRIPTION:
XS7581
END DESCRIPTION:
XS GIS Cut Line= 3
      2452592.98     13705689.65        2452257.     13705629.17
      2451369.93     13705978.62
#Sta/Elev= 30
    4367  312.72  4513.4  309.73    4558  308.21  4598.6  303.43  4629.1   303.4
  4645.8  300.46  4650.9  303.37  4699.4  300.13  4704.5  302.67  4713.3  299.63
    4732  299.74    4743  297.15    4762  298.42  4767.4   296.5  4793.3  300.33
  4797.2  299.02  4816.2  301.64    4861  301.68  4978.7  295.97  4998.7  291.94
    4999  291.44  5002.7  291.94  5013.8  296.05  5032.8  297.35  5043.7  300.36
  5183.4  301.14    5206  298.89  5215.7  301.12  5258.5  302.05  5661.8  309.69
#Mann= 6 ,-1 , 0
    4367     .07       0  4513.4     .12       0  4793.3      .1       0
  4998.7     .05       0  5002.7      .1       0  5258.5     .05       0
Bank Sta=4998.7,5002.7
XS Rating Curve= 0 ,0
Exp/Cntr=0.3,0.1

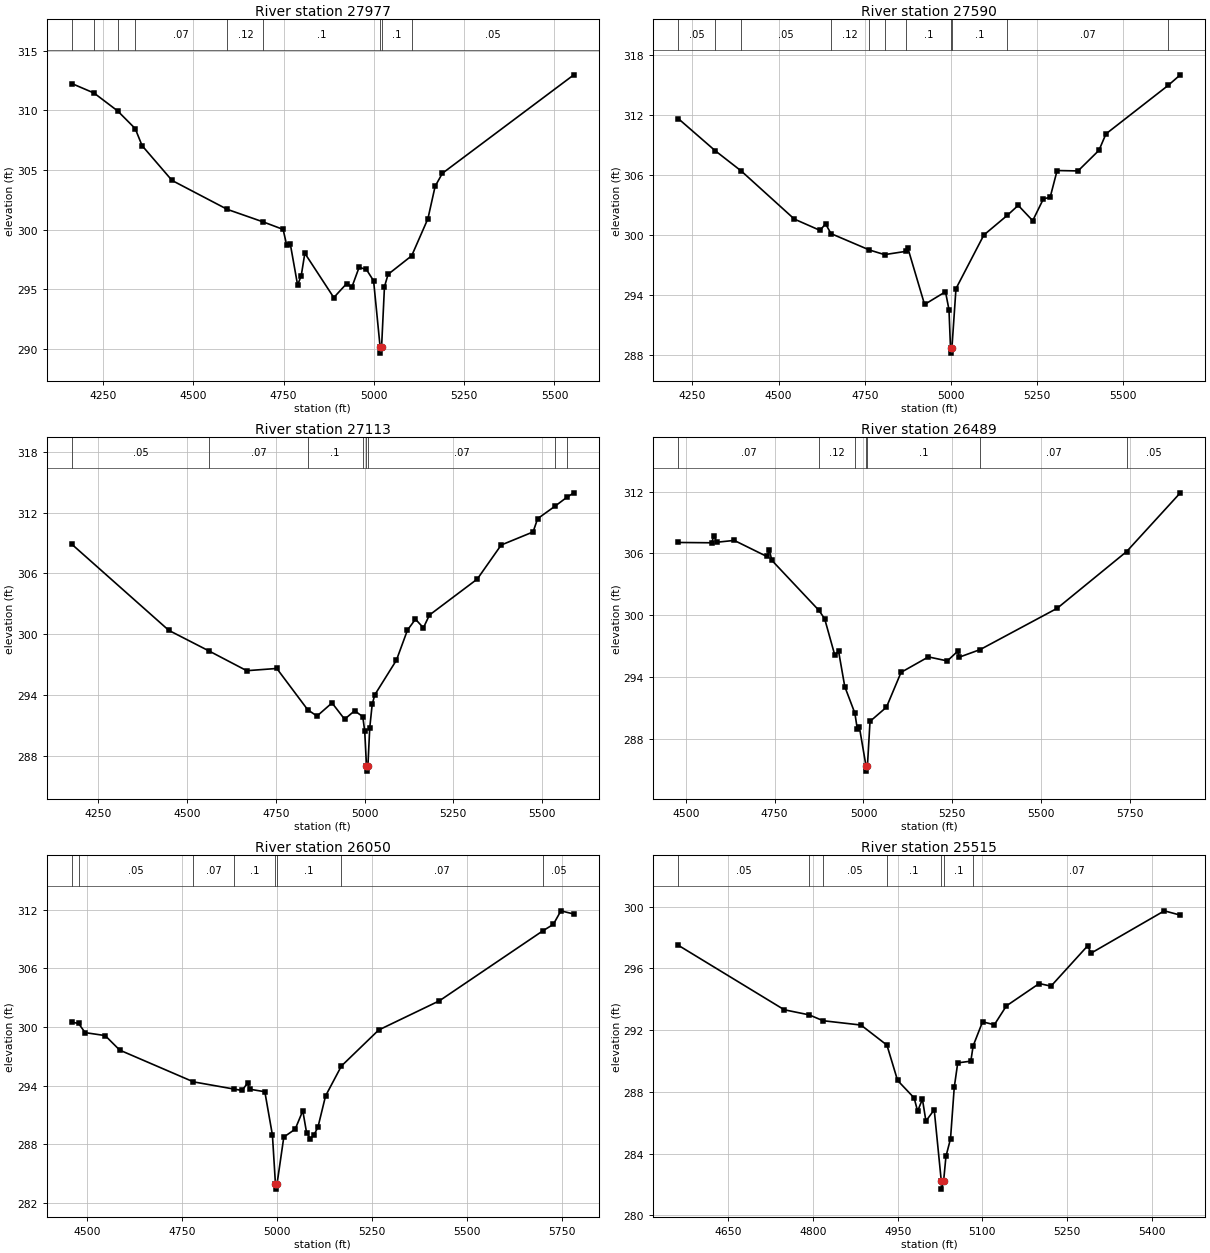
Type RM Length L Ch R = 1 ,27977   ,387,387,387
BEGIN DESCRIPTION:
XS7580
END DESCRIPTION:
XS GIS Cut Line= 3
      2452572.84     13705649.33      2452102.43     13705521.65
      2451201.88     13705582.13
#Sta/Elev= 30
  4163.6  312.26  4225.3  311.46  4290.6  309.96  4339.2  308.48  4358.2  307.05
  4441.1  304.13  4594.3   301.7  4694.4  300.64  4748.7  300.02  4758.7  298.69
  4768.7  298.78  4788.8  295.36  4798.8  296.12  4808.8  298.02    4889   294.3
  4924.5  295.47  4939.1  295.18  4959.1  296.84  4979.2  296.66  4999.2  295.71
  5017.3  290.14  5017.5  289.64  5021.3  290.14  5029.3  295.21  5039.3  296.25
  5104.7  297.81  5149.6  300.92  5169.6  303.64  5189.7  304.73  5553.6  312.99
#Mann= 9 ,-1 , 0
  4163.6     .05       0  4225.3     .07       0  4290.6     .12       0
  4339.2     .07       0  4594.3     .12       0  4694.4      .1       0
  5017.3     .05       0  5021.3      .1       0  5104.7     .05       0
Bank Sta=5017.3,5021.3
XS Rating Curve= 0 ,0
Exp/Cntr=0.3,0.1

Type RM Length L Ch R = 1 ,27590   ,477,477,477
BEGIN DESCRIPTION:
XS7579
END DESCRIPTION:
XS GIS Cut Line= 3
      2452545.94     13705595.56      2452008.35     13705286.44
      2451181.78     13705158.76
#Sta/Elev= 30
    4209  311.63  4316.9   308.4  4391.9  306.39  4545.8  301.59  4620.5  300.46
  4636.3  301.12  4652.1  300.14  4763.8   298.5  4807.6  298.04  4870.3  298.37
  4874.7  298.74  4923.6  293.06  4984.3  294.33  4994.4  292.55  4998.9   288.7
  4999.1   288.2  5002.9   288.7  5014.7  294.64  5095.6     300  5163.8  301.97
  5195.3  302.96  5237.3  301.43  5268.5  303.62  5287.9  303.76  5308.1  306.44
  5368.8   306.4  5429.5  308.46  5449.8   310.1  5630.1  314.94  5665.5     316
#Mann= 11 ,-1 , 0
    4209     .05       0  4316.9     .07       0  4391.9     .05       0
  4652.1     .12       0  4763.8      .1       0  4807.6     .12       0
  4870.3      .1       0  4998.9     .05       0  5002.9      .1       0
  5163.8     .07       0  5630.1     .05       0
Bank Sta=4998.9,5002.9
XS Rating Curve= 0 ,0
Exp/Cntr=0.3,0.1

Type RM Length L Ch R = 1 ,27113   ,624,624,624
BEGIN DESCRIPTION:
XS7578
END DESCRIPTION:
XS GIS Cut Line= 3
      2452485.47     13705481.31      2451853.78     13704822.74
      2451403.49     13704600.96
#Sta/Elev= 30
    4175  308.88  4448.4  300.38    4562  298.34  4667.9   296.4  4752.6  296.62
  4839.6  292.55  4865.8  291.92  4908.2  293.22  4943.7  291.61    4972  292.45
  4994.8  291.86  5000.3  290.46  5005.3  286.99  5005.5  286.49  5009.3  286.99
  5014.5  290.77  5021.4  293.08  5028.7  294.02  5089.7  297.44  5120.8  300.41
  5143.3  301.48  5165.7  300.63  5182.6  301.89  5317.4  305.44  5384.8   308.8
  5474.6  310.09  5487.5   311.4  5536.4  312.63  5570.2  313.52  5589.5  313.95
#Mann= 8 ,-1 , 0
    4175     .05       0    4562     .07       0  4839.6      .1       0
  4994.8     .07       0  5005.3     .05       0  5009.3     .07       0
  5536.4     .05       0  5570.2     .07       0
Bank Sta=5005.3,5009.3
XS Rating Curve= 0 ,0
Exp/Cntr=0.3,0.1

Type RM Length L Ch R = 1 ,26489   ,439,439,439
BEGIN DESCRIPTION:
XS7577
END DESCRIPTION:
XS GIS Cut Line= 3
      2452760.99     13705111.69      2452431.72     13704802.58
      2451498.77     13704567.66
#Sta/Elev= 30
  4478.5  307.07  4572.2  307.04  4579.6  307.73  4586.4  307.09  4636.2  307.27
    4728  305.71  4734.9  306.32  4742.2  305.33  4874.3  300.49  4890.7  299.67
    4919  296.17  4930.1  296.49  4947.4  293.08  4975.9  290.49  4982.6  288.97
  4988.6  289.13  5007.2  285.37  5007.5  284.87  5011.2  285.37  5018.5   289.7
  5064.8  291.08  5105.9  294.46  5182.9  295.96  5236.1  295.57  5265.1   296.5
  5270.3  295.94  5328.6  296.67  5545.5  300.68  5741.1  306.19  5892.2  311.89
#Mann= 7 ,-1 , 0
  4478.5     .07       0  4874.3     .12       0  4975.9      .1       0
  5007.2     .05       0  5011.2      .1       0  5328.6     .07       0
  5741.1     .05       0
Bank Sta=5007.2,5011.2
XS Rating Curve= 0 ,0
Exp/Cntr=0.3,0.1

Type RM Length L Ch R = 1 ,26050   ,535,535,535
BEGIN DESCRIPTION:
XS7576
END DESCRIPTION:
XS GIS Cut Line= 3
      2452774.44     13704553.92      2452404.84      13704379.2
      2451490.86     13704392.64
#Sta/Elev= 30
  4459.1  300.49  4476.9  300.36  4494.4  299.42    4547  299.12  4585.5  297.63
  4779.8  294.38  4885.6  293.65  4907.8   293.5  4922.5  294.27  4927.8  293.63
  4967.8  293.37  4987.8  288.93  4995.8   283.9    4996   283.4  4999.8   283.9
  5017.8  288.73  5047.8  289.54  5067.8  291.42  5077.8  289.18  5087.8  288.56
  5097.8  288.99  5107.8  289.75  5127.8  292.94  5169.5     296  5267.8  299.69
  5427.8  302.68    5701  309.86  5727.9   310.5  5747.9  311.89    5782  311.56
#Mann= 8 ,-1 , 0
  4459.1     .07       0  4476.9     .05       0  4779.8     .07       0
  4885.6      .1       0  4995.8     .05       0  4999.8      .1       0
  5169.5     .07       0    5701     .05       0
Bank Sta=4995.8,4999.8
XS Rating Curve= 0 ,0
Exp/Cntr=0.3,0.1

Type RM Length L Ch R = 1 ,25515   ,594,594,594
BEGIN DESCRIPTION:
XS7575
END DESCRIPTION:
XS GIS Cut Line= 2
      2452834.98     13704278.42      2452115.87     13703754.21
#Sta/Elev= 30
    4561   297.5  4748.9  293.32    4793  292.99  4817.8  292.61  4884.9  292.33
  4930.9  291.03  4949.8  288.74  4979.1  287.61  4985.3  286.75  4993.8  287.53
    5000  286.11  5014.7  286.84  5027.3   282.2  5027.6   281.7  5031.3   282.2
  5035.5  283.82  5043.6  284.96  5050.2  288.29  5056.4  289.88  5079.6  289.99
  5083.7  290.98  5100.4  292.54  5121.3  292.35  5142.6  293.57  5200.8  295.02
  5221.7  294.85  5286.6  297.46  5292.8  296.99  5422.6  299.73  5450.9  299.45
#Mann= 7 ,-1 , 0
    4561     .05       0    4793     .07       0  4817.8     .05       0
  4930.9      .1       0  5027.3     .05       0  5031.3      .1       0
  5083.7     .07       0
Bank Sta=5027.3,5031.3
XS Rating Curve= 0 ,0
Exp/Cntr=0.3,0.1

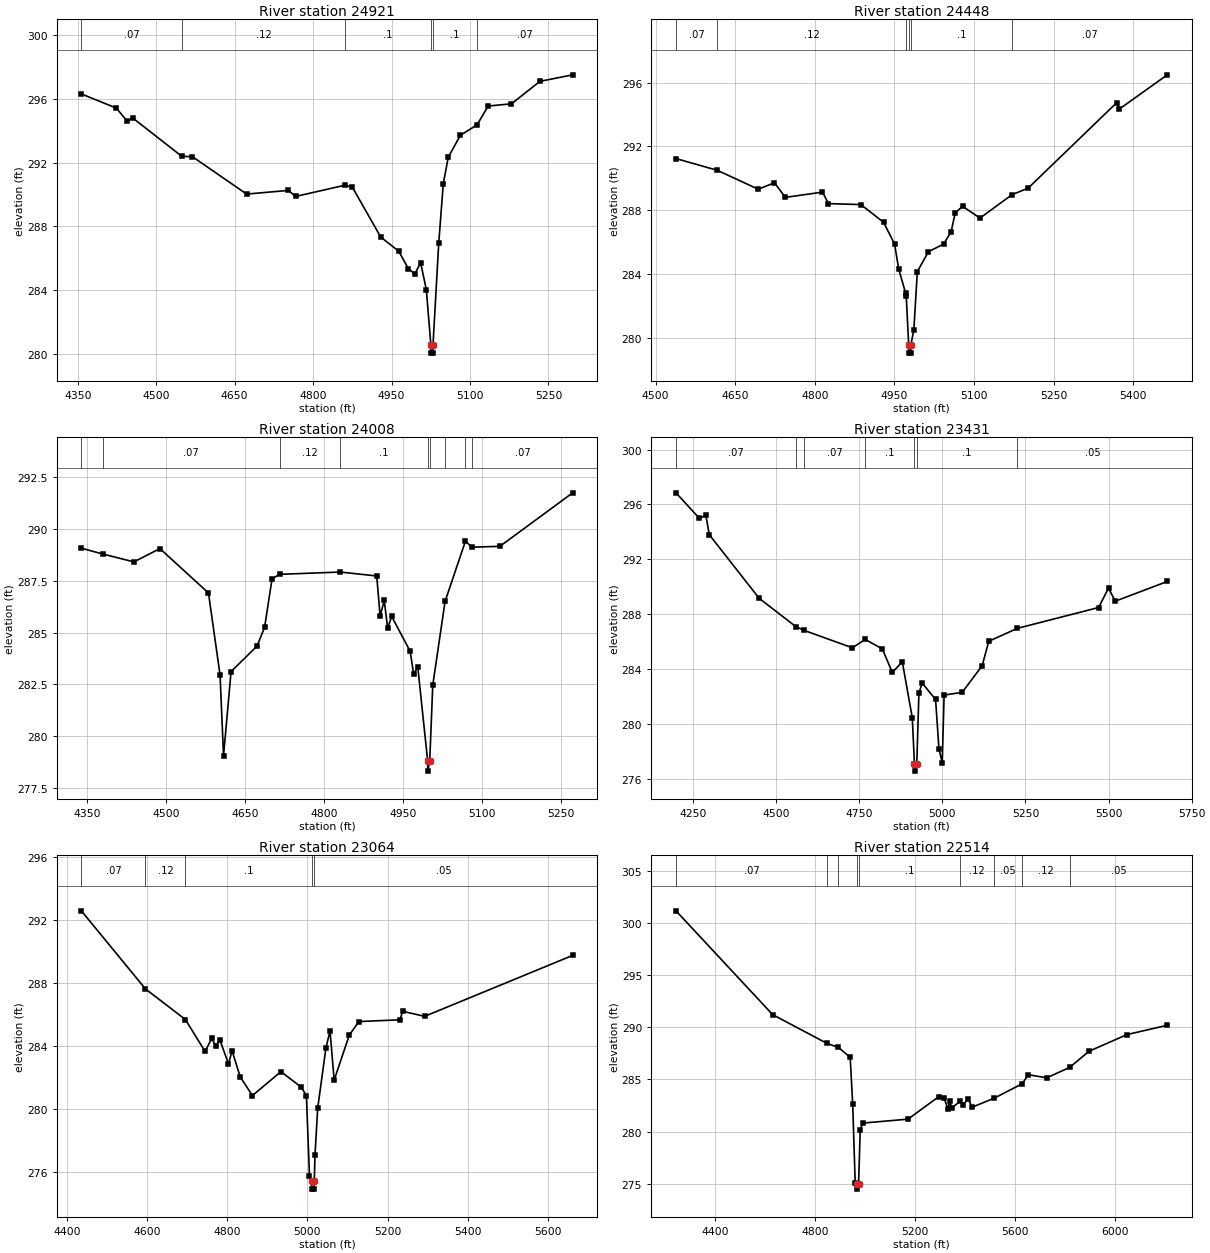
Type RM Length L Ch R = 1 ,24921   ,473,473,473
BEGIN DESCRIPTION:
XS7574
END DESCRIPTION:
XS GIS Cut Line= 3
      2452929.01      13704029.7      2452834.94     13703687.01
      2452297.34     13703458.53
#Sta/Elev= 30
  4356.9  296.32  4423.8  295.43  4444.7   294.6  4455.1  294.81    4549   292.4
  4569.2  292.38  4672.9  290.03    4753  290.26  4766.5  289.88  4861.4  290.59
  4875.2  290.46  4929.4  287.33  4963.9  286.44  4982.1  285.35  4994.7  285.01
  5005.6  285.73  5016.6  284.02  5025.3  280.54  5025.6  280.04  5029.1  280.04
  5029.3  280.54  5040.3  286.95    5049  290.69  5058.5  292.34  5081.6  293.72
  5113.6  294.38  5134.9  295.56  5179.4   295.7  5233.8  297.11  5296.4  297.52
#Mann= 6 ,-1 , 0
  4356.9     .07       0    4549     .12       0  4861.4      .1       0
  5025.3     .05       0  5029.3      .1       0  5113.6     .07       0
Bank Sta=5025.3,5029.3
XS Rating Curve= 0 ,0
Exp/Cntr=0.3,0.1

Type RM Length L Ch R = 1 ,24448   ,440,440,440
BEGIN DESCRIPTION:
XS7573
END DESCRIPTION:
XS GIS Cut Line= 4
      2452929.02      13703747.5      2452996.23      13703384.6
      2452861.82     13703270.36      2452485.51      13703216.6
#Sta/Elev= 30
  4538.5  291.24  4616.1  290.51  4693.6  289.32  4724.1  289.73  4744.4  288.81
  4814.5  289.14  4825.8  288.42  4886.8  288.36  4929.5  287.25  4950.3  285.89
  4958.1  284.32  4971.3  282.79  4972.3  282.63  4976.9  279.55  4977.1  279.05
  4980.6  279.05  4980.9  279.55  4986.6   280.5  4993.2  284.16  5014.2  285.41
  5042.6  285.88  5056.9  286.66  5064.6  287.85  5078.6  288.25  5111.1  287.51
  5171.6  288.98    5202  289.39    5369  294.75    5374  294.35  5464.1  296.49
#Mann= 6 ,-1 , 0
  4538.5     .07       0  4616.1     .12       0  4971.3      .1       0
  4976.9     .05       0  4980.9      .1       0  5171.6     .07       0
Bank Sta=4976.9,4980.9
XS Rating Curve= 0 ,0
Exp/Cntr=0.3,0.1

Type RM Length L Ch R = 1 ,24008   ,577,577,577
BEGIN DESCRIPTION:
Stream0731 39.0
END DESCRIPTION:
XS GIS Cut Line= 3
      2453386.02     13703404.77       2452855.1      13702954.5
      2452619.93     13702920.91
#Sta/Elev= 30
  4338.9  289.07  4379.4  288.79  4438.8  288.41  4488.2  289.05  4580.5  286.91
  4602.5  282.95  4609.1  279.06  4623.4  283.12  4672.8  284.35  4687.1  285.25
  4701.3  287.59  4715.6  287.81  4831.1  287.92  4900.2  287.73  4906.7   285.8
  4914.5  286.55    4921  285.22  4928.7  285.78  4963.9  284.09  4970.4  282.99
  4978.2  283.35    4997  278.82  4997.3  278.32    5001  278.82  5006.7  282.46
  5030.1   286.5  5068.8  289.41  5081.3  289.12  5134.3  289.16  5272.6  291.74
#Mann= 9 ,-1 , 0
  4338.9     .12       0  4379.4     .07       0  4715.6     .12       0
  4831.1      .1       0    4997     .05       0    5001      .1       0
  5030.1     .07       0  5068.8     .05       0  5081.3     .07       0
Bank Sta=4997,5001
XS Rating Curve= 0 ,0
Exp/Cntr=0.3,0.1

Type RM Length L Ch R = 1 ,23431   ,367,367,367
BEGIN DESCRIPTION:
Stream0731 38.0
END DESCRIPTION:
XS GIS Cut Line= 3
      2454124.97       13702775.       2453318.8     13702806.66
      2452648.42     13702820.06
#Sta/Elev= 30
  4199.4  296.85  4269.4     295  4289.4   295.2  4299.4   293.8  4449.6  289.15
  4559.6  287.09  4583.7  286.82  4729.8  285.54  4768.3  286.15  4819.8  285.46
  4849.9  283.74  4879.9  284.52  4909.9  280.44  4916.5  277.04    4917  276.54
  4923.4  277.04  4929.9  282.25  4939.9  282.96    4980  281.77    4990  278.19
    5000  277.14  5005.6  282.09    5060  282.29    5120  284.23    5140  286.02
    5226  286.96  5470.1  288.48  5500.1   289.9  5520.1  288.94  5676.7  290.38
#Mann= 7 ,-1 , 0
  4199.4     .07       0  4559.6      .1       0  4583.7     .07       0
  4768.3      .1       0  4916.5     .05       0  4923.4      .1       0
    5226     .05       0
Bank Sta=4916.5,4923.4
XS Rating Curve= 0 ,0
Exp/Cntr=0.3,0.1

Type RM Length L Ch R = 1 ,23064   ,550,550,550
BEGIN DESCRIPTION:
Stream0731 37.0
END DESCRIPTION:
XS GIS Cut Line= 3
      2453975.04     13702575.01        2453425.       13702475.
      2452775.04     13702624.99
#Sta/Elev= 30
  4435.9  292.58  4595.9  287.62  4695.5  285.68  4744.7  283.65  4761.2  284.48
  4771.4  283.99  4781.5  284.39  4803.1  282.86    4812   283.7  4832.3  282.04
  4862.8  280.85    4934  282.37  4984.8  281.38  4997.5  280.85  5005.2  275.74
  5010.3  275.41  5010.8  274.91  5016.7  274.91  5017.2  275.41  5018.9  277.05
  5025.7  280.05  5046.3  283.88  5056.5  284.95  5066.8  281.83  5104.4  284.68
  5128.4  285.55    5231  285.66  5237.8   286.2  5292.6  285.88    5662  289.75
#Mann= 5 ,-1 , 0
  4435.9     .07       0  4595.9     .12       0  4695.5      .1       0
  5010.3     .05       0  5017.2     .05       0
Bank Sta=5010.3,5017.2
XS Rating Curve= 0 ,0
Exp/Cntr=0.3,0.1

Type RM Length L Ch R = 1 ,22514   ,707,707,707
BEGIN DESCRIPTION:
Stream0731 36.0
END DESCRIPTION:
XS GIS Cut Line= 3
      2454481.43     13702040.54      2453654.82     13702047.26
      2452675.01       13702625.
#Sta/Elev= 30
  4244.1  301.17  4630.5  291.22  4846.9  288.47  4893.7  288.07  4940.6  287.12
  4950.6  282.61  4960.6  275.07    4967  274.99  4967.5  274.49  4974.1  274.99
  4980.6  280.15  4990.6  280.82  5171.9   281.2  5294.8  283.36  5316.3  283.18
  5331.9  282.17  5337.7  282.91  5347.6  282.27  5380.4  282.94  5390.5  282.52
  5411.9  283.17  5427.6  282.34  5515.3   283.2  5629.1   284.6  5651.9  285.46
  5726.1  285.16  5818.1  286.16  5894.8   287.7  6046.2   289.3  6208.2   290.2
#Mann= 9 ,-1 , 0
  4244.1     .07       0  4846.9     .12       0  4893.7      .1       0
    4967     .05       0  4974.1      .1       0  5380.4     .12       0
  5515.3     .05       0  5629.1     .12       0  5818.1     .05       0
Bank Sta=4967,4974.1
XS Rating Curve= 0 ,0
Exp/Cntr=0.3,0.1

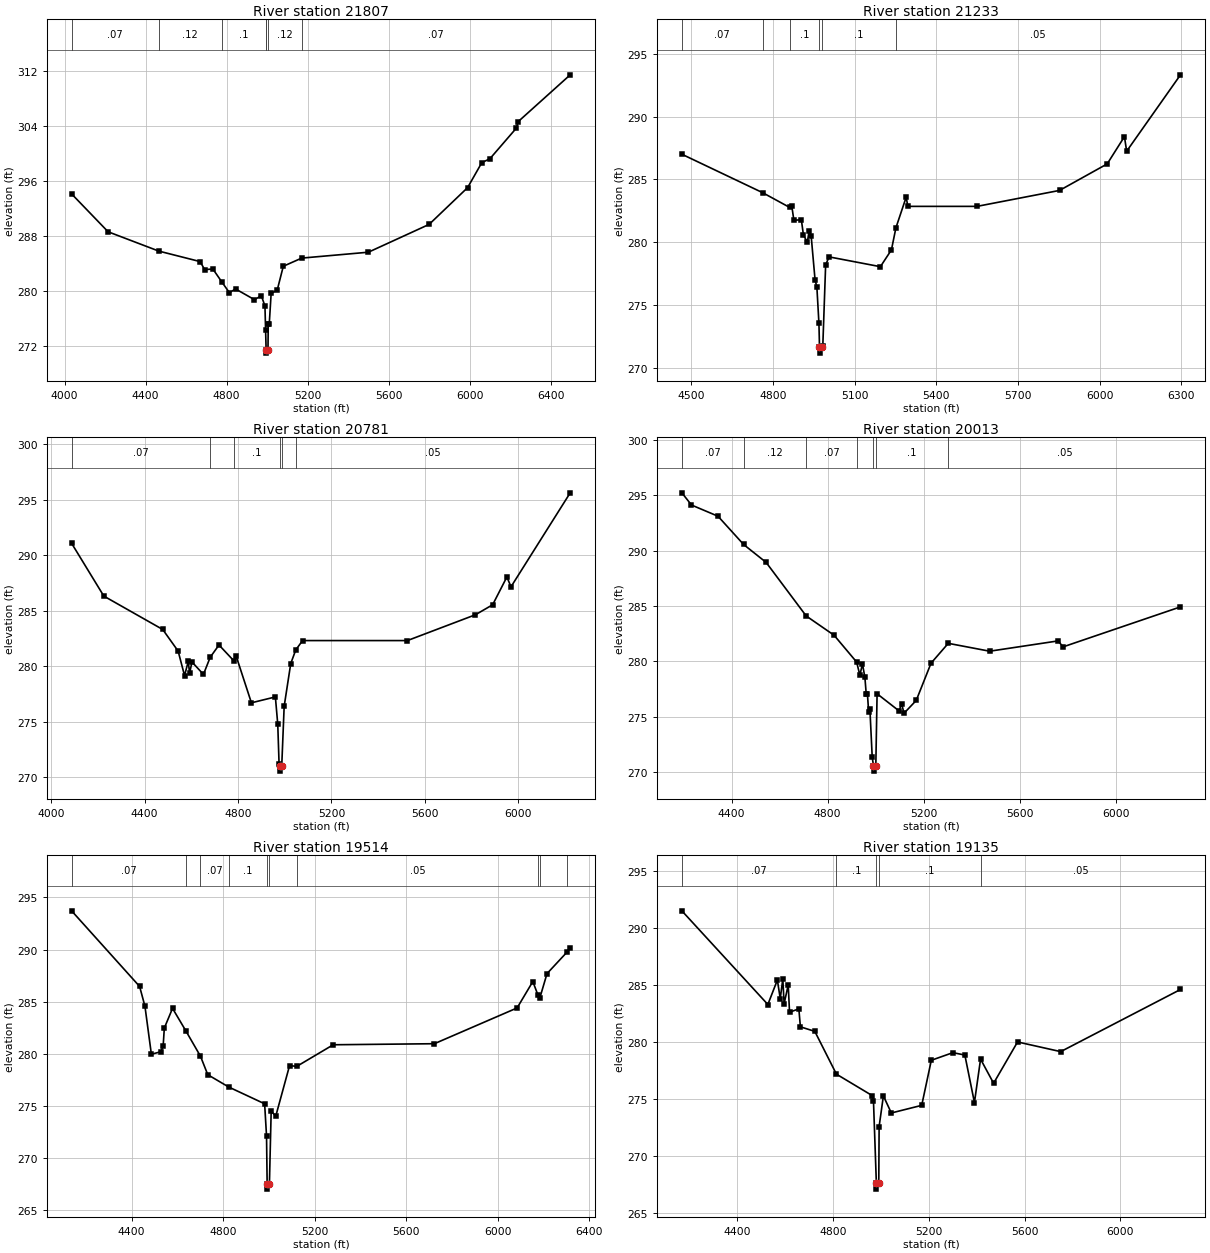
Type RM Length L Ch R = 1 ,21807   ,574,574,574
BEGIN DESCRIPTION:
Stream0731 35.0
END DESCRIPTION:
XS GIS Cut Line= 3
      2454259.66      13701892.7       2453318.8     13701650.77
      2451828.41     13701670.91
#Sta/Elev= 30
  4034.9  294.13  4215.2   288.6  4465.7  285.78  4669.6  284.25  4691.8  283.08
  4732.5  283.17  4775.9  281.31  4814.1  279.71  4844.4  280.26    4938  278.69
  4971.7  279.27  4989.6  277.77  4992.8  274.25  4995.4  271.39  4995.9  270.89
  5004.6  271.39  5005.8  275.12  5010.8  275.12  5020.2   279.6  5050.2  280.09
  5080.2  283.57  5171.1  284.76  5500.2  285.62  5800.2  289.68  5990.3  295.05
  6060.3  298.69  6100.3  299.26  6230.3  303.71  6240.3  304.69  6496.9  311.51
#Mann= 7 ,-1 , 0
  4034.9     .07       0  4465.7     .12       0  4775.9      .1       0
  4992.8     .12       0  4995.4     .05       0  5004.6     .12       0
  5171.1     .07       0
Bank Sta=4995.4,5004.6
XS Rating Curve= 0 ,0
Exp/Cntr=0.3,0.1

Type RM Length L Ch R = 1 ,21233   ,452,452,452
BEGIN DESCRIPTION:
Stream0731 34.0
END DESCRIPTION:
XS GIS Cut Line= 3
      2454124.97     13701674.97        2453725.       13701325.
      2452524.97     13700824.99
#Sta/Elev= 30
    4465  287.01  4761.7  283.95  4860.7  282.78  4868.8  282.88  4876.4  281.76
  4903.9  281.79  4911.5  280.59  4925.8     280  4932.4   280.9    4940  280.49
  4954.2  277.02  4960.9  276.44  4968.5  273.54  4970.5  271.68    4971  271.18
  4979.7  271.68  4982.7  271.76  4993.1   278.2  5005.7  278.84  5194.2  278.06
  5234.8   279.4  5251.2  281.15    5289   283.6  5294.9  282.86    5549  282.86
  5852.3  284.13  6027.3  286.24  6090.6  288.41  6098.8  287.25  6296.5  293.33
#Mann= 6 ,-1 , 0
    4465     .07       0  4761.7     .12       0  4860.7      .1       0
  4970.5     .05       0  4979.7      .1       0  5251.2     .05       0
Bank Sta=4970.5,4979.7
XS Rating Curve= 0 ,0
Exp/Cntr=0.3,0.1

Type RM Length L Ch R = 1 ,20781   ,768,768,768
BEGIN DESCRIPTION:
Stream0731 33.0
END DESCRIPTION:
XS GIS Cut Line= 3
      2454474.99     13701374.99        2453675.       13700925.
      2452475.01       13700725.
#Sta/Elev= 30
  4087.7  291.07  4225.7  286.31  4477.8   283.3  4543.8  281.35  4571.2  279.14
  4587.1  280.42  4592.8  279.36    4603  280.37  4652.1  279.25  4681.1   280.8
  4718.7   281.9  4783.8  280.44  4792.3  280.89  4857.4  276.69    4960  277.22
  4970.2  274.75  4975.9  271.14    4978  271.03  4978.5  270.53  4987.3  271.03
  4997.6  276.37  5025.8  280.23  5047.3  281.46  5076.5   282.3  5525.1   282.3
  5816.6  284.63  5890.1  285.53  5950.9  288.03  5968.7  287.15  6222.1  295.62
#Mann= 6 ,-1 , 0
  4087.7     .07       0  4681.1     .12       0  4783.8      .1       0
    4978     .05       0  4987.3      .1       0  5047.3     .05       0
Bank Sta=4978,4987.3
XS Rating Curve= 0 ,0
Exp/Cntr=0.3,0.1

Type RM Length L Ch R = 1 ,20013   ,499,499,499
BEGIN DESCRIPTION:
Stream0731 32.0
END DESCRIPTION:
XS GIS Cut Line= 3
      2454924.94      13700535.2      2454158.84       13700468.
      2452875.05     13700724.99
#Sta/Elev= 30
  4192.5  295.21  4232.6  294.11    4343   293.1  4449.8  290.55  4543.8  288.93
  4710.7   284.1    4827  282.36    4921  279.94  4934.4  278.76  4945.3  279.77
  4955.4  278.55    4961  277.05    4966  277.05  4971.1  275.43  4976.2  275.73
  4985.9  271.35  4991.2   270.6  4991.7   270.1  5000.9   270.6  5006.2  277.08
    5098  275.53  5108.2   276.2  5118.4  275.32  5169.4  276.48  5231.1  279.84
  5302.9  281.63  5475.4  280.92  5760.9  281.85  5781.3  281.31  6270.8  284.92
#Mann= 7 ,-1 , 0
  4192.5     .07       0  4449.8     .12       0  4710.7     .07       0
    4921      .1       0  4991.2     .05       0  5000.9      .1       0
  5302.9     .05       0
Bank Sta=4991.2,5000.9
XS Rating Curve= 0 ,0
Exp/Cntr=0.3,0.1

Type RM Length L Ch R = 1 ,19514   ,379,379,379
BEGIN DESCRIPTION:
Stream0731 31.0
END DESCRIPTION:
XS GIS Cut Line= 3
      2454864.48     13700273.11        2454025.       13700075.
      2452713.96     13700205.91
#Sta/Elev= 30
  4137.8  293.72  4435.2  286.47  4458.5  284.57  4486.6  279.97  4527.7  280.21
    4538  280.72  4543.2  282.48  4579.1  284.37  4637.7   282.2  4701.3  279.78
  4733.2  278.01  4824.7  276.83  4981.8  275.22  4990.1  272.14  4992.8  267.54
  4993.3  267.04  5002.7  267.54  5010.4  274.51  5030.5  274.04  5090.8  278.88
  5122.5  278.81  5281.7  280.88  5723.9  280.98  6085.7  284.41  6154.4  286.94
  6176.8  285.65  6185.1  285.37  6216.4   287.7  6304.2  289.77  6317.9  290.17
#Mann= 10 ,-1 , 0
  4137.8     .07       0  4637.7     .12       0  4701.3     .07       0
  4824.7      .1       0  4992.8     .05       0  5002.7      .1       0
  5122.5     .05       0  6176.8     .07       0  6185.1     .05       0
  6304.2    .035       0
Bank Sta=4992.8,5002.7
XS Rating Curve= 0 ,0
Exp/Cntr=0.3,0.1

Type RM Length L Ch R = 1 ,19135   ,786,786,786
BEGIN DESCRIPTION:
Stream0731 30.0
END DESCRIPTION:
XS GIS Cut Line= 3
      2454924.97     13700105.12      2454185.72     13699748.93
      2452924.98       13699775.
#Sta/Elev= 30
  4169.3  291.52  4528.3  283.29    4568  285.44    4580  283.81  4590.7  285.53
  4596.2  283.36  4613.3  285.01  4618.8  282.61  4657.7  282.91  4664.1  281.33
  4724.3  280.93  4814.6  277.17  4963.7  275.29  4969.2  274.83  4981.3  267.57
  4981.8  267.07  4991.3  267.57  4992.8  272.57  5010.6  275.26  5043.7  273.76
  5170.6  274.43  5210.7  278.39  5300.7  279.06  5350.7  278.85  5390.7  274.68
  5416.3  278.49  5470.7  276.37  5570.7     280  5750.8  279.15  6250.9  284.61
#Mann= 5 ,-1 , 0
  4169.3     .07       0  4814.6      .1       0  4981.3     .05       0
  4991.3      .1       0  5416.3     .05       0
Bank Sta=4981.3,4991.3
XS Rating Curve= 0 ,0
Exp/Cntr=0.3,0.1

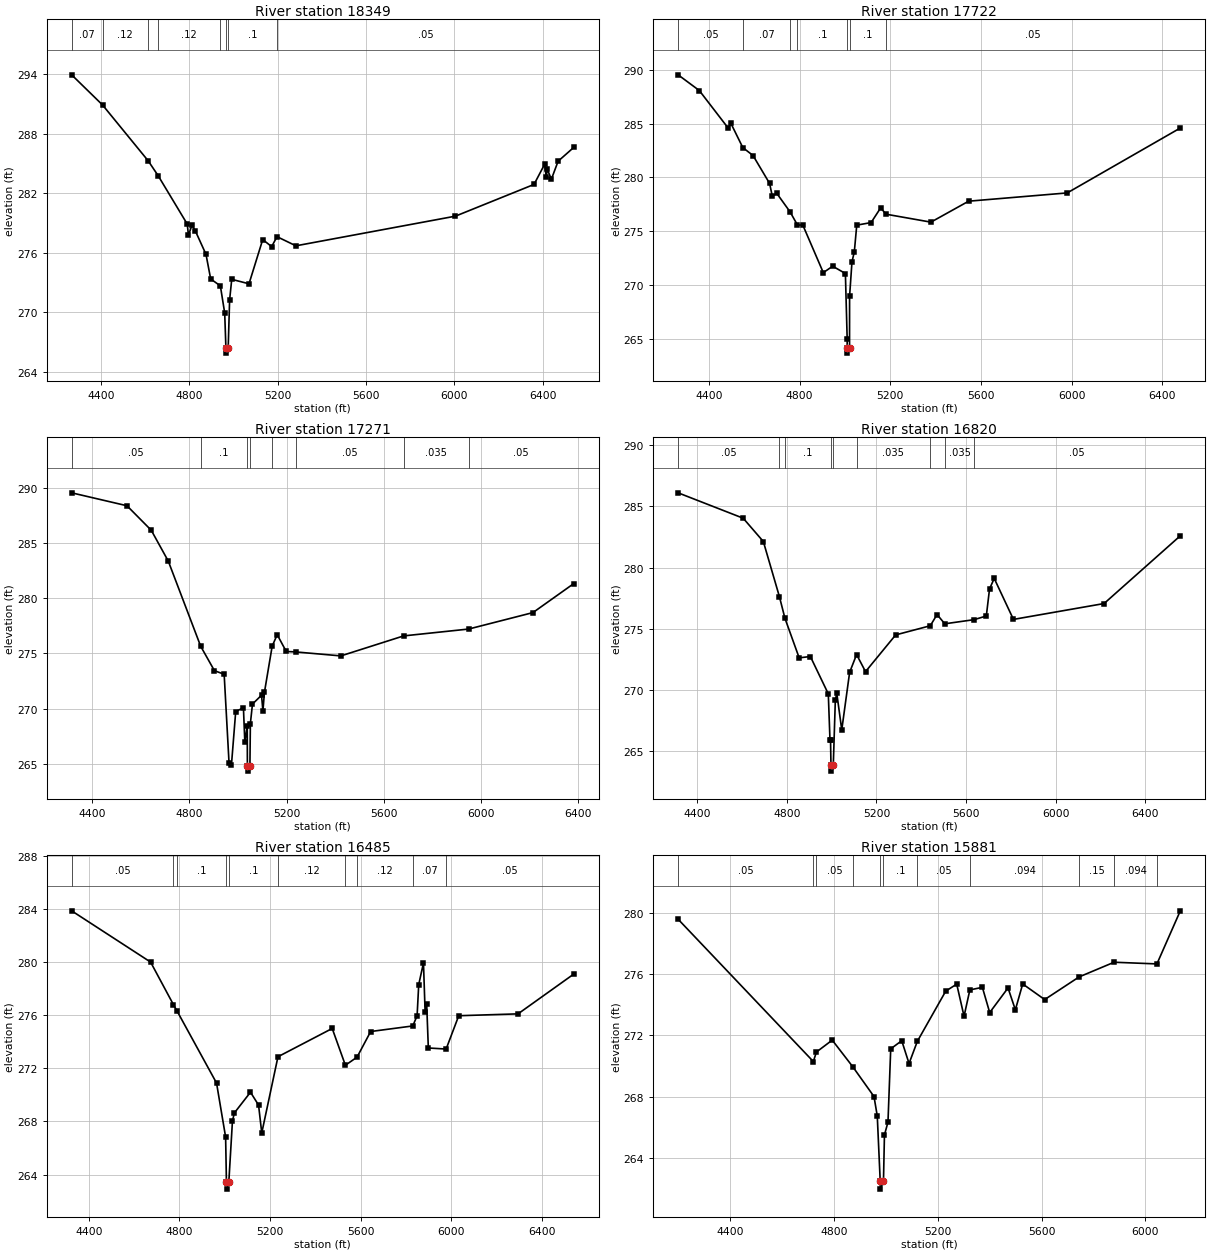
Type RM Length L Ch R = 1 ,18349   ,627,627,627
BEGIN DESCRIPTION:
XS7572
END DESCRIPTION:
XS GIS Cut Line= 3
      2455019.01     13699614.51      2454192.44     13699325.55
       2452814.8     13699560.76
#Sta/Elev= 30
  4267.6  293.92  4407.5  290.88    4614  285.25  4659.1  283.75  4790.9  278.87
  4796.3  277.74  4812.1  278.76  4827.4  278.19  4875.7  275.82  4896.9  273.34
  4940.8  272.64  4960.4   269.9  4965.9  266.36  4966.4  265.86  4976.2  266.36
  4982.6  271.21  4992.2   273.3  5070.4  272.85  5132.5  277.31  5172.9   276.6
  5197.3   277.6  5282.7  276.68  6004.8  279.67  6360.6  282.87  6408.7  284.91
  6415.6  283.64  6420.7  284.39  6439.1  283.39  6469.6  285.21  6540.8  286.61
#Mann= 8 ,-1 , 0
  4267.6     .07       0  4407.5     .12       0    4614     .07       0
  4659.1     .12       0  4940.8      .1       0  4965.9     .05       0
  4976.2      .1       0  5197.3     .05       0
Bank Sta=4965.9,4976.2
XS Rating Curve= 0 ,0
Exp/Cntr=0.3,0.1

Type RM Length L Ch R = 1 ,17722   ,451,451,451
BEGIN DESCRIPTION:
Stream0731 29.0
END DESCRIPTION:
XS GIS Cut Line= 3
      2455012.27     13698714.02        2454325.       13698975.
      2452922.29     13699446.52
#Sta/Elev= 30
  4264.2  289.55  4357.6  288.09  4485.9  284.57  4496.6  285.05  4549.5  282.78
  4594.6  282.04  4667.8  279.44  4679.6  278.25    4699  278.53  4758.2  276.79
  4790.6  275.57  4814.2  275.57  4904.6  271.14  4945.9  271.74    5002  271.06
  5009.8  265.01    5010  264.15  5010.5  263.65  5020.3  264.15  5020.5  268.94
    5031  272.14  5041.4  273.08  5052.1  275.56  5115.4   275.8  5157.6  277.17
    5181  276.58  5379.2  275.84  5545.6  277.79  5980.5  278.56  6479.2   284.6
#Mann= 7 ,-1 , 0
  4264.2     .05       0  4549.5     .07       0  4758.2     .12       0
  4790.6      .1       0    5010     .05       0  5020.3      .1       0
    5181     .05       0
Bank Sta=5010,5020.3
XS Rating Curve= 0 ,0
Exp/Cntr=0.3,0.1

Type RM Length L Ch R = 1 ,17271   ,451,451,451
BEGIN DESCRIPTION:
Stream0731 28.0
END DESCRIPTION:
XS GIS Cut Line= 3
      2455052.66      13698579.6        2454375.       13698575.
      2453175.02     13699274.99
#Sta/Elev= 30
  4315.6  289.54  4543.3  288.37  4643.3  286.15  4713.3  283.36  4846.7  275.65
  4903.3  273.44  4943.3  273.12  4963.3  265.12  4973.3  264.91  4990.8  269.74
  5022.6  270.09  5028.4  266.95  5038.3  268.46  5038.9  264.85  5039.4  264.35
  5049.3  264.85  5051.2  268.66  5059.8  270.42  5097.1  271.22  5102.8   269.8
  5109.1  271.49  5140.9  275.66  5161.6   276.7  5198.8  275.18  5237.2  275.14
  5423.7  274.78  5682.1  276.59  5949.4  277.21  6214.2   278.7  6382.5  281.33
#Mann= 8 ,-1 , 0
  4315.6     .05       0  4846.7      .1       0  5038.9     .05       0
  5049.3      .1       0  5140.9      .1       0  5237.2     .05       0
  5682.1    .035       0  5949.4     .05       0
Bank Sta=5038.9,5049.3
XS Rating Curve= 0 ,0
Exp/Cntr=0.3,0.1

Type RM Length L Ch R = 1 ,16820   ,335,335,335
BEGIN DESCRIPTION:
Stream0731 27.0
END DESCRIPTION:
XS GIS Cut Line= 3
      2455005.55     13698162.94        2454325.       13698175.
      2453125.01     13699174.99
#Sta/Elev= 30
  4314.3  286.12  4604.9  284.04  4694.9  282.13  4766.9   277.6  4791.2  275.85
  4854.9   272.6  4904.9  272.71    4985  269.65  4992.5  265.87    4995  265.87
  4996.9  263.82  4997.4  263.32  5007.3  263.82  5016.4  269.14  5022.9   269.7
  5045.1   266.7  5080.2  271.41  5111.3  272.87  5151.2  271.47  5285.9  274.48
  5440.4  275.23  5470.7  276.15  5505.1  275.39  5636.3  275.73  5690.7  276.03
    5705  278.24  5725.9  279.11  5811.8  275.75  6216.6  277.05    6557   282.6
#Mann= 9 ,-1 , 0
  4314.3     .05       0  4766.9     .07       0  4791.2      .1       0
  4996.9     .05       0  5007.3      .1       0  5111.3    .035       0
  5440.4     .05       0  5505.1    .035       0  5636.3     .05       0
Bank Sta=4996.9,5007.3
XS Rating Curve= 0 ,0
Exp/Cntr=0.3,0.1

Type RM Length L Ch R = 1 ,16485   ,604,604,604
BEGIN DESCRIPTION:
Stream0731 26.0
END DESCRIPTION:
XS GIS Cut Line= 3
      2454992.19     13697934.46      2454273.08     13697867.25
      2453252.84     13698961.32
#Sta/Elev= 30
  4323.8  283.86  4672.5     280  4773.2   276.8  4789.2  276.32  4963.8  270.89
  5003.9  266.82  5007.5   263.4    5008   262.9  5017.9   263.4  5034.1  268.04
  5042.6  268.64  5113.7   270.2  5149.4  269.23  5163.5  267.13  5235.1  272.87
  5474.7     275  5532.9  272.23  5584.4  272.84  5644.6  274.77  5830.6  275.19
  5849.7  275.96  5856.8   278.3  5877.8  279.94  5885.1  276.24  5891.9  276.88
  5899.3  273.53  5977.9  273.45  6033.6  275.96  6295.5   276.1    6542   279.1
#Mann= 10 ,-1 , 0
  4323.8     .05       0  4773.2     .07       0  4789.2      .1       0
  5007.5     .05       0  5017.9      .1       0  5235.1     .12       0
  5532.9      .1       0  5584.4     .12       0  5830.6     .07       0
  5977.9     .05       0
Bank Sta=5007.5,5017.9
XS Rating Curve= 0 ,0
Exp/Cntr=0.3,0.1

Type RM Length L Ch R = 1 ,15881   ,470,470,470
BEGIN DESCRIPTION:
Stream0731 25.0
END DESCRIPTION:
XS GIS Cut Line= 3
      2454824.97       13697775.        2454025.       13697675.
      2453224.97     13696874.97
#Sta/Elev= 30
  4197.9  279.59  4719.6  270.29  4731.5  270.91  4792.5  271.69  4871.3  269.96
  4953.7     268  4966.3  266.73  4977.7  262.45  4978.2  261.95  4990.2  262.45
    4994  265.49  5007.6  266.33  5018.2  271.12  5060.7  271.65  5088.9  270.16
  5120.9  271.61  5230.4  274.89  5272.8  275.35  5301.1  273.25  5323.5  274.97
  5371.8  275.14  5400.1  273.49  5470.8   275.1  5499.1  273.67  5527.4  275.36
  5612.2  274.34    5745  275.82    5880  276.78  6045.3  276.67  6135.5  280.14
#Mann= 11 ,-1 , 0
  4197.9     .05       0  4719.6      .1       0  4731.5     .05       0
  4871.3      .1       0  4977.7     .05       0  4990.2      .1       0
  5120.9     .05       0  5323.5    .094       0    5745     .15       0
    5880    .094       0  6045.3    .063       0
Bank Sta=4977.7,4990.2
XS Rating Curve= 0 ,0
Exp/Cntr=0.3,0.1