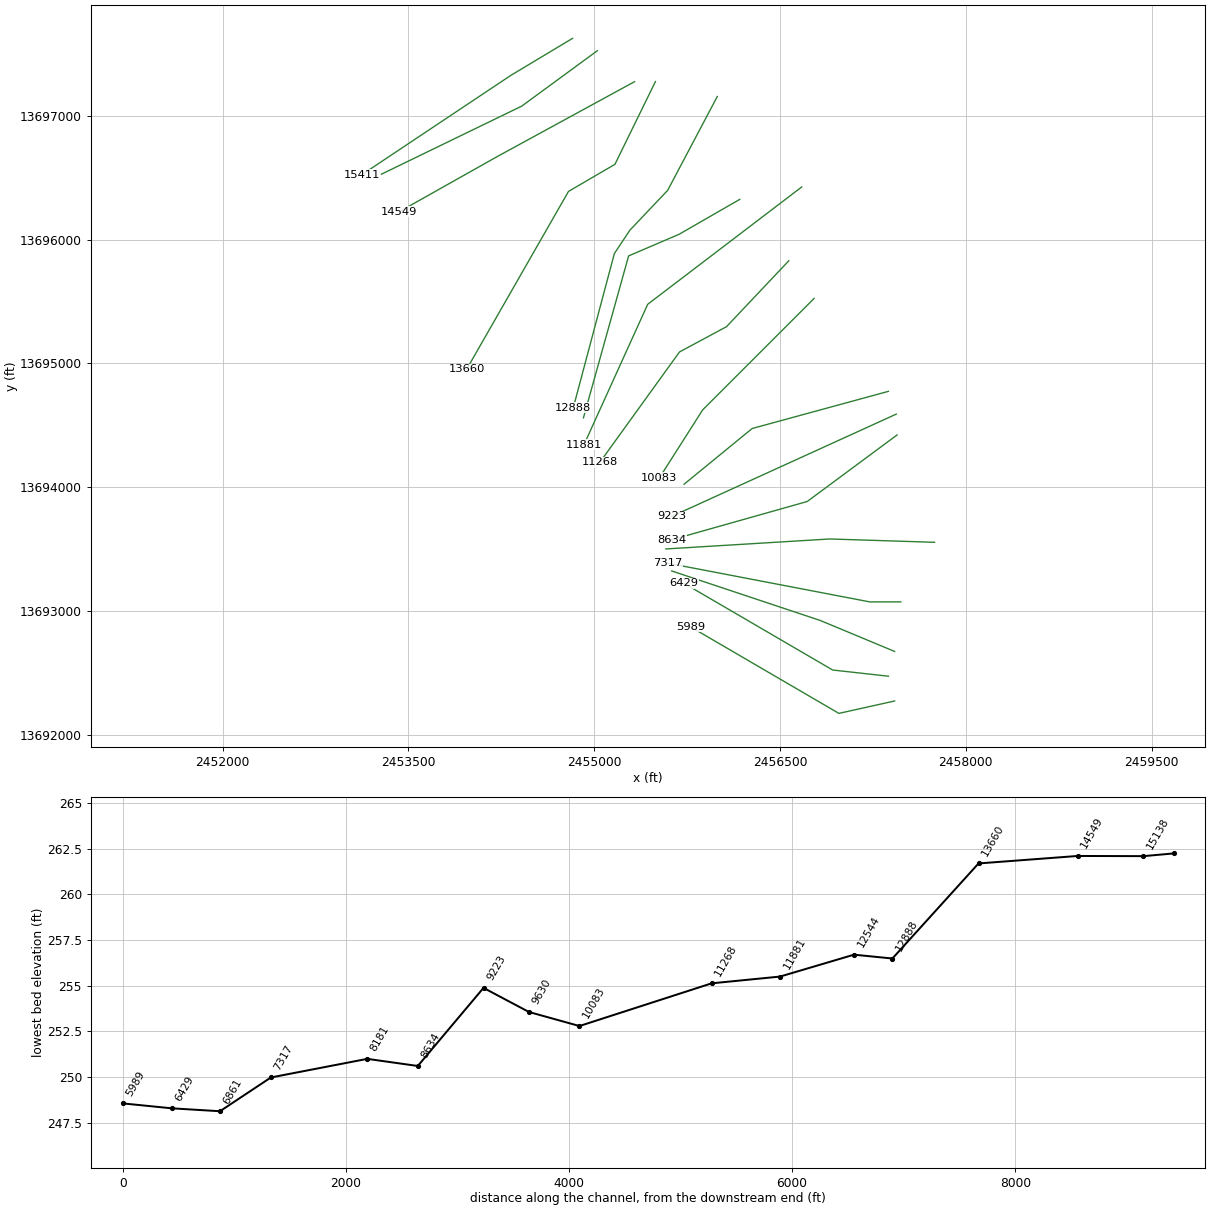
HEC-RAS study Stream0731.prj: Stream0731 Base Level Engineering

--- Stream0731.g01 (geometry) --- (continued)

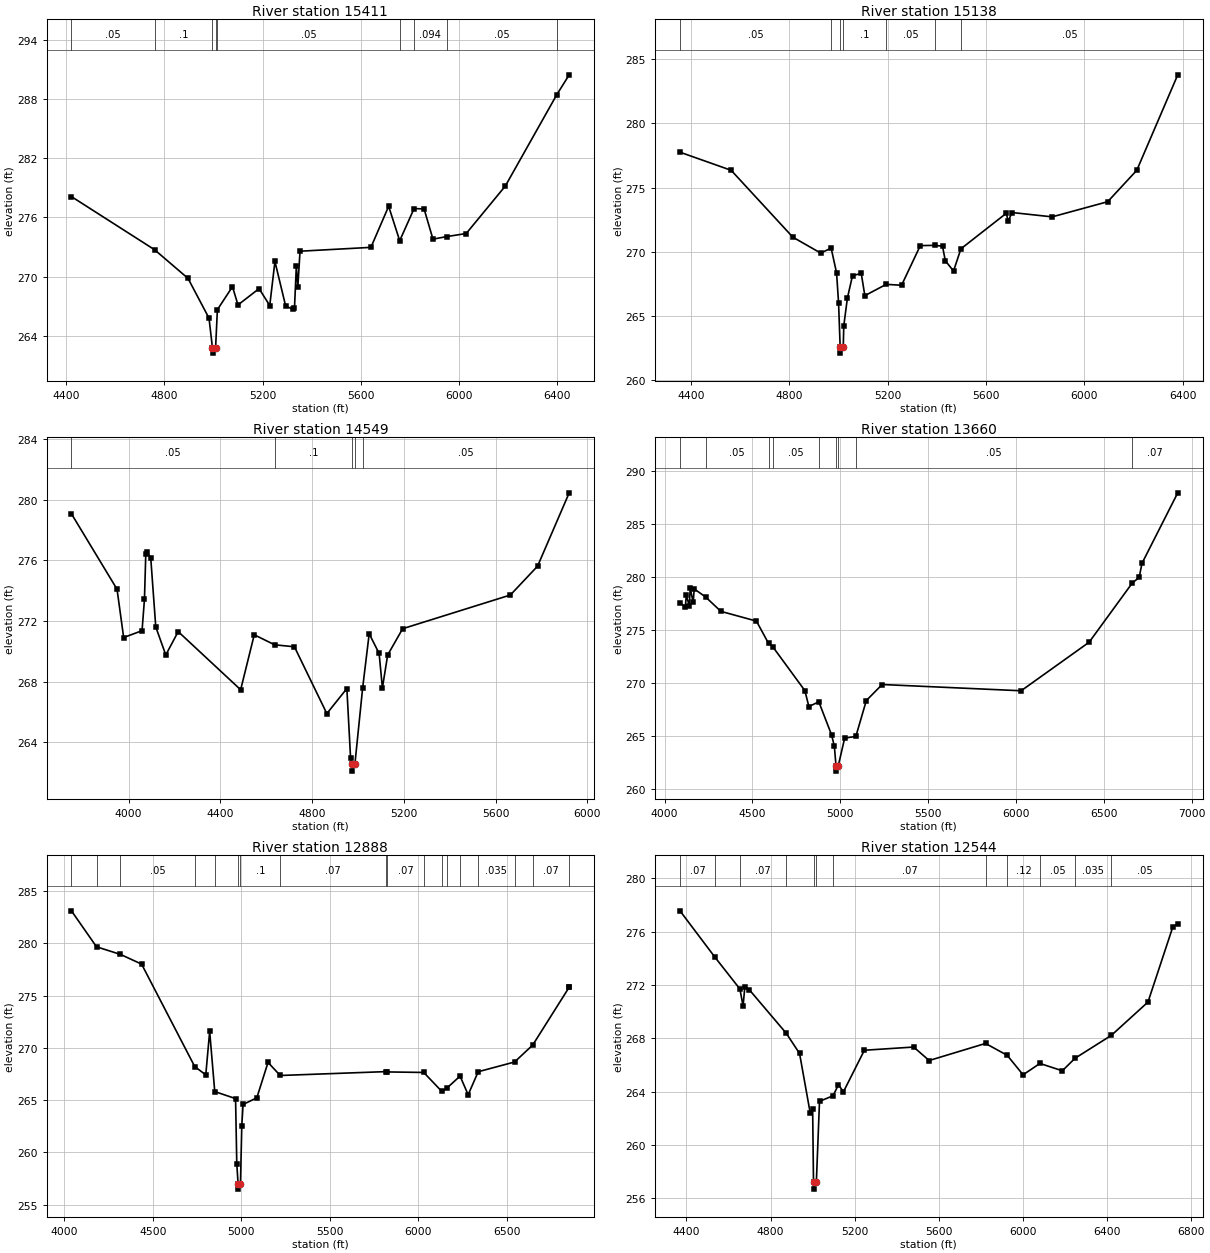
Type RM Length L Ch R = 1 ,15411   ,273,273,273
BEGIN DESCRIPTION:
Stream0731 24.0
END DESCRIPTION:
XS GIS Cut Line= 3
      2454825.01       13697625.        2454325.       13697325.
      2453125.02     13696525.01
#Sta/Elev= 30
  4422.4   278.1  4760.7  272.72  4896.7  269.82  4982.2  265.79  4996.3  262.75
  4996.8  262.25  5008.9  262.75  5016.3  266.65  5077.6  268.98  5100.1  267.13
  5185.8  268.78  5229.3  267.07  5250.4  271.53  5293.9  267.03  5322.5  266.69
    5330  266.85  5337.5  271.07  5343.5  268.93  5352.5  272.57    5641  272.96
  5713.1  277.12    5758  273.63  5816.6  276.89  5857.3  276.85  5893.4  273.79
  5949.1  274.05  6028.6  274.36  6187.8  279.17  6397.4  288.43  6447.7  290.43
#Mann= 9 ,-1 , 0
  4422.4     .05       0  4760.7      .1       0  4996.3     .05       0
  5008.9      .1       0  5016.3     .05       0    5758     .15       0
  5816.6    .094       0  5949.1     .05       0  6397.4    .035       0
Bank Sta=4996.3,5008.9
XS Rating Curve= 0 ,0
Exp/Cntr=0.3,0.1

Type RM Length L Ch R = 1 ,15138   ,589,589,589
BEGIN DESCRIPTION:
Stream0731 23.0
END DESCRIPTION:
XS GIS Cut Line= 3
        2455025.       13697525.      2454414.21     13697077.62
      2453274.98     13696524.99
#Sta/Elev= 30
  4356.1  277.76  4564.1  276.35  4814.7  271.14  4927.8   269.9  4970.6  270.28
  4992.6  268.36  5000.7  266.03  5007.2   262.6  5007.7   262.1  5019.8   262.6
  5021.9  264.22  5036.6  266.39  5057.4  268.14  5092.9  268.31  5107.6  266.58
  5194.4  267.46  5256.8  267.39    5333  270.48  5393.5   270.5  5423.2  270.43
  5434.6   269.3    5468   268.5    5498  270.23  5682.6     273  5690.3  272.36
  5705.2  273.06  5868.8  272.72  6094.5   273.9  6212.9  276.35  6379.4  283.79
#Mann= 7 ,-1 , 0
  4356.1     .05       0  4970.6      .1       0  5007.2     .05       0
  5019.8      .1       0  5194.4     .05       0  5393.5      .1       0
    5498     .05       0
Bank Sta=5007.2,5019.8
XS Rating Curve= 0 ,0
Exp/Cntr=0.3,0.1

Type RM Length L Ch R = 1 ,14549   ,889,889,889
BEGIN DESCRIPTION:
Stream0731 22.0
END DESCRIPTION:
XS GIS Cut Line= 3
      2455324.99     13697274.99        2454225.       13696675.
      2453424.96     13696224.98
#Sta/Elev= 30
  3750.4  279.06  3949.3  274.09  3978.2  270.91  4058.4  271.36  4068.9  273.43
  4074.6  276.38  4080.7  276.57  4096.4  276.13  4118.2  271.61  4161.9  269.76
    4216   271.3  4488.4  267.47  4547.7  271.09  4636.6  270.43  4722.9   270.3
  4864.3   265.9  4951.6  267.55  4967.8  262.98  4974.3  262.61  4974.8  262.11
  4986.9  262.61  5020.6  267.61    5049  271.16  5092.3  269.86  5106.6  267.59
  5129.6  269.76  5194.9  271.49  5664.7  273.71  5783.3  275.61  5921.3  280.44
#Mann= 5 ,-1 , 0
  3750.4     .05       0  4636.6      .1       0  4974.3     .05       0
  4986.9      .1       0  5020.6     .05       0
Bank Sta=4974.3,4986.9
XS Rating Curve= 0 ,0
Exp/Cntr=0.3,0.1

Type RM Length L Ch R = 1 ,13660   ,772,772,772
BEGIN DESCRIPTION:
Stream0731 21.0
END DESCRIPTION:
XS GIS Cut Line= 5
      2455493.89     13697276.04      2455166.92     13696607.79
        2455025.       13696525.      2454791.96     13696389.06
      2453969.35     13694952.34
#Sta/Elev= 30
  4087.4   277.6  4117.7  277.15  4123.3  278.27  4140.2  277.32  4145.8  278.95
  4162.7  277.61  4168.3  278.89    4233  278.13  4320.3  276.77  4522.7  275.85
  4591.8  273.74  4616.6  273.41  4798.5  269.29  4821.1  267.79  4877.7  268.24
  4950.6  265.11  4966.3  264.04  4975.6   262.2  4976.1   261.7  4988.5   262.2
    5025  264.82  5088.5  264.97  5148.2  268.36  5238.4  269.87  6029.5  269.28
  6416.6  273.86  6661.6  279.43  6701.5  279.98  6717.4   281.3    6921  287.95
#Mann= 9 ,-1 , 0
  4087.4    .035       0    4233     .05       0  4591.8    .035       0
  4616.6     .05       0  4877.7      .1       0  4975.6     .05       0
  4988.5      .1       0  5088.5     .05       0  6661.6     .07       0
Bank Sta=4975.6,4988.5
XS Rating Curve= 0 ,0
Exp/Cntr=0.3,0.1

Type RM Length L Ch R = 1 ,12888   ,344,344,344
BEGIN DESCRIPTION:
Stream0731 20.0
END DESCRIPTION:
XS GIS Cut Line= 5
       2455993.2     13697155.13      2455592.54     13696397.48
      2455287.84      13696076.3      2455162.32     13695887.34
      2454830.75     13694642.99
#Sta/Elev= 30
  4039.5  283.11  4181.3  279.67  4316.9  278.94  4436.3  278.01  4736.7  268.21
  4799.1  267.42  4821.1  271.58  4849.8  265.82  4967.5  265.15  4974.4  258.91
  4981.8  256.99  4982.3  256.49  4995.2  256.99  5002.7  262.55  5009.9  264.59
  5087.6  265.22  5151.1  268.61    5220  267.36    5818  267.73    5826   267.7
  6031.4  267.65  6134.1  265.83  6163.3  266.17  6236.8   267.3  6282.6  265.52
  6339.5  267.72  6544.9  268.65  6647.5  270.27  6852.9  275.78  6853.9  275.78
#Mann= 18 ,-1 , 0
  4039.5     .07       0  4181.3    .035       0  4316.9     .05       0
  4736.7     .07       0  4849.8      .1       0  4981.8     .05       0
  4995.2      .1       0    5220     .07       0    5818    .035       0
    5826     .07       0  6031.4     .05       0  6134.1     .12       0
  6163.3     .05       0  6236.8     .12       0  6339.5    .035       0
  6544.9     .05       0  6647.5     .07       0  6852.9     .05       0
Bank Sta=4981.8,4995.2
XS Rating Curve= 0 ,0
Exp/Cntr=0.3,0.1

Type RM Length L Ch R = 1 ,12544   ,663,663,663
BEGIN DESCRIPTION:
Stream0731 19.0
END DESCRIPTION:
XS GIS Cut Line= 4
      2456174.97     13696324.98      2455684.34     13696042.69
      2455277.42     13695868.43      2454912.67     13694561.07
#Sta/Elev= 30
  4369.5  277.56  4534.9   274.1  4654.4   271.7  4669.4  270.42  4677.7  271.85
  4699.3  271.64  4874.8  268.38  4937.9  266.87  4988.5  262.41  5000.1  262.71
  5004.2   257.2  5004.7   256.7  5017.7   257.2  5032.7  263.28  5097.3   263.7
  5122.7  264.53  5146.3  263.99    5246  267.11  5480.3  267.35  5553.9  266.34
  5821.9  267.62  5924.9  266.73  6000.3  265.27  6080.4  266.12  6186.8  265.57
  6247.4  266.51  6420.2  268.23  6593.9  270.72    6712  276.35  6735.5  276.58
#Mann= 12 ,-1 , 0
  4369.5     .07       0  4534.9     .12       0  4654.4     .07       0
  4874.8      .1       0  5004.2     .05       0  5017.7      .1       0
  5097.3     .07       0  5821.9     .05       0  5924.9     .12       0
  6080.4     .05       0  6247.4    .035       0  6420.2     .05       0
Bank Sta=5004.2,5017.7
XS Rating Curve= 0 ,0
Exp/Cntr=0.3,0.1

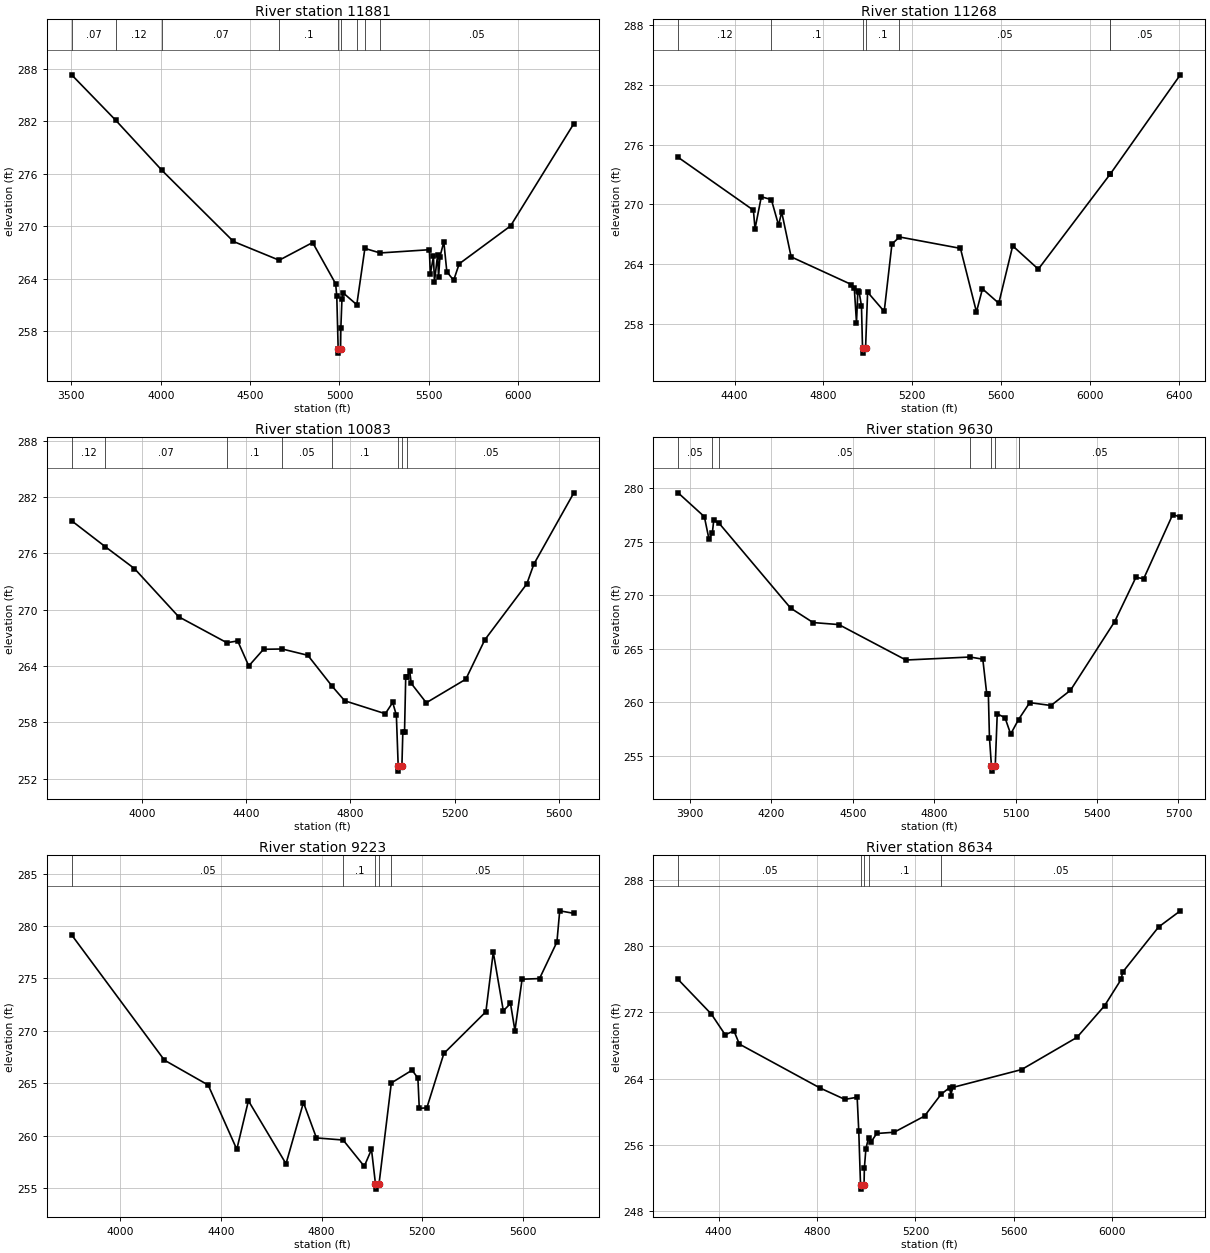
Type RM Length L Ch R = 1 ,11881   ,613,613,613
BEGIN DESCRIPTION:
Stream0731 18.0
END DESCRIPTION:
XS GIS Cut Line= 3
      2456675.01     13696425.01      2455431.47     13695477.75
      2454916.56      13694342.6
#Sta/Elev= 30
  3501.5  287.31  3747.9  282.12  4006.8  276.39  4406.9  268.26  4662.7  266.12
  4849.7  268.14  4978.5  263.43  4984.9  261.99  4992.6     256  4993.1   255.5
  5006.1     256  5007.6  258.35  5013.9  261.74  5022.2  262.36  5096.8  261.03
  5142.1  267.47  5227.2  266.95  5502.8  267.32  5508.2  264.54  5525.8  266.55
  5531.3  263.65  5548.9  266.72  5554.4  264.16  5561.9  266.51  5583.8  268.21
  5600.6  264.81  5638.7  263.82  5669.8  265.71  5957.2  270.04  6311.2  281.73
#Mann= 9 ,-1 , 0
  3501.5     .07       0  3747.9     .12       0  4006.8     .07       0
  4662.7      .1       0  4992.6     .05       0  5006.1      .1       0
  5096.8     .05       0  5142.1     .07       0  5227.2     .05       0
Bank Sta=4992.6,5006.1
XS Rating Curve= 0 ,0
Exp/Cntr=0.3,0.1

Type RM Length L Ch R = 1 ,11268   ,1185,1185,1185
BEGIN DESCRIPTION:
Stream0731 17.0
END DESCRIPTION:
XS GIS Cut Line= 4
      2456570.54     13695828.85       2456067.4     13695296.74
       2455688.2     13695092.93      2455045.32     13694202.22
#Sta/Elev= 30
    4146  274.72    4485  269.43  4492.3  267.57  4520.6  270.77  4565.9  270.49
  4598.3  267.93  4612.4  269.24  4654.9  264.76  4926.5  261.99  4939.1  261.69
  4949.2  258.19  4955.4  261.36  4961.1  261.23  4971.6  259.87  4976.4  255.63
  4976.9  255.13  4990.1  255.63  4999.2  261.23    5074   259.3  5108.8  266.04
  5142.7  266.75  5417.3  265.61  5489.4  259.25  5516.4  261.56  5589.9  260.12
  5652.6  265.86  5767.9  263.53  6091.6  273.04  6092.1  273.05  6407.3  282.97
#Mann= 7 ,-1 , 0
    4146     .12       0  4565.9      .1       0  4976.4     .05       0
  4990.1      .1       0  5142.7     .05       0  6091.6    .035       0
  6092.1     .05       0
Bank Sta=4976.4,4990.1
XS Rating Curve= 0 ,0
Exp/Cntr=0.3,0.1

Type RM Length L Ch R = 1 ,10083   ,453,453,453
BEGIN DESCRIPTION:
Stream0731 16.0
END DESCRIPTION:
XS GIS Cut Line= 3
      2456775.01     13695525.01        2455875.       13694625.
      2455525.01     13694075.02
#Sta/Elev= 30
  3731.3  279.48    3860  276.72  3971.7  274.39  4141.4  269.25  4326.1  266.48
  4367.7  266.67  4410.1     264  4466.7  265.78  4538.1  265.81  4636.4  265.14
  4730.2  261.82  4777.8  260.29  4933.4  258.91  4961.7  260.11  4975.8  258.76
  4982.9  253.29  4983.4  252.79    4997  253.29  5000.6  256.97  5007.1  256.97
  5011.7  262.86  5017.2  262.87    5027  263.42  5032.9  262.14  5090.5  260.08
    5242  262.59  5314.8  266.79  5475.7  272.75  5502.8  274.86    5656  282.46
#Mann= 8 ,-1 , 0
  3731.3     .12       0    3860     .07       0  4326.1      .1       0
  4538.1     .05       0  4730.2      .1       0  4982.9     .05       0
    4997      .1       0  5017.2     .05       0
Bank Sta=4982.9,4997
XS Rating Curve= 0 ,0
Exp/Cntr=0.3,0.1

Type RM Length L Ch R = 1 ,9630    ,407,407,407
BEGIN DESCRIPTION:
Stream0731 15.0
END DESCRIPTION:
XS GIS Cut Line= 3
        2457375.       13694775.        2456275.       13694475.
      2455725.01     13694025.01
#Sta/Elev= 30
  3855.9  279.56  3952.6  277.33  3969.9   275.2    3982  275.81  3987.2  276.99
  4007.5   276.7  4270.5  268.79  4353.4  267.44  4448.4  267.25  4695.5  263.94
  4931.7  264.22  4978.8  264.02  4993.5  260.74  4999.3  260.74  5003.3   256.7
  5010.6  254.06  5011.1  253.56  5024.7  254.06    5032  258.91  5060.7  258.55
  5081.5  257.02  5110.5  258.38  5151.8  259.96  5230.1  259.69  5301.9  261.11
  5464.8  267.53    5543  271.66  5571.8  271.54  5678.7  277.53  5706.7   277.3
#Mann= 7 ,-1 , 0
  3855.9     .05       0    3982     .07       0  4007.5     .05       0
  4931.7      .1       0  5010.6     .05       0  5024.7      .1       0
  5110.5     .05       0
Bank Sta=5010.6,5024.7
XS Rating Curve= 0 ,0
Exp/Cntr=0.3,0.1

Type RM Length L Ch R = 1 ,9223    ,589,589,589
BEGIN DESCRIPTION:
XS7571
END DESCRIPTION:
XS GIS Cut Line= 2
      2457438.33     13694591.11      2455623.85     13693764.51
#Sta/Elev= 30
  3807.8  279.16    4176   267.2  4349.9  264.82  4463.5  258.68  4509.6  263.32
  4658.9   257.3  4728.1  263.15  4779.7  259.77  4885.7  259.57  4969.6  257.06
  4998.3  258.67  5014.1  255.38  5014.6  254.88  5028.2  255.38    5077  265.02
  5159.4  266.24  5182.5  265.49    5188   262.6    5218  262.64  5285.7  267.84
  5452.5  271.82  5481.8  277.51  5521.7  271.91  5550.2  272.61  5567.8  270.02
  5596.3  274.93  5665.5  274.99  5734.5  278.48  5745.6  281.46  5801.7  281.22
#Mann= 5 ,-1 , 0
  3807.8     .05       0  4885.7      .1       0  5014.1     .05       0
  5028.2      .1       0    5077     .05       0
Bank Sta=5014.1,5028.2
XS Rating Curve= 0 ,0
Exp/Cntr=0.3,0.1

Type RM Length L Ch R = 1 ,8634    ,453,453,453
BEGIN DESCRIPTION:
XS7570
END DESCRIPTION:
XS GIS Cut Line= 3
      2457445.04     13694423.09      2456719.26     13693885.49
      2455623.85     13693576.35
#Sta/Elev= 30
  4235.3     276  4370.5   271.8  4426.8  269.29  4462.2  269.78  4484.2  268.17
  4812.9  262.84    4913  261.47  4963.1  261.73  4969.6  257.66  4976.8   251.1
  4977.3   250.6  4991.1   251.1  4992.4  253.12  4998.6  255.49  5009.6  256.84
  5019.4   256.3  5042.5  257.34  5113.4  257.49    5237  259.45  5304.2  262.09
    5339   262.9  5344.2  261.94  5350.7  262.91  5631.3  265.08  5856.5  268.98
  5968.8  272.81  6036.5  276.02    6042  276.87  6188.4  282.35  6276.7  284.31
#Mann= 5 ,-1 , 0
  4235.3     .05       0  4976.8     .05       0  4991.1     .05       0
  5009.6      .1       0  5304.2     .05       0
Bank Sta=4976.8,4991.1
XS Rating Curve= 0 ,0
Exp/Cntr=0.3,0.1

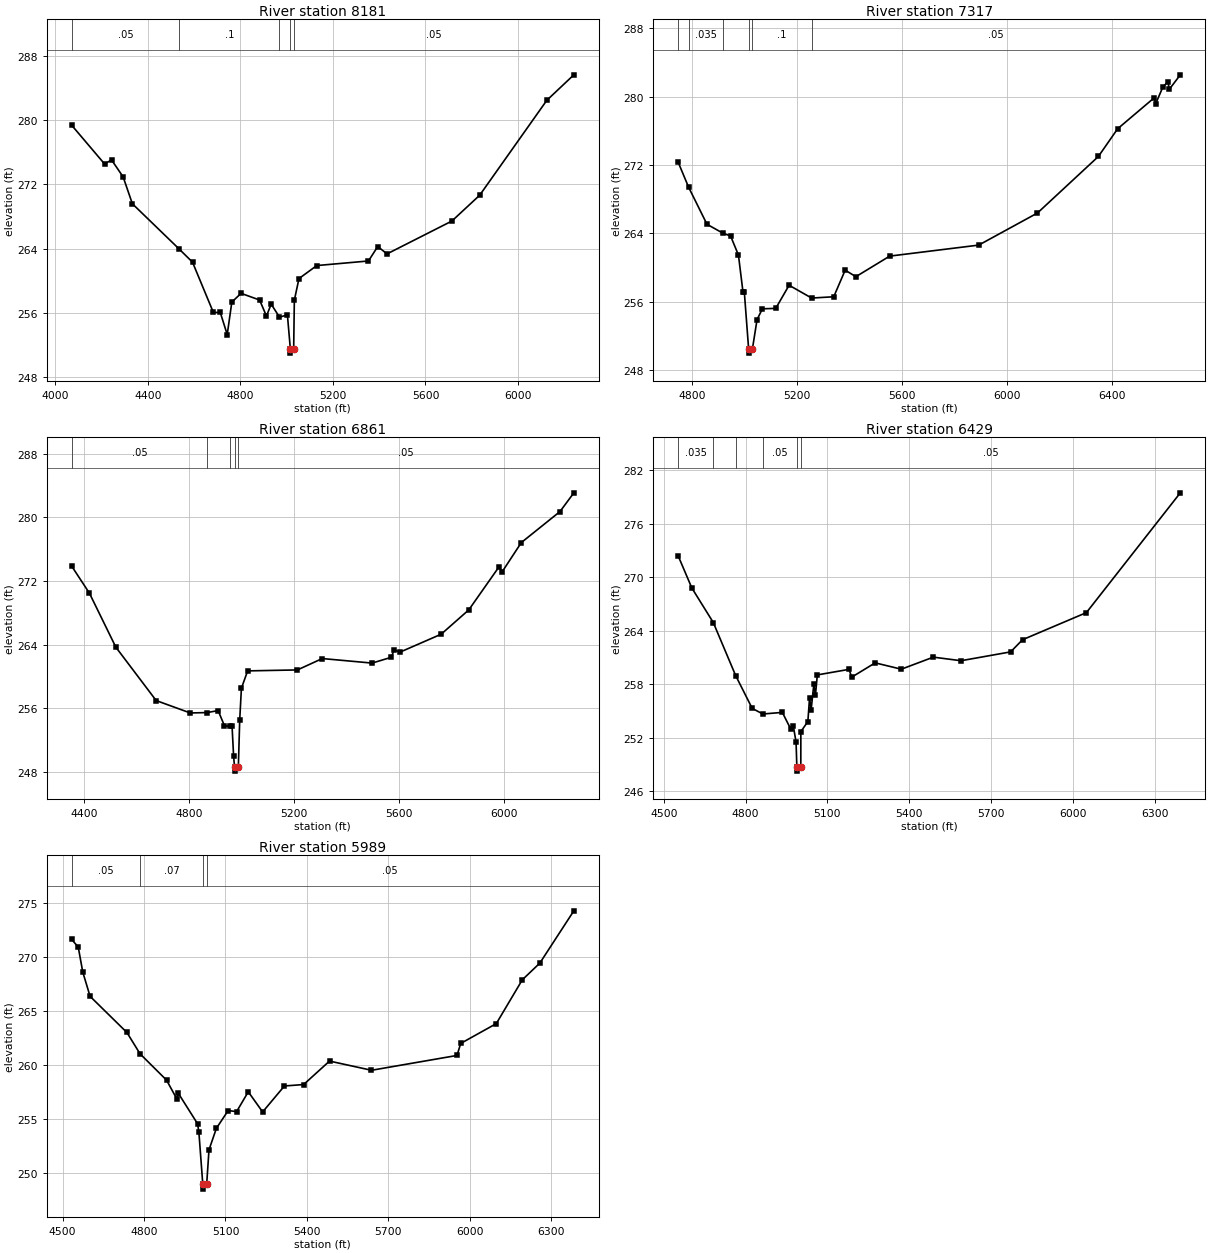
Type RM Length L Ch R = 1 ,8181    ,864,864,864
BEGIN DESCRIPTION:
XS7569
END DESCRIPTION:
XS GIS Cut Line= 3
      2457747.47     13693556.19      2456900.71     13693583.07
      2455578.45     13693502.53
#Sta/Elev= 30
  4069.9  279.36  4212.4  274.53  4242.5  275.04  4292.5  272.93  4332.5  269.58
  4535.5  263.93  4592.6  262.31  4682.7  256.06  4712.7  256.05  4742.7   253.3
  4762.7  257.35  4802.7  258.43  4882.8   257.6  4912.4   255.6  4932.8  257.09
  4968.8  255.47    5003  255.75  5015.8  251.49  5016.3  250.99  5030.1  251.49
    5033  257.57    5053  260.27  5130.1  261.89  5353.6  262.46  5393.7  264.26
  5433.8  263.34  5714.3  267.43  5834.5  270.64    6125  282.46  6241.8  285.63
#Mann= 5 ,-1 , 0
  4069.9     .05       0  4535.5      .1       0  4968.8     .05       0
  5015.8     .05       0  5030.1     .05       0
Bank Sta=5015.8,5030.1
XS Rating Curve= 0 ,0
Exp/Cntr=0.3,0.1

Type RM Length L Ch R = 1 ,7317    ,456,456,456
BEGIN DESCRIPTION:
Stream0731 14.0
END DESCRIPTION:
XS GIS Cut Line= 3
        2457475.       13693075.        2457225.       13693075.
      2455590.23     13693388.19
#Sta/Elev= 30
  4745.6  272.34  4785.9  269.38  4855.6  265.06  4917.3     264  4945.6  263.69
  4975.6  261.45  4993.1  257.08  4998.1  257.08  5014.4  250.47  5014.9  249.97
  5028.9  250.47  5046.5  253.89  5066.9  255.16  5117.8  255.21  5168.7  257.92
  5254.6  256.42  5338.9  256.57  5382.5  259.69  5423.2  258.92  5552.1  261.33
  5891.6  262.62  6115.6  266.38  6347.8     273  6421.1  276.24    6561  279.88
  6566.1  279.17  6594.2  281.17    6613  281.75  6618.1  280.86  6660.1  282.56
#Mann= 6 ,-1 , 0
  4745.6     .05       0  4785.9    .035       0  4917.3      .1       0
  5014.4     .05       0  5028.9      .1       0  5254.6     .05       0
Bank Sta=5014.4,5028.9
XS Rating Curve= 0 ,0
Exp/Cntr=0.3,0.1

Type RM Length L Ch R = 1 ,6861    ,432,432,432
BEGIN DESCRIPTION:
Stream0731 13.0
END DESCRIPTION:
XS GIS Cut Line= 3
      2457425.03     13692674.99        2456825.       13692925.
      2455625.04     13693324.99
#Sta/Elev= 30
  4353.3  273.89    4421  270.49  4521.8   263.7  4675.6  256.99  4805.6  255.43
  4869.8  255.48  4911.8  255.73  4935.6  253.85  4956.2  253.73  4964.9  253.81
  4970.8  250.03  4974.4  248.62  4974.9  248.12  4988.9  248.62  4994.1  254.51
  5000.6  258.54  5024.4  260.72  5214.2  260.84    5309  262.27  5498.8   261.7
  5572.5  262.43  5583.1   263.4  5604.2  263.06  5762.3  265.33  5867.7  268.39
  5983.6  273.83  5994.2  273.14    6068  276.85  6215.5  280.75  6268.2   283.1
#Mann= 5 ,-1 , 0
  4353.3     .05       0  4869.8      .1       0  4956.2     .05       0
  4974.4     .05       0  4988.9     .05       0
Bank Sta=4974.4,4988.9
XS Rating Curve= 0 ,0
Exp/Cntr=0.3,0.1

Type RM Length L Ch R = 1 ,6429    ,440,440,440
BEGIN DESCRIPTION:
Stream0731 12.0
END DESCRIPTION:
XS GIS Cut Line= 3
      2457374.99       13692475.        2456925.       13692525.
      2455725.01       13693225.
#Sta/Elev= 30
  4552.6  272.41  4602.9   268.8  4681.6  264.93  4763.6  258.99  4824.3  255.31
  4863.4  254.68  4934.9  254.86  4965.1  253.03  4975.2  253.32  4985.2  251.54
  4988.1  248.78  4988.6  248.28  5002.6  248.78  5002.8  252.71  5028.5  253.83
  5034.7  256.49  5040.5  255.18  5050.4  258.01  5056.2  256.77  5063.2  259.06
  5179.4  259.68  5189.4  258.81  5275.4  260.41  5371.3   259.7  5488.7  261.05
  5590.4  260.65  5772.3  261.64  5815.8     263  6050.2  266.04  6394.6  279.46
#Mann= 6 ,-1 , 0
  4552.6    .035       0  4681.6     .05       0  4763.6      .1       0
  4863.4     .05       0  4988.1     .05       0  5002.6     .05       0
Bank Sta=4988.1,5002.6
XS Rating Curve= 0 ,0
Exp/Cntr=0.3,0.1

Type RM Length L Ch R = 1 ,5989    ,474,474,474
BEGIN DESCRIPTION:
Stream0731 11.0
END DESCRIPTION:
XS GIS Cut Line= 3
      2457424.99       13692275.        2456975.       13692175.
      2455775.01     13692874.99
#Sta/Elev= 30
  4533.3  271.62  4557.6  270.91  4574.3   268.6  4601.2  266.36  4736.9  263.02
  4785.3  261.05  4882.9  258.62  4921.3  256.86  4926.4   257.4  4997.2  254.59
  5002.1   253.8  5016.3  249.05  5016.8  248.55  5030.9  249.05  5039.3  252.18
  5066.6  254.17    5110  255.81    5141  255.71    5184  257.54    5237  255.68
  5317.2  258.08  5387.9  258.21  5483.4  260.38    5638  259.53  5953.1   260.9
  5966.7  262.01  6097.8  263.84  6193.7  267.89  6258.2  269.43  6383.5  274.26
#Mann= 4 ,-1 , 0
  4533.3     .05       0  4785.3     .07       0  5016.3     .05       0
  5030.9     .05       0
Bank Sta=5016.3,5030.9
XS Rating Curve= 0 ,0
Exp/Cntr=0.3,0.1