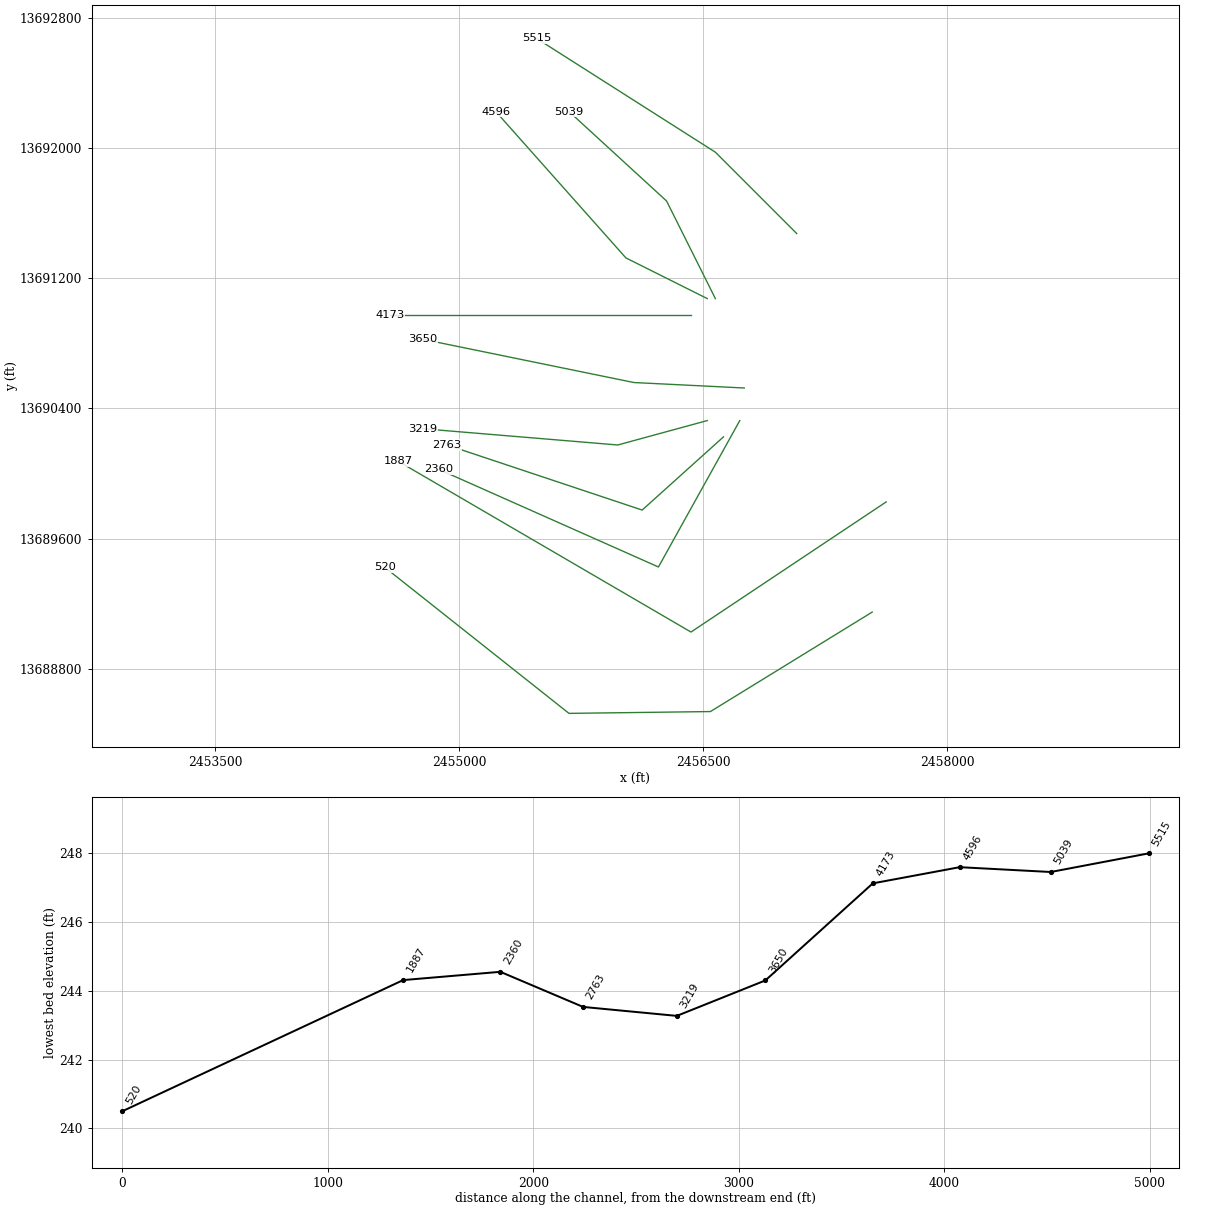
HEC-RAS study Stream0731.prj: Stream0731 Base Level Engineering

--- Stream0731.g01 (geometry) --- (continued)

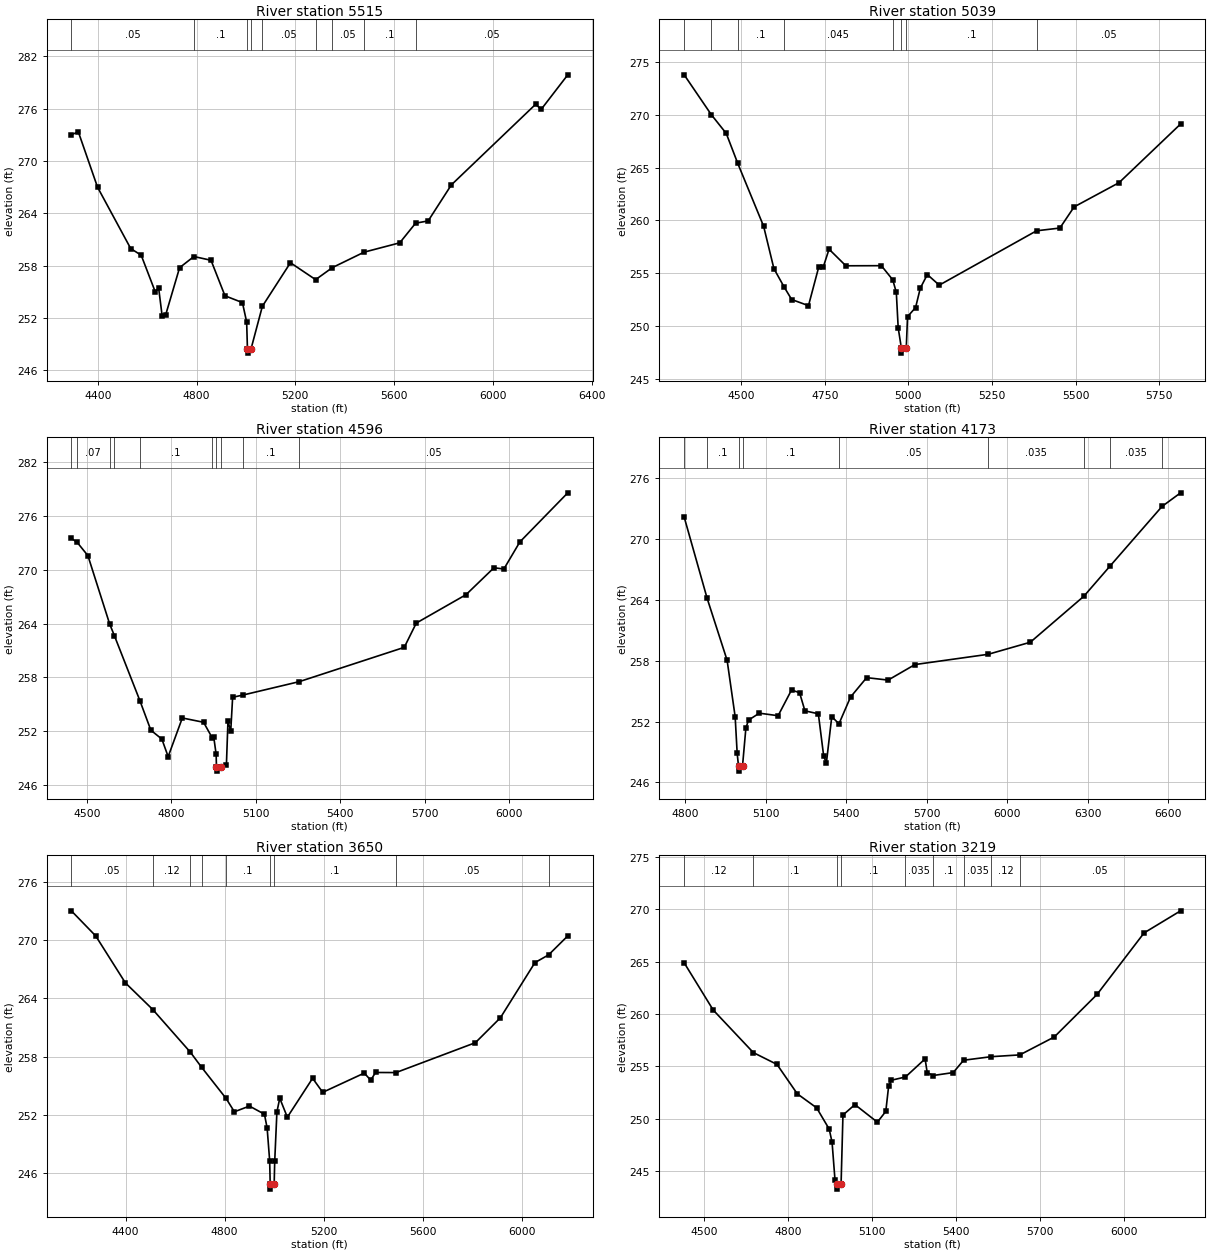
Type RM Length L Ch R = 1 ,5515    ,476,476,476
BEGIN DESCRIPTION:
Stream0731 10.0
END DESCRIPTION:
XS GIS Cut Line= 3
      2457075.03     13691474.97        2456575.       13691975.
      2455474.99     13692675.01
#Sta/Elev= 30
  4292.7  273.02    4321  273.34  4398.8     267  4533.2  259.97  4575.6  259.21
  4632.2  255.04  4646.3  255.45  4660.4  252.27  4674.6  252.36  4731.1  257.78
  4789.1  259.06  4858.4  258.63    4915  254.56  4985.7  253.78  5002.8  251.56
    5006  248.49  5006.5  247.99  5020.7  248.49  5066.5  253.36  5180.2  258.35
  5282.2  256.41    5350  257.79  5478.6  259.56    5623  260.63  5687.2  262.88
  5738.1  263.14  5832.1  267.27  6173.3   276.5  6196.2  275.93  6303.7  279.88
#Mann= 9 ,-1 , 0
  4292.7     .05       0  4789.1      .1       0    5006     .05       0
  5020.7      .1       0  5066.5     .05       0  5282.2      .1       0
    5350     .05       0  5478.6      .1       0  5687.2     .05       0
Bank Sta=5006,5020.7
XS Rating Curve= 0 ,0
Exp/Cntr=0.3,0.1

Type RM Length L Ch R = 1 ,5039    ,443,443,443
BEGIN DESCRIPTION:
Stream0731 9.0
END DESCRIPTION:
XS GIS Cut Line= 3
      2456575.02     13691074.97        2456275.       13691675.
        2455675.       13692225.
#Sta/Elev= 30
  4329.4  273.77  4410.6     270  4455.2  268.23  4489.6   265.4    4567  259.45
  4597.8  255.44  4627.7  253.74  4650.9  252.52  4701.2  251.94  4731.9   255.6
  4745.9  255.64  4762.7  257.28    4813  255.71  4919.2  255.72  4953.3  254.38
  4963.9  253.19  4969.5  249.85  4978.9  247.95  4979.4  247.45  4993.7  247.95
  4997.5   250.9  5021.5  251.76  5035.7   253.6  5056.7  254.88  5092.4  253.88
  5383.4  259.02  5453.2  259.28  5495.7  261.28  5630.1  263.57  5814.2  269.12
#Mann= 8 ,-1 , 0
  4329.4     .05       0  4410.6     .07       0  4489.6      .1       0
  4627.7    .045       0  4953.3      .1       0  4978.9     .05       0
  4993.7      .1       0  5383.4     .05       0
Bank Sta=4978.9,4993.7
XS Rating Curve= 0 ,0
Exp/Cntr=0.3,0.1

Type RM Length L Ch R = 1 ,4596    ,423,423,423
BEGIN DESCRIPTION:
Stream0731 8.0
END DESCRIPTION:
XS GIS Cut Line= 3
      2456525.02     13691074.99        2456025.       13691325.
        2455225.       13692225.
#Sta/Elev= 30
  4444.7  273.46  4464.6  273.05  4503.4  271.55  4580.7  263.95  4597.4  262.66
  4687.9  255.44    4727  252.14  4766.2  251.15  4788.5   249.2  4838.8   253.5
  4914.3  253.02  4944.9   251.3  4950.6  251.34    4959  249.45    4960  248.09
  4960.5  247.59  4974.8  248.09  4995.4  248.29  5000.9  253.13  5010.8  252.04
  5017.5   255.8    5053  256.04  5254.4  257.54  5627.1  261.35  5669.8  264.05
  5846.6  267.21  5945.7   270.2  5980.9  270.06  6037.7  273.07  6207.9  278.53
#Mann= 10 ,-1 , 0
  4444.7     .05       0  4464.6     .07       0  4580.7      .1       0
  4597.4     .07       0  4687.9      .1       0  4944.9     .05       0
    4960     .05       0  4974.8     .05       0    5053      .1       0
  5254.4     .05       0
Bank Sta=4960,4974.8
XS Rating Curve= 0 ,0
Exp/Cntr=0.3,0.1

Type RM Length L Ch R = 1 ,4173    ,523,523,523
BEGIN DESCRIPTION:
Stream0731 7.0
END DESCRIPTION:
XS GIS Cut Line= 3
      2456424.97       13690975.        2456225.       13690975.
      2454574.97       13690975.
#Sta/Elev= 30
  4795.8  272.15  4881.4  264.14  4955.8  258.04  4985.8  252.48  4993.3  248.87
  4998.3  247.62  4998.8  247.12  5013.2  247.62  5025.8  251.38  5035.8  252.15
  5075.8  252.83  5145.8  252.58  5195.8  255.11  5225.8  254.85  5245.8  253.06
  5295.8  252.77  5315.8  248.58  5325.8  247.93  5345.8  252.49  5372.6  251.78
  5415.8  254.42  5475.8  256.33  5555.8  256.09  5655.8  257.62  5928.5  258.63
  6085.8  259.82  6285.3  264.35  6383.7  267.35  6576.6   273.2  6645.8  274.54
#Mann= 9 ,-1 , 0
  4795.8     .07       0  4881.4      .1       0  4998.3     .05       0
  5013.2      .1       0  5372.6     .05       0  5928.5    .035       0
  6285.3     .05       0  6383.7    .035       0  6576.6     .05       0
Bank Sta=4998.3,5013.2
XS Rating Curve= 0 ,0
Exp/Cntr=0.3,0.1

Type RM Length L Ch R = 1 ,3650    ,431,431,431
BEGIN DESCRIPTION:
Stream0731 6.0
END DESCRIPTION:
XS GIS Cut Line= 3
      2456752.89     13690525.34      2456074.12     13690558.95
      2454774.99       13690825.
#Sta/Elev= 30
  4181.1  273.05  4279.7  270.45  4399.3  265.61  4510.1  262.85  4662.1  258.44
  4707.5  256.88  4806.2  253.67  4839.8  252.29  4900.6  252.88  4961.2  252.04
  4972.1  250.61  4982.3  247.24  4984.5   244.8    4985   244.3  5000.5   244.8
  5002.7  247.16  5011.6  252.28  5023.1  253.69  5053.7  251.73  5155.8  255.75
  5196.7   254.3  5364.7  256.29  5390.6  255.55  5410.1  256.35  5492.7  256.34
  5813.6  259.43  5914.5     262  6054.1   267.7  6109.3   268.5  6186.8  270.46
#Mann= 9 ,-1 , 0
  4181.1     .05       0  4510.1     .12       0  4662.1     .05       0
  4707.5    .035       0  4806.2      .1       0  4984.5     .05       0
  5000.5      .1       0  5492.7     .05       0  6109.3    .035       0
Bank Sta=4984.5,5000.5
XS Rating Curve= 0 ,0
Exp/Cntr=0.3,0.1

Type RM Length L Ch R = 1 ,3219    ,456,456,456
BEGIN DESCRIPTION:
Stream0731 5.0
END DESCRIPTION:
XS GIS Cut Line= 3
      2456525.01       13690325.        2455975.       13690175.
      2454774.96       13690275.
#Sta/Elev= 30
  4429.5   264.9  4533.2  260.39  4676.7  256.32  4761.2  255.19  4833.8  252.38
  4902.9  251.04  4947.8  249.01  4958.1  247.75  4968.5  244.16  4974.3  243.77
  4974.8  243.27  4990.3  243.77    4997  250.35  5039.7  251.35    5120  249.67
  5150.1   250.7  5160.2   253.1  5170.2  253.68  5220.4  253.99  5290.6  255.72
  5298.1  254.41  5319.4  254.13    5391  254.41  5428.2  255.59  5527.2  255.93
  5629.1   256.1  5752.2  257.81  5905.2  261.88  6073.3  267.76  6203.8  269.87
#Mann= 9 ,-1 , 0
  4429.5     .12       0  4676.7      .1       0  4974.3     .05       0
  4990.3      .1       0  5220.4    .035       0  5319.4      .1       0
  5428.2    .035       0  5527.2     .12       0  5629.1     .05       0
Bank Sta=4974.3,4990.3
XS Rating Curve= 0 ,0
Exp/Cntr=0.3,0.1

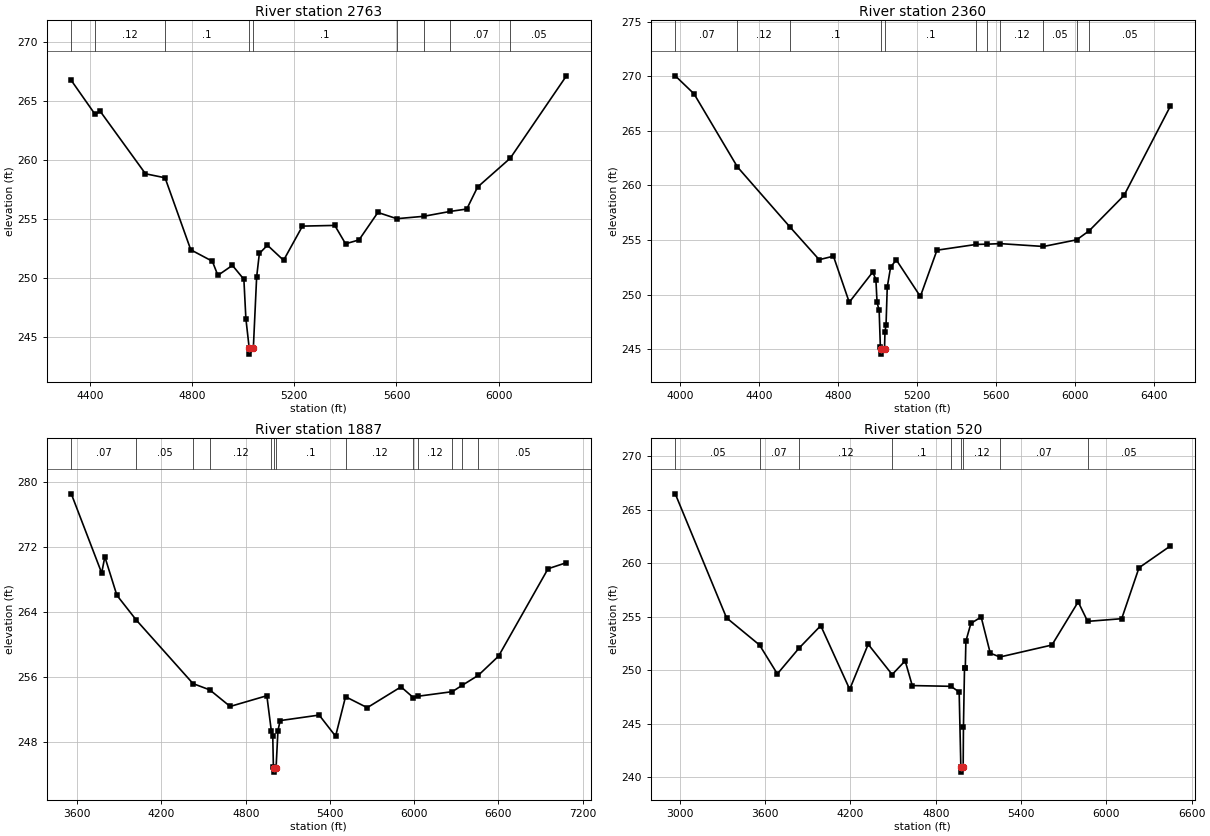
Type RM Length L Ch R = 1 ,2763    ,403,403,403
BEGIN DESCRIPTION:
Stream0731 4.0
END DESCRIPTION:
XS GIS Cut Line= 3
      2456624.96     13690224.97        2456125.       13689775.
      2454925.04     13690174.99
#Sta/Elev= 30
  4327.7  266.75  4420.5  263.88  4440.9  264.13    4618  258.83  4694.6  258.49
  4795.2  252.38  4879.6  251.41  4901.3  250.21  4958.1  251.06    5003  249.88
  5010.9  246.53  5023.9  244.03  5024.4  243.53    5040  244.03    5053  250.08
  5063.6  252.07  5095.2  252.77  5158.4  251.49  5232.2  254.39  5358.7  254.45
  5400.9  252.89  5453.6  253.22  5527.4  255.55  5601.3  255.02    5706  255.22
  5811.2  255.64  5875.2  255.84  5917.4   257.7  6045.3  260.15  6265.2  267.14
#Mann= 9 ,-1 , 0
  4327.7     .07       0  4420.5     .12       0  4694.6      .1       0
  5023.9     .05       0    5040      .1       0  5601.3    .035       0
    5706     .12       0  5811.2     .07       0  6045.3     .05       0
Bank Sta=5023.9,5040
XS Rating Curve= 0 ,0
Exp/Cntr=0.3,0.1

Type RM Length L Ch R = 1 ,2360    ,473,473,473
BEGIN DESCRIPTION:
Stream0731 3.0
END DESCRIPTION:
XS GIS Cut Line= 3
        2456725.     13690325.01        2456225.       13689425.
        2454875.       13690025.
#Sta/Elev= 30
  3976.5  270.04  4071.5  268.39  4291.4  261.69  4557.4  256.19  4705.2   253.2
  4777.3  253.52  4857.4   249.3  4976.3  252.07  4992.3  251.38  4998.1   249.3
  5008.8  248.55    5015  245.17  5019.9  245.05  5020.4  244.55    5036  245.05
  5038.2  246.56  5043.7  247.26  5049.8  250.69  5066.9  252.53  5095.7  253.18
  5217.4  249.83  5301.5  254.07  5501.1   254.6  5553.2  254.62  5622.6  254.67
  5840.8  254.41  6008.8  255.02  6072.3  255.85  6248.8  259.09  6483.4  267.27
#Mann= 11 ,-1 , 0
  3976.5     .07       0  4291.4     .12       0  4557.4      .1       0
  5019.9     .05       0    5036      .1       0  5501.1     .12       0
  5553.2      .1       0  5622.6     .12       0  5840.8     .05       0
  6008.8     .07       0  6072.3     .05       0
Bank Sta=5019.9,5036
XS Rating Curve= 0 ,0
Exp/Cntr=0.3,0.1

Type RM Length L Ch R = 1 ,1887    ,1367,1367,1367
BEGIN DESCRIPTION:
Stream0731 2.0
END DESCRIPTION:
XS GIS Cut Line= 3
        2457625.       13689825.        2456425.       13689025.
      2454624.99     13690075.01
#Sta/Elev= 30
  3557.8  278.55  3774.1  268.81  3796.7   270.8  3882.3  266.07  4021.1  263.01
  4424.7   255.2    4544  254.43    4689  252.39  4950.4  253.71  4982.8  249.31
  4992.5  248.71    4997  244.97  4999.7  244.81  5000.2  244.31    5016  244.81
  5029.4  249.41  5045.1  250.65  5322.9  251.33  5439.9  248.73  5510.8  253.59
  5665.3  252.24  5905.9   254.8  5992.8  253.49  6028.7  253.65  6270.9  254.21
  6340.4  254.98  6456.3  256.22  6600.5  258.58  6952.8  269.33  7083.9  270.08
#Mann= 13 ,-1 , 0
  3557.8     .07       0  4021.1     .05       0  4424.7     .07       0
    4544     .12       0  4982.8      .1       0  4999.7     .05       0
    5016      .1       0  5510.8     .12       0  5992.8     .07       0
  6028.7     .12       0  6270.9     .05       0  6340.4     .12       0
  6456.3     .05       0
Bank Sta=4999.7,5016
XS Rating Curve= 0 ,0
Exp/Cntr=0.3,0.1

Type RM Length L Ch R = 1 ,520     ,0,0,0
BEGIN DESCRIPTION:
Stream0731 1.0
END DESCRIPTION:
XS GIS Cut Line= 4
      2457539.12     13689147.68      2456544.54     13688536.14
        2455675.       13688525.      2454541.88     13689423.23
#Sta/Elev= 30
  2967.4  266.51    3328  254.92  3560.3  252.38  3685.5  249.68  3837.6  252.08
  3990.8  254.19  4194.5  248.24  4324.5  252.45  4493.1  249.62  4584.5   250.9
  4634.5  248.59  4906.6  248.52  4964.5  247.99  4976.3     241  4976.8   240.5
  4992.7     241  4994.6   244.7  5002.1  250.23  5007.7  250.23  5011.8  252.74
    5047   254.4  5119.2     255  5183.2  251.62  5251.2  251.26  5617.1  252.38
  5801.7  256.41  5868.3  254.59  6107.8  254.84  6229.6   259.6  6450.5  261.64
#Mann= 9 ,-1 , 0
  2967.4     .05       0  3560.3     .07       0  3837.6     .12       0
  4493.1      .1       0  4906.6     .12       0  4976.3     .05       0
  4992.7     .12       0  5251.2     .07       0  5868.3     .05       0
Bank Sta=4976.3,4992.7
XS Rating Curve= 0 ,0
Exp/Cntr=0.3,0.1

Chan Stop Cuts=-1
Use User Specified Reach Order=0
Composite Channel Slope=5