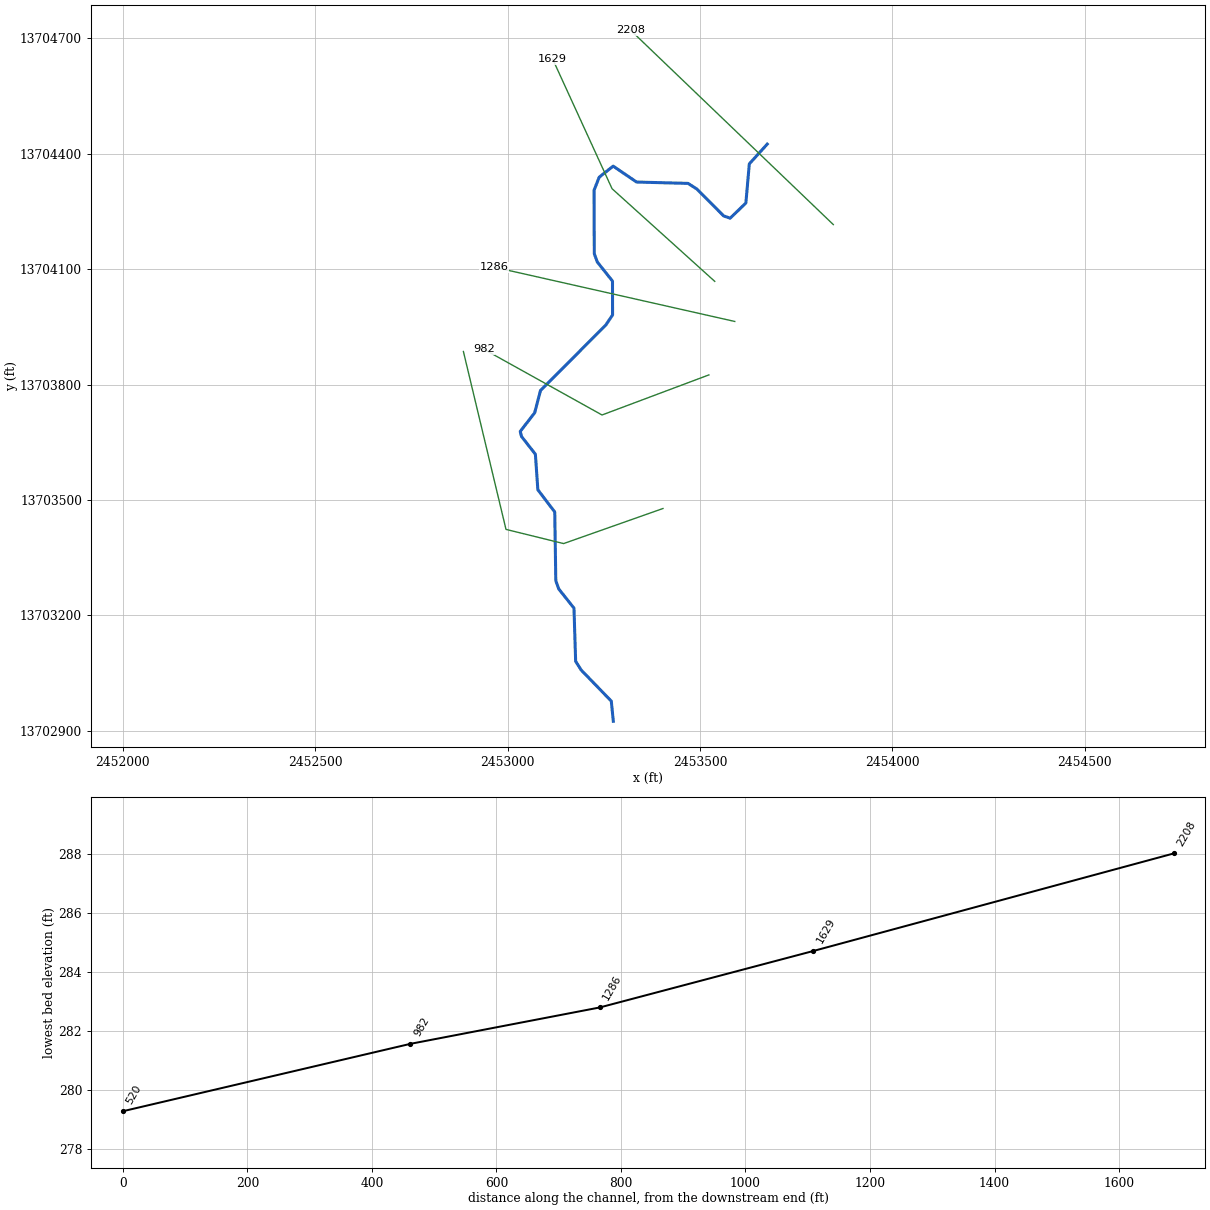
--- Stream0732.prj (project) ---

Proj Title=Stream0732 Base Level Engineering
Current Plan=p01
Default Exp/Contr=0.3,0.1
English Units
Geom File=g01
Flow File=f01
Plan File=p01
BEGIN DESCRIPTION:
Stream0732
END DESCRIPTION:

--- Stream0732.p01 (plan) ---

Plan Title=Multiple Run
Short Identifier=Multiple
Geom File=g01
Flow File=f01
Subcritical Flow
K Sum by GR= 0
Std Step Tol= 0.01
Critical Tol= 0.01
Num of Std Step Trials= 20
Max Error Tol= 0.3
Flow Tol Ratio= 0.001
Split Flow NTrial= 30
Split Flow Tol= 0.02
Split Flow Ratio= 0.02
Log Output Level= 0
Friction Slope Method= 1
Unsteady Friction Slope Method= 2
Unsteady Bridges Friction Slope Method= 1
Parabolic Critical Depth
Global Vel Dist=  1 , 1 , 1
Global Log Level= 0
CheckData=True
Encroach Param= -1, 0, 0, 0
BEGIN DESCRIPTION:
Multiple Run
END DESCRIPTION:

--- Stream0732.f01 (steady flow) ---

Flow Title=Multiple
Number of Profiles=7
Profile Names=10-year,25-year,50-year,1pct_min,100-year,1pct_plu,500-year
River Rch & RM= Stream0732,Reach-1,2208
     396     614     802     509    1015    2025    1606
Boundary for River Rch & Prof#=Stream0732,Reach-1,1
Up Type=0
Dn Type=3
Dn Slope=0.005
Boundary for River Rch & Prof#=Stream0732,Reach-1,2
Up Type=0
Dn Type=3
Dn Slope=0.005
Boundary for River Rch & Prof#=Stream0732,Reach-1,3
Up Type=0
Dn Type=3
Dn Slope=0.005
Boundary for River Rch & Prof#=Stream0732,Reach-1,4
Up Type=0
Dn Type=3
Dn Slope=0.005
Boundary for River Rch & Prof#=Stream0732,Reach-1,5
Up Type=0
Dn Type=3
Dn Slope=0.005
Boundary for River Rch & Prof#=Stream0732,Reach-1,6
Up Type=0
Dn Type=3
Dn Slope=0.005
Boundary for River Rch & Prof#=Stream0732,Reach-1,7
Up Type=0
Dn Type=3
Dn Slope=0.005

--- Stream0732.g01 (geometry) ---

Geom Title=Existing Conditions

River Reach=Stream0732,Reach-1
Reach XY= 30
      2453675.00     13704425.00      2453628.39     13704373.59
      2453619.50     13704271.98      2453578.62     13704232.48
      2453561.80     13704238.39      2453491.77     13704308.50
      2453469.14     13704322.92      2453335.43     13704326.41
      2453274.65     13704367.79      2453238.36     13704339.14
      2453224.95     13704305.24      2453225.52     13704140.22
      2453233.15     13704118.94      2453272.84     13704069.02
      2453273.04     13703980.89      2453255.42     13703954.84
      2453085.75     13703784.68      2453070.55     13703726.65
      2453033.04     13703678.32      2453036.45     13703665.10
      2453072.45     13703619.11      2453078.85     13703526.60
      2453122.74     13703469.06      2453125.52     13703290.22
      2453133.14     13703268.94      2453172.73     13703219.06
      2453177.07     13703080.86      2453191.44     13703058.24
      2453269.67     13702977.51      2453275.00     13702925.00

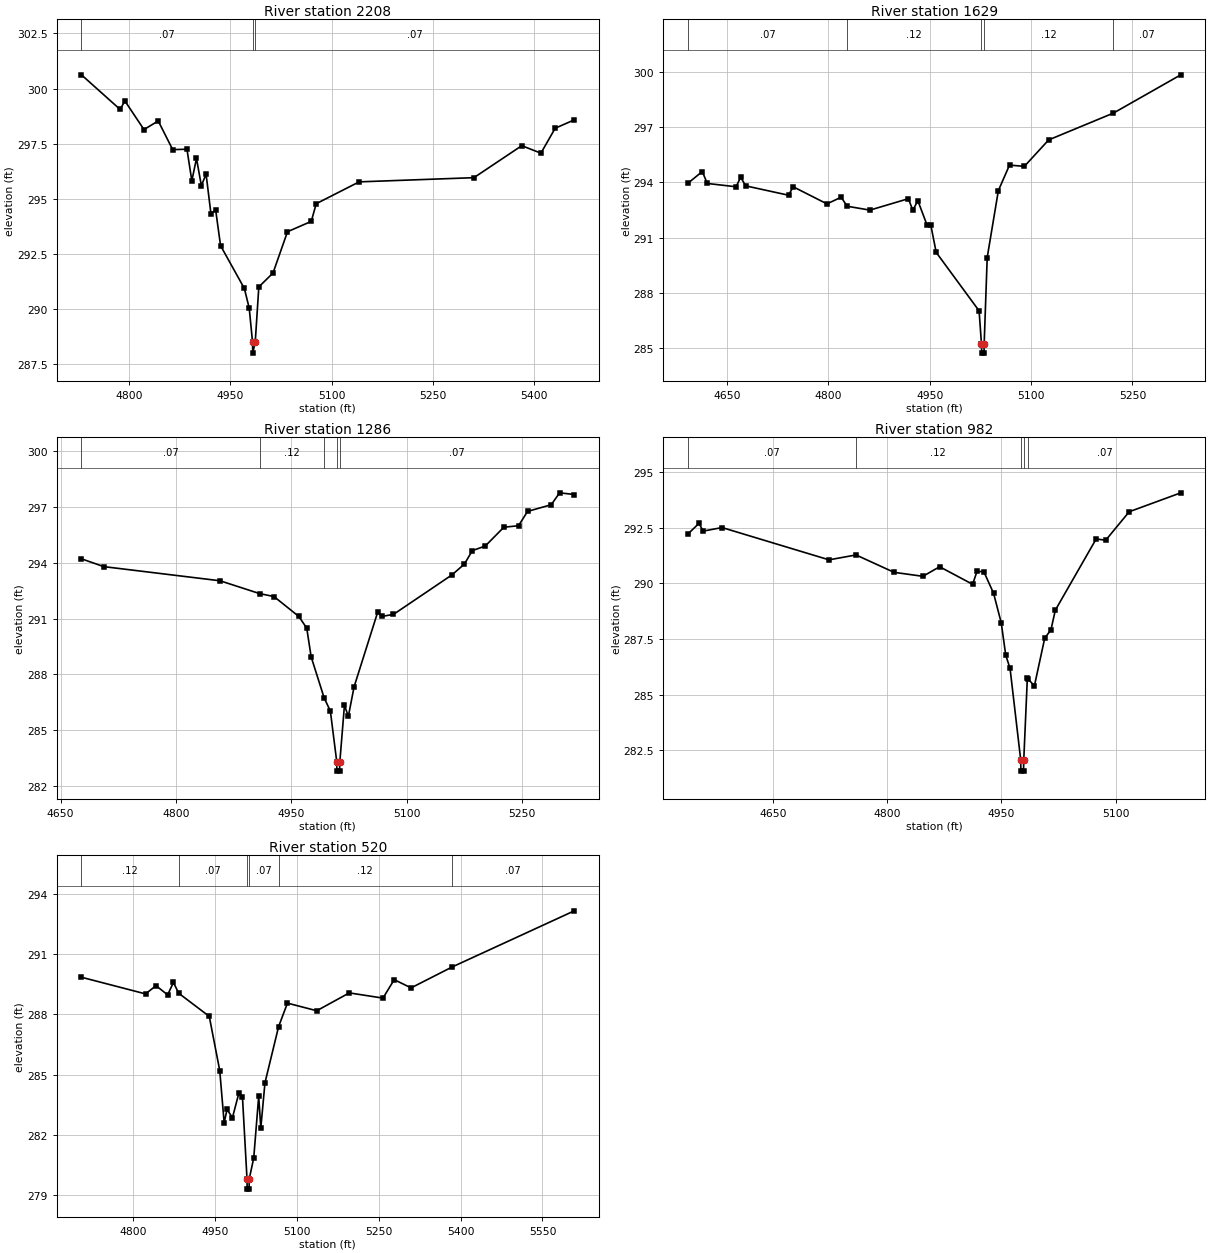
Type RM Length L Ch R = 1,2208,579,579,579
BEGIN DESCRIPTION:
XS7591
END DESCRIPTION:
XS GIS Cut Line= 2
      2453846.71     13704215.87      2453320.45     13704720.48
#Sta/Elev= 30
  4729.9  300.62  4787.2  299.05  4794.1  299.44  4822.4  298.14  4843.5  298.53
  4864.9  297.23  4886.0  297.25  4893.2  295.82  4900.1  296.83  4907.3  295.60
  4914.3  296.12  4921.5  294.32  4928.4  294.51  4935.7  292.88  4970.9  290.94
  4978.1  290.05  4983.0  288.51  4983.3  288.01  4987.0  288.51  4992.3  291.01
  5013.3  291.64  5034.7  293.51  5069.9  293.98  5077.2  294.78  5140.7  295.77
  5310.5  295.96  5381.3  297.41  5409.6  297.07  5430.7  298.20  5459.0  298.58
#Mann=3,-1,0
  4729.9    0.07       0  4983.0    0.05       0  4987.0    0.07       0
Bank Sta=4983,4987
Exp/Cntr=0.3,0.1

Type RM Length L Ch R = 1,1629,343,343,343
BEGIN DESCRIPTION:
XS7590
END DESCRIPTION:
XS GIS Cut Line= 3
      2453538.58     13704068.28      2453271.66     13704309.16
      2453117.59     13704645.50
#Sta/Elev= 30
  4592.1  293.95  4613.4  294.59  4620.8  293.94  4663.4  293.76  4670.2  294.28
  4677.6  293.81  4741.1  293.30  4747.9  293.76  4797.9  292.83  4818.9  293.19
  4827.9  292.70  4861.5  292.49  4918.3  293.11  4925.0  292.49  4932.5  293.00
  4946.0  291.68  4951.6  291.68  4959.6  290.19  5023.1  287.01  5026.6  285.21
  5026.9  284.71  5030.4  284.71  5030.6  285.21  5035.1  289.91  5051.6  293.55
  5068.1  294.94  5090.1  294.87  5126.1  296.31  5222.0  297.77  5321.6  299.85
#Mann=5,-1,0
  4592.1    0.07       0  4827.9    0.12       0  5026.6    0.05       0
  5030.6    0.12       0  5222.0    0.07       0
Bank Sta=5026.6,5030.6
Exp/Cntr=0.3,0.1

Type RM Length L Ch R = 1,1286,304,304,304
BEGIN DESCRIPTION:
XS7589
END DESCRIPTION:
XS GIS Cut Line= 2
      2453590.67     13703964.11      2452965.69     13704105.16
#Sta/Elev= 30
  4677.2  294.22  4706.3  293.80  4857.3  293.04  4908.8  292.35  4927.5  292.19
  4959.8  291.12  4970.1  290.49  4975.8  288.95  4992.7  286.74  5000.8  286.03
  5009.1  283.30  5009.3  282.80  5012.8  282.80  5013.1  283.30  5019.1  286.34
  5024.2  285.75  5031.6  287.33  5062.3  291.35  5067.4  291.12  5082.8  291.23
  5159.0  293.36  5175.1  293.94  5185.3  294.66  5202.2  294.91  5226.3  295.92
  5245.4  296.00  5257.1  296.77  5287.9  297.13  5298.8  297.77  5317.9  297.68
#Mann=5,-1,0
  4677.2    0.07       0  4908.8    0.12       0  4992.7    0.07       0
  5009.1    0.05       0  5013.1    0.07       0
Bank Sta=5009.1,5013.1
Exp/Cntr=0.3,0.1

Type RM Length L Ch R = 1,982,462,462,462
BEGIN DESCRIPTION:
XS7588
END DESCRIPTION:
XS GIS Cut Line= 3
      2453523.44     13703825.23      2453245.62     13703721.05
      2452938.72     13703891.79
#Sta/Elev= 30
  4537.8  292.22  4552.4  292.70  4557.8  292.35  4582.7  292.51  4723.3  291.06
  4758.8  291.28  4808.7  290.50  4846.7  290.32  4868.7  290.75  4912.1  289.96
  4917.8  290.54  4926.8  290.53  4939.6  289.56  4949.7  288.23  4955.6  286.78
  4961.3  286.18  4975.3  282.07  4975.5  281.57  4979.0  281.57  4979.3  282.07
  4984.0  285.74  4985.2  285.70  4993.3  285.40  5006.9  287.55  5015.0  287.91
  5020.8  288.80  5074.5  292.00  5087.0  291.94  5117.9  293.22  5185.7  294.07
#Mann=5,-1,0
  4537.8    0.07       0  4758.8    0.12       0  4975.3    0.05       0
  4979.3    0.12       0  4985.2    0.07       0
Bank Sta=4975.3,4979.3
Exp/Cntr=0.3,0.1

Type RM Length L Ch R = 1,520,0,0,0
BEGIN DESCRIPTION:
XS7587
END DESCRIPTION:
XS GIS Cut Line= 4
      2453404.01     13703477.99      2453145.79     13703386.85
      2452996.05     13703423.74      2452885.36     13703886.02
#Sta/Elev= 30
  4704.9  289.85  4822.4  289.02  4841.7  289.43  4862.9  288.97  4873.5  289.59
  4883.3  289.05  4939.2  287.90  4958.4  285.20  4966.5  282.60  4971.8  283.26
  4981.7  282.85  4993.5  284.08  5000.1  283.86  5008.4  279.79  5008.7  279.29
  5012.2  279.29  5012.4  279.79  5020.7  280.84  5029.8  283.91  5033.7  282.34
  5041.3  284.59  5066.3  287.39  5082.5  288.56  5136.2  288.18  5195.9  289.07
  5257.6  288.81  5278.2  289.73  5309.1  289.32  5384.3  290.36  5608.3  293.16
#Mann=6,-1,0
  4704.9    0.12       0  4883.3    0.07       0  5008.4    0.05       0
  5012.4    0.07       0  5066.3    0.12       0  5384.3    0.07       0
Bank Sta=5008.4,5012.4
Exp/Cntr=0.3,0.1

Chan Stop Cuts=-1