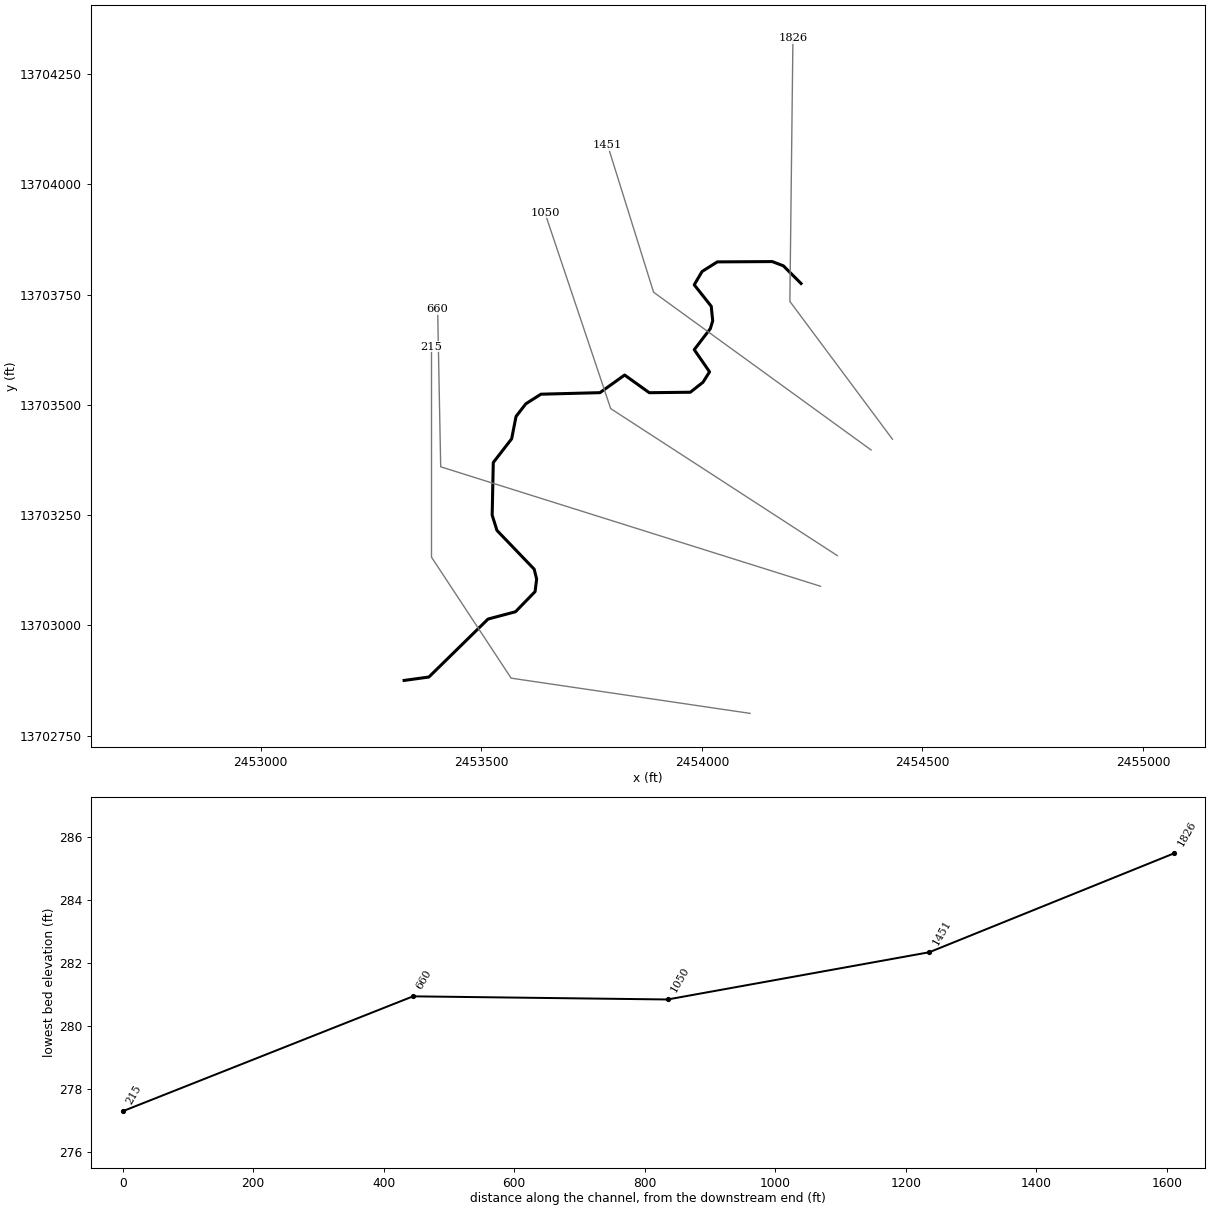
--- Stream0733.prj (project) ---

Proj Title=Stream0733 Base Level Engineering
Current Plan=p01
Default Exp/Contr=0.3,0.1
English Units
Geom File=g01
Flow File=f01
Plan File=p01
BEGIN DESCRIPTION:
Stream0733
END DESCRIPTION:

--- Stream0733.p01 (plan) ---

Plan Title=Multiple Run
Short Identifier=Multiple
Geom File=g01
Flow File=f01
Subcritical Flow
K Sum by GR= 0
Std Step Tol= 0.01
Critical Tol= 0.01
Num of Std Step Trials= 20
Max Error Tol= 0.3
Flow Tol Ratio= 0.001
Split Flow NTrial= 30
Split Flow Tol= 0.02
Split Flow Ratio= 0.02
Log Output Level= 0
Friction Slope Method= 1
Unsteady Friction Slope Method= 2
Unsteady Bridges Friction Slope Method= 1
Parabolic Critical Depth
Global Vel Dist=  1 , 1 , 1
Global Log Level= 0
CheckData=True
Encroach Param= -1, 0, 0, 0
BEGIN DESCRIPTION:
Multiple Run
END DESCRIPTION:

--- Stream0733.f01 (steady flow) ---

Flow Title=Multiple
Number of Profiles=7
Profile Names=10-year,25-year,50-year,1pct_min,100-year,1pct_plu,500-year
River Rch & RM= Stream0733,Reach-1,1826
     477     747     984     629    1254    2502    2014
Boundary for River Rch & Prof#=Stream0733,Reach-1,1
Up Type=0
Dn Type=3
Dn Slope=0.005
Boundary for River Rch & Prof#=Stream0733,Reach-1,2
Up Type=0
Dn Type=3
Dn Slope=0.005
Boundary for River Rch & Prof#=Stream0733,Reach-1,3
Up Type=0
Dn Type=3
Dn Slope=0.005
Boundary for River Rch & Prof#=Stream0733,Reach-1,4
Up Type=0
Dn Type=3
Dn Slope=0.005
Boundary for River Rch & Prof#=Stream0733,Reach-1,5
Up Type=0
Dn Type=3
Dn Slope=0.005
Boundary for River Rch & Prof#=Stream0733,Reach-1,6
Up Type=0
Dn Type=3
Dn Slope=0.005
Boundary for River Rch & Prof#=Stream0733,Reach-1,7
Up Type=0
Dn Type=3
Dn Slope=0.005

--- Stream0733.g01 (geometry) ---

Geom Title=Existing Conditions

River Reach=Stream0733,Reach-1
Reach XY= 30
      2454225.00     13703775.00      2454184.98     13703814.96
      2454159.84     13703824.66      2454035.10     13703823.97
      2454000.53     13703802.16      2453982.82     13703771.98
      2454021.35     13703723.37      2454024.72     13703690.36
      2454019.34     13703672.71      2453982.84     13703624.90
      2454017.55     13703574.75      2454002.69     13703551.15
      2453973.97     13703528.46      2453880.90     13703527.36
      2453825.00     13703567.44      2453769.14     13703527.47
      2453635.29     13703524.00      2453601.09     13703502.30
      2453578.84     13703473.61      2453568.85     13703422.86
      2453527.23     13703369.07      2453524.68     13703249.89
      2453535.50     13703215.21      2453619.93     13703127.26
      2453625.50     13703104.77      2453621.99     13703076.43
      2453577.61     13703030.75      2453515.34     13703014.21
      2453381.21     13702882.76      2453325.00     13702875.00

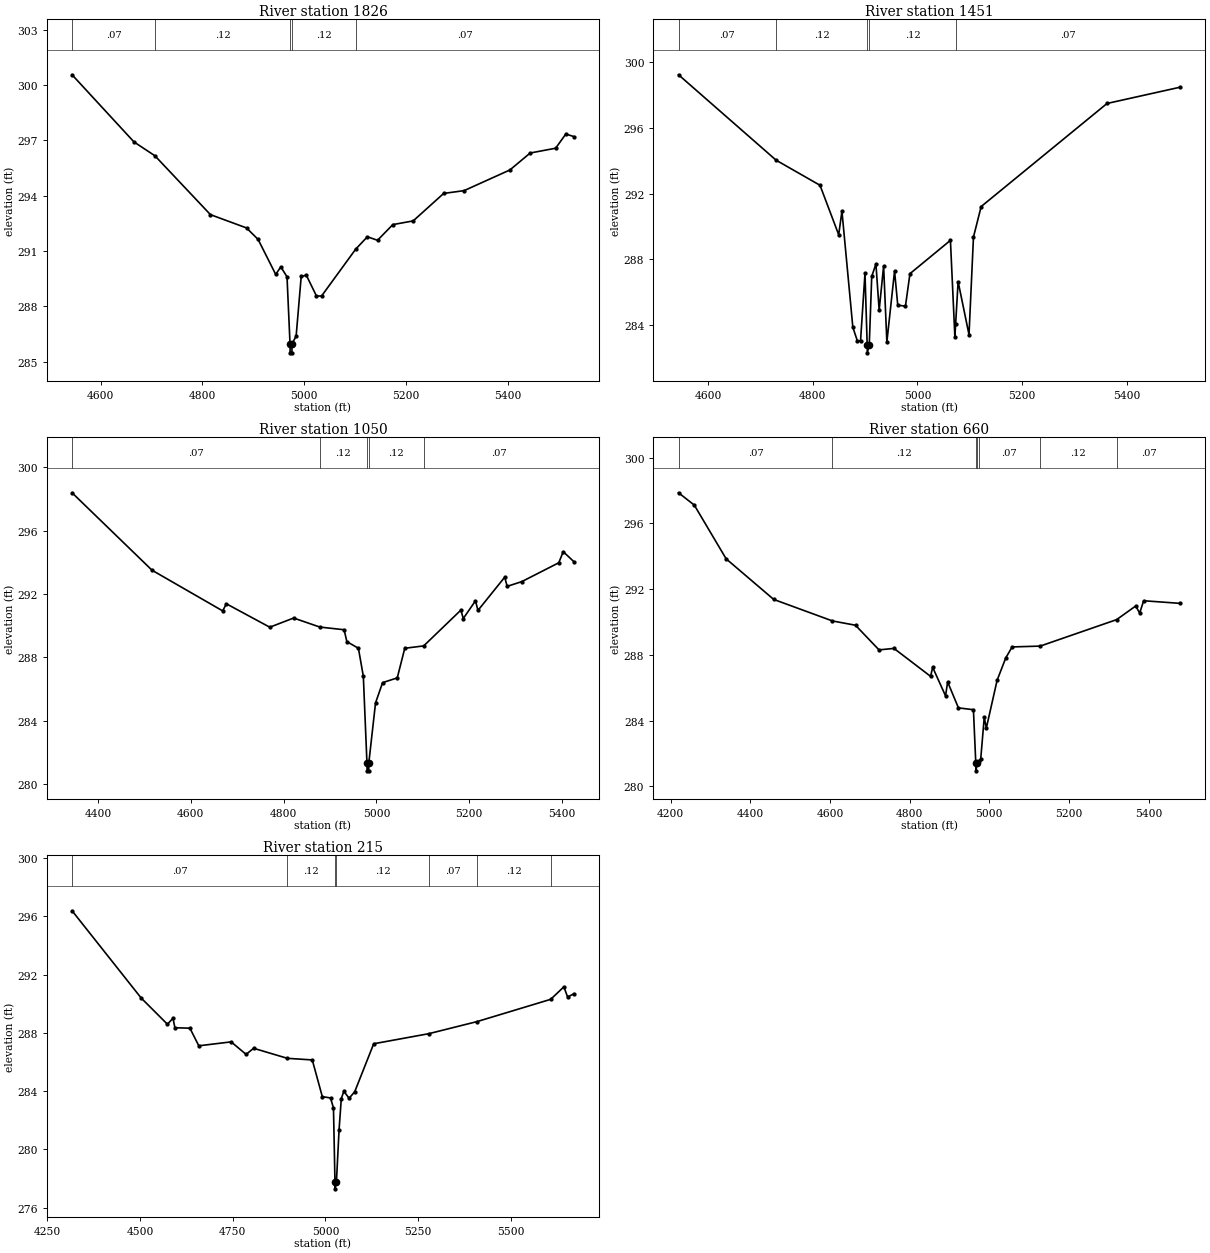
Type RM Length L Ch R = 1,1826,375,375,375
BEGIN DESCRIPTION:
XS7596
END DESCRIPTION:
XS GIS Cut Line= 3
      2454432.31     13703421.84      2454199.65     13703734.38
      2454206.59     13704330.81
#Sta/Elev= 30
  4544.0  300.55  4665.7  296.91  4706.8  296.16  4815.9  292.97  4886.8  292.25
  4909.5  291.63  4944.2  289.73  4954.2  290.14  4966.4  289.60  4972.3  285.98
  4972.5  285.48  4976.0  285.48  4976.3  285.98  4984.3  286.38  4994.3  289.62
  5004.3  289.69  5024.3  288.56  5034.3  288.56  5101.4  291.10  5124.3  291.77
  5144.3  291.58  5174.3  292.43  5214.3  292.63  5274.3  294.12  5314.3  294.27
  5404.3  295.39  5444.3  296.31  5494.3  296.57  5514.3  297.34  5530.1  297.20
#Mann=5,-1,0
  4544.0    0.07       0  4706.8    0.12       0  4972.3    0.05       0
  4976.3    0.12       0  5101.4    0.07       0
Bank Sta=4972.3,4976.3
Exp/Cntr=0.3,0.1

Type RM Length L Ch R = 1,1451,401,401,401
BEGIN DESCRIPTION:
XS7595
END DESCRIPTION:
XS GIS Cut Line= 3
      2454383.70     13703397.56      2453890.63     13703755.21
      2453786.44     13704088.59
#Sta/Elev= 30
  4543.6  299.20  4730.0  294.02  4813.8  292.50  4849.5  289.50  4855.7  290.93
  4876.5  283.89  4885.0  283.08  4891.2  283.05  4899.7  287.16  4903.9  282.84
  4904.2  282.34  4907.9  282.84  4912.6  286.97  4920.6  287.73  4926.8  284.93
  4935.3  287.60  4941.5  283.00  4956.2  287.30  4962.3  285.23  4977.0  285.17
  4985.6  287.14  5062.9  289.16  5071.4  283.31  5072.8  284.07  5077.6  286.66
  5098.4  283.44  5106.9  289.36  5121.6  291.21  5362.0  297.46  5502.0  298.45
#Mann=5,-1,0
  4543.6    0.07       0  4730.0    0.12       0  4903.9    0.05       0
  4907.9    0.12       0  5072.8    0.07       0
Bank Sta=4903.9,4907.9
Exp/Cntr=0.3,0.1

Type RM Length L Ch R = 1,1050,390,390,390
BEGIN DESCRIPTION:
XS7594
END DESCRIPTION:
XS GIS Cut Line= 3
      2454307.30     13703157.98      2453793.40     13703491.32
      2453644.09     13703935.77
#Sta/Elev= 30
  4344.1  298.40  4516.4  293.51  4668.7  290.94  4676.6  291.39  4770.2  289.91
  4821.6  290.49  4878.0  289.92  4930.4  289.75  4936.3  289.00  4961.2  288.58
  4971.8  286.81  4979.6  281.34  4979.9  280.84  4983.4  280.84  4983.6  281.34
  4998.1  285.13  5013.3  286.41  5044.9  286.71  5061.1  288.58  5101.9  288.73
  5182.0  290.99  5187.2  290.46  5213.5  291.58  5218.8  290.97  5276.5  293.07
  5281.8  292.49  5313.3  292.79  5393.0  293.98  5402.6  294.68  5425.5  294.05
#Mann=5,-1,0
  4344.1    0.07       0  4878.0    0.12       0  4979.6    0.05       0
  4983.6    0.12       0  5101.9    0.07       0
Bank Sta=4979.6,4983.6
Exp/Cntr=0.3,0.1

Type RM Length L Ch R = 1,660,445,445,445
BEGIN DESCRIPTION:
XS7593
END DESCRIPTION:
XS GIS Cut Line= 3
      2454269.07     13703088.55      2453407.99     13703359.38
      2453401.04     13703717.04
#Sta/Elev= 30
  4219.5  297.86  4259.1  297.11  4339.1  293.84  4458.6  291.37  4606.2  290.06
  4664.0  289.80  4723.0  288.30  4760.6  288.39  4852.6  286.69  4857.8  287.24
  4890.2  285.50  4895.4  286.35  4922.6  284.77  4960.2  284.66  4966.1  281.44
  4966.3  280.94  4970.1  281.44  4973.1  281.52  4978.5  281.65  4987.4  284.20
  4992.6  283.54  5019.7  286.45  5041.4  287.81  5057.4  288.48  5127.9  288.53
  5319.8  290.14  5367.8  290.97  5377.8  290.54  5387.8  291.29  5479.9  291.13
#Mann=7,-1,0
  4219.5    0.07       0  4606.2    0.12       0  4966.1    0.05       0
  4970.1    0.12       0  4973.1    0.07       0  5127.9    0.12       0
  5319.8    0.07       0
Bank Sta=4966.1,4970.1
Exp/Cntr=0.3,0.1

Type RM Length L Ch R = 1,215,0,0,0
BEGIN DESCRIPTION:
XS7592
END DESCRIPTION:
XS GIS Cut Line= 4
      2454109.41     13702800.34      2453567.71     13702880.21
      2453387.15     13703154.51      2453387.15     13703631.86
#Sta/Elev= 30
  4316.7  296.38  4503.1  290.39  4573.9  288.59  4588.8  289.00  4594.1  288.35
  4634.5  288.32  4658.5  287.11  4745.7  287.38  4786.1  286.52  4806.3  286.94
  4897.4  286.25  4964.5  286.14  4991.6  283.62  5013.7  283.53  5021.7  282.84
  5025.7  277.79  5025.9  277.29  5029.7  277.79  5036.8  281.35  5042.8  283.48
  5049.6  283.99  5063.8  283.51  5078.9  283.95  5130.2  287.25  5278.5  287.94
  5408.6  288.77  5607.5  290.30  5643.1  291.16  5653.1  290.46  5670.0  290.68
#Mann=7,-1,0
  4316.7    0.07       0  4897.4    0.12       0  5025.7    0.05       0
  5029.7    0.12       0  5278.5    0.07       0  5408.6    0.12       0
  5607.5    0.07       0
Bank Sta=5025.7,5029.7
Exp/Cntr=0.3,0.1

Chan Stop Cuts=-1