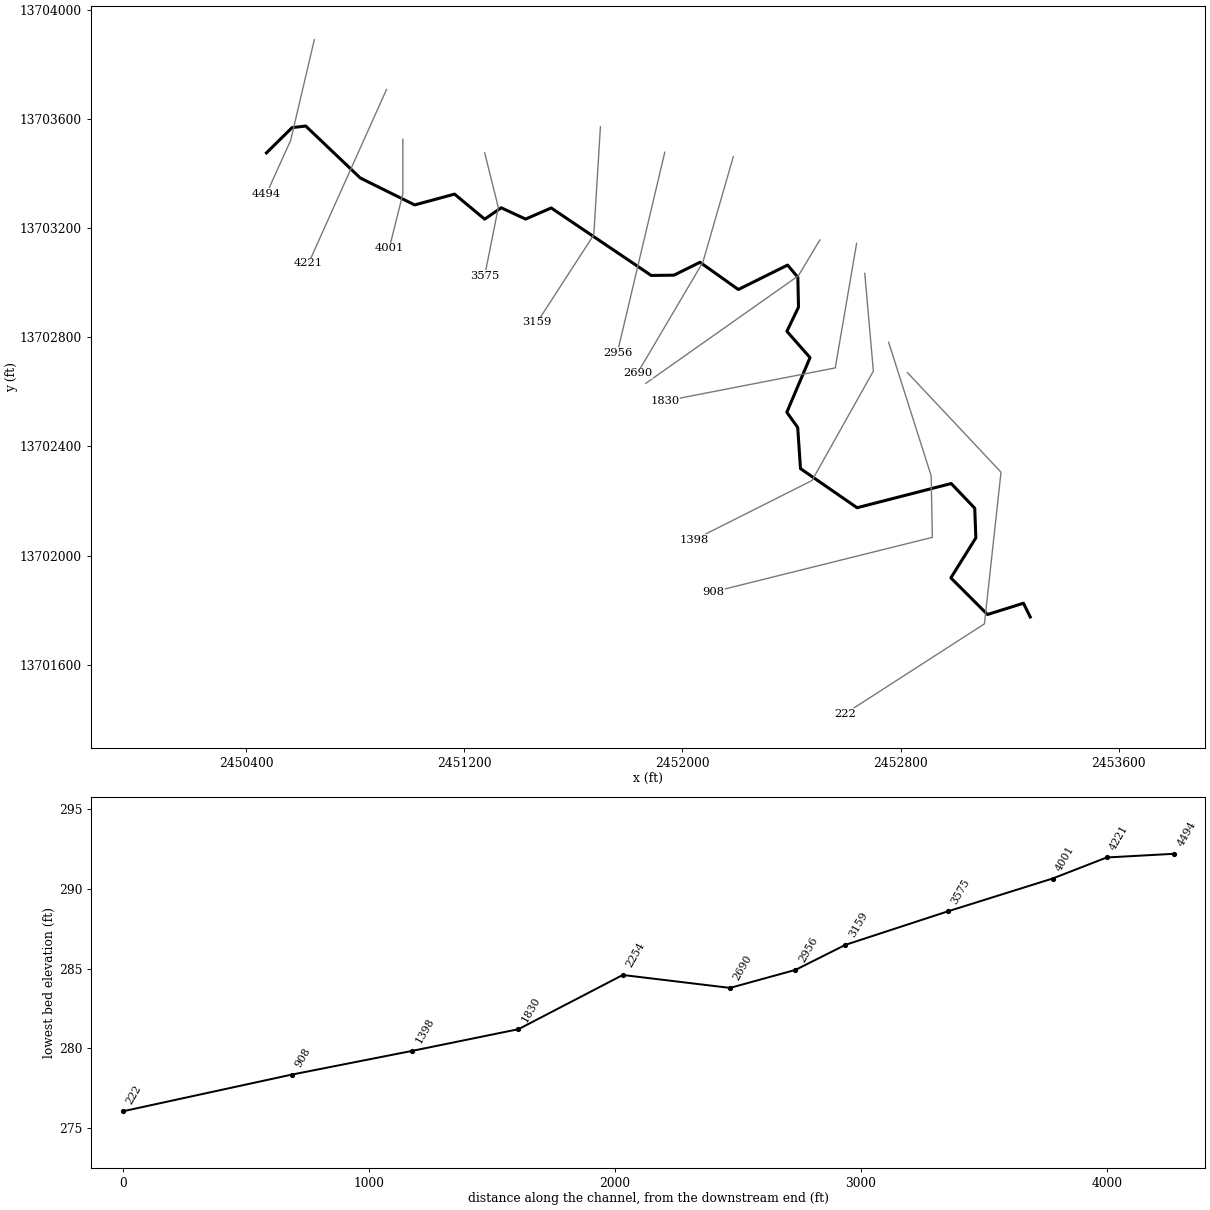
--- Stream0734.prj (project) ---

Proj Title=Stream0734 Base Level Engineering
Current Plan=p01
Default Exp/Contr=0.3,0.1
English Units
Geom File=g01
Flow File=f01
Plan File=p01
BEGIN DESCRIPTION:
Stream0734
END DESCRIPTION:

--- Stream0734.p01 (plan) ---

Plan Title=Multiple Run
Short Identifier=Multiple
Geom File=g01
Flow File=f01
Subcritical Flow
K Sum by GR= 0
Std Step Tol= 0.01
Critical Tol= 0.01
Num of Std Step Trials= 20
Max Error Tol= 0.3
Flow Tol Ratio= 0.001
Split Flow NTrial= 30
Split Flow Tol= 0.02
Split Flow Ratio= 0.02
Log Output Level= 0
Friction Slope Method= 1
Unsteady Friction Slope Method= 2
Unsteady Bridges Friction Slope Method= 1
Parabolic Critical Depth
Global Vel Dist=  1 , 1 , 1
Global Log Level= 0
CheckData=True
Encroach Param= -1, 0, 0, 0
BEGIN DESCRIPTION:
Multiple Run
END DESCRIPTION:

--- Stream0734.f01 (steady flow) ---

Flow Title=Multiple
Number of Profiles=7
Profile Names=10-year,25-year,50-year,1pct_min,100-year,1pct_plu,500-year
River Rch & RM= Stream0734,Reach-1,4494
     536     848    1124     723    1442    2877    2346
Boundary for River Rch & Prof#=Stream0734,Reach-1,1
Up Type=0
Dn Type=3
Dn Slope=0.005
Boundary for River Rch & Prof#=Stream0734,Reach-1,2
Up Type=0
Dn Type=3
Dn Slope=0.005
Boundary for River Rch & Prof#=Stream0734,Reach-1,3
Up Type=0
Dn Type=3
Dn Slope=0.005
Boundary for River Rch & Prof#=Stream0734,Reach-1,4
Up Type=0
Dn Type=3
Dn Slope=0.005
Boundary for River Rch & Prof#=Stream0734,Reach-1,5
Up Type=0
Dn Type=3
Dn Slope=0.005
Boundary for River Rch & Prof#=Stream0734,Reach-1,6
Up Type=0
Dn Type=3
Dn Slope=0.005
Boundary for River Rch & Prof#=Stream0734,Reach-1,7
Up Type=0
Dn Type=3
Dn Slope=0.005

--- Stream0734.g01 (geometry) ---

Geom Title=Existing Conditions

River Reach=Stream0734,Reach-1
Reach XY= 30
      2450475.00     13703475.00      2450568.93     13703567.64
      2450618.96     13703573.43      2450818.94     13703383.14
      2451018.38     13703284.42      2451164.52     13703324.05
      2451274.92     13703232.36      2451335.64     13703274.01
      2451425.00     13703232.62      2451518.95     13703273.34
      2451885.54     13703026.08      2451969.03     13703027.19
      2452064.38     13703074.39      2452204.80     13702974.63
      2452385.43     13703064.07      2452422.96     13703019.55
      2452425.41     13702909.82      2452382.82     13702821.58
      2452467.66     13702725.10      2452382.56     13702525.00
      2452422.53     13702469.14      2452432.70     13702318.53
      2452640.22     13702175.25      2452985.08     13702263.91
      2453071.47     13702173.56      2453075.55     13702064.81
      2452983.96     13701918.33      2453118.26     13701784.13
      2453250.08     13701825.45      2453275.00     13701775.00

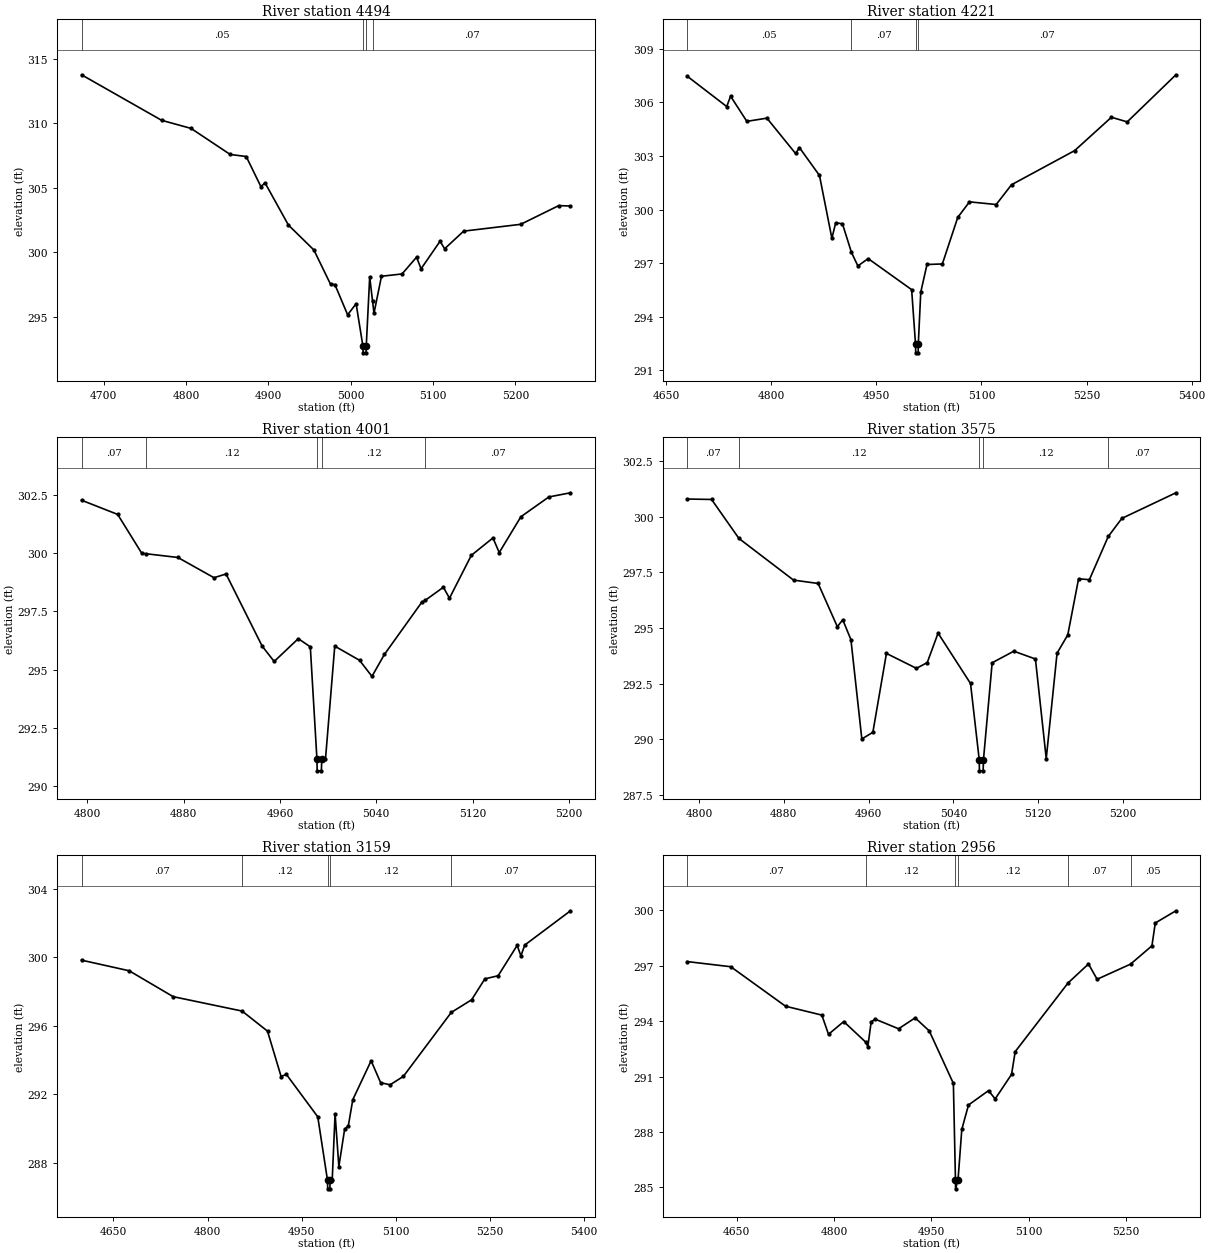
Type RM Length L Ch R = 1,4494,273,273,273
BEGIN DESCRIPTION:
Stream0734 7.0
END DESCRIPTION:
XS GIS Cut Line= 3
      2450650.43     13703889.65      2450563.63     13703520.75
      2450474.98     13703324.96
#Sta/Elev= 30
  4673.1  313.77  4770.3  310.24  4806.1  309.61  4853.6  307.59  4873.1  307.43
  4890.9  305.10  4896.0  305.38  4924.4  302.11  4955.3  300.18  4975.6  297.51
  4980.8  297.50  4996.3  295.15  5006.6  296.01  5014.9  292.70  5015.1  292.20
  5018.6  292.20  5018.9  292.70  5023.1  298.09  5026.6  296.19  5028.3  295.27
  5037.4  298.14  5062.4  298.32  5080.0  299.62  5085.5  298.72  5108.6  300.86
  5114.1  300.27  5137.2  301.64  5206.5  302.17  5252.7  303.62  5267.0  303.59
#Mann=4,-1,0
  4673.1    0.05       0  5014.9    0.05       0  5018.9    0.05       0
  5026.6    0.07       0
Bank Sta=5014.9,5018.9
Exp/Cntr=0.3,0.1

Type RM Length L Ch R = 1,4221,220,220,220
BEGIN DESCRIPTION:
XS7600
END DESCRIPTION:
XS GIS Cut Line= 2
      2450915.19     13703707.38      2450629.50     13703071.07
#Sta/Elev= 30
  4680.0  307.48  4736.7  305.77  4742.2  306.35  4765.4  304.94  4794.0  305.12
  4834.9  303.14  4840.4  303.47  4869.0  301.91  4886.7  298.39  4892.2  299.26
  4901.8  299.20  4914.6  297.60  4923.8  296.84  4938.5  297.25  5000.5  295.51
  5006.0  292.47  5006.3  291.97  5009.8  291.97  5010.0  292.47  5013.5  295.37
  5022.4  296.92  5044.3  296.95  5066.3  299.56  5083.0  300.43  5121.1  300.28
  5143.0  301.39  5233.0  303.30  5285.5  305.17  5308.0  304.91  5377.5  307.55
#Mann=4,-1,0
  4680.0    0.05       0  4914.6    0.07       0  5006.0    0.05       0
  5010.0    0.07       0
Bank Sta=5006,5010
Exp/Cntr=0.3,0.1

Type RM Length L Ch R = 1,4001,426,426,426
BEGIN DESCRIPTION:
Stream0734 6.0
END DESCRIPTION:
XS GIS Cut Line= 3
      2450975.00     13703524.99      2450975.00     13703325.00
      2450925.01     13703125.05
#Sta/Elev= 30
  4795.2  302.28  4825.2  301.67  4845.2  300.00  4848.8  299.98  4875.2  299.82
  4905.2  298.95  4915.2  299.11  4945.2  296.01  4955.2  295.35  4975.2  296.33
  4985.2  295.98  4990.7  291.15  4990.9  290.65  4994.4  290.65  4994.7  291.15
  4997.8  291.15  5005.5  296.01  5026.1  295.40  5036.4  294.71  5046.7  295.65
  5077.7  297.89  5080.7  297.98  5095.7  298.54  5100.8  298.07  5118.9  299.91
  5136.9  300.66  5142.1  300.03  5160.1  301.57  5183.3  302.42  5201.3  302.60
#Mann=5,-1,0
  4795.2    0.07       0  4848.8    0.12       0  4990.7    0.05       0
  4994.7    0.12       0  5080.7    0.07       0
Bank Sta=4990.7,4994.7
Exp/Cntr=0.3,0.1

Type RM Length L Ch R = 1,3575,416,416,416
BEGIN DESCRIPTION:
Stream0734 5.0
END DESCRIPTION:
XS GIS Cut Line= 3
      2451274.99     13703475.02      2451325.00     13703275.00
      2451275.01     13703025.03
#Sta/Elev= 30
  4788.7  300.79  4811.9  300.77  4837.7  299.02  4889.2  297.15  4912.4  297.00
  4930.5  295.06  4935.6  295.37  4943.3  294.48  4953.6  290.02  4964.0  290.32
  4976.8  293.86  5005.1  293.19  5015.3  293.45  5025.5  294.77  5056.1  292.51
  5064.3  289.09  5064.5  288.59  5068.0  288.59  5068.3  289.09  5076.5  293.44
  5096.9  293.96  5117.3  293.61  5127.5  289.14  5137.7  293.87  5147.8  294.69
  5158.0  297.21  5168.2  297.17  5186.0  299.11  5198.8  299.92  5249.8  301.07
#Mann=5,-1,0
  4788.7    0.07       0  4837.7    0.12       0  5064.3    0.05       0
  5068.3    0.12       0  5186.0    0.07       0
Bank Sta=5064.3,5068.3
Exp/Cntr=0.3,0.1

Type RM Length L Ch R = 1,3159,203,203,203
BEGIN DESCRIPTION:
Stream0734 4.0
END DESCRIPTION:
XS GIS Cut Line= 3
      2451699.26     13703570.71      2451675.00     13703175.00
      2451466.95     13702853.85
#Sta/Elev= 30
  4599.1  299.83  4675.0  299.21  4745.1  297.70  4854.9  296.86  4895.4  295.69
  4917.1  293.04  4925.4  293.17  4975.5  290.69  4991.0  286.99  4991.3  286.49
  4994.8  286.49  4995.0  286.99  4998.5  286.99  5003.1  290.87  5009.1  287.79
  5018.3  289.97  5024.2  290.17  5031.3  291.69  5060.5  293.96  5075.7  292.68
  5090.8  292.56  5111.9  293.05  5188.2  296.78  5220.7  297.52  5241.8  298.74
  5262.9  298.92  5293.2  300.69  5299.2  300.08  5305.3  300.71  5378.2  302.71
#Mann=5,-1,0
  4599.1    0.07       0  4854.9    0.12       0  4991.0    0.05       0
  4995.0    0.12       0  5188.2    0.07       0
Bank Sta=4991,4995
Exp/Cntr=0.3,0.1

Type RM Length L Ch R = 1,2956,266,266,266
BEGIN DESCRIPTION:
XS7601
END DESCRIPTION:
XS GIS Cut Line= 2
      2451935.16     13703477.35      2451761.54     13702743.82
#Sta/Elev= 30
  4573.1  297.23  4640.6  296.95  4725.1  294.81  4781.0  294.33  4791.3  293.29
  4814.8  293.98  4848.8  292.86  4851.9  292.62  4857.1  293.97  4863.3  294.11
  4899.3  293.59  4924.9  294.18  4946.7  293.47  4983.8  290.63  4987.0  285.42
  4987.2  284.92  4991.0  285.42  4996.8  288.14  5007.1  289.46  5038.0  290.24
  5048.2  289.79  5073.5  291.12  5079.1  292.35  5160.6  296.07  5192.1  297.10
  5205.4  296.27  5256.9  297.09  5289.9  298.08  5295.1  299.32  5326.9  299.98
#Mann=6,-1,0
  4573.1    0.07       0  4848.8    0.12       0  4987.0    0.05       0
  4991.0    0.12       0  5160.6    0.07       0  5256.9    0.05       0
Bank Sta=4987,4991
Exp/Cntr=0.3,0.1

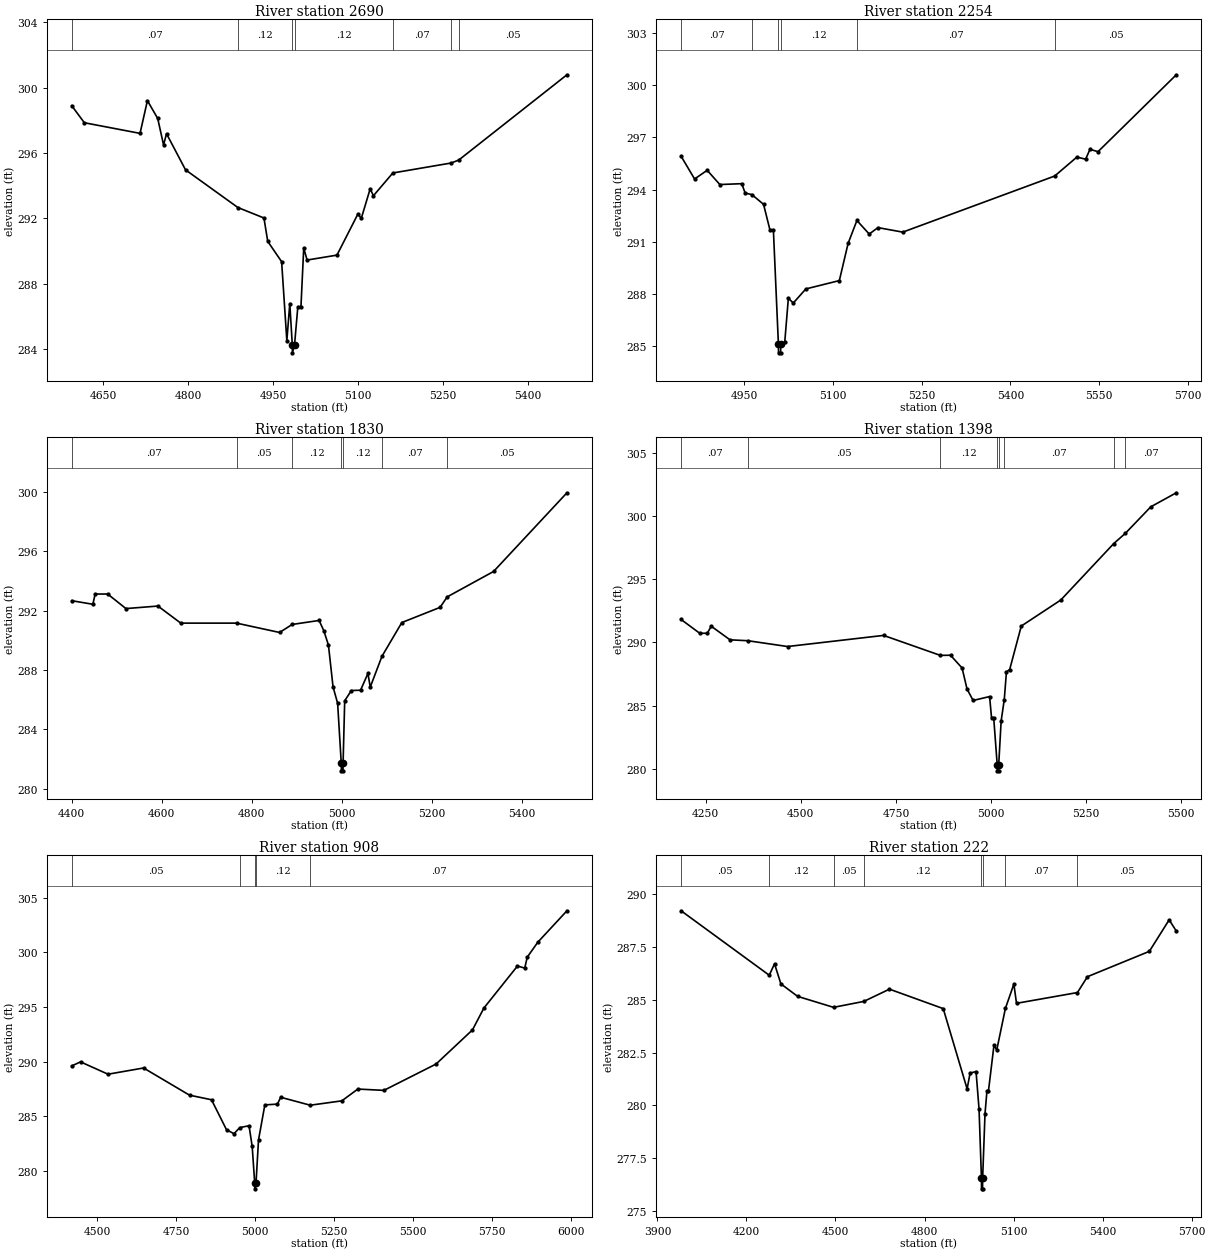
Type RM Length L Ch R = 1,2690,436,436,436
BEGIN DESCRIPTION:
Stream0734 3.0
END DESCRIPTION:
XS GIS Cut Line= 3
      2452186.30     13703460.79      2452075.00     13703075.00
      2451835.15     13702668.28
#Sta/Elev= 30
  4594.9  298.89  4617.1  297.85  4715.4  297.20  4728.4  299.20  4746.6  298.11
  4756.9  296.49  4762.1  297.18  4795.7  294.97  4888.0  292.67  4934.0  292.03
  4940.7  290.60  4965.2  289.36  4974.4  284.53  4979.6  286.80  4984.0  284.29
  4984.3  283.79  4988.0  284.29  4993.8  286.61  4999.3  286.61  5004.2  290.20
  5010.1  289.46  5062.8  289.76  5099.9  292.28  5105.7  292.00  5121.4  293.81
  5127.2  293.39  5161.4  294.78  5264.5  295.39  5277.7  295.57  5468.6  300.78
#Mann=7,-1,0
  4594.9    0.07       0  4888.0    0.12       0  4984.0    0.05       0
  4988.0    0.12       0  5161.4    0.07       0  5264.5    0.12       0
  5277.7    0.05       0
Bank Sta=4984,4988
Exp/Cntr=0.3,0.1

Type RM Length L Ch R = 1,2254,424,424,424
BEGIN DESCRIPTION:
Stream0734 2.0
END DESCRIPTION:
XS GIS Cut Line= 3
      2452503.73     13703156.17      2452425.00     13703025.00
      2451865.73     13702631.00
#Sta/Elev= 30
  4843.2  295.92  4866.0  294.61  4887.3  295.11  4908.7  294.29  4945.7  294.34
  4951.5  293.80  4962.9  293.71  4982.6  293.15  4993.3  291.69  4999.2  291.69
  5007.7  285.10  5007.9  284.60  5011.4  284.60  5011.7  285.10  5018.4  285.21
  5024.5  287.74  5032.9  287.47  5054.1  288.28  5110.7  288.76  5125.5  290.90
  5140.4  292.22  5161.2  291.44  5176.0  291.81  5217.9  291.55  5474.7  294.78
  5512.2  295.87  5527.0  295.75  5534.4  296.32  5547.9  296.18  5680.3  300.61
#Mann=6,-1,0
  4843.2    0.07       0  4962.9    0.12       0  5007.7    0.05       0
  5011.7    0.12       0  5140.4    0.07       0  5474.7    0.05       0
Bank Sta=5007.7,5011.7
Exp/Cntr=0.3,0.1

Type RM Length L Ch R = 1,1830,432,432,432
BEGIN DESCRIPTION:
XS7599
END DESCRIPTION:
XS GIS Cut Line= 3
      2452638.39     13703143.61      2452560.16     13702687.41
      2451935.12     13702565.88
#Sta/Elev= 30
  4400.5  292.66  4447.4  292.42  4452.5  293.11  4480.3  293.11  4520.8  292.13
  4591.9  292.30  4642.6  291.15  4766.4  291.15  4862.0  290.52  4889.9  291.06
  4949.8  291.33  4960.3  290.63  4970.5  289.67  4980.7  286.86  4990.9  285.75
  4999.0  281.70  4999.3  281.20  5002.8  281.20  5003.0  281.70  5006.6  285.92
  5021.4  286.61  5041.8  286.63  5058.2  287.76  5063.3  286.84  5089.4  288.92
  5133.5  291.19  5218.3  292.21  5234.3  292.92  5337.2  294.63  5500.1  299.93
#Mann=7,-1,0
  4400.5    0.07       0  4766.4    0.05       0  4889.9    0.12       0
  4999.0    0.05       0  5003.0    0.12       0  5089.4    0.07       0
  5234.3    0.05       0
Bank Sta=4999,5003
Exp/Cntr=0.3,0.1

Type RM Length L Ch R = 1,1398,490,490,490
BEGIN DESCRIPTION:
Stream0734 1.0
END DESCRIPTION:
XS GIS Cut Line= 4
      2452668.36     13703033.76      2452699.82     13702675.73
      2452475.00     13702275.00      2452043.68     13702058.08
#Sta/Elev= 30
  4185.3  291.82  4234.3  290.73  4254.3  290.73  4264.4  291.29  4313.9  290.21
  4360.8  290.14  4465.1  289.68  4717.5  290.56  4866.7  288.98  4893.5  288.99
  4923.9  287.98  4936.9  286.32  4952.9  285.41  4996.2  285.72  5001.3  284.05
  5007.0  284.05  5016.2  280.34  5016.4  279.84  5019.9  279.84  5020.2  280.34
  5026.6  283.79  5034.8  285.48  5040.5  287.67  5049.0  287.86  5079.5  291.30
  5183.3  293.36  5322.6  297.83  5353.1  298.64  5420.0  300.74  5487.0  301.85
#Mann=8,-1,0
  4185.3    0.07       0  4360.8    0.05       0  4866.7    0.12       0
  5016.2    0.05       0  5020.2    0.12       0  5034.8    0.07       0
  5322.6    0.05       0  5353.1    0.07       0
Bank Sta=5016.2,5020.2
Exp/Cntr=0.3,0.1

Type RM Length L Ch R = 1,908,686,686,686
BEGIN DESCRIPTION:
XS7598
END DESCRIPTION:
XS GIS Cut Line= 4
      2452755.78     13702781.49      2452911.72     13702292.45
      2452916.06     13702066.75      2452113.15     13701867.11
#Sta/Elev= 30
  4420.4  289.61  4448.2  289.98  4535.2  288.85  4647.6  289.42  4792.9  286.93
  4862.5  286.51  4910.0  283.76  4933.7  283.40  4951.8  283.96  4981.2  284.13
  4991.2  282.23  4999.2  278.85  4999.4  278.35  5003.2  278.85  5011.2  282.83
  5031.2  286.04  5071.2  286.11  5081.2  286.74  5174.8  286.01  5274.7  286.41
  5325.4  287.49  5407.8  287.37  5572.7  289.78  5688.0  292.91  5724.1  294.91
  5830.3  298.76  5853.3  298.57  5861.2  299.57  5894.6  300.94  5986.8  303.82
#Mann=5,-1,0
  4420.4    0.05       0  4951.8    0.12       0  4999.2    0.05       0
  5003.2    0.12       0  5174.8    0.07       0
Bank Sta=4999.2,5003.2
Exp/Cntr=0.3,0.1

Type RM Length L Ch R = 1,222,0,0,0
BEGIN DESCRIPTION:
XS7597
END DESCRIPTION:
XS GIS Cut Line= 4
      2452824.94     13702670.03      2453167.80     13702305.47
      2453107.03     13701749.91      2452594.89     13701420.06
#Sta/Elev= 30
  3979.8  289.21  4276.8  286.16  4294.6  286.70  4316.1  285.75  4372.3  285.16
  4493.4  284.64  4595.3  284.92  4681.9  285.50  4863.0  284.58  4943.5  280.78
  4953.5  281.53  4973.6  281.60  4983.7  279.82  4991.8  276.55  4992.0  276.05
  4995.5  276.05  4995.8  276.55  5003.8  279.61  5010.3  280.68  5015.4  280.68
  5034.0  282.85  5043.3  282.62  5072.5  284.59  5101.0  285.74  5109.9  284.83
  5315.2  285.34  5348.9  286.09  5557.5  287.29  5624.2  288.78  5648.3  288.25
#Mann=8,-1,0
  3979.8    0.05       0  4276.8    0.12       0  4493.4    0.05       0
  4595.3    0.12       0  4991.8    0.05       0  4995.8    0.12       0
  5072.5    0.07       0  5315.2    0.05       0
Bank Sta=4991.8,4995.8
Exp/Cntr=0.3,0.1

Chan Stop Cuts=-1