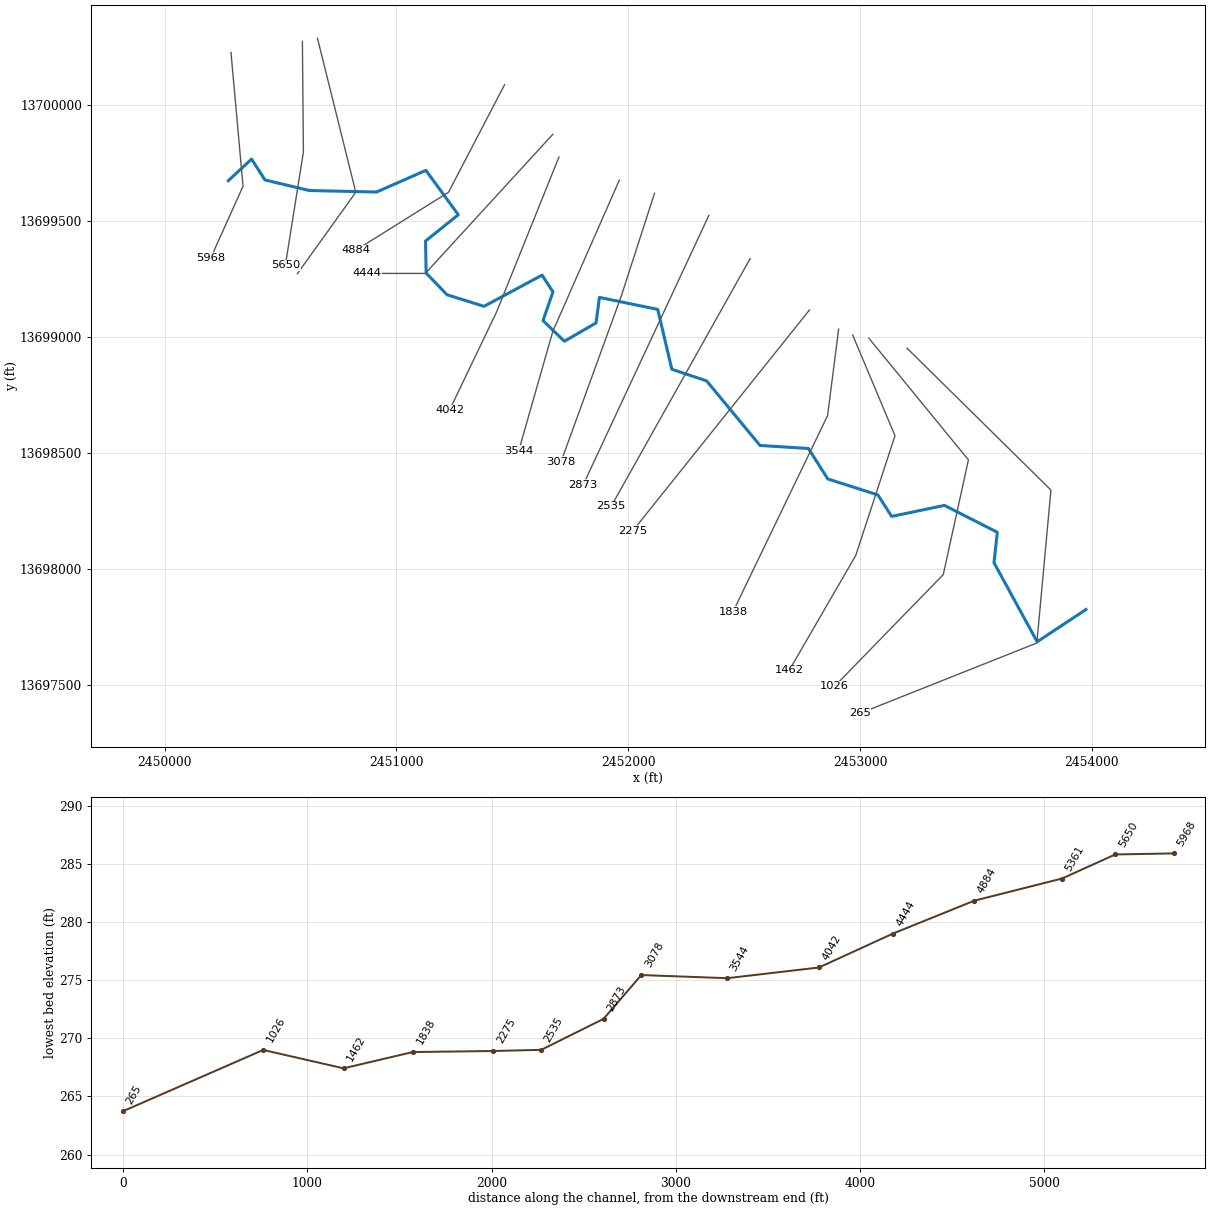
--- Stream0735.prj (project) ---

Proj Title=Stream0735 Base Level Engineering
Current Plan=p01
Default Exp/Contr=0.3,0.1
English Units
Geom File=g01
Flow File=f01
Plan File=p01
BEGIN DESCRIPTION:
Stream0735
END DESCRIPTION:

--- Stream0735.p01 (plan) ---

Plan Title=Multiple Run
Short Identifier=Multiple
Geom File=g01
Flow File=f01
Subcritical Flow
K Sum by GR= 0
Std Step Tol= 0.01
Critical Tol= 0.01
Num of Std Step Trials= 20
Max Error Tol= 0.3
Flow Tol Ratio= 0.001
Split Flow NTrial= 30
Split Flow Tol= 0.02
Split Flow Ratio= 0.02
Log Output Level= 0
Friction Slope Method= 1
Unsteady Friction Slope Method= 2
Unsteady Bridges Friction Slope Method= 1
Parabolic Critical Depth
Global Vel Dist=  1 , 1 , 1
Global Log Level= 0
CheckData=True
Encroach Param= -1, 0, 0, 0
BEGIN DESCRIPTION:
Multiple Run
END DESCRIPTION:

--- Stream0735.f01 (steady flow) ---

Flow Title=Multiple
Number of Profiles=7
Profile Names=10-year,25-year,50-year,1pct_min,100-year,1pct_plu,500-year
River Rch & RM= Stream0735,Reach-1,5968
     353     546     715     454     906    1807    1438
River Rch & RM= Stream0735,Reach-1,4042
     626     998    1330     859    1713    3418    2812
Boundary for River Rch & Prof#=Stream0735,Reach-1,1
Up Type=0
Dn Type=3
Dn Slope=0.005
Boundary for River Rch & Prof#=Stream0735,Reach-1,2
Up Type=0
Dn Type=3
Dn Slope=0.005
Boundary for River Rch & Prof#=Stream0735,Reach-1,3
Up Type=0
Dn Type=3
Dn Slope=0.005
Boundary for River Rch & Prof#=Stream0735,Reach-1,4
Up Type=0
Dn Type=3
Dn Slope=0.005
Boundary for River Rch & Prof#=Stream0735,Reach-1,5
Up Type=0
Dn Type=3
Dn Slope=0.005
Boundary for River Rch & Prof#=Stream0735,Reach-1,6
Up Type=0
Dn Type=3
Dn Slope=0.005
Boundary for River Rch & Prof#=Stream0735,Reach-1,7
Up Type=0
Dn Type=3
Dn Slope=0.005

--- Stream0735.g01 (geometry) ---

Geom Title=Existing Conditions

River Reach=Stream0735,Reach-1
Reach XY= 30
      2450275.00     13699675.00      2450375.21     13699768.09
      2450433.30     13699678.13      2450625.01     13699632.59
      2450914.56     13699626.04      2451127.44     13699719.61
      2451267.24     13699528.05      2451125.97     13699414.71
      2451128.52     13699276.46      2451218.81     13699182.85
      2451378.30     13699133.08      2451628.63     13699267.52
      2451675.66     13699195.23      2451632.80     13699071.55
      2451724.89     13698982.28      2451861.49     13699061.32
      2451876.03     13699171.54      2452127.71     13699119.60
      2452188.47     13698861.25      2452338.30     13698811.60
      2452568.79     13698532.80      2452777.70     13698519.64
      2452861.35     13698388.26      2453077.53     13698319.23
      2453136.84     13698226.63      2453364.32     13698274.25
      2453592.56     13698158.37      2453578.37     13698026.74
      2453764.57     13697685.93      2453975.00     13697825.00

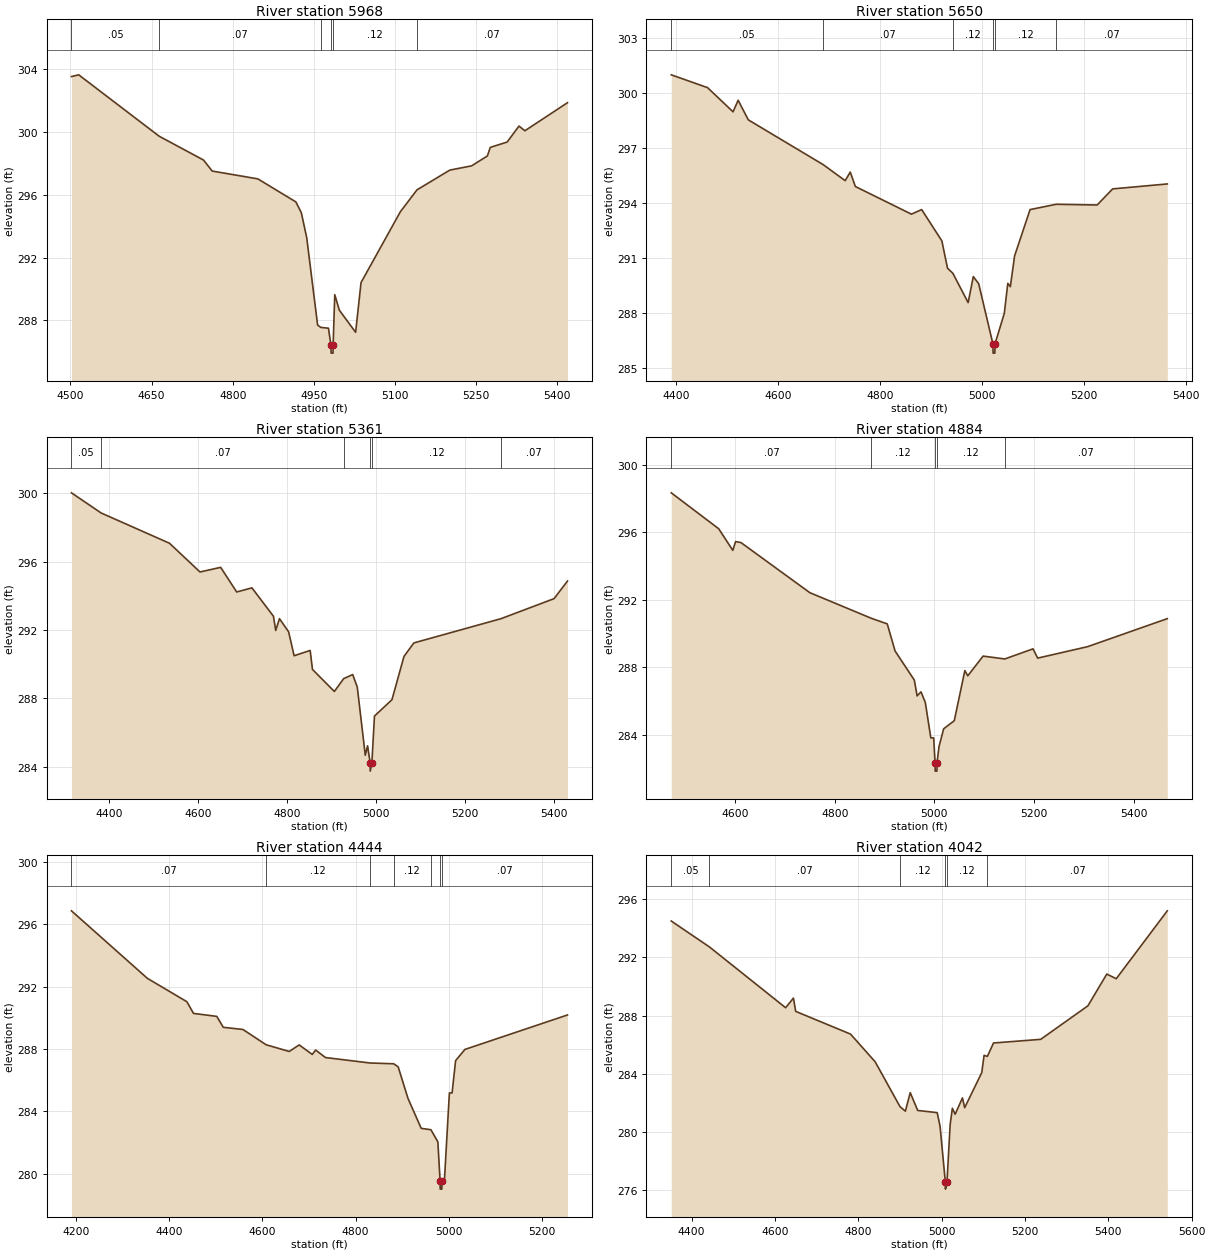
Type RM Length L Ch R = 1,5968,318,318,318
BEGIN DESCRIPTION:
XS7610
END DESCRIPTION:
XS GIS Cut Line= 3
      2450286.55     13700228.35      2450338.63     13699651.13
      2450199.86     13699343.23
#Sta/Elev= 30
  4501.8  303.55  4515.2  303.66  4664.1  299.74  4746.1  298.22  4762.0  297.52
  4846.5  297.02  4916.8  295.55  4926.9  294.86  4936.9  293.26  4957.0  287.69
  4963.0  287.54  4977.1  287.49  4981.7  286.40  4982.0  285.90  4985.5  285.90
  4985.7  286.40  4988.7  289.63  4997.2  288.64  5027.3  287.23  5037.3  290.40
  5110.0  294.92  5140.8  296.32  5201.5  297.58  5241.7  297.85  5270.9  298.48
  5276.4  299.03  5307.5  299.37  5329.4  300.39  5340.3  300.09  5419.1  301.88
#Mann=6,-1,0
  4501.8    0.05       0  4664.1    0.07       0  4963.0    0.12       0
  4981.7    0.05       0  4985.7    0.12       0  5140.8    0.07       0
Bank Sta=4981.7,4985.7
Exp/Cntr=0.3,0.1

Type RM Length L Ch R = 1,5650,289,289,289
BEGIN DESCRIPTION:
XS7609
END DESCRIPTION:
XS GIS Cut Line= 3
      2450594.70     13700276.16      2450599.05     13699798.70
      2450521.06     13699309.15
#Sta/Elev= 30
  4390.6  301.01  4461.8  300.31  4511.8  298.99  4521.8  299.62  4541.8  298.55
  4688.4  296.11  4731.8  295.23  4741.8  295.70  4751.8  294.91  4861.8  293.40
  4881.9  293.65  4921.5  291.94  4932.6  290.45  4943.1  290.17  4973.1  288.57
  4983.2  289.99  4993.8  289.60  5021.7  286.31  5022.0  285.81  5025.5  285.81
  5025.7  286.31  5044.0  287.98  5050.9  289.62  5055.9  289.44  5064.2  291.12
  5094.6  293.65  5145.9  293.94  5226.2  293.90  5256.6  294.78  5363.8  295.05
#Mann=6,-1,0
  4390.6    0.05       0  4688.4    0.07       0  4943.1    0.12       0
  5021.7    0.05       0  5025.7    0.12       0  5145.9    0.07       0
Bank Sta=5021.7,5025.7
Exp/Cntr=0.3,0.1

Type RM Length L Ch R = 1,5361,477,477,477
BEGIN DESCRIPTION:
Stream0735 11.0
END DESCRIPTION:
XS GIS Cut Line= 3
      2450659.82     13700289.12      2450825.00     13699625.00
      2450573.35     13699274.18
#Sta/Elev= 30
  4315.1  300.02  4381.9  298.84  4535.7  297.07  4604.3  295.39  4650.8  295.66
  4686.9  294.22  4721.2  294.46  4769.6  292.80  4774.7  291.97  4783.1  292.66
  4803.7  291.89  4816.1  290.49  4852.2  290.80  4857.4  289.69  4906.7  288.40
  4927.6  289.15  4947.9  289.39  4958.2  288.66  4976.2  284.67  4981.4  285.22
  4987.1  284.24  4987.4  283.74  4991.1  284.24  4996.9  286.96  5036.3  287.92
  5063.3  290.45  5085.6  291.24  5281.9  292.66  5401.0  293.83  5431.2  294.86
#Mann=6,-1,0
  4315.1    0.05       0  4381.9    0.07       0  4927.6    0.12       0
  4987.1    0.05       0  4991.1    0.12       0  5281.9    0.07       0
Bank Sta=4987.1,4991.1
Exp/Cntr=0.3,0.1

Type RM Length L Ch R = 1,4884,440,440,440
BEGIN DESCRIPTION:
Stream0735 10.0
END DESCRIPTION:
XS GIS Cut Line= 3
      2451467.08     13700089.45      2451225.00     13699625.00
      2450824.96     13699374.97
#Sta/Elev= 30
  4471.9  298.33  4567.1  296.20  4595.4  294.92  4601.0  295.44  4611.8  295.38
  4750.0  292.41  4873.5  290.89  4905.4  290.56  4921.1  288.95  4959.7  287.23
  4965.3  286.29  4973.1  286.53  4981.8  285.90  4992.8  283.80  4998.6  283.80
  5001.3  282.33  5001.6  281.83  5005.1  281.83  5005.3  282.33  5009.2  283.28
  5018.6  284.34  5039.9  284.82  5061.1  287.79  5067.0  287.48  5097.7  288.65
  5141.3  288.48  5197.9  289.08  5207.3  288.53  5307.6  289.21  5467.4  290.87
#Mann=5,-1,0
  4471.9    0.07       0  4873.5    0.12       0  5001.3    0.05       0
  5005.3    0.12       0  5141.3    0.07       0
Bank Sta=5001.3,5005.3
Exp/Cntr=0.3,0.1

Type RM Length L Ch R = 1,4444,402,402,402
BEGIN DESCRIPTION:
Stream0735 9.0
END DESCRIPTION:
XS GIS Cut Line= 3
      2451675.00     13699875.00      2451125.00     13699275.00
      2450875.04     13699275.00
#Sta/Elev= 30
  4190.4  296.86  4353.2  292.53  4438.0  291.03  4452.2  290.28  4502.1  290.09
  4516.0  289.39  4558.2  289.25  4607.9  288.27  4657.5  287.84  4678.8  288.26
  4706.8  287.65  4714.2  287.93  4735.2  287.45  4830.7  287.10  4881.5  287.05
  4891.2  286.85  4912.2  284.83  4940.5  282.91  4961.4  282.82  4976.3  282.04
  4981.1  279.51  4981.3  279.01  4984.8  279.01  4985.1  279.51  4990.5  279.65
  5001.0  285.18  5006.8  285.18  5014.3  287.25  5034.3  287.97  5254.3  290.18
#Mann=7,-1,0
  4190.4    0.07       0  4607.9    0.12       0  4830.7    0.07       0
  4881.5    0.12       0  4961.4    0.07       0  4981.1    0.05       0
  4985.1    0.07       0
Bank Sta=4981.1,4985.1
Exp/Cntr=0.3,0.1

Type RM Length L Ch R = 1,4042,498,498,498
BEGIN DESCRIPTION:
Stream0735 8.0
END DESCRIPTION:
XS GIS Cut Line= 3
      2451701.48     13699777.01      2451432.38     13699108.59
      2451229.20     13698684.95
#Sta/Elev= 30
  4351.1  294.49  4442.8  292.71  4625.5  288.54  4644.3  289.20  4649.7  288.29
  4781.3  286.73  4840.4  284.83  4900.1  281.75  4912.9  281.44  4924.6  282.71
  4942.5  281.49  4989.3  281.34  4996.2  280.40  5008.8  276.59  5009.1  276.09
  5012.8  276.59  5020.4  280.52  5025.7  281.64  5032.4  281.23  5049.9  282.35
  5055.3  281.68  5096.3  284.09  5101.8  285.27  5109.7  285.20  5124.5  286.12
  5237.7  286.37  5351.0  288.67  5396.3  290.85  5419.0  290.53  5541.5  295.19
#Mann=6,-1,0
  4351.1    0.05       0  4442.8    0.07       0  4900.1    0.12       0
  5008.8    0.05       0  5012.8    0.12       0  5109.7    0.07       0
Bank Sta=5008.8,5012.8
Exp/Cntr=0.3,0.1

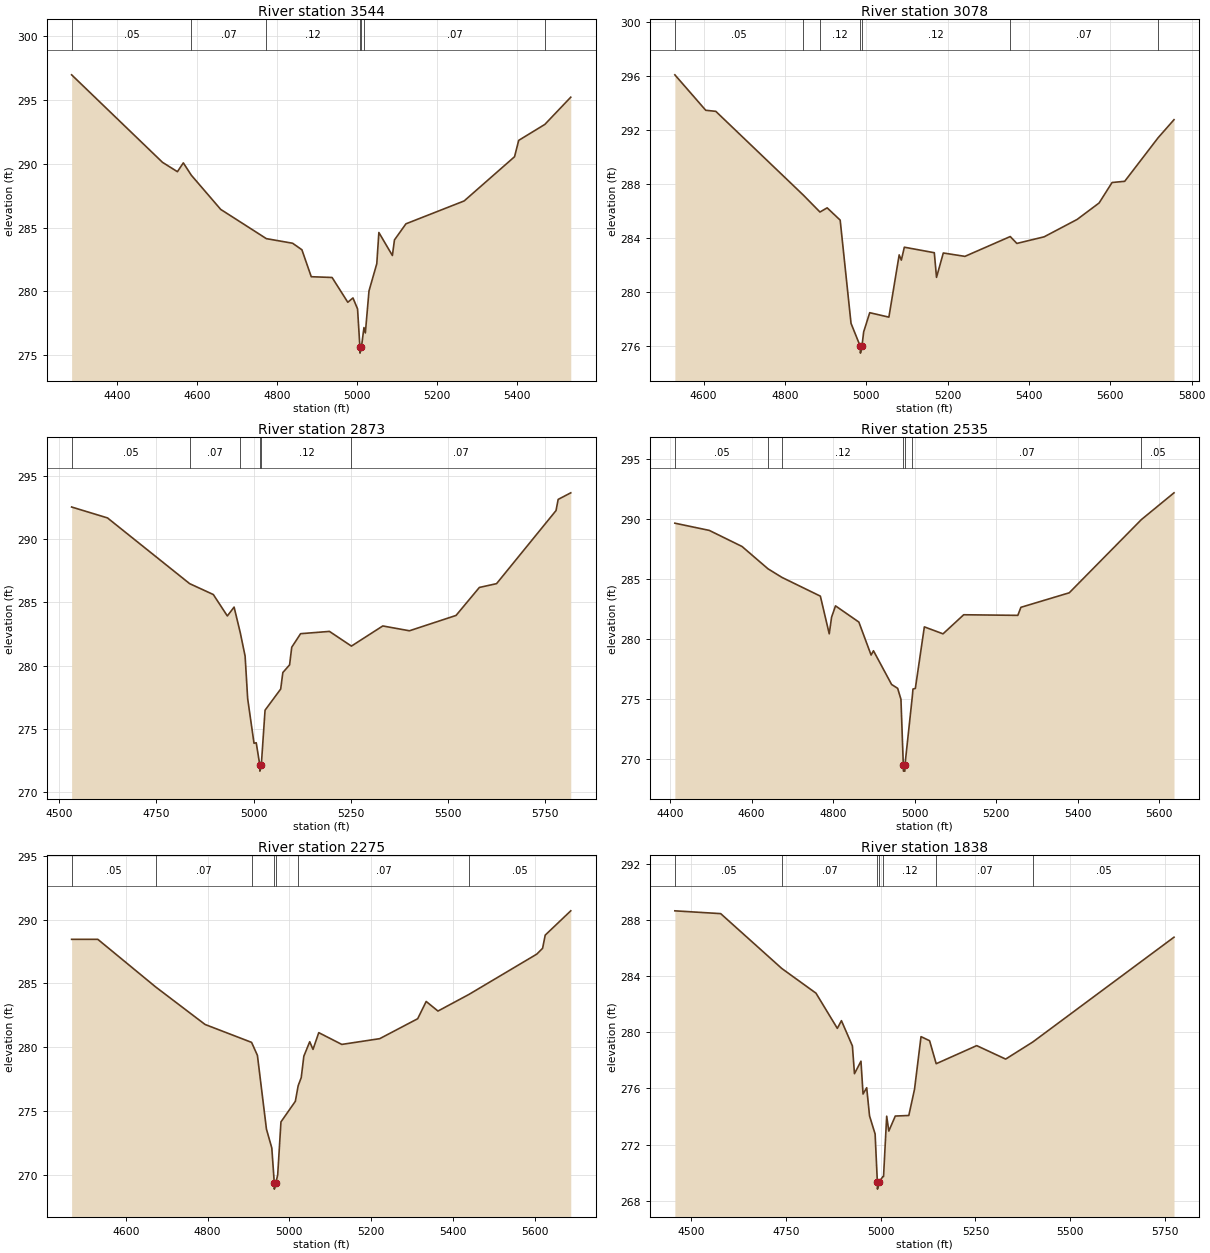
Type RM Length L Ch R = 1,3544,466,466,466
BEGIN DESCRIPTION:
Stream0735 7.0
END DESCRIPTION:
XS GIS Cut Line= 3
      2451961.91     13699677.20      2451675.00     13699025.00
      2451527.91     13698509.80
#Sta/Elev= 30
  4286.7  296.95  4514.0  290.10  4551.3  289.37  4566.1  290.06  4585.9  289.10
  4659.5  286.42  4773.7  284.13  4839.3  283.77  4862.6  283.26  4886.0  281.15
  4938.1  281.09  4977.4  279.15  4990.3  279.49  5001.8  278.63  5007.6  275.67
  5007.9  275.17  5011.6  275.67  5017.8  277.17  5021.3  276.75  5030.4  280.04
  5049.9  282.17  5055.1  284.61  5088.9  282.81  5094.1  284.03  5122.8  285.29
  5268.4  287.08  5394.4  290.54  5404.8  291.82  5470.2  293.07  5535.0  295.20
#Mann=7,-1,0
  4286.7    0.05       0  4585.9    0.07       0  4773.7    0.12       0
  5007.6    0.05       0  5011.6    0.12       0  5017.8    0.07       0
  5470.2    0.05       0
Bank Sta=5007.6,5011.6
Exp/Cntr=0.3,0.1

Type RM Length L Ch R = 1,3078,205,205,205
BEGIN DESCRIPTION:
Stream0735 6.0
END DESCRIPTION:
XS GIS Cut Line= 3
      2452113.81     13699620.79      2451970.57     13699178.04
      2451710.15     13698461.86
#Sta/Elev= 30
  4529.2  296.09  4605.1  293.46  4629.9  293.38  4845.3  287.16  4886.0  285.91
  4903.7  286.22  4935.7  285.31  4962.4  277.65  4985.2  275.94  4985.5  275.44
  4989.2  275.94  4993.5  277.02  5008.4  278.44  5055.5  278.11  5080.8  282.73
  5086.1  282.34  5093.5  283.30  5167.2  282.89  5172.6  281.06  5189.3  282.87
  5242.5  282.62  5353.9  284.09  5370.2  283.58  5437.3  284.07  5518.4  285.36
  5572.4  286.58  5604.3  288.10  5635.4  288.19  5717.5  291.42  5756.6  292.76
#Mann=7,-1,0
  4529.2    0.05       0  4845.3    0.07       0  4886.0    0.12       0
  4985.2    0.05       0  4989.2    0.12       0  5353.9    0.07       0
  5717.5    0.05       0
Bank Sta=4985.2,4989.2
Exp/Cntr=0.3,0.1

Type RM Length L Ch R = 1,2873,338,338,338
BEGIN DESCRIPTION:
XS7608
END DESCRIPTION:
XS GIS Cut Line= 2
      2452348.17     13699525.24      2451805.63     13698362.04
#Sta/Elev= 30
  4531.9  292.52  4624.1  291.66  4835.4  286.47  4896.3  285.61  4932.3  283.92
  4949.7  284.62  4965.7  282.58  4978.0  280.75  4984.6  277.39  5000.9  273.87
  5006.6  273.91  5015.7  272.17  5015.9  271.67  5019.7  272.17  5029.3  276.48
  5069.5  278.15  5075.0  279.45  5092.4  280.06  5097.9  281.45  5120.7  282.52
  5194.9  282.70  5251.4  281.54  5332.0  283.13  5400.6  282.75  5520.4  283.96
  5580.4  286.17  5624.6  286.47  5777.5  292.24  5783.0  293.12  5815.4  293.64
#Mann=6,-1,0
  4531.9    0.05       0  4835.4    0.07       0  4965.7    0.12       0
  5015.7    0.05       0  5019.7    0.12       0  5251.4    0.07       0
Bank Sta=5015.7,5019.7
Exp/Cntr=0.3,0.1

Type RM Length L Ch R = 1,2535,260,260,260
BEGIN DESCRIPTION:
XS7607
END DESCRIPTION:
XS GIS Cut Line= 2
      2452526.13     13699338.64      2451927.19     13698270.96
#Sta/Elev= 30
  4411.9  289.67  4496.3  289.07  4576.6  287.73  4640.3  285.87  4674.7  285.15
  4768.8  283.59  4790.5  280.45  4796.3  281.84  4805.9  282.78  4863.2  281.43
  4893.2  278.68  4899.0  279.04  4943.5  276.23  4958.3  275.91  4966.4  275.00
  4972.2  269.51  4972.5  269.01  4976.0  269.01  4976.2  269.51  4994.3  275.23
  4995.9  275.85  5001.7  275.90  5023.8  281.03  5069.6  280.45  5120.3  282.04
  5253.1  281.99  5260.6  282.66  5379.2  283.87  5556.1  289.97  5636.1  292.20
#Mann=7,-1,0
  4411.9    0.05       0  4640.3    0.07       0  4674.7    0.12       0
  4972.2    0.05       0  4976.2    0.12       0  4994.3    0.07       0
  5556.1    0.05       0
Bank Sta=4972.2,4976.2
Exp/Cntr=0.3,0.1

Type RM Length L Ch R = 1,2275,437,437,437
BEGIN DESCRIPTION:
XS7606
END DESCRIPTION:
XS GIS Cut Line= 2
      2452782.22     13699117.29      2452019.16     13698163.46
#Sta/Elev= 30
  4467.1  288.45  4531.2  288.45  4673.0  284.72  4793.7  281.79  4907.5  280.39
  4921.8  279.37  4943.9  273.60  4957.0  272.13  4963.0  269.41  4963.2  268.91
  4967.0  269.41  4971.4  270.03  4979.4  274.17  5014.6  275.78  5021.5  277.00
  5029.0  277.63  5035.4  279.31  5049.8  280.44  5057.8  279.84  5071.9  281.15
  5128.3  280.23  5221.1  280.68  5314.0  282.24  5334.8  283.59  5363.6  282.84
  5439.4  284.14  5605.3  287.29  5619.7  287.75  5626.1  288.78  5688.6  290.68
#Mann=7,-1,0
  4467.1    0.05       0  4673.0    0.07       0  4907.5    0.12       0
  4963.0    0.05       0  4967.0    0.12       0  5021.5    0.07       0
  5439.4    0.05       0
Bank Sta=4963,4967
Exp/Cntr=0.3,0.1

Type RM Length L Ch R = 1,1838,376,376,376
BEGIN DESCRIPTION:
XS7605
END DESCRIPTION:
XS GIS Cut Line= 3
      2452908.07     13699034.78      2452860.33     13698661.55
      2452452.36     13697815.23
#Sta/Elev= 30
  4457.8  288.66  4578.6  288.46  4739.7  284.55  4829.8  282.79  4886.1  280.28
  4896.9  280.83  4925.8  279.03  4931.3  277.05  4948.4  277.94  4953.9  275.60
  4963.5  276.05  4971.0  274.04  4985.7  272.75  4991.6  269.32  4991.9  268.82
  4995.6  269.32  5006.2  269.71  5007.9  269.72  5016.2  274.02  5021.8  272.96
  5038.9  274.03  5074.5  274.07  5089.6  275.94  5106.7  279.69  5129.3  279.40
  5146.7  277.76  5253.5  279.05  5329.8  278.09  5401.4  279.31  5773.6  286.78
#Mann=7,-1,0
  4457.8    0.05       0  4739.7    0.07       0  4991.6    0.05       0
  4995.6    0.07       0  5006.2    0.12       0  5146.7    0.07       0
  5401.4    0.05       0
Bank Sta=4991.6,4995.6
Exp/Cntr=0.3,0.1

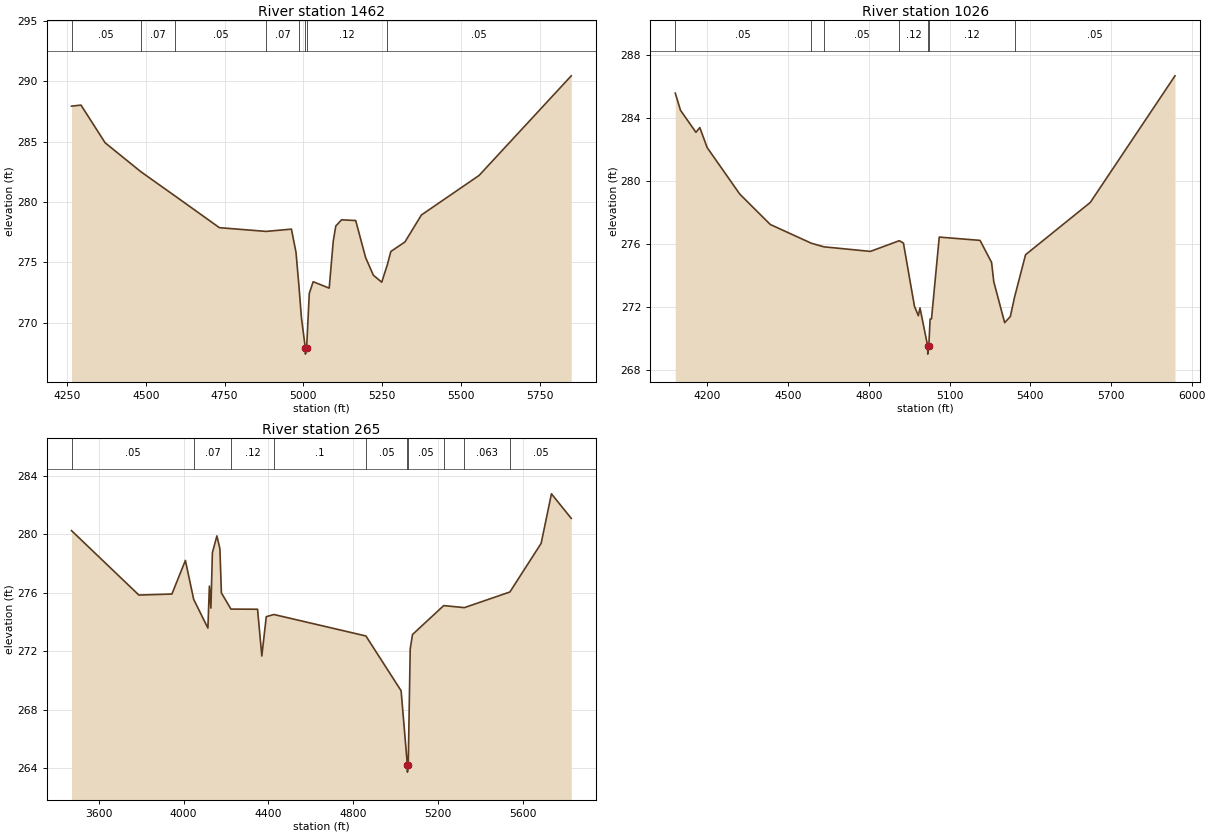
Type RM Length L Ch R = 1,1462,436,436,436
BEGIN DESCRIPTION:
XS7604
END DESCRIPTION:
XS GIS Cut Line= 4
      2452968.84     13699008.77      2453151.13     13698574.74
      2452981.86     13698058.25      2452695.40     13697563.46
#Sta/Elev= 30
  4264.0  287.93  4294.0  288.02  4370.7  284.90  4484.5  282.50  4592.7  280.50
  4733.3  277.88  4881.7  277.57  4961.9  277.76  4976.5  275.83  4986.3  272.89
  4993.8  270.40  5006.1  267.92  5006.3  267.42  5010.1  267.92  5018.6  272.44
  5030.9  273.41  5081.8  272.88  5094.6  276.75  5102.8  278.02  5121.1  278.53
  5165.9  278.47  5197.5  275.40  5221.9  273.95  5248.5  273.37  5266.4  274.82
  5277.4  275.91  5322.2  276.70  5374.5  278.93  5557.5  282.20  5850.0  290.44
#Mann=8,-1,0
  4264.0    0.05       0  4484.5    0.07       0  4592.7    0.05       0
  4881.7    0.07       0  4986.3    0.12       0  5006.1    0.05       0
  5010.1    0.12       0  5266.4    0.05       0
Bank Sta=5006.1,5010.1
Exp/Cntr=0.3,0.1

Type RM Length L Ch R = 1,1026,761,761,761
BEGIN DESCRIPTION:
XS7603
END DESCRIPTION:
XS GIS Cut Line= 4
      2453038.30     13698995.72      2453467.97     13698470.57
      2453359.46     13697975.78      2452890.68     13697493.98
#Sta/Elev= 30
  4080.8  285.59  4100.2  284.50  4157.6  283.10  4172.0  283.40  4199.3  282.13
  4320.6  279.17  4434.0  277.24  4586.3  276.05  4633.5  275.82  4806.0  275.53
  4913.5  276.21  4928.8  276.06  4969.8  272.04  4984.2  271.44  4990.3  271.94
  5019.0  269.50  5019.2  269.00  5023.0  269.50  5028.0  271.23  5033.1  271.24
  5061.9  276.44  5213.5  276.23  5256.4  274.83  5264.6  273.60  5305.0  271.00
  5326.1  271.39  5341.6  272.61  5382.7  275.32  5623.2  278.64  5938.1  286.69
#Mann=7,-1,0
  4080.8    0.05       0  4586.3    0.07       0  4633.5    0.05       0
  4913.5    0.12       0  5019.0    0.05       0  5023.0    0.12       0
  5341.6    0.05       0
Bank Sta=5019,5023
Exp/Cntr=0.3,0.1

Type RM Length L Ch R = 1,265,0,0,0
BEGIN DESCRIPTION:
XS7602
END DESCRIPTION:
XS GIS Cut Line= 4
      2453203.19     13698952.36      2453823.87     13698340.36
      2453763.11     13697680.64      2452999.65     13697376.99
#Sta/Elev= 30
  3471.8  280.26  3789.4  275.85  3945.0  275.92  4008.6  278.22  4047.6  275.56
  4114.7  273.59  4121.7  276.46  4128.8  274.96  4135.9  278.75  4157.1  279.90
  4171.3  279.02  4178.3  276.00  4223.5  274.89  4348.8  274.88  4368.9  271.68
  4389.9  274.37  4425.7  274.52  4859.6  273.05  5025.5  269.30  5055.0  264.23
  5055.3  263.73  5059.1  264.23  5068.5  272.17  5079.3  273.15  5226.4  275.13
  5323.8  274.99  5538.3  276.06  5685.7  279.39  5734.3  282.78  5827.6  281.10
#Mann=10,-1,0
  3471.8    0.05       0  4047.6    0.07       0  4223.5    0.12       0
  4425.7     0.1       0  4859.6    0.05       0  5055.0    0.05       0
  5059.1    0.05       0  5226.4     0.1       0  5323.8   0.063       0
  5538.3    0.05       0
Bank Sta=5055,5059.1
Exp/Cntr=0.3,0.1

Chan Stop Cuts=-1