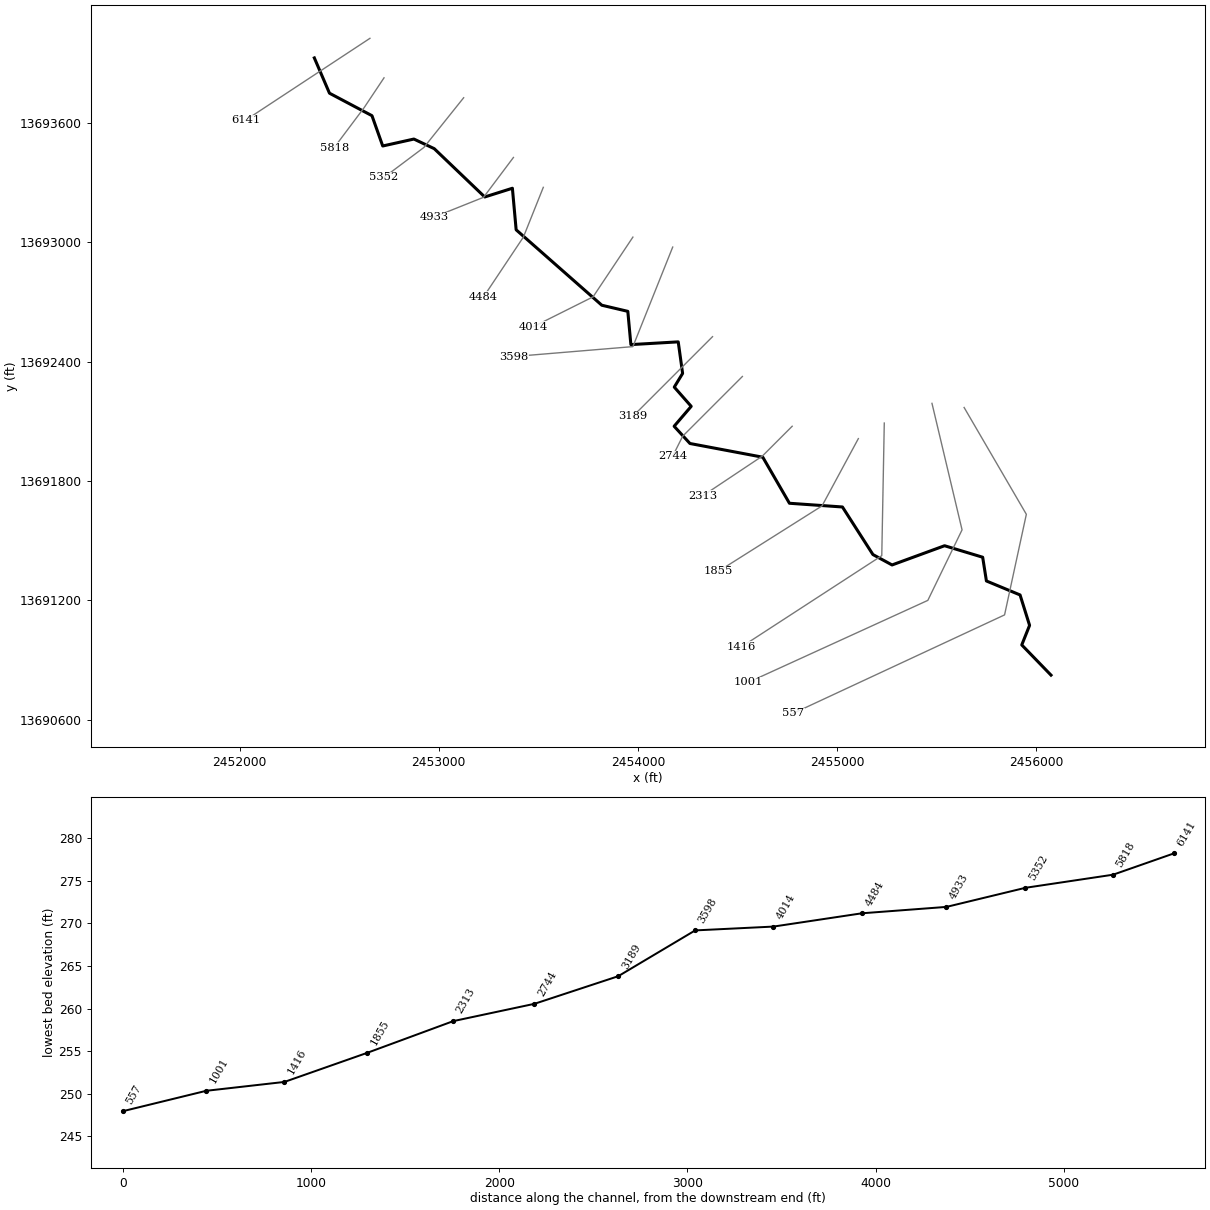
--- Stream0736.prj (project) ---

Proj Title=Stream0736 Base Level Engineering
Current Plan=p01
Default Exp/Contr=0.3,0.1
English Units
Geom File=g01
Flow File=f01
Plan File=p01
BEGIN DESCRIPTION:
Stream0736
END DESCRIPTION:

--- Stream0736.p01 (plan) ---

Plan Title=Multiple Run
Short Identifier=Multiple
Geom File=g01
Flow File=f01
Subcritical Flow
K Sum by GR= 0
Std Step Tol= 0.01
Critical Tol= 0.01
Num of Std Step Trials= 20
Max Error Tol= 0.3
Flow Tol Ratio= 0.001
Split Flow NTrial= 30
Split Flow Tol= 0.02
Split Flow Ratio= 0.02
Log Output Level= 0
Friction Slope Method= 1
Unsteady Friction Slope Method= 2
Unsteady Bridges Friction Slope Method= 1
Parabolic Critical Depth
Global Vel Dist=  1 , 1 , 1
Global Log Level= 0
CheckData=True
Encroach Param= -1, 0, 0, 0
BEGIN DESCRIPTION:
Multiple Run
END DESCRIPTION:

--- Stream0736.f01 (steady flow) ---

Flow Title=Multiple
Number of Profiles=7
Profile Names=10-year,25-year,50-year,1pct_min,100-year,1pct_plu,500-year
River Rch & RM= Stream0736,Reach-1,6141
     423     659     865     550    1097    2190    1749
Boundary for River Rch & Prof#=Stream0736,Reach-1,1
Up Type=0
Dn Type=3
Dn Slope=0.005
Boundary for River Rch & Prof#=Stream0736,Reach-1,2
Up Type=0
Dn Type=3
Dn Slope=0.005
Boundary for River Rch & Prof#=Stream0736,Reach-1,3
Up Type=0
Dn Type=3
Dn Slope=0.005
Boundary for River Rch & Prof#=Stream0736,Reach-1,4
Up Type=0
Dn Type=3
Dn Slope=0.005
Boundary for River Rch & Prof#=Stream0736,Reach-1,5
Up Type=0
Dn Type=3
Dn Slope=0.005
Boundary for River Rch & Prof#=Stream0736,Reach-1,6
Up Type=0
Dn Type=3
Dn Slope=0.005
Boundary for River Rch & Prof#=Stream0736,Reach-1,7
Up Type=0
Dn Type=3
Dn Slope=0.005

--- Stream0736.g01 (geometry) ---

Geom Title=Existing Conditions

River Reach=Stream0736,Reach-1
Reach XY= 30
      2452375.00     13693925.00      2452451.10     13693747.72
      2452664.49     13693634.81      2452718.50     13693482.63
      2452875.01     13693517.47      2452977.28     13693469.18
      2453230.86     13693226.55      2453369.76     13693270.37
      2453388.64     13693061.66      2453818.83     13692682.86
      2453949.46     13692652.14      2453964.88     13692485.06
      2454202.69     13692498.85      2454224.71     13692340.36
      2454182.85     13692271.59      2454267.88     13692175.00
      2454182.09     13692074.99      2454261.62     13691988.37
      2454627.44     13691919.48      2454761.27     13691688.20
      2455027.47     13691669.55      2455180.58     13691430.58
      2455276.69     13691378.33      2455540.39     13691474.91
      2455731.80     13691417.14      2455750.59     13691297.88
      2455919.60     13691227.71      2455967.41     13691074.99
      2455928.15     13690976.65      2456075.00     13690825.00

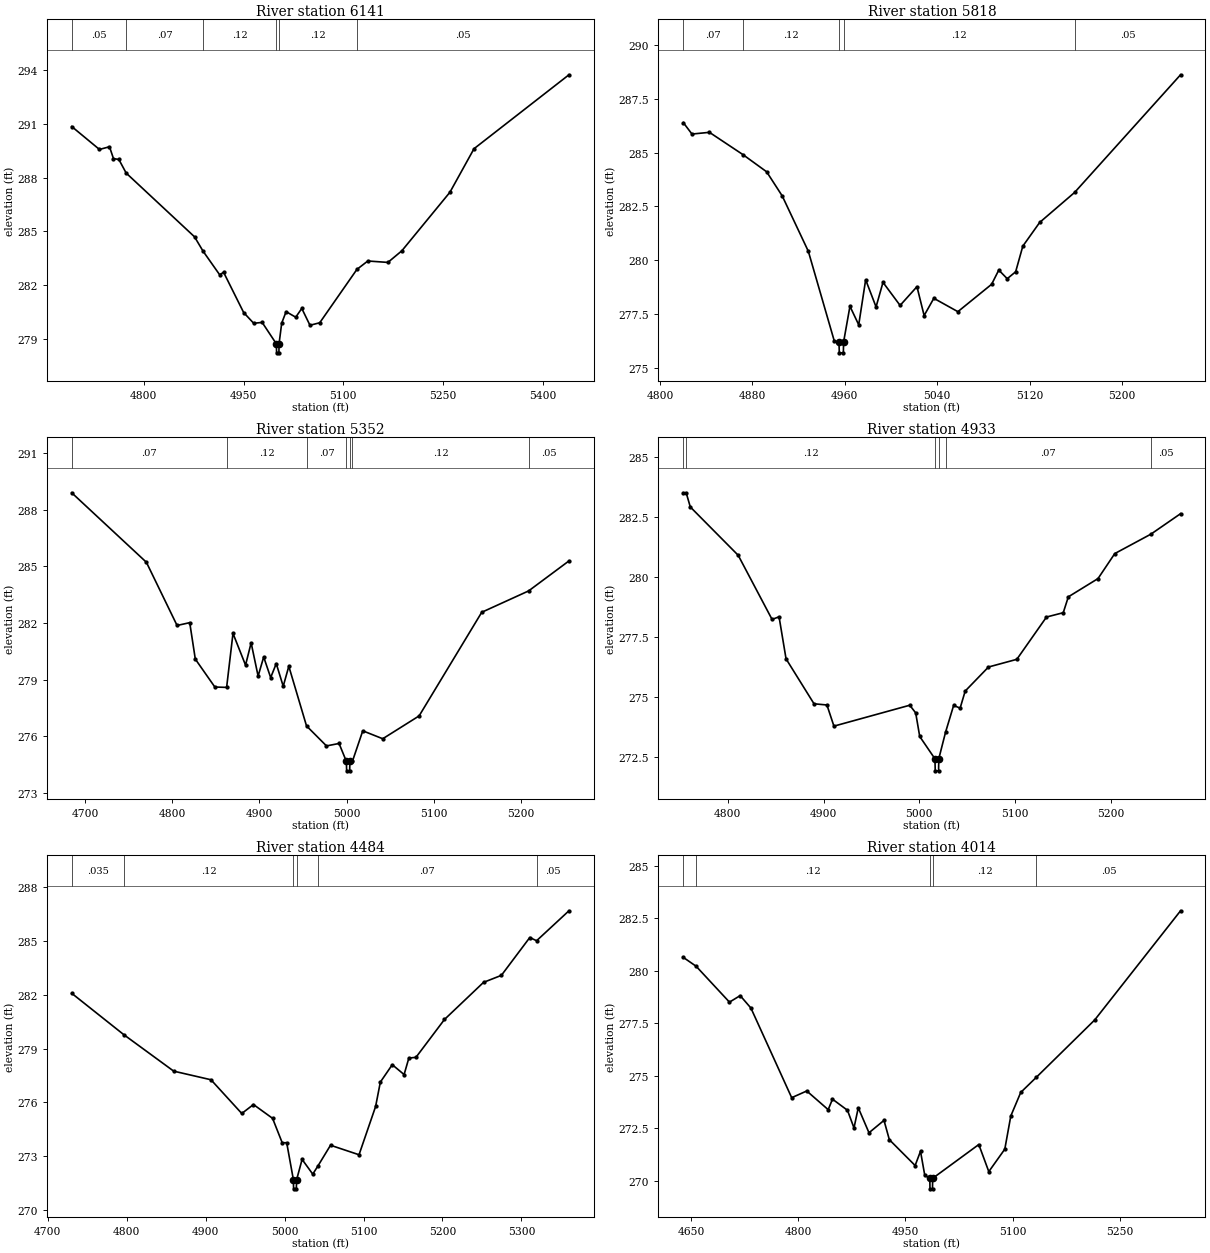
Type RM Length L Ch R = 1,6141,323,323,323
BEGIN DESCRIPTION:
XS7613
END DESCRIPTION:
XS GIS Cut Line= 2
      2452654.24     13694023.34      2452029.65     13693612.15
#Sta/Elev= 30
  4691.6  290.85  4733.3  289.57  4748.4  289.72  4754.4  289.06  4762.5  289.01
  4773.5  288.25  4876.3  284.69  4889.1  283.89  4914.1  282.57  4920.0  282.71
  4950.2  280.46  4965.3  279.86  4978.0  279.91  4999.4  278.71  4999.7  278.21
  5003.2  278.21  5003.4  278.71  5007.4  279.87  5014.0  280.51  5028.5  280.20
  5037.6  280.69  5049.9  279.75  5064.6  279.89  5120.5  282.87  5136.9  283.34
  5167.1  283.26  5188.1  283.91  5260.4  287.18  5296.6  289.61  5439.4  293.74
#Mann=6,-1,0
  4691.6    0.05       0  4773.5    0.07       0  4889.1    0.12       0
  4999.4    0.05       0  5003.4    0.12       0  5120.5    0.05       0
Bank Sta=4999.4,5003.4
Exp/Cntr=0.3,0.1

Type RM Length L Ch R = 1,5818,466,466,466
BEGIN DESCRIPTION:
Stream0736 11.0
END DESCRIPTION:
XS GIS Cut Line= 3
      2452725.01     13693825.01      2452625.00     13693675.00
      2452475.00     13693475.00
#Sta/Elev= 30
  4820.2  286.39  4827.7  285.86  4842.8  285.94  4871.7  284.91  4892.3  284.11
  4905.8  282.99  4928.4  280.42  4950.9  276.25  4954.9  276.21  4955.2  275.71
  4958.7  275.71  4958.9  276.21  4964.4  277.87  4972.0  277.01  4978.0  279.10
  4987.0  277.84  4993.0  278.98  5007.8  277.91  5022.4  278.78  5028.6  277.44
  5037.0  278.24  5057.8  277.62  5087.0  278.89  5093.2  279.55  5100.5  279.15
  5107.8  279.47  5114.0  280.66  5128.6  281.76  5158.8  283.15  5250.5  288.61
#Mann=5,-1,0
  4820.2    0.07       0  4871.7    0.12       0  4954.9    0.05       0
  4958.9    0.12       0  5158.8    0.05       0
Bank Sta=4954.9,4958.9
Exp/Cntr=0.3,0.1

Type RM Length L Ch R = 1,5352,419,419,419
BEGIN DESCRIPTION:
Stream0736 10.0
END DESCRIPTION:
XS GIS Cut Line= 3
      2453124.99     13693724.99      2452925.00     13693475.00
      2452725.03     13693325.02
#Sta/Elev= 30
  4684.9  288.90  4770.5  285.22  4805.7  281.87  4820.2  282.02  4826.6  280.09
  4849.0  278.61  4862.5  278.59  4869.8  281.45  4884.2  279.77  4890.6  280.95
  4898.6  279.19  4905.0  280.20  4913.0  279.11  4919.4  279.85  4927.4  278.65
  4933.8  279.71  4954.1  276.55  4977.0  275.49  4991.4  275.62  4999.8  274.67
  5000.1  274.17  5003.6  274.17  5003.8  274.67  5006.7  274.67  5018.6  276.29
  5041.5  275.87  5083.2  277.08  5155.0  282.57  5208.7  283.70  5255.0  285.29
#Mann=7,-1,0
  4684.9    0.07       0  4862.5    0.12       0  4954.1    0.07       0
  4999.8    0.05       0  5003.8    0.07       0  5006.7    0.12       0
  5208.7    0.05       0
Bank Sta=4999.8,5003.8
Exp/Cntr=0.3,0.1

Type RM Length L Ch R = 1,4933,449,449,449
BEGIN DESCRIPTION:
Stream0736 9.0
END DESCRIPTION:
XS GIS Cut Line= 3
      2453375.01     13693425.01      2453225.00     13693225.00
      2452974.98     13693124.99
#Sta/Elev= 30
  4753.5  283.50  4756.5  283.50  4760.8  282.91  4810.8  280.90  4846.2  278.23
  4853.5  278.34  4860.8  276.59  4890.0  274.72  4903.5  274.67  4910.8  273.79
  4990.0  274.66  4996.2  274.34  5000.4  273.36  5016.3  272.43  5016.6  271.93
  5020.1  271.93  5020.3  272.43  5027.4  273.54  5035.8  274.65  5042.6  274.54
  5047.9  275.25  5072.2  276.25  5101.8  276.57  5132.8  278.33  5150.3  278.51
  5155.6  279.17  5186.6  279.93  5204.1  280.97  5241.9  281.78  5272.8  282.63
#Mann=6,-1,0
  4753.5    0.07       0  4756.5    0.12       0  5016.3    0.05       0
  5020.3    0.12       0  5027.4    0.07       0  5241.9    0.05       0
Bank Sta=5016.3,5020.3
Exp/Cntr=0.3,0.1

Type RM Length L Ch R = 1,4484,470,470,470
BEGIN DESCRIPTION:
Stream0736 8.0
END DESCRIPTION:
XS GIS Cut Line= 3
      2453525.00     13693274.99      2453425.00     13693025.00
      2453225.00     13692725.00
#Sta/Elev= 30
  4730.4  282.08  4796.5  279.77  4859.6  277.74  4906.8  277.26  4945.8  275.38
  4960.6  275.88  4984.8  275.11  4997.0  273.75  5002.7  273.75  5011.2  271.68
  5011.4  271.18  5014.9  271.18  5015.2  271.68  5022.2  272.82  5035.7  272.00
  5041.9  272.43  5058.2  273.61  5094.3  273.08  5115.3  275.77  5121.3  277.13
  5136.4  278.10  5151.4  277.55  5157.4  278.47  5166.4  278.51  5202.5  280.62
  5252.0  282.69  5274.6  283.08  5310.6  285.19  5319.2  285.01  5360.2  286.68
#Mann=6,-1,0
  4730.4   0.035       0  4796.5    0.12       0  5011.2    0.05       0
  5015.2    0.12       0  5041.9    0.07       0  5319.2    0.05       0
Bank Sta=5011.2,5015.2
Exp/Cntr=0.3,0.1

Type RM Length L Ch R = 1,4014,416,416,416
BEGIN DESCRIPTION:
Stream0736 7.0
END DESCRIPTION:
XS GIS Cut Line= 3
      2453974.99     13693024.99      2453775.00     13692725.00
      2453474.96     13692574.98
#Sta/Elev= 30
  4639.2  280.64  4657.1  280.22  4703.8  278.51  4718.8  278.82  4733.8  278.23
  4790.9  273.96  4812.0  274.28  4842.0  273.39  4848.0  273.89  4869.0  273.36
  4878.1  272.52  4884.1  273.48  4899.1  272.29  4920.1  272.88  4927.6  271.96
  4963.7  270.73  4971.2  271.41  4977.2  270.26  4984.2  270.12  4984.5  269.62
  4988.0  269.62  4988.2  270.12  5052.8  271.73  5066.8  270.44  5089.2  271.51
  5097.6  273.09  5111.5  274.21  5133.3  274.93  5215.0  277.66  5335.2  282.86
#Mann=5,-1,0
  4639.2    0.05       0  4657.1    0.12       0  4984.2    0.05       0
  4988.2    0.12       0  5133.3    0.05       0
Bank Sta=4984.2,4988.2
Exp/Cntr=0.3,0.1

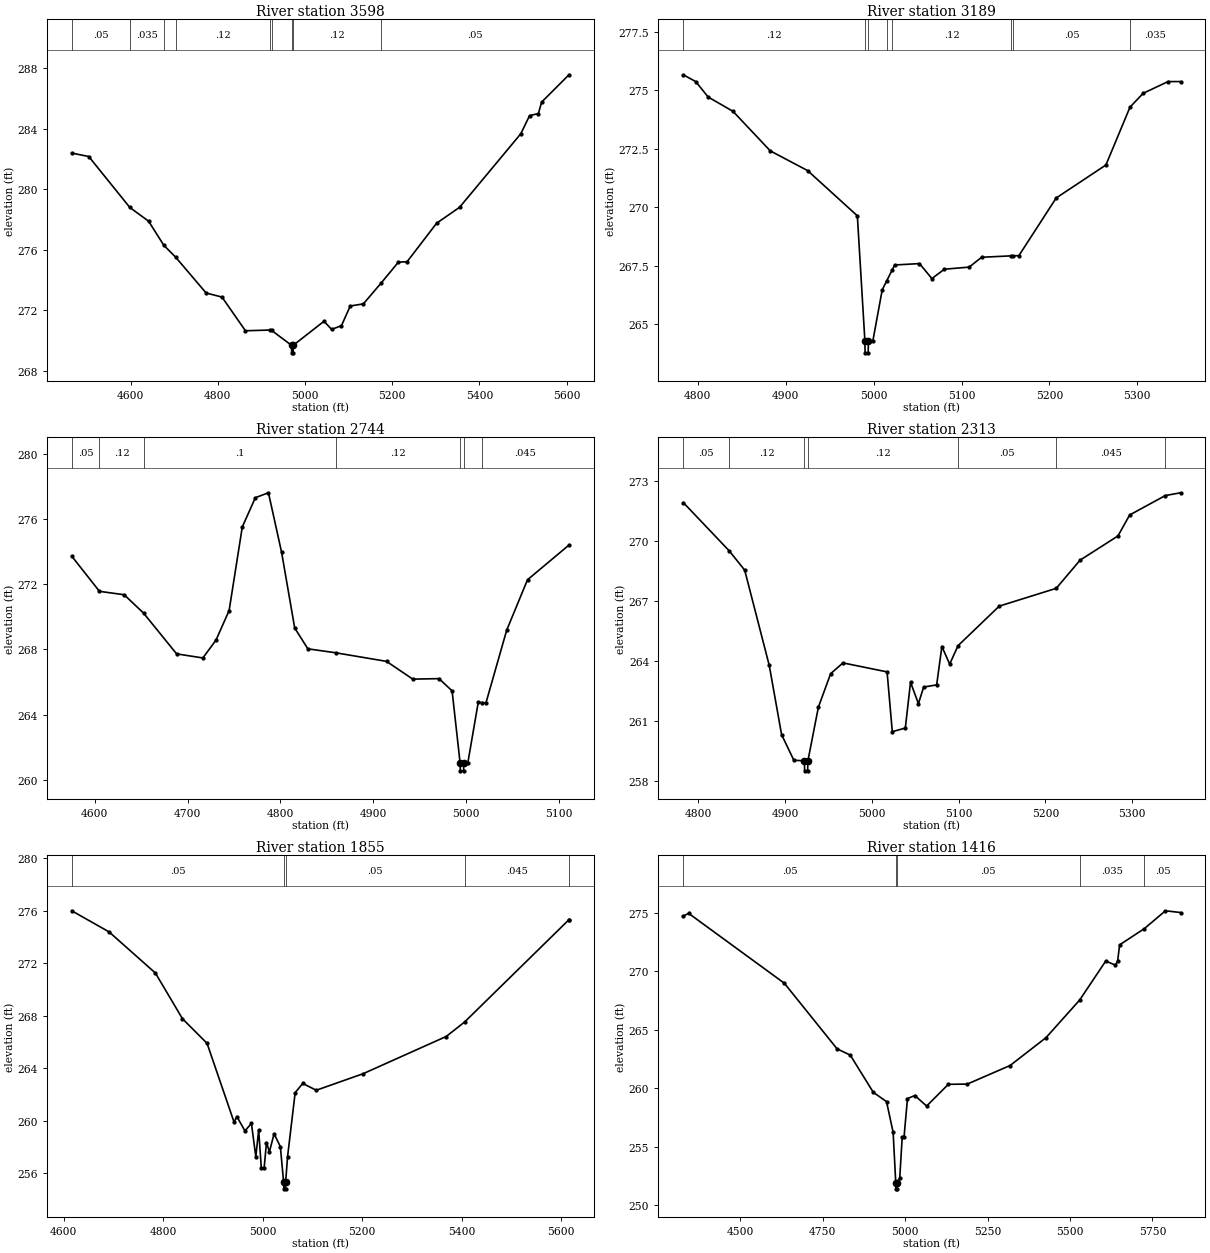
Type RM Length L Ch R = 1,3598,409,409,409
BEGIN DESCRIPTION:
Stream0736 6.0
END DESCRIPTION:
XS GIS Cut Line= 3
      2454175.01     13692975.02      2453975.00     13692475.00
      2453375.02     13692425.00
#Sta/Elev= 30
  4464.8  282.39  4503.9  282.16  4598.1  278.79  4641.2  277.88  4676.0  276.29
  4703.2  275.50  4773.1  273.13  4809.5  272.86  4863.3  270.63  4920.0  270.68
  4923.4  270.65  4969.0  269.67  4969.3  269.17  4972.8  269.17  4973.0  269.67
  5043.5  271.26  5061.0  270.72  5083.6  270.97  5103.7  272.27  5133.8  272.41
  5174.9  273.80  5214.1  275.17  5234.1  275.20  5301.9  277.75  5354.5  278.80
  5495.0  283.67  5515.1  284.87  5535.2  285.00  5542.7  285.76  5605.4  287.57
#Mann=9,-1,0
  4464.8    0.05       0  4598.1   0.035       0  4676.0    0.05       0
  4703.2    0.12       0  4920.0   0.035       0  4923.4    0.12       0
  4969.0    0.05       0  4973.0    0.12       0  5174.9    0.05       0
Bank Sta=4969,4973
Exp/Cntr=0.3,0.1

Type RM Length L Ch R = 1,3189,445,445,445
BEGIN DESCRIPTION:
Stream0736 5.0
END DESCRIPTION:
XS GIS Cut Line= 3
      2454374.99     13692524.99      2454225.00     13692375.00
      2453974.97     13692124.97
#Sta/Elev= 30
  4783.5  275.66  4797.6  275.37  4811.8  274.71  4840.0  274.10  4882.5  272.41
  4924.9  271.57  4981.5  269.64  4990.1  264.29  4990.3  263.79  4993.8  263.79
  4994.1  264.29  4999.1  264.29  5009.8  266.48  5015.0  266.87  5021.0  267.32
  5023.9  267.54  5052.2  267.60  5066.3  266.96  5080.5  267.36  5108.7  267.45
  5122.9  267.87  5156.3  267.93  5158.4  267.93  5165.3  267.94  5207.7  270.40
  5264.3  271.81  5291.7  274.28  5306.7  274.87  5335.0  275.37  5349.2  275.37
#Mann=8,-1,0
  4783.5    0.12       0  4990.1    0.05       0  4994.1    0.12       0
  5015.0     0.1       0  5021.0    0.12       0  5156.3   0.035       0
  5158.4    0.05       0  5291.7   0.035       0
Bank Sta=4990.1,4994.1
Exp/Cntr=0.3,0.1

Type RM Length L Ch R = 1,2744,431,431,431
BEGIN DESCRIPTION:
Stream0736 4.0
END DESCRIPTION:
XS GIS Cut Line= 3
      2454525.01     13692325.01      2454225.00     13692025.00
      2454174.99     13691924.98
#Sta/Elev= 30
  4575.1  273.73  4605.0  271.57  4631.7  271.36  4652.6  270.23  4688.2  267.73
  4716.5  267.48  4730.7  268.58  4744.8  270.39  4759.0  275.52  4773.1  277.32
  4787.2  277.62  4801.4  273.96  4815.5  269.32  4829.7  268.04  4859.5  267.80
  4914.5  267.27  4942.8  266.18  4971.1  266.21  4985.2  265.46  4993.8  261.05
  4994.1  260.55  4997.6  260.55  4997.8  261.05  5002.2  261.05  5013.4  264.76
  5017.3  264.74  5021.7  264.72  5044.1  269.19  5066.5  272.28  5111.2  274.41
#Mann=7,-1,0
  4575.1    0.05       0  4605.0    0.12       0  4652.6     0.1       0
  4859.5    0.12       0  4993.8    0.05       0  4997.8    0.12       0
  5017.3   0.045       0
Bank Sta=4993.8,4997.8
Exp/Cntr=0.3,0.1

Type RM Length L Ch R = 1,2313,458,458,458
BEGIN DESCRIPTION:
Stream0736 3.0
END DESCRIPTION:
XS GIS Cut Line= 3
      2454775.03     13692075.03      2454625.00     13691925.00
      2454325.02     13691725.01
#Sta/Elev= 30
  4782.9  271.94  4835.9  269.52  4853.6  268.56  4881.9  263.79  4896.1  260.33
  4910.2  259.05  4922.4  259.02  4922.6  258.52  4926.1  258.52  4926.4  259.02
  4938.5  261.71  4952.6  263.38  4966.8  263.92  5017.6  263.47  5023.6  260.48
  5038.6  260.66  5044.6  262.95  5053.7  261.88  5059.7  262.71  5074.7  262.82
  5080.7  264.74  5089.7  263.86  5099.3  264.78  5146.8  266.76  5212.4  267.65
  5239.9  269.06  5283.5  270.27  5297.0  271.32  5338.0  272.29  5355.6  272.43
#Mann=7,-1,0
  4782.9    0.05       0  4835.9    0.12       0  4922.4    0.05       0
  4926.4    0.12       0  5099.3    0.05       0  5212.4   0.045       0
  5338.0    0.05       0
Bank Sta=4922.4,4926.4
Exp/Cntr=0.3,0.1

Type RM Length L Ch R = 1,1855,439,439,439
BEGIN DESCRIPTION:
Stream0736 2.0
END DESCRIPTION:
XS GIS Cut Line= 3
      2455107.37     13692012.92      2454925.00     13691675.00
      2454404.27     13691346.28
#Sta/Elev= 30
  4616.1  276.00  4691.2  274.39  4784.4  271.25  4838.7  267.77  4888.2  265.89
  4942.5  259.88  4948.2  260.30  4964.4  259.21  4977.4  259.78  4986.3  257.23
  4992.0  259.28  4997.3  256.38  5003.0  256.38  5007.7  258.32  5013.6  257.62
  5023.0  258.99  5035.6  258.01  5042.2  255.29  5042.5  254.79  5046.0  254.79
  5046.2  255.29  5050.1  257.24  5065.4  262.13  5080.7  262.83  5107.8  262.31
  5201.9  263.57  5369.0  266.41  5405.9  267.51  5615.1  275.29  5615.9  275.29
#Mann=5,-1,0
  4616.1    0.05       0  5042.2    0.05       0  5046.2    0.05       0
  5405.9   0.045       0  5615.1   0.035       0
Bank Sta=5042.2,5046.2
Exp/Cntr=0.3,0.1

Type RM Length L Ch R = 1,1416,415,415,415
BEGIN DESCRIPTION:
Stream0736 1.0
END DESCRIPTION:
XS GIS Cut Line= 3
      2455237.59     13692091.10      2455225.00     13691425.00
      2454519.43     13690966.45
#Sta/Elev= 30
  4327.6  274.73  4343.7  274.97  4633.8  268.99  4793.8  263.37  4833.8  262.83
  4903.8  259.64  4943.8  258.85  4963.8  256.22  4971.8  251.88  4972.1  251.38
  4975.6  251.38  4975.8  251.88  4983.8  252.29  4991.3  255.79  4996.8  255.79
  5007.3  259.11  5029.6  259.37  5065.4  258.47  5131.2  260.33  5188.6  260.35
  5318.4  261.94  5427.1  264.32  5529.2  267.54  5608.3  270.88  5637.8  270.54
  5644.5  270.87  5650.5  272.27  5725.9  273.67  5789.5  275.19  5835.3  275.04
#Mann=5,-1,0
  4327.6    0.05       0  4971.8    0.05       0  4975.8    0.05       0
  5529.2   0.035       0  5725.9    0.05       0
Bank Sta=4971.8,4975.8
Exp/Cntr=0.3,0.1

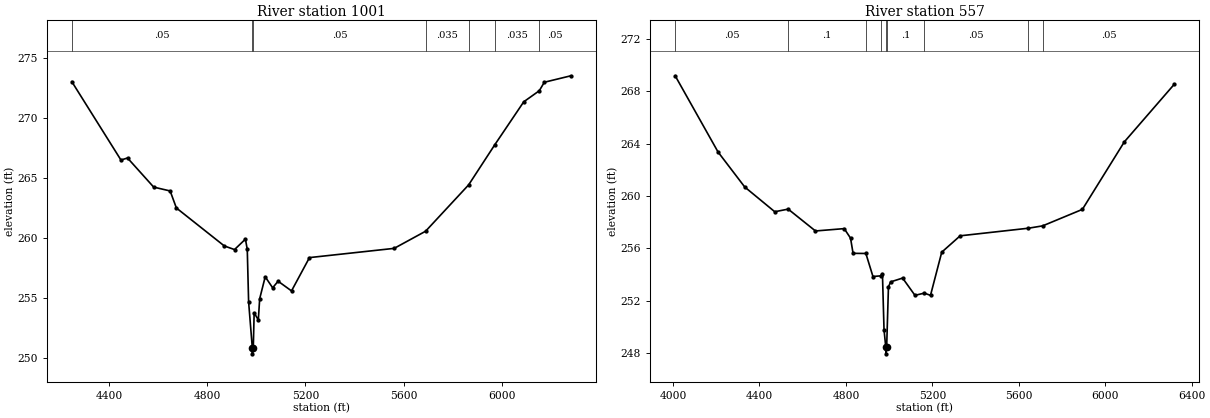
Type RM Length L Ch R = 1,1001,444,444,444
BEGIN DESCRIPTION:
XS7612
END DESCRIPTION:
XS GIS Cut Line= 4
      2455477.17     13692190.02      2455628.21     13691554.60
      2455456.34     13691200.43      2454556.42     13690789.49
#Sta/Elev= 30
  4246.7  273.05  4447.2  266.51  4474.0  266.68  4580.8  264.25  4647.9  263.93
  4673.3  262.51  4869.0  259.34  4910.5  259.04  4955.0  259.91  4962.5  259.06
  4968.0  254.68  4983.1  250.84  4983.3  250.34  4987.1  250.84  4990.6  253.76
  5007.6  253.17  5013.2  254.94  5035.7  256.77  5066.1  255.85  5088.3  256.40
  5143.0  255.59  5216.3  258.37  5561.8  259.14  5690.0  260.57  5865.7  264.44
  5972.5  267.79  6090.5  271.37  6153.8  272.29  6174.4  273.00  6282.8  273.54
#Mann=7,-1,0
  4246.7    0.05       0  4983.1    0.05       0  4987.1    0.05       0
  5690.0   0.035       0  5865.7    0.05       0  5972.5   0.035       0
  6153.8    0.05       0
Bank Sta=4983.1,4987.1
Exp/Cntr=0.3,0.1

Type RM Length L Ch R = 1,557,0,0,0
BEGIN DESCRIPTION:
XS7611
END DESCRIPTION:
XS GIS Cut Line= 4
      2455638.63     13692169.19      2455951.13     13691632.73
      2455841.75     13691127.52      2454779.63     13690632.90
#Sta/Elev= 30
  4009.8  269.19  4208.4  263.36  4331.7  260.69  4470.6  258.80  4532.7  259.00
  4659.0  257.33  4792.0  257.51  4821.3  256.78  4833.0  255.62  4892.2  255.61
  4925.0  253.85  4961.0  253.90  4968.9  254.07  4976.2  249.79  4984.4  248.44
  4984.7  247.94  4988.4  248.44  4996.7  253.06  5006.9  253.44  5062.2  253.73
  5119.4  252.41  5162.5  252.58  5191.3  252.41  5243.3  255.71  5328.6  256.96
  5644.2  257.54  5710.3  257.72  5894.1  258.98  6088.2  264.14  6319.2  268.54
#Mann=9,-1,0
  4009.8    0.05       0  4532.7     0.1       0  4892.2    0.05       0
  4961.0     0.1       0  4984.4    0.05       0  4988.4     0.1       0
  5162.5    0.05       0  5644.2   0.035       0  5710.3    0.05       0
Bank Sta=4984.4,4988.4
Exp/Cntr=0.3,0.1

Chan Stop Cuts=-1