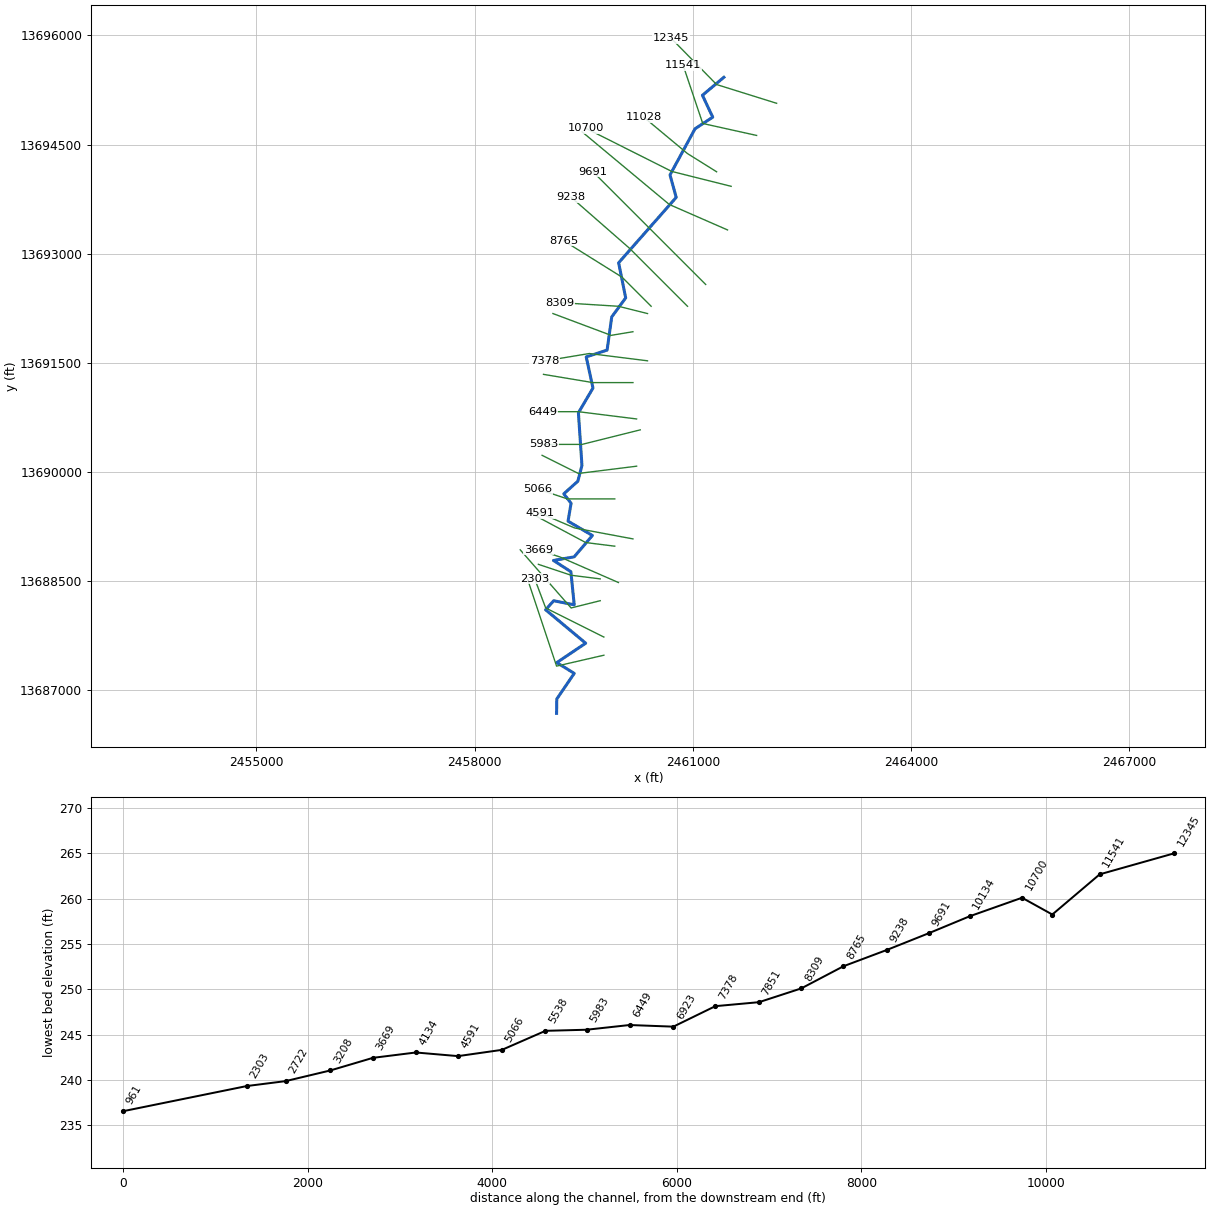
--- Stream0737.prj (project) ---

Proj Title=Stream0737 Base Level Engineering
Current Plan=p01
Default Exp/Contr=0.3,0.1
English Units
Geom File=g01
Flow File=f01
Plan File=p01
Y Axis Title=Elevation
X Axis Title(PF)=Main Channel Distance
X Axis Title(XS)=Station
BEGIN DESCRIPTION:
Stream0737
END DESCRIPTION:
DSS Export Rating Curves= 0
DSS Export Rating Curve Sorted= 0
DSS Export Volume Flow Curves= 0
DXF OffsetX= 0
DXF OffsetY= 0
DXF ScaleX= 1
DXF ScaleY= 10

--- Stream0737.p01 (plan) ---

Plan Title=Multiple Run
Short Identifier=Multiple
Geom File=g01
Flow File=f01
Subcritical Flow
K Sum by GR= 0
Std Step Tol= 0.01
Critical Tol= 0.01
Num of Std Step Trials= 20
Max Error Tol= 0.3
Flow Tol Ratio= 0.001
Split Flow NTrial= 30
Split Flow Tol= 0.02
Split Flow Ratio= 0.02
Log Output Level= 0
Friction Slope Method= 1
Unsteady Friction Slope Method= 2
Unsteady Bridges Friction Slope Method= 1
Parabolic Critical Depth
Global Vel Dist=  1 , 1 , 1
Global Log Level= 0
CheckData=True
Encroach Param= -1, 0, 0, 0
BEGIN DESCRIPTION:
Multiple Run
END DESCRIPTION:

--- Stream0737.f01 (steady flow) ---

Flow Title=Multiple
Number of Profiles=7
Profile Names=10-year,25-year,50-year,1pct_min,100-year,1pct_plu,500-year
River Rch & RM= Stream0737,Reach-1,12345
     919    1498    2025    1324    2642    5271    4454
River Rch & RM= Stream0737,Reach-1,11541
     935    1522    2058    1345    2683    5354    4519
River Rch & RM= Stream0737,Reach-1,11028
    1490    2471    3379    2229    4447    8873    7636
Boundary for River Rch & Prof#=Stream0737,Reach-1,1
Up Type=0
Dn Type=3
Dn Slope=0.005
Boundary for River Rch & Prof#=Stream0737,Reach-1,2
Up Type=0
Dn Type=3
Dn Slope=0.005
Boundary for River Rch & Prof#=Stream0737,Reach-1,3
Up Type=0
Dn Type=3
Dn Slope=0.005
Boundary for River Rch & Prof#=Stream0737,Reach-1,4
Up Type=0
Dn Type=3
Dn Slope=0.005
Boundary for River Rch & Prof#=Stream0737,Reach-1,5
Up Type=0
Dn Type=3
Dn Slope=0.005
Boundary for River Rch & Prof#=Stream0737,Reach-1,6
Up Type=0
Dn Type=3
Dn Slope=0.005
Boundary for River Rch & Prof#=Stream0737,Reach-1,7
Up Type=0
Dn Type=3
Dn Slope=0.005

--- Stream0737.g01 (geometry) ---

Geom Title=Existing Conditions
Program Version=4.10

River Reach=Stream0737      ,Reach-1
Reach XY= 30
        2461425.       13695425.      2461130.05     13695177.27
      2461271.56     13694876.25      2461028.32     13694716.66
      2460684.29     13694081.67      2460769.61     13693772.56
      2459978.14     13692873.36      2460075.05     13692390.34
      2459883.24     13692128.23       2459819.6     13691672.29
      2459532.68     13691578.71      2459625.32     13691149.89
      2459425.25     13690809.78      2459473.79     13690085.51
       2459417.3     13689868.53      2459224.53     13689695.17
      2459324.39     13689564.38      2459282.81     13689318.81
      2459617.49     13689121.89       2459366.7     13688828.07
      2459082.39     13688778.44      2459321.55     13688623.75
      2459367.64     13688168.57      2459085.61     13688224.41
      2458974.41       13688100.      2459525.11     13687640.36
      2459127.99     13687373.54      2459367.79     13687225.35
      2459128.13     13686873.37        2459125.       13686675.

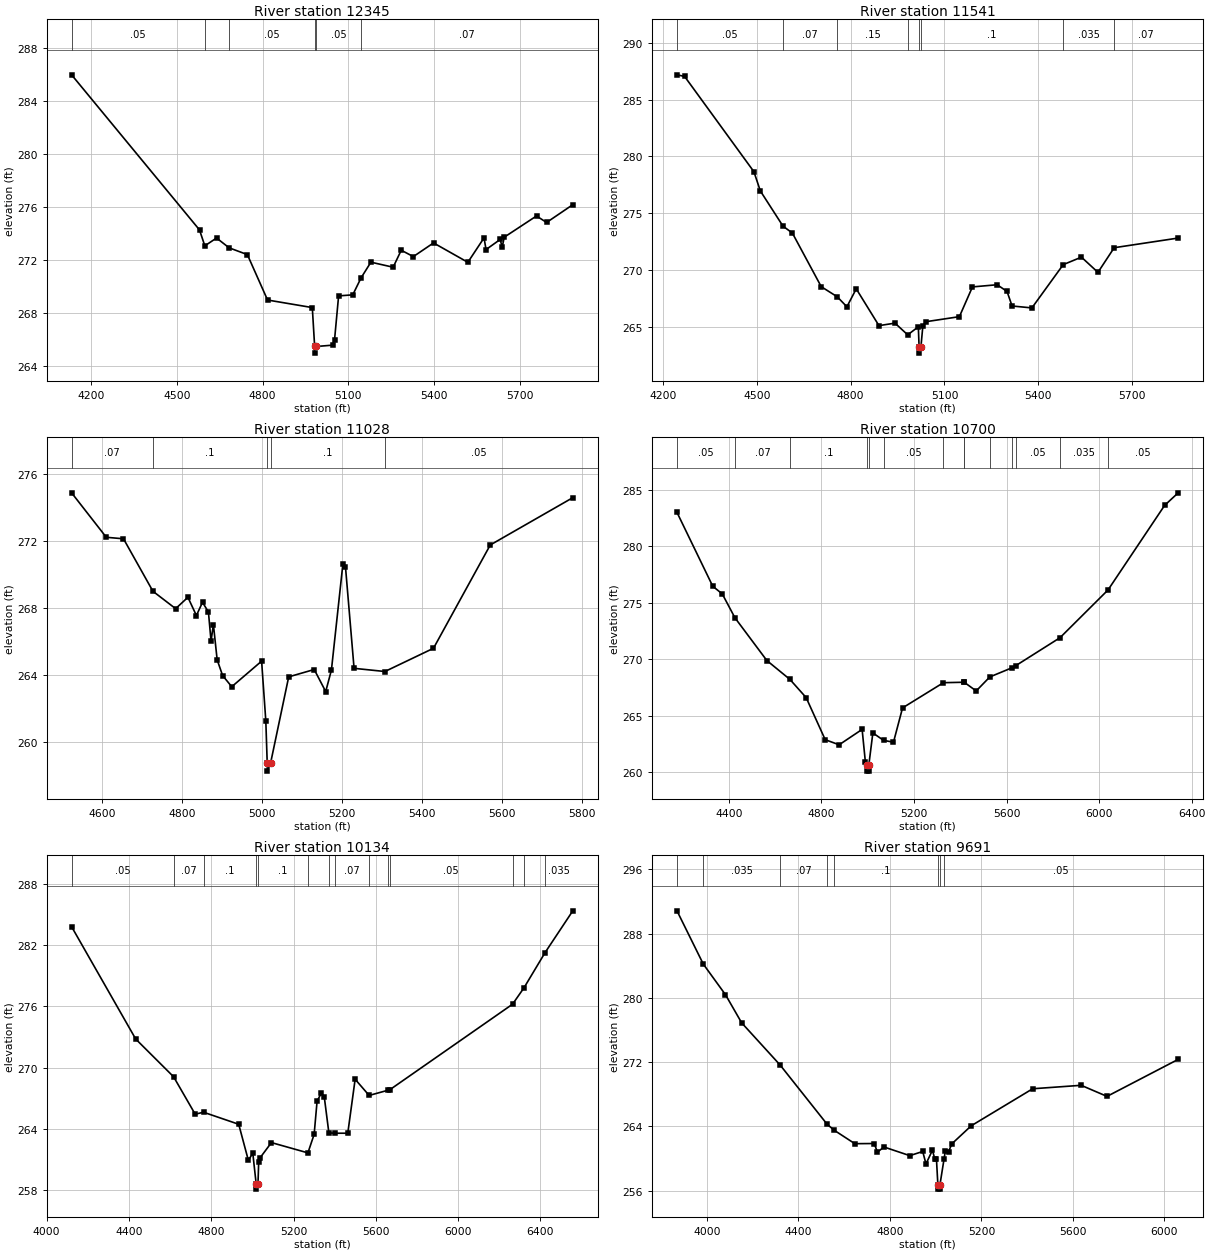
Type RM Length L Ch R = 1 ,12345   ,804,804,804
BEGIN DESCRIPTION:
Stream0737 23.0
END DESCRIPTION:
XS GIS Cut Line= 3
      2462149.98     13695067.15        2461325.       13695325.
      2460700.95     13695960.63
#Sta/Elev= 30
  4130.9  285.95  4578.8  274.27  4597.4  273.07  4638.5  273.66  4682.6  272.92
  4746.4  272.41  4817.1  268.99  4973.8  268.42    4982  265.49  4982.5  264.99
  4987.5  265.49  5044.7  265.59  5051.7     266  5065.9   269.3  5115.5  269.38
  5144.6  270.66    5179  271.84  5256.9  271.46  5285.2  272.74  5327.6  272.26
  5398.3  273.29  5518.5  271.83  5575.1  273.67  5582.2  272.79  5631.7  273.55
  5638.8  272.97  5645.8  273.72  5758.9  275.32  5794.2  274.83    5886  276.17
#Mann= 6 ,-1 , 0
  4130.9     .05       0  4597.4     .07       0  4682.6     .05       0
    4982     .05       0  4987.5     .05       0  5144.6     .07       0
Bank Sta=4982,4987.5
XS Rating Curve= 0 ,0
Exp/Cntr=0.3,0.1

Type RM Length L Ch R = 1 ,11541   ,513,513,513
BEGIN DESCRIPTION:
Stream0737 22.0
END DESCRIPTION:
XS GIS Cut Line= 3
      2461874.98       13694625.      2461134.38     13694789.36
       2460865.3     13695587.93
#Sta/Elev= 30
  4245.3  287.18  4269.6  287.04  4491.1  278.65  4511.6  276.96    4584  273.86
    4614  273.25  4706.2  268.53  4757.3  267.64  4788.2  266.76    4818  268.34
  4890.6   265.1  4941.8  265.32  4982.5  264.29  5016.4     265  5018.9  263.18
  5019.3  262.68  5024.5  263.18    5031  265.11  5041.5  265.45  5147.6  265.89
  5189.3  268.51  5268.3   268.7  5299.8  268.11  5315.9  266.83  5379.2  266.66
  5479.3  270.47  5537.5  271.13  5590.3  269.79  5642.1  271.96  5846.6  272.81
#Mann= 8 ,-1 , 0
  4245.3     .05       0    4584     .07       0  4757.3     .15       0
  4982.5      .1       0  5018.9     .05       0  5024.5      .1       0
  5479.3    .035       0  5642.1     .07       0
Bank Sta=5018.9,5024.5
XS Rating Curve= 0 ,0
Exp/Cntr=0.3,0.1

Type RM Length L Ch R = 1 ,11028   ,328,328,328
BEGIN DESCRIPTION:
Stream0737 21.0
END DESCRIPTION:
XS GIS Cut Line= 3
      2461324.99       13694125.        2460925.       13694375.
      2460325.01     13694874.99
#Sta/Elev= 30
  4524.2   274.9  4610.9  272.24  4653.9  272.15  4727.5  269.01  4784.2  267.97
  4814.9  268.65  4836.1  267.56  4851.4  268.35  4866.2  267.77  4872.7  266.03
  4878.6  267.02    4888  264.91  4901.6  263.97  4924.5   263.3  4999.1  264.83
  5009.6  261.26  5013.1  258.75  5013.6  258.25  5021.7  258.75  5066.8  263.89
  5130.6  264.33  5159.3  263.01  5173.6   264.3  5202.2  270.63  5208.7  270.48
  5230.2   264.4  5307.3  264.21  5428.7   265.6  5570.6  271.78  5776.9  274.61
#Mann= 5 ,-1 , 0
  4524.2     .07       0  4727.5      .1       0  5013.1     .05       0
  5021.7      .1       0  5307.3     .05       0
Bank Sta=5013.1,5021.7
XS Rating Curve= 0 ,0
Exp/Cntr=0.3,0.1

Type RM Length L Ch R = 1 ,10700   ,566,566,566
BEGIN DESCRIPTION:
Stream0737 20.0
END DESCRIPTION:
XS GIS Cut Line= 3
      2461524.96     13693925.01      2460709.03     13694129.64
      2459524.98     13694725.01
#Sta/Elev= 30
  4175.4  282.98    4330  276.45  4371.2  275.77  4425.9  273.66  4563.9  269.88
  4663.6  268.21  4733.8   266.6  4816.1  262.88  4876.4  262.43  4975.7  263.79
  4989.8   260.9  4995.8   260.6  4996.3   260.1  5003.9   260.1  5004.4   260.6
  5022.1  263.48  5068.3  262.82  5111.3  262.66  5150.4  265.69    5327  267.92
  5415.9  267.96  5416.3  267.97  5468.8  267.19  5527.7  268.43  5623.7  269.24
  5639.4  269.42  5831.2   271.9  6038.6  276.12  6283.3   283.6  6341.9  284.71
#Mann= 14 ,-1 , 0
  4175.4     .05       0  4425.9     .07       0  4663.6      .1       0
  4995.8     .05       0  5004.4      .1       0  5068.3     .05       0
    5327    .035       0  5415.9     .07       0  5416.3     .05       0
  5527.7     .07       0  5623.7    .035       0  5639.4     .05       0
  5831.2    .035       0  6038.6     .05       0
Bank Sta=4995.8,5004.4
XS Rating Curve= 0 ,0
Exp/Cntr=0.3,0.1

Type RM Length L Ch R = 1 ,10134   ,443,443,443
BEGIN DESCRIPTION:
Stream0737 19.0
END DESCRIPTION:
XS GIS Cut Line= 3
      2461475.03     13693324.99        2460675.       13693675.
        2459475.       13694675.
#Sta/Elev= 30
  4121.7  283.83  4433.2   272.8  4617.4  269.09  4722.1  265.42  4762.9  265.61
  4933.7  264.43  4980.5  260.89  5002.1  261.59  5018.6  258.56  5019.1  258.06
  5027.3  258.56  5030.7  260.71  5037.3  261.13  5092.6  262.63  5269.9  261.62
  5300.2  263.44  5314.5   266.7  5335.3   267.5  5349.7  267.07  5371.8  263.58
  5401.1  263.55  5463.6  263.55  5499.4  268.85  5567.4  267.26  5660.6  267.78
  5666.4   267.8  6264.2  276.22  6319.8  277.83  6422.3  281.29    6557  285.39
#Mann= 14 ,-1 , 0
  4121.7     .05       0  4617.4     .07       0  4762.9      .1       0
  5018.6     .05       0  5027.3      .1       0  5269.9     .07       0
  5371.8     .05       0  5401.1     .07       0  5567.4     .05       0
  5660.6     .07       0  5666.4     .05       0  6264.2    .035       0
  6319.8     .05       0  6422.3    .035       0
Bank Sta=5018.6,5027.3
XS Rating Curve= 0 ,0
Exp/Cntr=0.3,0.1

Type RM Length L Ch R = 1 ,9691    ,453,453,453
BEGIN DESCRIPTION:
Stream0737 18.0
END DESCRIPTION:
XS GIS Cut Line= 3
      2461175.01     13692574.99        2460375.       13693375.
      2459624.97     13694125.03
#Sta/Elev= 30
  3868.6  290.85  3983.6  284.22  4080.8   280.4  4151.5   276.9  4319.6  271.65
  4525.2  264.27  4557.5   263.5  4646.4  261.85  4731.3  261.87  4745.4  260.79
  4773.7  261.44  4886.9  260.36  4943.4  260.88  4957.6  259.33  4985.8  261.03
  4996.5  259.92  5003.5  259.92  5009.7  256.69  5010.2  256.19    5018  256.19
  5018.5  256.69  5036.6  259.93  5042.4  260.97  5056.6  260.87  5070.7  261.83
  5155.6  264.08  5424.3  268.69  5636.4  269.12  5749.5  267.74  6060.7  272.35
#Mann= 8 ,-1 , 0
  3868.6     .05       0  3983.6    .035       0  4319.6     .07       0
  4525.2     .12       0  4557.5      .1       0  5009.7     .05       0
  5018.5      .1       0  5036.6     .05       0
Bank Sta=5009.7,5018.5
XS Rating Curve= 0 ,0
Exp/Cntr=0.3,0.1

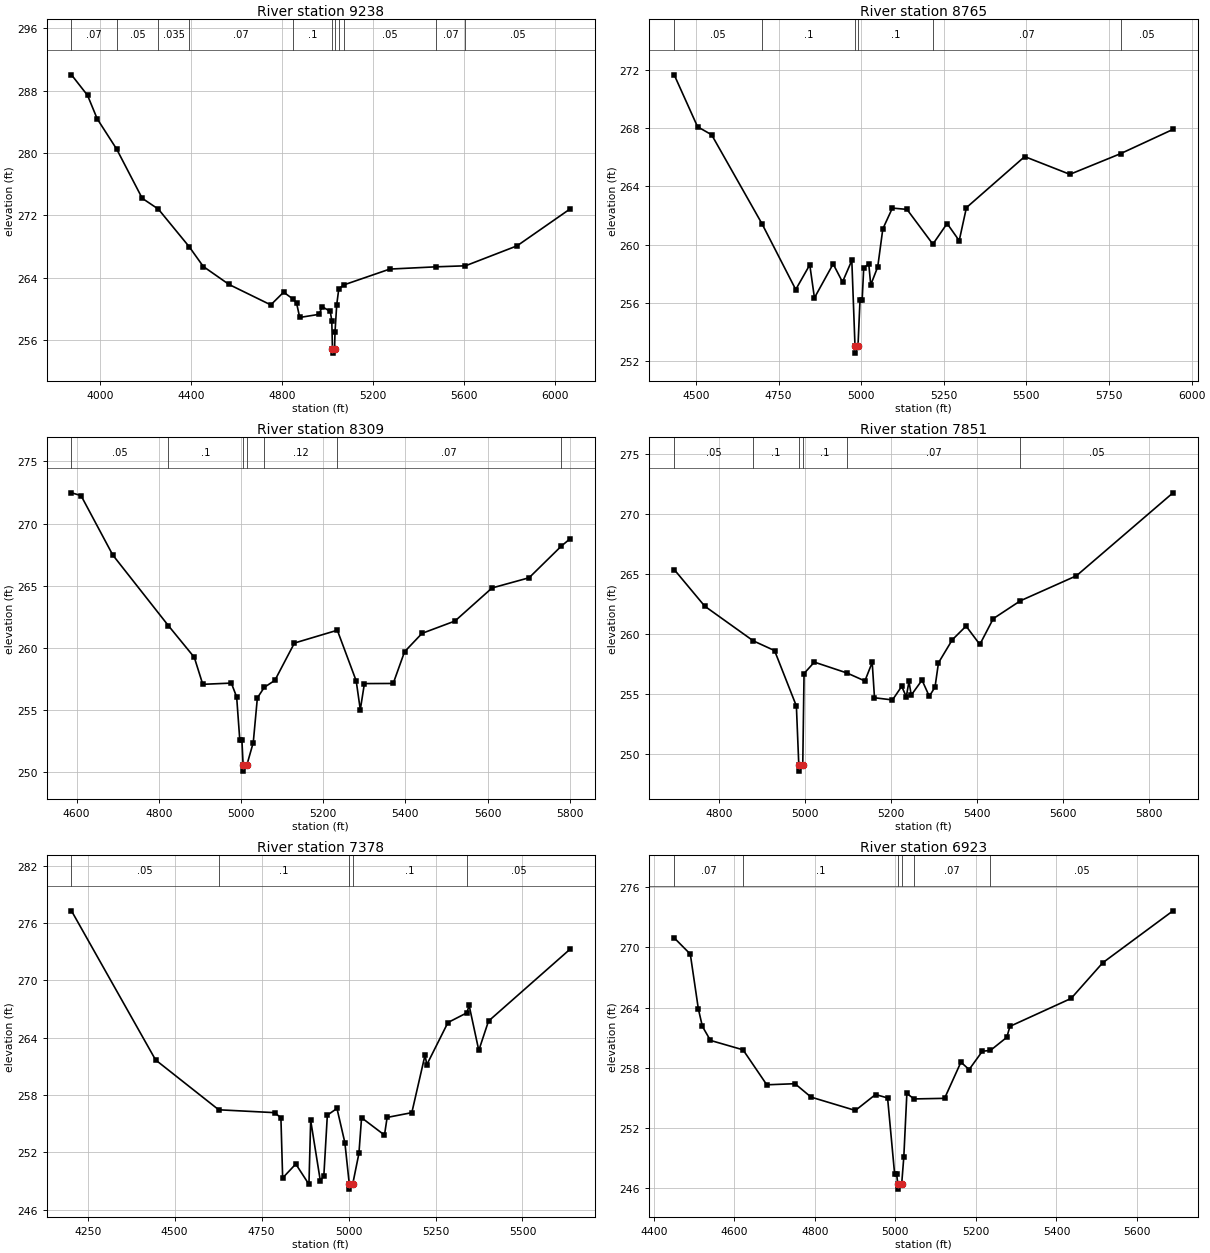
Type RM Length L Ch R = 1 ,9238    ,473,473,473
BEGIN DESCRIPTION:
Stream0737 17.0
END DESCRIPTION:
XS GIS Cut Line= 3
      2460925.03     13692274.97        2460125.       13693075.
      2459325.02     13693774.99
#Sta/Elev= 30
  3872.8  290.01  3943.5  287.38    3986  284.37  4071.6  280.49    4184  274.19
  4255.1   272.8  4390.5  267.99  4452.7  265.45  4565.8  263.15  4749.6  260.53
  4806.2  262.16  4845.9  261.31  4862.8   260.8  4876.9  258.92  4961.8  259.32
  4975.9  260.29  5011.3   259.7    5018  258.51    5021  254.85  5021.5  254.35
  5030.1  254.85  5032.2  257.05  5039.8  260.58  5048.9   262.6  5071.9   263.1
  5273.3  265.12  5477.6  265.41  5606.2  265.54  5833.3   268.1  6067.2  272.84
#Mann= 11 ,-1 , 0
  3872.8     .07       0  4071.6     .05       0  4255.1    .035       0
  4390.5     .07       0  4845.9      .1       0    5021     .05       0
  5030.1      .1       0  5048.9     .07       0  5071.9     .05       0
  5477.6     .07       0  5606.2     .05       0
Bank Sta=5021,5030.1
XS Rating Curve= 0 ,0
Exp/Cntr=0.3,0.1

Type RM Length L Ch R = 1 ,8765    ,456,456,456
BEGIN DESCRIPTION:
Stream0737 16.0
END DESCRIPTION:
XS GIS Cut Line= 3
      2460425.02     13692274.98        2460025.       13692675.
      2459225.01     13693174.99
#Sta/Elev= 30
  4434.4  271.67  4505.1   268.1  4547.6  267.55  4700.3  261.42  4802.1  256.91
  4844.6  258.61  4858.7  256.34  4915.3  258.67  4943.6  257.43  4971.8  258.91
  4981.4  253.04  4981.9  252.54  4990.5  253.04  4996.6   256.2  5003.1   256.2
  5007.8   258.4  5023.1  258.67    5029  257.23  5050.2  258.47  5065.6  261.08
  5094.5  262.51  5138.7  262.42    5217  260.03  5260.1  261.45  5296.7  260.27
  5318.5  262.54  5494.8  266.05  5631.6  264.83  5784.8  266.25  5943.5  267.92
#Mann= 6 ,-1 , 0
  4434.4     .05       0  4700.3      .1       0  4981.4     .05       0
  4990.5      .1       0    5217     .07       0  5784.8     .05       0
Bank Sta=4981.4,4990.5
XS Rating Curve= 0 ,0
Exp/Cntr=0.3,0.1

Type RM Length L Ch R = 1 ,8309    ,458,458,458
BEGIN DESCRIPTION:
Stream0737 15.0
END DESCRIPTION:
XS GIS Cut Line= 3
        2460375.       13692175.        2459975.       13692275.
      2459174.97       13692325.
#Sta/Elev= 30
  4587.4  272.48  4610.6  272.26  4687.9  267.48  4823.2   261.8  4886.3  259.25
  4906.9  257.08  4976.5  257.18  4989.4  256.06  4997.1  252.57  5002.2  252.57
  5005.1   250.6  5005.6   250.1  5014.3   250.6  5029.8   252.4  5039.8  255.99
  5056.7  256.84  5082.4   257.4    5130   260.4  5234.4  261.43  5280.3  257.36
  5290.3  255.04  5300.3  257.14  5370.4  257.15    5398   259.7  5440.6  261.18
  5520.7  262.17  5610.9  264.83  5701.1  265.65  5779.4  268.19  5801.3   268.8
#Mann= 7 ,-1 , 0
  4587.4     .05       0  4823.2      .1       0  5005.1     .05       0
  5014.3      .1       0  5056.7     .12       0  5234.4     .07       0
  5779.4     .05       0
Bank Sta=5005.1,5014.3
XS Rating Curve= 0 ,0
Exp/Cntr=0.3,0.1

Type RM Length L Ch R = 1 ,7851    ,473,473,473
BEGIN DESCRIPTION:
Stream0737 14.0
END DESCRIPTION:
XS GIS Cut Line= 3
      2460174.97     13691924.99        2459875.       13691875.
        2459075.       13692175.
#Sta/Elev= 30
  4696.3  265.37  4767.2  262.32    4880  259.43  4929.4  258.62  4980.1     254
  4985.7  249.08  4986.2  248.58  4994.9  249.08  4997.9  256.71  5021.8  257.66
  5097.9  256.75  5139.2  256.09  5156.2  257.64  5161.5  254.69  5203.3  254.51
  5224.7  255.64  5235.4  254.77  5241.6  256.05  5246.9  254.91  5271.9  256.16
  5288.8  254.81  5302.1  255.58  5310.1   257.6  5342.2  259.52  5374.2  260.66
  5406.2  259.13  5437.4  261.28  5500.5  262.77  5630.5  264.85  5854.8  271.76
#Mann= 6 ,-1 , 0
  4696.3     .05       0    4880      .1       0  4985.7     .05       0
  4994.9      .1       0  5097.9     .07       0  5500.5     .05       0
Bank Sta=4985.7,4994.9
XS Rating Curve= 0 ,0
Exp/Cntr=0.3,0.1

Type RM Length L Ch R = 1 ,7378    ,455,455,455
BEGIN DESCRIPTION:
Stream0737 13.0
END DESCRIPTION:
XS GIS Cut Line= 4
      2460375.01       13691525.        2459575.       13691625.
        2459275.       13691575.      2458955.58     13691521.76
#Sta/Elev= 30
  4203.3  277.29  4445.2  261.67  4626.7  256.45  4787.8  256.15  4805.5   255.6
  4810.5  249.31  4848.3  250.77  4886.1  248.64  4891.1  255.34  4918.8  249.02
  4928.9  249.52    4939  255.89  4966.7  256.59  4989.4  253.01  5002.2  248.64
  5002.7  248.14  5011.8  248.64  5029.8  251.88  5037.4  255.62  5103.3   253.8
  5110.9  255.65  5181.9  256.15  5219.9  262.18    5225  261.17  5285.8  265.59
  5340.4  266.61  5346.6   267.4  5374.5  262.67  5402.4  265.74  5637.5  273.29
#Mann= 5 ,-1 , 0
  4203.3     .05       0  4626.7      .1       0  5002.2     .05       0
  5011.8      .1       0  5340.4     .05       0
Bank Sta=5002.2,5011.8
XS Rating Curve= 0 ,0
Exp/Cntr=0.3,0.1

Type RM Length L Ch R = 1 ,6923    ,474,474,474
BEGIN DESCRIPTION:
Stream0737 12.0
END DESCRIPTION:
XS GIS Cut Line= 4
      2460174.98       13691225.        2459625.       13691225.
        2459325.       13691275.      2458945.45     13691338.26
#Sta/Elev= 30
  4450.5  270.95  4490.5  269.33  4510.5  263.86  4520.5  262.12  4540.5  260.72
  4621.5  259.78  4680.5  256.29  4750.5   256.4  4790.5  255.06  4900.5  253.73
  4950.5  255.32  4980.5  254.98    4998  247.39    5003  247.39  5005.8  246.38
  5006.3  245.88  5015.5  246.38  5020.8  249.08  5028.4  255.43  5046.2  254.88
  5122.1  254.94  5162.7  258.55    5183  257.81  5215.9  259.64  5235.9  259.72
  5276.7  261.03  5284.3  262.12  5436.4  264.91    5515  268.47  5689.4  273.65
#Mann= 6 ,-1 , 0
  4450.5     .07       0  4621.5      .1       0  5005.8     .05       0
  5015.5      .1       0  5046.2     .07       0  5235.9     .05       0
Bank Sta=5005.8,5015.5
XS Rating Curve= 0 ,0
Exp/Cntr=0.3,0.1

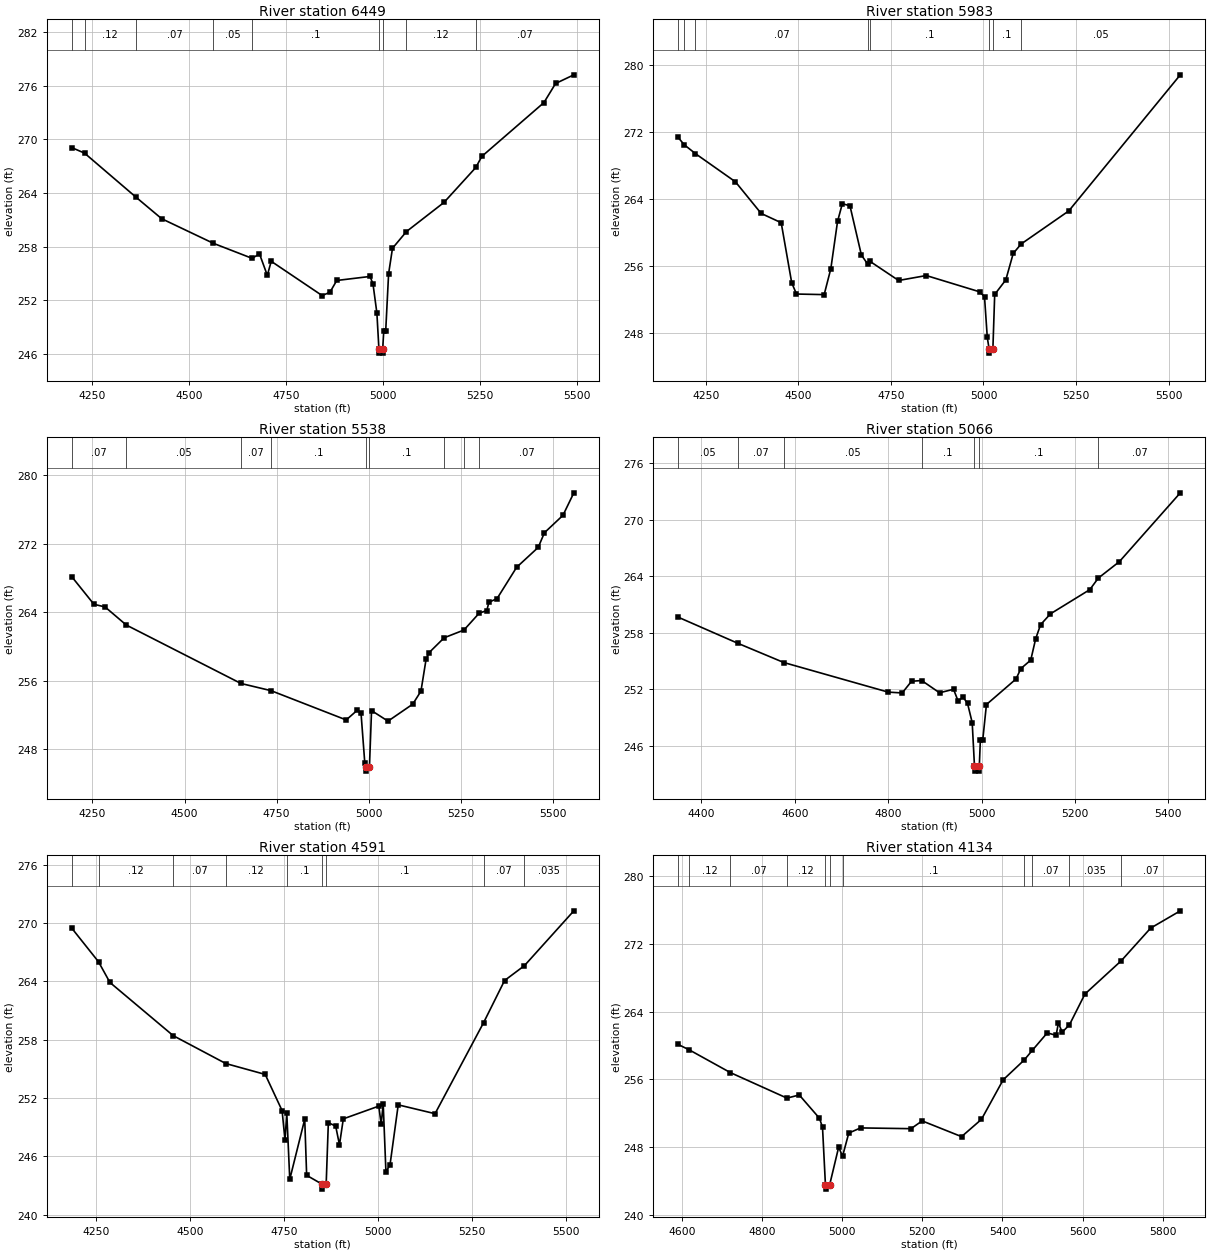
Type RM Length L Ch R = 1 ,6449    ,466,466,466
BEGIN DESCRIPTION:
Stream0737 11.0
END DESCRIPTION:
XS GIS Cut Line= 4
      2460224.97       13690725.        2459425.       13690825.
        2459275.       13690825.        2458938.       13690825.
#Sta/Elev= 30
  4197.8  269.09  4230.9  268.47  4363.8  263.52  4429.6  261.12  4562.9  258.36
  4662.5  256.68  4681.5  257.18  4701.7  254.77  4711.7  256.35  4842.8  252.51
  4862.9  252.88  4880.5   254.2  4966.2  254.65  4973.8  253.81  4983.8  250.56
    4989  246.56  4989.5  246.06  4998.3  246.06  4998.8  246.56  5001.5  248.52
  5006.5  248.52    5014  254.96    5024  257.81    5060  259.68  5156.5  262.94
  5238.6  266.86    5254   268.1    5414  274.13    5444  276.27    5491  277.24
#Mann= 9 ,-1 , 0
  4197.8     .07       0  4230.9     .12       0  4363.8     .07       0
  4562.9     .05       0  4662.5      .1       0    4989     .05       0
  4998.8      .1       0    5060     .12       0  5238.6     .07       0
Bank Sta=4989,4998.8
XS Rating Curve= 0 ,0
Exp/Cntr=0.3,0.1

Type RM Length L Ch R = 1 ,5983    ,445,445,445
BEGIN DESCRIPTION:
Stream0737 10.0
END DESCRIPTION:
XS GIS Cut Line= 4
      2460275.04     13690575.01        2459475.       13690375.
        2459275.       13690375.      2458943.86       13690375.
#Sta/Elev= 30
  4175.7  271.32  4191.8  270.45  4222.6  269.37  4330.4  266.01  4399.9  262.23
    4454  261.12  4482.4  253.94  4495.3   252.6    4570  252.53    4588  255.63
  4606.1  261.27    4619  263.39  4639.6  263.15  4670.5  257.26  4687.1   256.2
  4694.2  256.49    4771  254.22  4845.7  254.81  4990.1  252.86  5002.9  252.27
  5010.4  247.41  5015.3  246.04  5015.8  245.54  5025.5  246.04  5030.4  252.55
  5060.4  254.29  5080.4  257.45  5101.8  258.58  5230.4  262.53  5531.5  278.79
#Mann= 8 ,-1 , 0
  4175.7     .07       0  4191.8     .12       0  4222.6     .07       0
  4687.1     .05       0  4694.2      .1       0  5015.3     .05       0
  5025.5      .1       0  5101.8     .05       0
Bank Sta=5015.3,5025.5
XS Rating Curve= 0 ,0
Exp/Cntr=0.3,0.1

Type RM Length L Ch R = 1 ,5538    ,472,472,472
BEGIN DESCRIPTION:
Stream0737 9.0
END DESCRIPTION:
XS GIS Cut Line= 4
      2460225.01       13690075.        2459425.       13689975.
        2459225.       13690075.      2458926.03     13690224.49
#Sta/Elev= 30
  4193.4  268.15  4253.9  264.91  4284.1   264.6  4341.7  262.49  4653.3  255.66
    4735  254.82  4939.2   251.4  4969.4  252.54  4979.5  252.16  4989.6   246.4
    4992  245.92  4992.5  245.42  5002.3  245.92    5008  252.49  5052.7  251.26
  5119.8  253.24  5142.2  254.76  5156.2   258.5  5164.5  259.27  5205.3     261
  5258.9   261.9  5300.6  263.88  5321.1  264.18  5326.7  265.14    5349  265.58
  5402.1  269.23  5460.8  271.56  5477.6  273.27  5527.9   275.3  5557.5  277.93
#Mann= 9 ,-1 , 0
  4193.4     .07       0  4341.7     .05       0  4653.3     .07       0
    4735      .1       0    4992     .05       0  5002.3      .1       0
  5205.3     .05       0  5258.9     .12       0  5300.6     .07       0
Bank Sta=4992,5002.3
XS Rating Curve= 0 ,0
Exp/Cntr=0.3,0.1

Type RM Length L Ch R = 1 ,5066    ,475,475,475
BEGIN DESCRIPTION:
Stream0737 8.0
END DESCRIPTION:
XS GIS Cut Line= 4
      2459925.01       13689625.        2459275.       13689625.
        2459125.       13689675.      2458871.06     13689759.65
#Sta/Elev= 30
    4350  259.67  4478.1  256.89  4576.5  254.85    4800  251.71    4830  251.62
    4850  252.86  4871.8  252.94    4910  251.64    4940  252.01    4950  250.74
    4960   251.2    4970  250.51    4980  248.47  4984.9  243.82  4985.4  243.32
  4994.7  243.32  4995.2  243.82  4997.5  246.64  5002.6  246.64  5010.5  250.39
  5073.8   253.1  5084.3  254.21  5105.4  255.11    5116  257.38  5126.5  258.87
  5147.6  260.02  5231.9  262.59  5250.2  263.82  5295.2  265.56  5425.8  272.87
#Mann= 7 ,-1 , 0
    4350     .05       0  4478.1     .07       0  4576.5     .05       0
  4871.8      .1       0  4984.9     .05       0  4995.2      .1       0
  5250.2     .07       0
Bank Sta=4984.9,4995.2
XS Rating Curve= 0 ,0
Exp/Cntr=0.3,0.1

Type RM Length L Ch R = 1 ,4591    ,457,457,457
BEGIN DESCRIPTION:
Stream0737 7.0
END DESCRIPTION:
XS GIS Cut Line= 4
      2460175.04     13689074.99        2459375.       13689225.
        2459025.       13689375.      2458895.74      13689430.4
#Sta/Elev= 30
  4185.9  269.49  4257.3  266.02  4287.7  263.89  4455.9  258.42  4595.8  255.55
  4700.6  254.43  4745.5  250.71  4753.2  247.69    4758  250.43  4765.9  243.64
  4805.7  249.82  4810.8  244.05  4852.2  243.13  4852.7  242.63  4862.7  243.13
  4868.5  249.47    4888  249.11  4898.1  247.19  4908.3  249.86  5002.6  251.17
  5008.9  249.33  5014.4  251.38  5021.6   244.4  5032.5  245.13  5054.3   251.3
  5152.2  250.39  5281.5  259.77  5337.1  264.09  5389.9  265.62  5521.3  271.26
#Mann= 9 ,-1 , 0
  4185.9     .07       0  4257.3     .12       0  4455.9     .07       0
  4595.8     .12       0    4758      .1       0  4852.2     .05       0
  4862.7      .1       0  5281.5     .07       0  5389.9    .035       0
Bank Sta=4852.2,4862.7
XS Rating Curve= 0 ,0
Exp/Cntr=0.3,0.1

Type RM Length L Ch R = 1 ,4134    ,465,465,465
BEGIN DESCRIPTION:
Stream0737 6.0
END DESCRIPTION:
XS GIS Cut Line= 3
      2459924.98       13688975.        2459525.       13689025.
      2458774.99       13689425.
#Sta/Elev= 30
  4590.6  260.12  4618.7  259.47  4721.1  256.79  4862.2  253.78  4892.9  254.15
  4943.3   251.4  4950.9  250.34  4958.2  243.53  4958.7  243.03  4968.7  243.53
  4991.2  247.99  5000.9  246.91  5016.4  249.65  5045.8  250.26  5171.8  250.17
  5199.5  251.09  5297.9  249.23  5347.5  251.27  5401.7  255.94    5454  258.27
  5474.4  259.42  5511.8  261.49  5533.8  261.19  5539.5  262.66    5549  261.56
  5567.2  262.45  5605.7  266.07  5696.5  270.01  5769.7  273.86  5843.7   275.9
#Mann= 11 ,-1 , 0
  4590.6     .07       0  4618.7     .12       0  4721.1     .07       0
  4862.2     .12       0  4958.2     .05       0  4968.7     .12       0
  5000.9      .1       0    5454    .035       0  5474.4     .07       0
  5567.2    .035       0  5696.5     .07       0
Bank Sta=4958.2,4968.7
XS Rating Curve= 0 ,0
Exp/Cntr=0.3,0.1

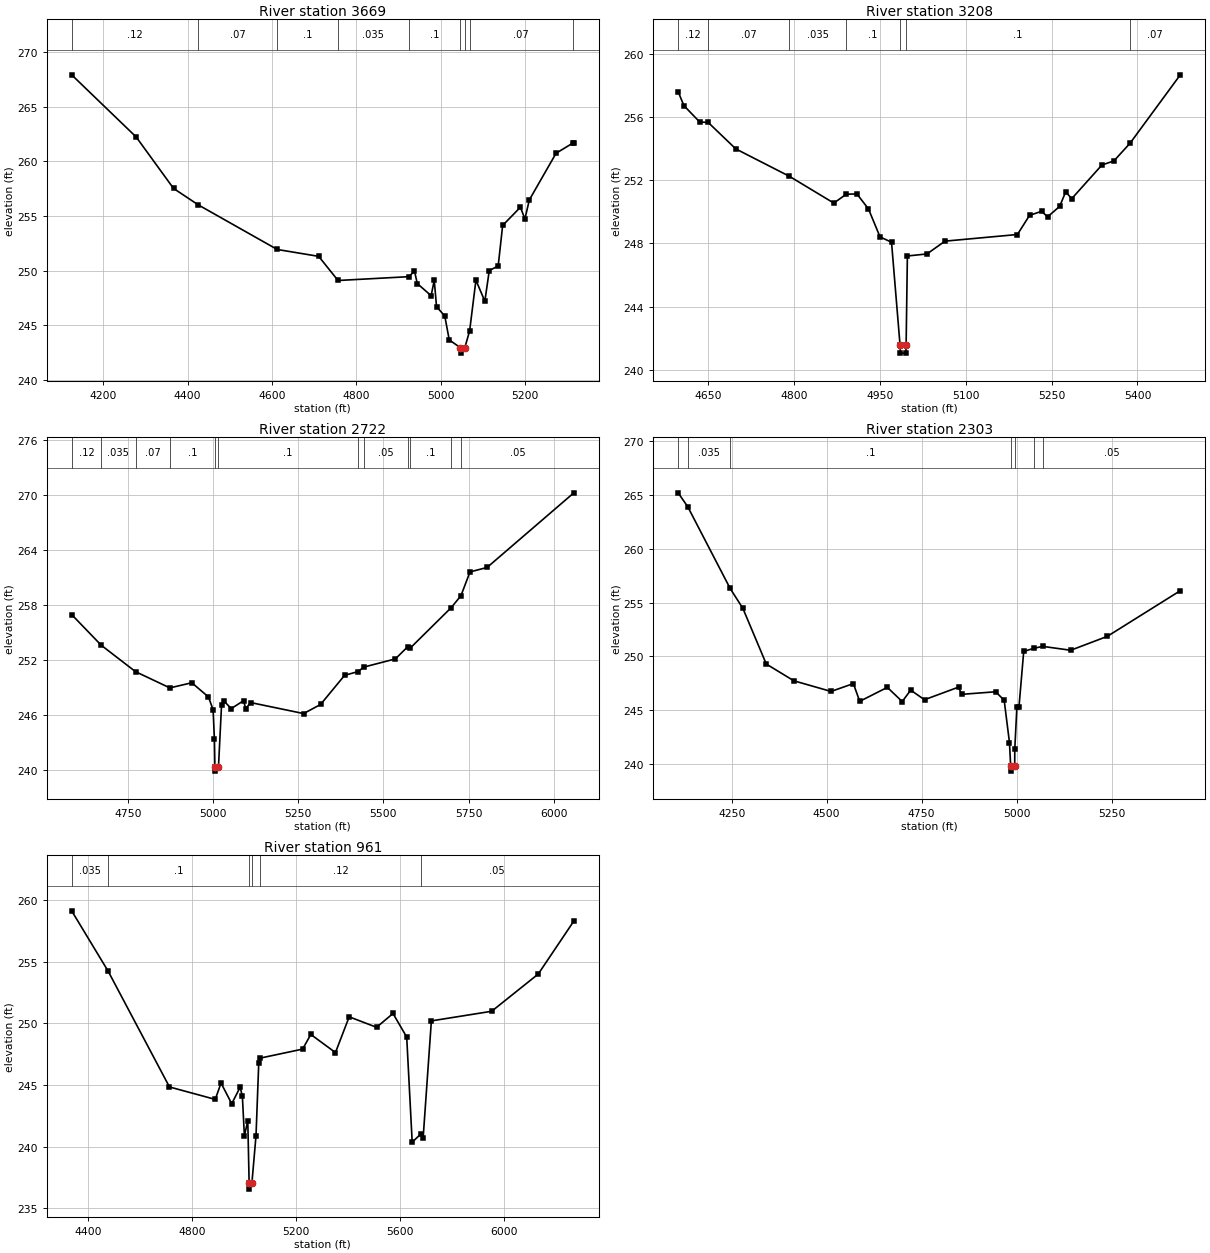
Type RM Length L Ch R = 1 ,3669    ,461,461,461
BEGIN DESCRIPTION:
Stream0737 5.0
END DESCRIPTION:
XS GIS Cut Line= 3
      2459974.98     13688475.01        2459175.       13688825.
      2458875.02     13688924.99
#Sta/Elev= 30
  4125.4  267.92  4278.2  262.23  4366.7  257.52    4425  256.02  4612.3  251.93
  4710.5   251.3  4756.3  249.09  4923.9  249.44  4937.4  249.95    4944  248.81
  4976.8   247.7  4984.2  249.11  4989.6  246.69  5009.1  245.84  5019.7  243.65
    5046  242.94  5046.5  242.44  5056.6  242.94    5068  244.48  5082.9  249.12
    5104  247.19  5114.5     250  5135.6  250.42  5146.2  254.13  5188.3   255.8
  5198.9  254.72  5209.4  256.47  5272.7  260.74    5312  261.66  5314.8  261.65
#Mann= 9 ,-1 , 0
  4125.4     .12       0    4425     .07       0  4612.3      .1       0
  4756.3    .035       0  4923.9      .1       0    5046     .05       0
  5056.6      .1       0    5068     .07       0    5312     .05       0
Bank Sta=5046,5056.6
XS Rating Curve= 0 ,0
Exp/Cntr=0.3,0.1

Type RM Length L Ch R = 1 ,3208    ,486,486,486
BEGIN DESCRIPTION:
Stream0737 4.0
END DESCRIPTION:
XS GIS Cut Line= 3
      2459725.04       13688525.        2459325.       13688575.
      2458874.99       13688725.
#Sta/Elev= 30
  4597.3  257.61  4607.4  256.72  4635.1  255.68  4649.7  255.66  4698.1  253.98
  4791.5  252.25  4869.4  250.55    4891  251.11  4909.7  251.13  4929.9  250.18
  4950.1  248.41  4970.2  248.07  4985.1  241.55  4985.6  241.05  4995.2  241.05
  4995.7  241.55  4997.9   247.2  5032.1  247.33  5063.7  248.14  5190.2  248.56
  5211.3  249.77  5232.4  250.03  5242.9  249.68    5264  250.34  5274.5  251.26
  5285.1  250.83  5337.8  252.96  5358.8  253.22    5387  254.34  5474.8  258.67
#Mann= 7 ,-1 , 0
  4597.3     .12       0  4649.7     .07       0  4791.5    .035       0
    4891      .1       0  4985.1     .05       0  4995.7      .1       0
    5387     .07       0
Bank Sta=4985.1,4995.7
XS Rating Curve= 0 ,0
Exp/Cntr=0.3,0.1

Type RM Length L Ch R = 1 ,2722    ,419,419,419
BEGIN DESCRIPTION:
Stream0737 3.0
END DESCRIPTION:
XS GIS Cut Line= 3
        2459725.       13688225.        2459325.       13688125.
      2458625.02     13688924.98
#Sta/Elev= 30
  4584.1  256.95  4671.1   253.6  4771.8  250.72  4872.6  248.95  4937.1  249.51
  4986.1  247.96  4999.7  246.55  5003.5  243.35  5004.9  240.37  5005.4  239.87
  5015.5  240.37  5024.4  247.04    5032   247.5  5052.9  246.69    5089  247.55
  5095.6  246.69  5109.8  247.35  5265.5  246.15  5315.3  247.14    5386  250.32
  5424.5  250.72  5443.4  251.23    5535  252.11  5571.1  253.43    5579   253.3
  5698.7  257.69  5727.7     259  5754.3   261.6  5804.6  262.09  6059.4  270.23
#Mann= 12 ,-1 , 0
  4584.1     .12       0  4671.1    .035       0  4771.8     .07       0
  4872.6      .1       0  5004.9     .05       0  5015.5      .1       0
  5424.5     .07       0  5443.4     .05       0  5571.1     .07       0
    5579      .1       0  5698.7     .07       0  5727.7     .05       0
Bank Sta=5004.9,5015.5
XS Rating Curve= 0 ,0
Exp/Cntr=0.3,0.1

Type RM Length L Ch R = 1 ,2303    ,1342,1342,1342
BEGIN DESCRIPTION:
Stream0737 2.0
END DESCRIPTION:
XS GIS Cut Line= 3
      2459774.97     13687725.01        2458975.       13688125.
        2458825.       13688525.
#Sta/Elev= 30
  4109.1  265.21  4134.4  263.92    4246  256.32  4279.6  254.46  4341.1  249.29
  4413.7  247.73  4511.6  246.74  4570.3  247.47    4587  245.82  4659.7  247.12
  4698.8   245.8  4721.2  246.86  4757.5  245.97    4847  247.14  4855.4  246.47
  4944.8  246.71  4967.2  245.92  4981.1  241.99  4984.2  239.83  4984.7  239.33
  4994.9  239.83  4995.1  241.38  5000.7  245.33  5006.2  245.33  5018.6  250.46
  5045.1  250.75  5068.6  250.93  5142.3  250.57  5238.5  251.86  5430.7  256.11
#Mann= 7 ,-1 , 0
  4109.1     .07       0  4134.4    .035       0    4246      .1       0
  4984.2     .05       0  4994.9      .1       0  5045.1     .07       0
  5068.6     .05       0
Bank Sta=4984.2,4994.9
XS Rating Curve= 0 ,0
Exp/Cntr=0.3,0.1

Type RM Length L Ch R = 1 ,961     ,0,0,0
BEGIN DESCRIPTION:
Stream0737 1.0
END DESCRIPTION:
XS GIS Cut Line= 3
      2459775.01       13687475.        2459125.       13687325.
        2458725.     13688524.99
#Sta/Elev= 30
  4336.3  259.13  4476.5  254.24  4712.6  244.84  4888.8  243.83    4911  245.16
  4952.1  243.48  4984.6  244.82  4993.1  244.08  5000.8  240.88  5013.9  242.08
  5019.1  237.05  5019.6  236.55  5029.8  237.05  5045.6   240.9  5056.1  246.78
  5061.7  247.18  5224.8  247.91  5256.4   249.1  5351.2  247.63    5404  250.53
  5509.4  249.68  5572.6   250.8  5625.3  248.89  5646.4  240.36  5678.6     241
  5688.6  240.73  5720.2   250.2  5952.1  250.98  6131.3     254  6268.3   258.3
#Mann= 6 ,-1 , 0
  4336.3    .035       0  4476.5      .1       0  5019.1     .05       0
  5029.8      .1       0  5061.7     .12       0  5678.6     .05       0
Bank Sta=5019.1,5029.8
XS Rating Curve= 0 ,0
Exp/Cntr=0.3,0.1

Chan Stop Cuts=-1
Use User Specified Reach Order=0
Composite Channel Slope=5