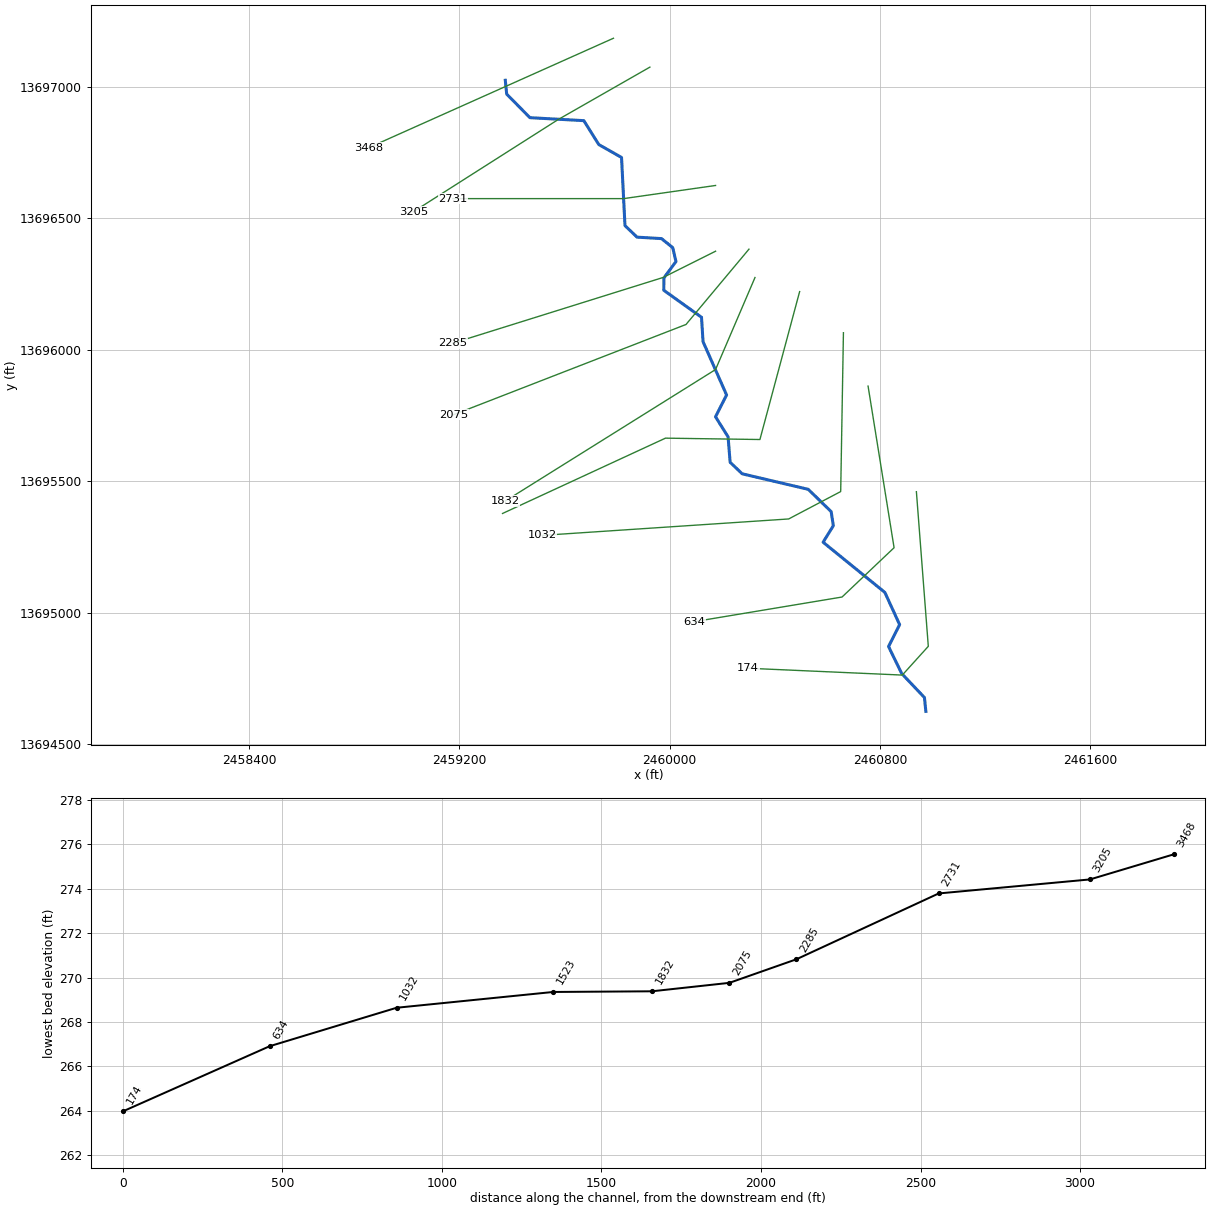
--- Stream0738.prj (project) ---

Proj Title=Stream0738 Base Level Engineering
Current Plan=p01
Default Exp/Contr=0.3,0.1
English Units
Geom File=g01
Flow File=f01
Plan File=p01
BEGIN DESCRIPTION:
Stream0738
END DESCRIPTION:

--- Stream0738.p01 (plan) ---

Plan Title=Multiple Run
Short Identifier=Multiple
Geom File=g01
Flow File=f01
Subcritical Flow
K Sum by GR= 0
Std Step Tol= 0.01
Critical Tol= 0.01
Num of Std Step Trials= 20
Max Error Tol= 0.3
Flow Tol Ratio= 0.001
Split Flow NTrial= 30
Split Flow Tol= 0.02
Split Flow Ratio= 0.02
Log Output Level= 0
Friction Slope Method= 1
Unsteady Friction Slope Method= 2
Unsteady Bridges Friction Slope Method= 1
Parabolic Critical Depth
Global Vel Dist=  1 , 1 , 1
Global Log Level= 0
CheckData=True
Encroach Param= -1, 0, 0, 0
BEGIN DESCRIPTION:
Multiple Run
END DESCRIPTION:

--- Stream0738.f01 (steady flow) ---

Flow Title=Multiple
Number of Profiles=7
Profile Names=10-year,25-year,50-year,1pct_min,100-year,1pct_plu,500-year
River Rch & RM= Stream0738,Reach-1,3468
     658    1052    1403     906    1808    3608    2974
Boundary for River Rch & Prof#=Stream0738,Reach-1,1
Up Type=0
Dn Type=3
Dn Slope=0.005
Boundary for River Rch & Prof#=Stream0738,Reach-1,2
Up Type=0
Dn Type=3
Dn Slope=0.005
Boundary for River Rch & Prof#=Stream0738,Reach-1,3
Up Type=0
Dn Type=3
Dn Slope=0.005
Boundary for River Rch & Prof#=Stream0738,Reach-1,4
Up Type=0
Dn Type=3
Dn Slope=0.005
Boundary for River Rch & Prof#=Stream0738,Reach-1,5
Up Type=0
Dn Type=3
Dn Slope=0.005
Boundary for River Rch & Prof#=Stream0738,Reach-1,6
Up Type=0
Dn Type=3
Dn Slope=0.005
Boundary for River Rch & Prof#=Stream0738,Reach-1,7
Up Type=0
Dn Type=3
Dn Slope=0.005

--- Stream0738.g01 (geometry) ---

Geom Title=Existing Conditions

River Reach=Stream0738,Reach-1
Reach XY= 30
      2459375.00     13697025.00      2459380.30     13696972.46
      2459468.79     13696882.79      2459673.74     13696871.52
      2459730.67     13696780.67      2459817.26     13696731.46
      2459830.34     13696472.26      2459876.25     13696428.51
      2459969.33     13696422.92      2460012.05     13696388.63
      2460024.28     13696335.75      2459978.36     13696273.24
      2459978.04     13696226.42      2460121.48     13696123.72
      2460127.36     13696030.98      2460216.90     13695828.29
      2460174.79     13695745.21      2460222.62     13695669.03
      2460230.40     13695572.29      2460276.25     13695528.51
      2460527.44     13695469.48      2460614.80     13695384.70
      2460623.01     13695331.05      2460584.14     13695268.25
      2460819.18     13695077.31      2460875.22     13694954.80
      2460833.07     13694871.69      2460883.12     13694768.95
      2460969.67     13694677.51      2460975.00     13694625.00

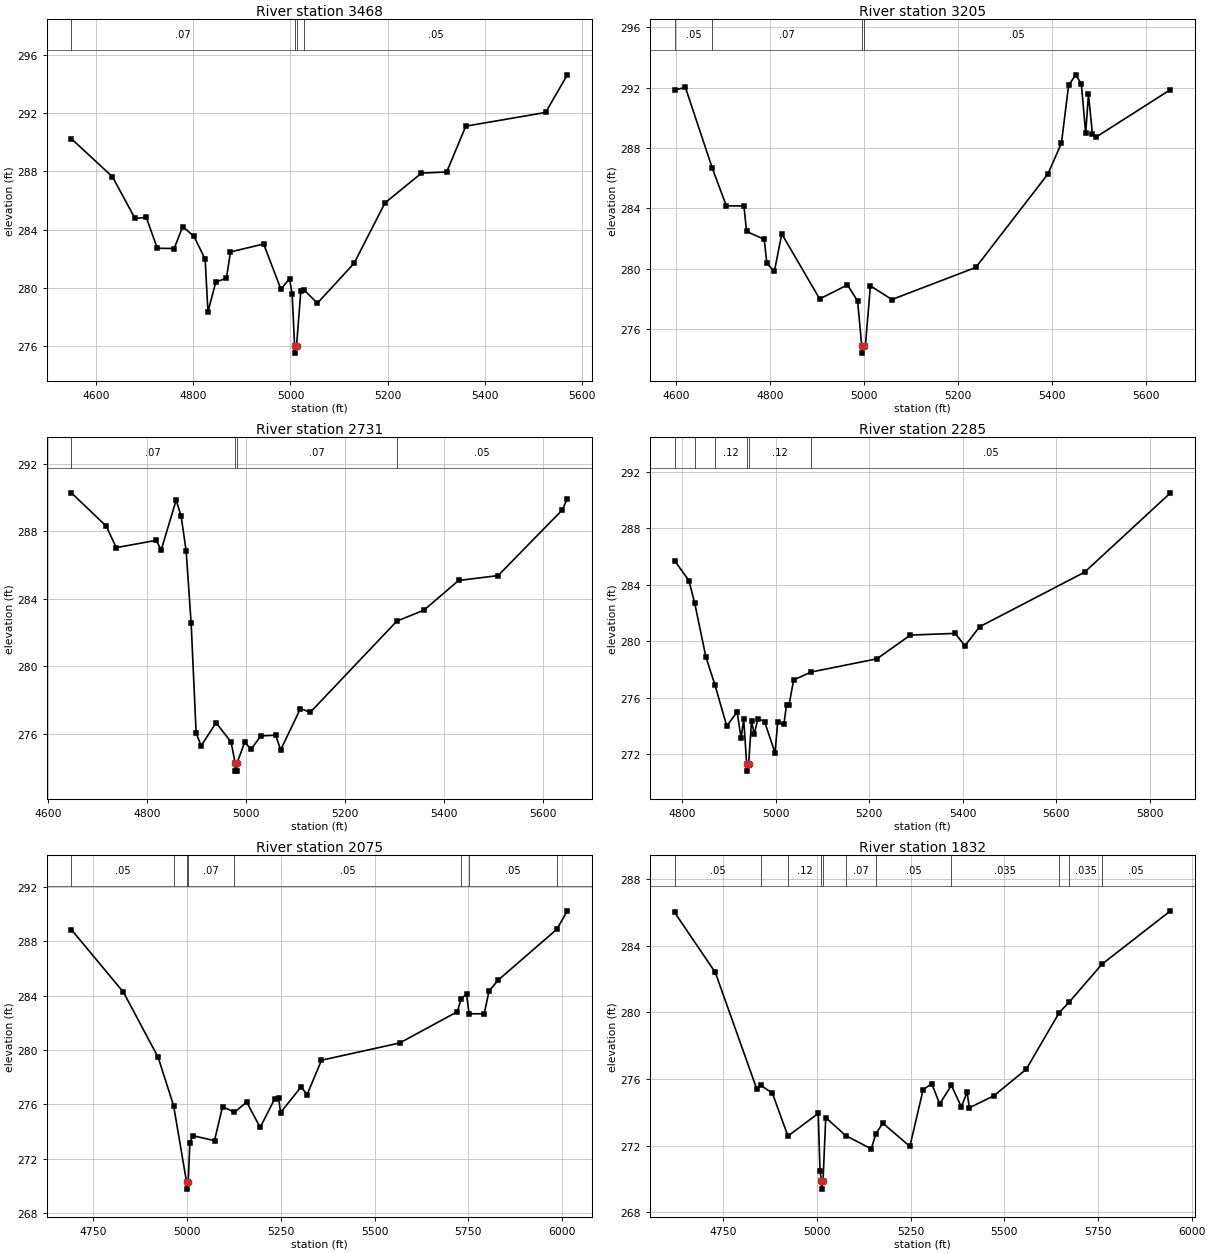
Type RM Length L Ch R = 1,3468,263,263,263
BEGIN DESCRIPTION:
XS7619
END DESCRIPTION:
XS GIS Cut Line= 2
      2459786.50     13697184.92      2458854.18     13696768.24
#Sta/Elev= 30
  4548.8  290.24  4633.5  287.63  4679.9  284.77  4703.1  284.85  4725.7  282.73
  4760.5  282.71  4778.2  284.22  4801.4  283.54  4824.3  281.98  4830.1  278.38
  4846.2  280.41  4868.1  280.68  4876.5  282.48  4944.8  283.02  4980.3  279.92
  4998.0  280.64  5003.5  279.56  5008.5  276.04  5008.7  275.54  5012.5  276.04
  5021.2  279.77  5027.2  279.90  5055.4  278.96  5131.0  281.70  5194.6  285.84
  5269.7  287.88  5321.6  287.96  5361.0  291.10  5525.3  292.04  5570.0  294.62
#Mann=4,-1,0
  4548.8    0.07       0  5008.5    0.05       0  5012.5    0.07       0
  5027.2    0.05       0
Bank Sta=5008.5,5012.5
Exp/Cntr=0.3,0.1

Type RM Length L Ch R = 1,3205,474,474,474
BEGIN DESCRIPTION:
Stream0738 4.0
END DESCRIPTION:
XS GIS Cut Line= 3
      2459925.02     13697075.01      2459575.00     13696875.00
      2459024.96     13696524.97
#Sta/Elev= 30
  4596.9  291.84  4620.0  292.02  4677.3  286.66  4707.1  284.17  4744.5  284.16
  4750.2  282.47  4787.7  281.95  4793.4  280.36  4809.3  279.82  4825.1  282.31
  4905.7  278.00  4964.8  278.93  4986.4  277.86  4995.1  274.91  4995.4  274.41
  4999.2  274.91  5003.0  274.91  5013.6  278.87  5059.3  277.96  5237.9  280.09
  5391.2  286.28  5420.0  288.32  5435.2  292.15  5450.4  292.85  5462.3  292.25
  5471.6  288.98  5477.5  291.55  5486.0  288.90  5492.8  288.71  5652.0  291.87
#Mann=4,-1,0
  4596.9    0.05       0  4677.3    0.07       0  4995.1    0.05       0
  4999.2    0.05       0
Bank Sta=4995.1,4999.2
Exp/Cntr=0.3,0.1

Type RM Length L Ch R = 1,2731,446,446,446
BEGIN DESCRIPTION:
Stream0738 3.0
END DESCRIPTION:
XS GIS Cut Line= 3
      2460174.96     13696624.99      2459825.00     13696575.00
      2459175.02     13696575.00
#Sta/Elev= 30
  4646.4  290.29  4717.1  288.31  4737.3  287.04  4818.1  287.47  4828.2  286.90
  4858.5  289.86  4868.6  288.89  4878.7  286.84  4888.8  282.55  4898.9  276.03
  4909.0  275.28  4939.3  276.65  4969.6  275.50  4977.7  274.28  4977.9  273.78
  4981.5  273.78  4981.8  274.28  4997.4  275.51  5009.9  275.07  5029.9  275.87
  5059.9  275.91  5069.9  275.04  5109.9  277.49  5129.9  277.27  5305.0  282.68
  5359.9  283.33  5429.9  285.09  5509.9  285.38  5639.9  289.28  5649.9  289.95
#Mann=4,-1,0
  4646.4    0.07       0  4977.7    0.05       0  4981.8    0.07       0
  5305.0    0.05       0
Bank Sta=4977.7,4981.8
Exp/Cntr=0.3,0.1

Type RM Length L Ch R = 1,2285,210,210,210
BEGIN DESCRIPTION:
Stream0738 2.0
END DESCRIPTION:
XS GIS Cut Line= 3
      2460174.98     13696374.99      2459975.00     13696275.00
      2459175.04     13696025.01
#Sta/Elev= 30
  4783.0  285.71  4813.7  284.30  4826.2  282.70  4850.1  278.90  4869.5  276.92
  4894.8  274.01  4917.1  275.01  4925.5  273.14  4931.1  274.50  4937.4  271.32
  4937.7  270.82  4941.6  271.32  4947.9  274.36  4953.5  273.45  4961.9  274.54
  4975.8  274.32  4998.2  272.11  5003.8  274.26  5017.1  274.13  5022.8  275.51
  5028.1  275.50  5038.0  277.27  5075.8  277.83  5216.1  278.76  5287.9  280.44
  5383.8  280.56  5404.7  279.68  5436.1  281.03  5660.9  284.89  5844.7  290.50
#Mann=6,-1,0
  4783.0    0.05       0  4826.2    0.07       0  4869.5    0.12       0
  4937.4    0.05       0  4941.6    0.12       0  5075.8    0.05       0
Bank Sta=4937.4,4941.6
Exp/Cntr=0.3,0.1

Type RM Length L Ch R = 1,2075,243,243,243
BEGIN DESCRIPTION:
XS7618
END DESCRIPTION:
XS GIS Cut Line= 3
      2460302.11     13696382.85      2460062.50     13696096.35
      2459178.56     13695753.18
#Sta/Elev= 30
  4692.0  288.87  4830.8  284.26  4923.2  279.47  4964.5  275.91  4999.2  270.26
  4999.5  269.76  5003.4  270.26  5007.8  273.13  5015.1  273.70  5073.5  273.33
  5095.0  275.84  5126.6  275.42  5159.3  276.17  5195.2  274.30  5234.4  276.43
  5244.3  276.44  5249.7  275.40  5304.1  277.28  5320.3  276.72  5358.6  279.25
  5567.0  280.52  5720.5  282.82  5731.1  283.79  5745.1  284.11  5752.0  282.67
  5792.3  282.67  5804.9  284.33  5829.4  285.15  5985.7  288.89  6013.7  290.25
#Mann=8,-1,0
  4692.0    0.05       0  4964.5    0.07       0  4999.2    0.05       0
  5003.4    0.07       0  5126.6    0.05       0  5731.1   0.035       0
  5752.0    0.05       0  5985.7   0.045       0
Bank Sta=4999.2,5003.4
Exp/Cntr=0.3,0.1

Type RM Length L Ch R = 1,1832,309,309,309
BEGIN DESCRIPTION:
Stream0738 1.0
END DESCRIPTION:
XS GIS Cut Line= 3
      2460325.00     13696275.01      2460175.00     13695925.00
      2459375.00     13695425.00
#Sta/Elev= 30
  4619.3  286.02  4728.1  282.41  4838.7  275.41  4849.7  275.61  4880.4  275.16
  4922.1  272.57  5003.0  273.93  5007.8  270.45  5011.6  269.88  5011.9  269.38
  5015.8  269.88  5023.1  273.68  5076.2  272.60  5144.6  271.80  5156.5  272.68
  5175.2  273.35  5247.7  271.95  5283.1  275.36  5306.1  275.72  5327.3  274.50
  5358.6  275.62  5385.1  274.32  5400.5  275.22  5406.3  274.27  5471.8  274.99
  5558.5  276.59  5646.4  279.99  5673.7  280.64  5760.4  282.90  5943.5  286.11
#Mann=11,-1,0
  4619.3    0.05       0  4849.7    0.07       0  4922.1    0.12       0
  5011.6    0.05       0  5015.8    0.12       0  5076.2    0.07       0
  5156.5    0.05       0  5358.6   0.035       0  5646.4    0.05       0
  5673.7   0.035       0  5760.4    0.05       0
Bank Sta=5011.6,5015.8
Exp/Cntr=0.3,0.1

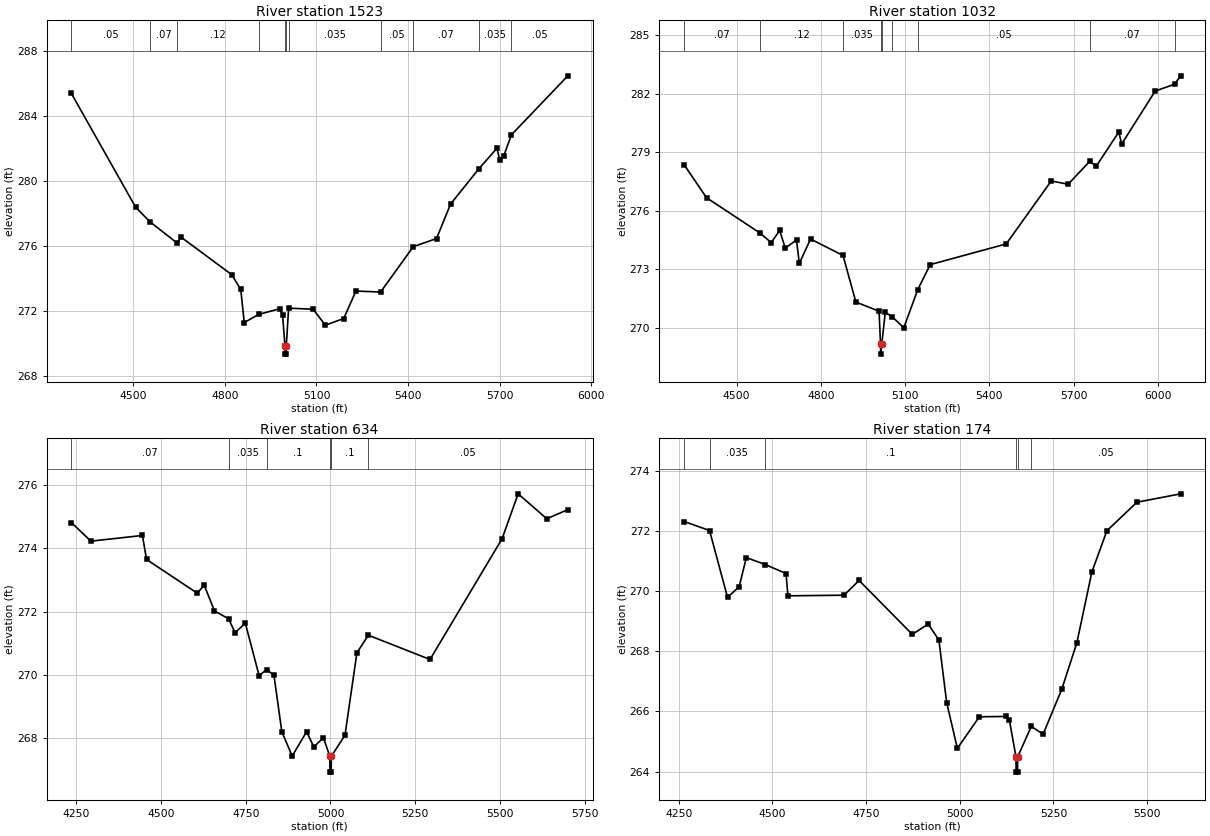
Type RM Length L Ch R = 1,1523,491,491,491
BEGIN DESCRIPTION:
XS7617
END DESCRIPTION:
XS GIS Cut Line= 4
      2460494.79     13696221.36      2460343.75     13695658.85
      2459984.38     13695664.06      2459364.61     13695377.62
#Sta/Elev= 30
  4298.0  285.39  4507.9  278.40  4554.6  277.50  4644.9  276.17  4656.6  276.55
  4822.6  274.24  4852.3  273.33  4863.7  271.29  4910.4  271.79  4979.2  272.14
  4989.2  271.74  4997.0  269.85  4997.3  269.35  5001.0  269.35  5001.3  269.85
  5008.9  272.18  5089.2  272.11  5129.2  271.13  5189.2  271.54  5229.2  273.23
  5309.9  273.17  5416.9  275.96  5493.0  276.46  5538.8  278.58  5631.0  280.74
  5690.8  282.02  5699.4  281.30  5712.9  281.55  5738.0  282.84  5922.6  286.47
#Mann=11,-1,0
  4298.0    0.05       0  4554.6    0.07       0  4644.9    0.12       0
  4910.4    0.07       0  4997.0    0.05       0  5001.3    0.07       0
  5008.9   0.035       0  5309.9    0.05       0  5416.9    0.07       0
  5631.0   0.035       0  5738.0    0.05       0
Bank Sta=4997,5001.3
Exp/Cntr=0.3,0.1

Type RM Length L Ch R = 1,1032,398,398,398
BEGIN DESCRIPTION:
XS7616
END DESCRIPTION:
XS GIS Cut Line= 4
      2460661.46     13696065.07      2460651.04     13695460.94
      2460453.13     13695356.77      2459515.59     13695294.27
#Sta/Elev= 30
  4313.4  278.35  4393.2  276.66  4583.5  274.85  4623.5  274.36  4653.5  274.98
  4673.5  274.08  4713.5  274.49  4723.5  273.29  4763.5  274.54  4879.1  273.70
  4924.9  271.31  5007.4  270.84  5012.7  269.14  5013.0  268.64  5017.0  269.14
  5029.4  270.78  5053.8  270.56  5095.5  269.99  5145.2  271.95  5189.5  273.23
  5460.1  274.29  5620.5  277.52  5680.6  277.35  5757.1  278.52  5780.8  278.28
  5861.0  280.03  5871.0  279.41  5990.5  282.13  6059.7  282.48  6080.9  282.91
#Mann=9,-1,0
  4313.4    0.07       0  4583.5    0.12       0  4879.1   0.035       0
  5012.7   0.035       0  5017.0   0.035       0  5053.8     0.1       0
  5145.2    0.05       0  5757.1    0.07       0  6059.7   0.035       0
Bank Sta=5012.7,5017
Exp/Cntr=0.3,0.1

Type RM Length L Ch R = 1,634,460,460,460
BEGIN DESCRIPTION:
XS7615
END DESCRIPTION:
XS GIS Cut Line= 4
      2460755.20     13695862.01      2460854.17     13695247.40
      2460656.25     13695059.90      2460093.77     13694966.15
#Sta/Elev= 30
  4235.3  274.82  4293.0  274.23  4445.0  274.41  4457.2  273.65  4607.0  272.58
  4627.3  272.84  4657.7  272.02  4699.2  271.77  4718.5  271.33  4748.8  271.63
  4789.4  269.97  4811.7  270.16  4833.3  269.98  4856.5  268.19  4887.1  267.42
  4929.6  268.19  4951.0  267.71  4979.3  268.00  4998.2  267.41  4998.5  266.91
  5002.2  266.91  5002.5  267.41  5042.9  268.08  5078.1  270.69  5111.9  271.25
  5293.9  270.48  5506.8  274.31  5554.0  275.73  5638.6  274.94  5700.7  275.23
#Mann=6,-1,0
  4235.3    0.07       0  4699.2   0.035       0  4811.7     0.1       0
  4998.2    0.05       0  5002.5     0.1       0  5111.9    0.05       0
Bank Sta=4998.2,5002.5
Exp/Cntr=0.3,0.1

Type RM Length L Ch R = 1,174,0,0,0
BEGIN DESCRIPTION:
XS7614
END DESCRIPTION:
XS GIS Cut Line= 4
      2460939.03     13695460.48      2460984.38     13694872.40
      2460885.42     13694763.02      2460298.42     13694788.99
#Sta/Elev= 30
  4264.4  272.31  4332.3  272.01  4380.2  269.79  4411.2  270.14  4430.4  271.11
  4481.0  270.88  4536.4  270.58  4541.4  269.84  4691.1  269.86  4731.3  270.35
  4873.3  268.56  4915.9  268.90  4944.3  268.37  4965.2  266.28  4993.6  264.77
  5052.2  265.82  5122.3  265.83  5132.3  265.72  5150.1  264.48  5150.4  263.98
  5154.1  263.98  5154.4  264.48  5190.8  265.50  5222.4  265.24  5272.4  266.74
  5312.5  268.28  5352.5  270.63  5392.5  272.00  5472.6  272.95  5589.3  273.23
#Mann=6,-1,0
  4264.4    0.07       0  4332.3   0.035       0  4481.0     0.1       0
  5150.1    0.05       0  5154.4     0.1       0  5190.8    0.05       0
Bank Sta=5150.1,5154.4
Exp/Cntr=0.3,0.1

Chan Stop Cuts=-1