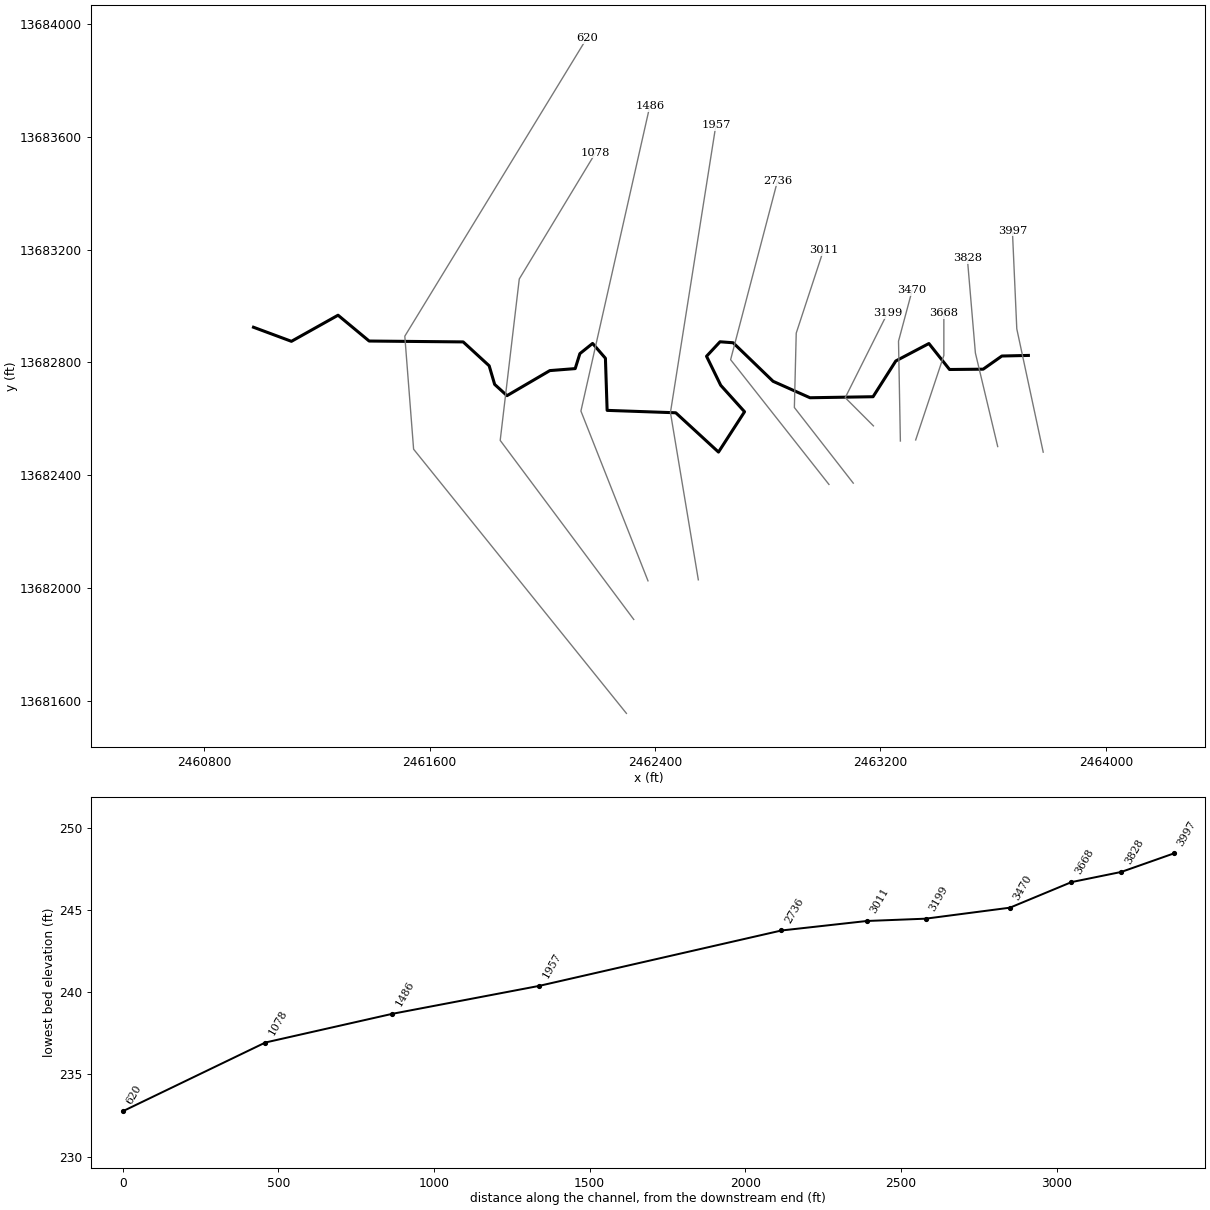
--- Stream0740.prj (project) ---

Proj Title=Stream0740 Base Level Engineering
Current Plan=p01
Default Exp/Contr=0.3,0.1
English Units
Geom File=g01
Flow File=f01
Plan File=p01
BEGIN DESCRIPTION:
Stream0740
END DESCRIPTION:

--- Stream0740.p01 (plan) ---

Plan Title=Multiple Run
Short Identifier=Multiple
Geom File=g01
Flow File=f01
Subcritical Flow
K Sum by GR= 0
Std Step Tol= 0.01
Critical Tol= 0.01
Num of Std Step Trials= 20
Max Error Tol= 0.3
Flow Tol Ratio= 0.001
Split Flow NTrial= 30
Split Flow Tol= 0.02
Split Flow Ratio= 0.02
Log Output Level= 0
Friction Slope Method= 1
Unsteady Friction Slope Method= 2
Unsteady Bridges Friction Slope Method= 1
Parabolic Critical Depth
Global Vel Dist=  1 , 1 , 1
Global Log Level= 0
CheckData=True
Encroach Param= -1, 0, 0, 0
BEGIN DESCRIPTION:
Multiple Run
END DESCRIPTION:

--- Stream0740.f01 (steady flow) ---

Flow Title=Multiple
Number of Profiles=7
Profile Names=10-year,25-year,50-year,1pct_min,100-year,1pct_plu,500-year
River Rch & RM= Stream0740,Reach-1,3997
     389     604     791     503    1003    2001    1595
Boundary for River Rch & Prof#=Stream0740,Reach-1,1
Up Type=0
Dn Type=3
Dn Slope=0.005
Boundary for River Rch & Prof#=Stream0740,Reach-1,2
Up Type=0
Dn Type=3
Dn Slope=0.005
Boundary for River Rch & Prof#=Stream0740,Reach-1,3
Up Type=0
Dn Type=3
Dn Slope=0.005
Boundary for River Rch & Prof#=Stream0740,Reach-1,4
Up Type=0
Dn Type=3
Dn Slope=0.005
Boundary for River Rch & Prof#=Stream0740,Reach-1,5
Up Type=0
Dn Type=3
Dn Slope=0.005
Boundary for River Rch & Prof#=Stream0740,Reach-1,6
Up Type=0
Dn Type=3
Dn Slope=0.005
Boundary for River Rch & Prof#=Stream0740,Reach-1,7
Up Type=0
Dn Type=3
Dn Slope=0.005

--- Stream0740.g01 (geometry) ---

Geom Title=Existing Conditions

River Reach=Stream0740,Reach-1
Reach XY= 30
      2463725.00     13682825.00      2463630.87     13682822.90
      2463564.49     13682776.18      2463445.20     13682775.05
      2463371.94     13682867.22      2463254.53     13682805.38
      2463173.75     13682678.45      2462949.91     13682674.79
      2462818.94     13682733.14      2462677.24     13682869.94
      2462630.65     13682873.43      2462582.76     13682822.00
      2462633.16     13682718.95      2462717.70     13682625.08
      2462625.22     13682481.98      2462473.54     13682621.46
      2462230.00     13682630.00      2462223.94     13682814.91
      2462178.45     13682867.58      2462133.32     13682831.37
      2462116.66     13682778.22      2462026.66     13682771.14
      2461874.70     13682682.20      2461830.85     13682722.15
      2461811.38     13682788.21      2461719.16     13682872.95
      2461385.43     13682876.06      2461275.08     13682967.70
      2461109.62     13682875.03      2460975.00     13682925.00

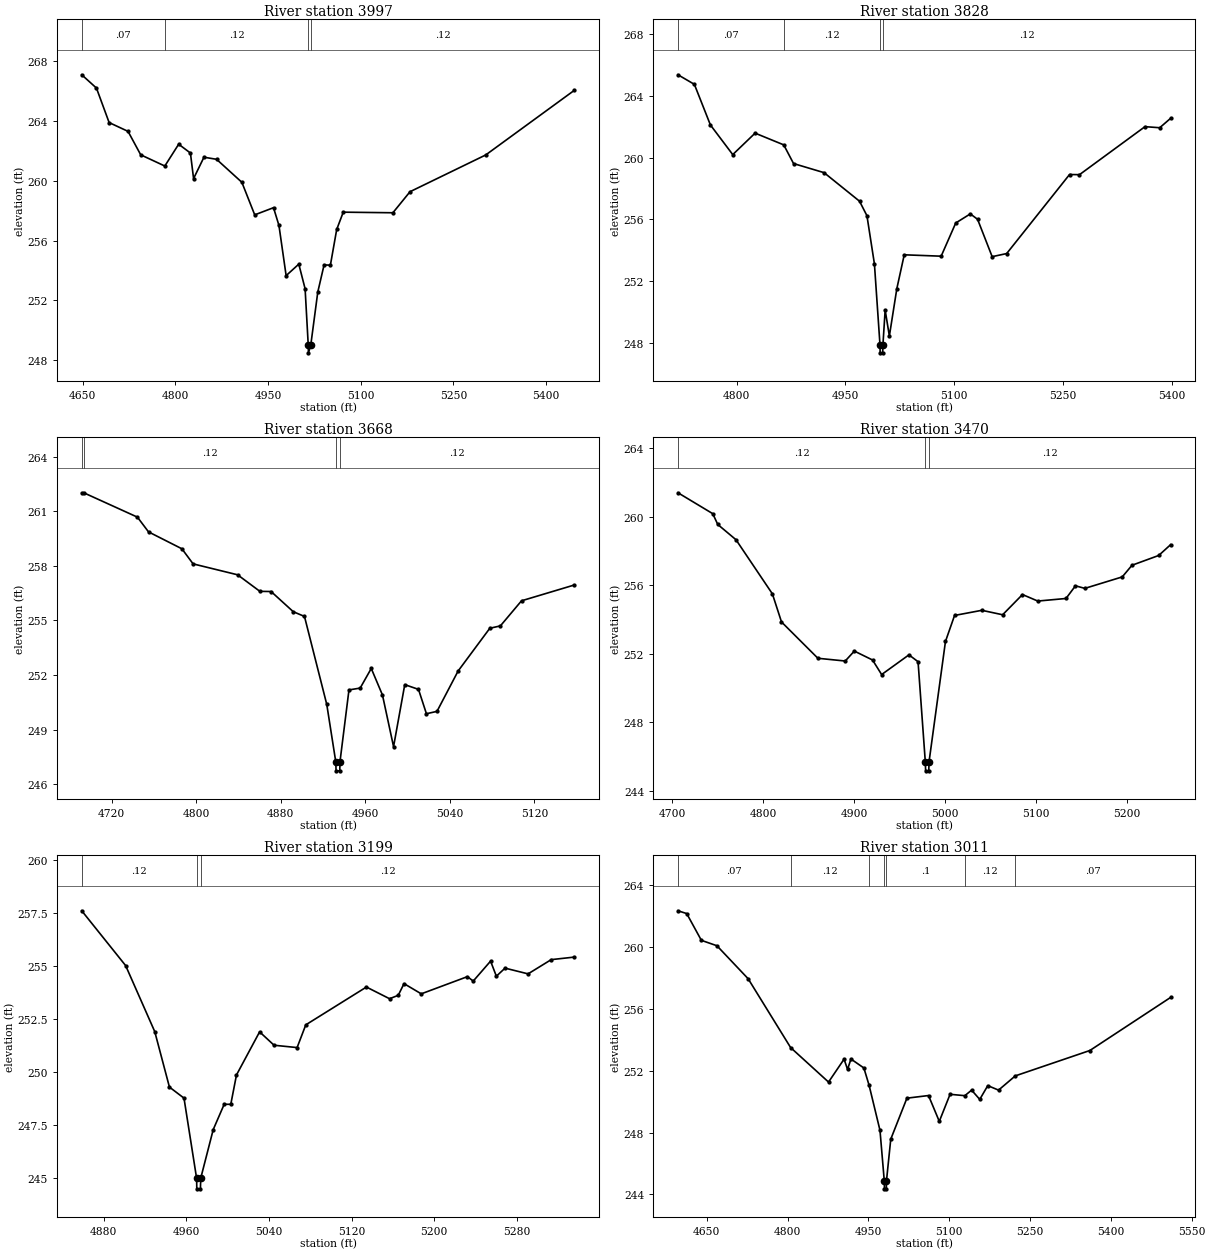
Type RM Length L Ch R = 1,3997,169,169,169
BEGIN DESCRIPTION:
XS7622
END DESCRIPTION:
XS GIS Cut Line= 3
      2463777.61     13682481.72      2463683.85     13682919.27
      2463668.23     13683268.24
#Sta/Elev= 30
  4648.7  267.10  4672.5  266.21  4693.0  263.90  4723.6  263.31  4744.1  261.74
  4783.1  260.99  4805.5  262.45  4824.5  261.86  4829.6  260.15  4846.4  261.58
  4866.8  261.44  4907.7  259.90  4928.5  257.72  4958.9  258.20  4967.7  257.01
  4979.3  253.65  4999.8  254.42  5010.0  252.77  5015.1  248.98  5015.4  248.48
  5019.1  248.98  5030.5  252.55  5040.7  254.37  5050.9  254.35  5061.1  256.74
  5071.7  257.90  5152.0  257.86  5179.7  259.27  5302.1  261.73  5445.5  266.06
#Mann=4,-1,0
  4648.7    0.07       0  4783.1    0.12       0  5015.1    0.05       0
  5019.1    0.12       0
Bank Sta=5015.1,5019.1
Exp/Cntr=0.3,0.1

Type RM Length L Ch R = 1,3828,160,160,160
BEGIN DESCRIPTION:
E21305
END DESCRIPTION:
XS GIS Cut Line= 3
      2463616.09     13682501.57      2463536.90     13682833.74
      2463508.32     13683170.14
#Sta/Elev= 30
  4719.1  265.36  4741.7  264.74  4763.8  262.11  4794.6  260.19  4825.4  261.58
  4864.9  260.82  4878.4  259.61  4920.5  259.02  4969.4  257.17  4979.6  256.23
  4989.9  253.11  4997.6  247.85  4997.8  247.35  5001.3  247.35  5001.6  247.85
  5004.7  250.12  5010.5  248.44  5020.8  251.51  5031.0  253.70  5081.9  253.61
  5102.0  255.76  5122.1  256.35  5132.1  256.00  5152.2  253.58  5172.2  253.78
  5258.9  258.90  5272.6  258.89  5362.9  262.00  5383.2  261.93  5398.2  262.54
#Mann=4,-1,0
  4719.1    0.07       0  4864.9    0.12       0  4997.6    0.05       0
  5001.6    0.12       0
Bank Sta=4997.6,5001.6
Exp/Cntr=0.3,0.1

Type RM Length L Ch R = 1,3668,198,198,198
BEGIN DESCRIPTION:
Stream0740 5.0
END DESCRIPTION:
XS GIS Cut Line= 3
      2463325.01     13682525.03      2463425.00     13682825.00
      2463425.00     13682975.01
#Sta/Elev= 30
  4691.6  262.02  4693.5  262.02  4744.3  260.68  4754.8  259.87  4786.4  258.94
  4797.0  258.11  4839.1  257.51  4860.2  256.60  4870.8  256.59  4891.8  255.48
  4902.4  255.22  4923.5  250.38  4932.0  247.23  4932.3  246.73  4935.8  246.73
  4936.0  247.23  4944.5  251.18  4955.1  251.28  4965.6  252.36  4976.2  250.90
  4986.7  248.06  4997.3  251.47  5010.3  251.21  5017.8  249.87  5027.8  250.00
  5047.8  252.22  5077.8  254.57  5087.8  254.70  5107.8  256.08  5157.8  256.95
#Mann=4,-1,0
  4691.6    0.07       0  4693.5    0.12       0  4932.0    0.05       0
  4936.0    0.12       0
Bank Sta=4932,4936
Exp/Cntr=0.3,0.1

Type RM Length L Ch R = 1,3470,271,271,271
BEGIN DESCRIPTION:
E21304
END DESCRIPTION:
XS GIS Cut Line= 3
      2463270.70     13682521.30      2463264.10     13682875.54
      2463312.50     13683055.96
#Sta/Elev= 30
  4706.7  261.40  4744.9  260.18  4750.4  259.55  4770.4  258.66  4810.4  255.50
  4820.4  253.86  4860.4  251.74  4890.4  251.58  4900.4  252.16  4920.4  251.64
  4930.4  250.79  4960.4  251.94  4970.4  251.54  4978.4  245.67  4978.7  245.17
  4982.2  245.17  4982.4  245.67  5000.5  252.72  5010.5  254.24  5040.5  254.54
  5063.3  254.28  5085.1  255.46  5101.9  255.08  5132.9  255.23  5143.3  255.97
  5153.6  255.82  5194.7  256.49  5205.4  257.17  5234.7  257.74  5247.8  258.37
#Mann=3,-1,0
  4706.7    0.12       0  4978.4    0.05       0  4982.4    0.12       0
Bank Sta=4978.4,4982.4
Exp/Cntr=0.3,0.1

Type RM Length L Ch R = 1,3199,188,188,188
BEGIN DESCRIPTION:
Stream0740 4.0
END DESCRIPTION:
XS GIS Cut Line= 3
      2463175.03     13682574.97      2463075.00     13682675.00
      2463225.01     13682975.03
#Sta/Elev= 30
  4858.7  257.59  4901.2  255.01  4929.4  251.90  4943.6  249.29  4957.7  248.77
  4969.9  245.00  4970.1  244.50  4973.6  244.50  4973.9  245.00  4986.0  247.29
  4996.6  248.48  5003.0  248.48  5008.5  249.86  5030.9  251.89  5044.9  251.26
  5067.2  251.15  5075.6  252.22  5134.3  254.00  5156.7  253.45  5165.1  253.61
  5170.7  254.16  5187.4  253.68  5232.1  254.49  5237.7  254.28  5254.5  255.22
  5260.1  254.51  5268.5  254.89  5290.8  254.62  5313.2  255.29  5335.6  255.41
#Mann=3,-1,0
  4858.7    0.12       0  4969.9    0.05       0  4973.9    0.12       0
Bank Sta=4969.9,4973.9
Exp/Cntr=0.3,0.1

Type RM Length L Ch R = 1,3011,275,275,275
BEGIN DESCRIPTION:
E21303
END DESCRIPTION:
XS GIS Cut Line= 4
      2463103.49     13682371.75      2462894.50     13682640.14
      2462901.10     13682904.14      2462997.89     13683198.91
#Sta/Elev= 30
  4596.4  262.33  4612.6  262.15  4639.8  260.42  4668.7  260.07  4726.6  257.94
  4805.5  253.49  4875.9  251.26  4904.7  252.74  4911.2  252.08  4917.5  252.75
  4941.5  252.17  4951.2  251.05  4971.4  248.14  4979.4  244.86  4979.7  244.36
  4983.2  244.36  4983.4  244.86  4991.4  247.57  5021.4  250.22  5061.5  250.39
  5081.5  248.72  5101.5  250.47  5128.9  250.38  5141.5  250.74  5156.6  250.14
  5171.5  251.03  5191.5  250.74  5222.6  251.66  5361.0  253.30  5510.9  256.73
#Mann=7,-1,0
  4596.4    0.07       0  4805.5    0.12       0  4951.2     0.1       0
  4979.4    0.05       0  4983.4     0.1       0  5128.9    0.12       0
  5222.6    0.07       0
Bank Sta=4979.4,4983.4
Exp/Cntr=0.3,0.1

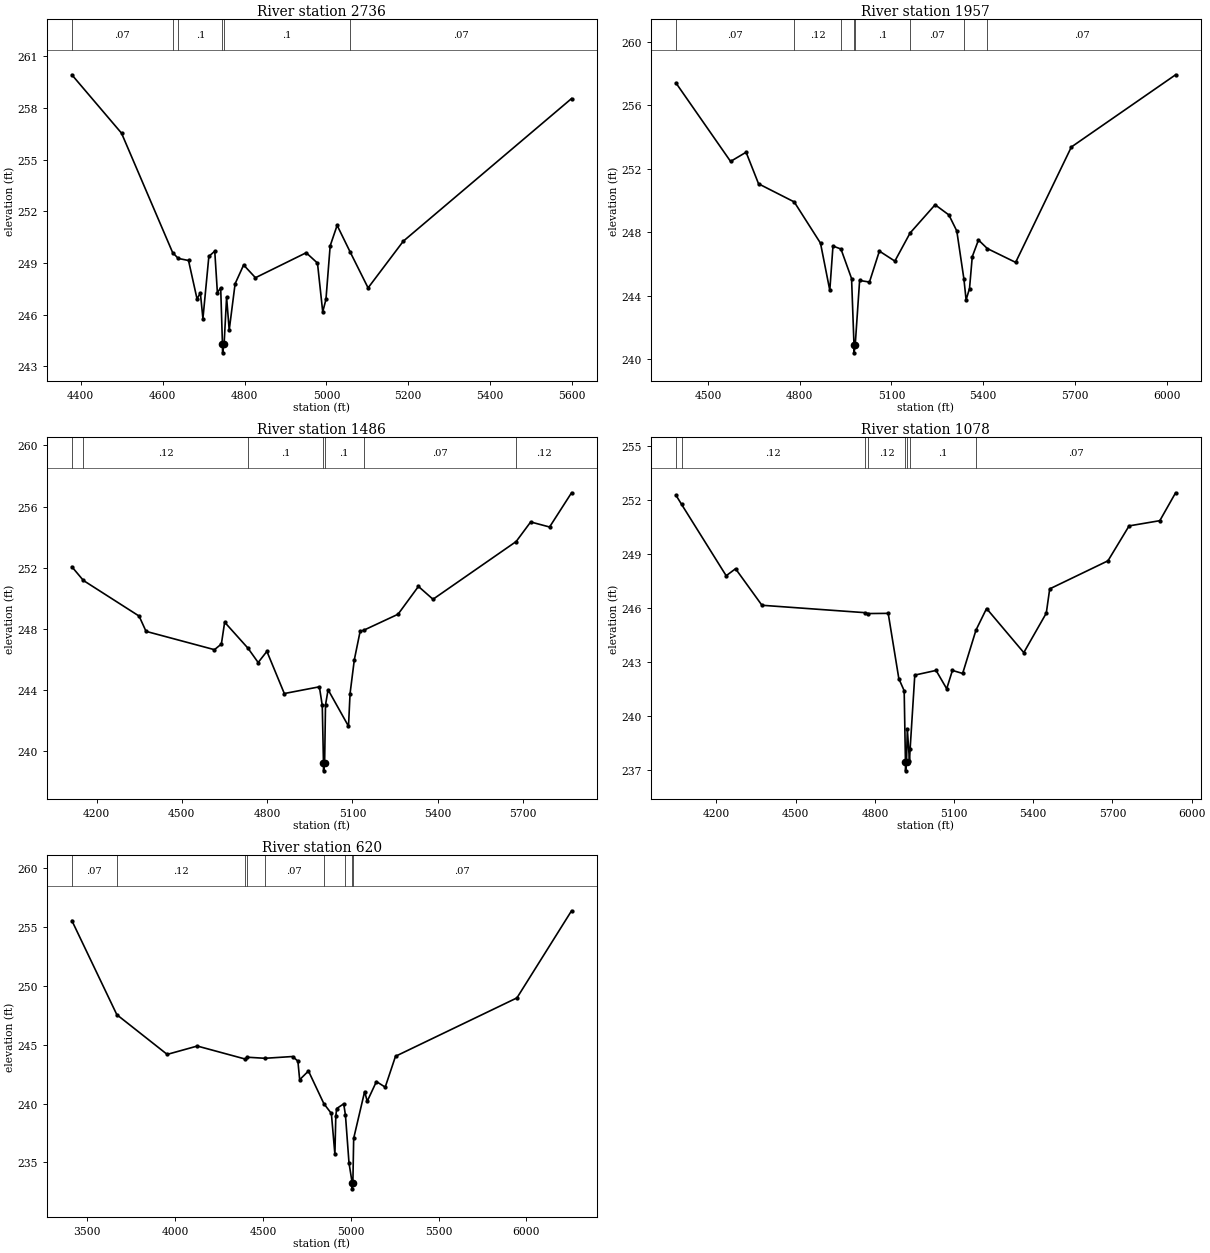
Type RM Length L Ch R = 1,2736,779,779,779
BEGIN DESCRIPTION:
XS7621
END DESCRIPTION:
XS GIS Cut Line= 3
      2463017.19     13682367.18      2462668.23     13682809.90
      2462834.89     13683445.29
#Sta/Elev= 30
  4378.2  259.92  4499.6  256.53  4624.4  249.60  4638.1  249.26  4663.2  249.14
  4684.0  246.91  4692.1  247.26  4698.4  245.77  4712.9  249.38  4727.3  249.68
  4733.7  247.28  4741.8  247.55  4746.1  244.28  4746.4  243.78  4750.1  244.28
  4756.2  247.01  4762.6  245.10  4777.0  247.79  4797.8  248.88  4826.7  248.14
  4950.6  249.59  4978.2  248.99  4991.0  246.16  4998.9  246.88  5009.2  249.99
  5026.2  251.18  5058.1  249.63  5101.8  247.55  5187.8  250.26  5598.8  258.54
#Mann=6,-1,0
  4378.2    0.07       0  4624.4    0.12       0  4638.1     0.1       0
  4746.1    0.05       0  4750.1     0.1       0  5058.1    0.07       0
Bank Sta=4746.1,4750.1
Exp/Cntr=0.3,0.1

Type RM Length L Ch R = 1,1957,471,471,471
BEGIN DESCRIPTION:
Stream0740 3.0
END DESCRIPTION:
XS GIS Cut Line= 3
      2462553.64     13682028.66      2462454.69     13682622.40
      2462615.89     13683641.60
#Sta/Elev= 30
  4395.4  257.41  4574.2  252.46  4624.9  253.04  4665.7  251.05  4782.2  249.91
  4868.2  247.31  4898.6  244.34  4909.0  247.13  4935.1  246.94  4969.8  245.08
  4977.7  240.90  4977.9  240.40  4981.7  240.90  4996.1  244.96  5028.3  244.86
  5060.7  246.81  5111.3  246.18  5161.1  247.95  5242.9  249.73  5287.9  249.09
  5313.8  248.08  5337.1  245.05  5344.2  243.74  5355.4  244.45  5364.4  246.46
  5384.7  247.51  5413.7  246.97  5506.2  246.10  5688.4  253.37  6029.2  257.92
#Mann=8,-1,0
  4395.4    0.07       0  4782.2    0.12       0  4935.1     0.1       0
  4977.7    0.05       0  4981.7     0.1       0  5161.1    0.07       0
  5337.1     0.1       0  5413.7    0.07       0
Bank Sta=4977.7,4981.7
Exp/Cntr=0.3,0.1

Type RM Length L Ch R = 1,1486,408,408,408
BEGIN DESCRIPTION:
Stream0740 2.0
END DESCRIPTION:
XS GIS Cut Line= 3
      2462374.99     13682025.03      2462136.98     13682627.60
      2462381.65     13683710.42
#Sta/Elev= 30
  4112.9  252.06  4153.6  251.16  4349.5  248.83  4373.9  247.83  4614.6  246.63
  4639.0  247.00  4650.5  248.43  4732.9  246.72  4768.4  245.79  4799.1  246.52
  4860.4  243.76  4983.7  244.20  4993.9  242.98  4998.2  239.20  4998.4  238.70
  5002.2  239.20  5005.3  243.01  5014.4  244.01  5086.2  241.62  5091.7  243.76
  5106.7  245.97  5127.2  247.84  5139.4  247.90  5260.5  248.95  5332.2  250.77
  5383.5  249.93  5676.1  253.71  5727.1  254.99  5793.6  254.66  5870.9  256.90
#Mann=7,-1,0
  4112.9    0.07       0  4153.6    0.12       0  4732.9     0.1       0
  4998.2    0.05       0  5002.2     0.1       0  5139.4    0.07       0
  5676.1    0.12       0
Bank Sta=4998.2,5002.2
Exp/Cntr=0.3,0.1

Type RM Length L Ch R = 1,1078,458,458,458
BEGIN DESCRIPTION:
XS7620
END DESCRIPTION:
XS GIS Cut Line= 4
      2462324.47     13681888.03      2461850.52     13682523.44
      2461918.23     13683096.35      2462189.04     13683544.24
#Sta/Elev= 30
  4046.2  252.27  4068.0  251.75  4236.7  247.79  4272.2  248.18  4372.2  246.15
  4761.1  245.74  4774.5  245.69  4850.5  245.70  4890.8  242.07  4911.0  241.40
  4915.8  237.45  4916.1  236.95  4919.8  237.45  4922.9  239.27  4931.1  237.50
  4933.5  238.16  4951.2  242.27  5031.8  242.53  5072.1  241.51  5093.7  242.53
  5132.5  242.36  5183.0  244.77  5223.1  245.97  5364.1  243.52  5449.3  245.71
  5462.3  247.06  5683.0  248.62  5763.0  250.56  5879.4  250.85  5939.2  252.40
#Mann=8,-1,0
  4046.2    0.07       0  4068.0    0.12       0  4761.1    0.07       0
  4774.5    0.12       0  4915.8    0.05       0  4919.8    0.12       0
  4933.5     0.1       0  5183.0    0.07       0
Bank Sta=4915.8,4919.8
Exp/Cntr=0.3,0.1

Type RM Length L Ch R = 1,620,0,0,0
BEGIN DESCRIPTION:
Stream0740 1.0
END DESCRIPTION:
XS GIS Cut Line= 4
      2462298.45     13681554.67      2461543.23     13682492.19
      2461511.98     13682893.23      2462157.68     13683950.30
#Sta/Elev= 30
  3412.2  255.55  3668.5  247.55  3955.0  244.18  4126.2  244.89  4400.7  243.78
  4411.0  243.94  4511.7  243.85  4669.0  244.00  4699.1  243.61  4709.2  242.03
  4759.3  242.77  4846.8  240.00  4889.7  239.16  4909.8  235.69  4914.9  238.93
  4919.9  239.58  4959.9  239.98  4969.8  239.03  4990.0  234.97  5008.1  233.26
  5008.3  232.76  5012.1  233.26  5016.7  237.05  5079.0  241.02  5093.9  240.20
  5146.1  241.87  5196.2  241.40  5254.8  244.02  5946.1  248.98  6257.0  256.38
#Mann=9,-1,0
  3412.2    0.07       0  3668.5    0.12       0  4400.7    0.07       0
  4411.0    0.12       0  4511.7    0.07       0  4846.8     0.1       0
  4969.8    0.07       0  5008.1    0.05       0  5012.1    0.07       0
Bank Sta=5008.1,5012.1
Exp/Cntr=0.3,0.1

Chan Stop Cuts=-1