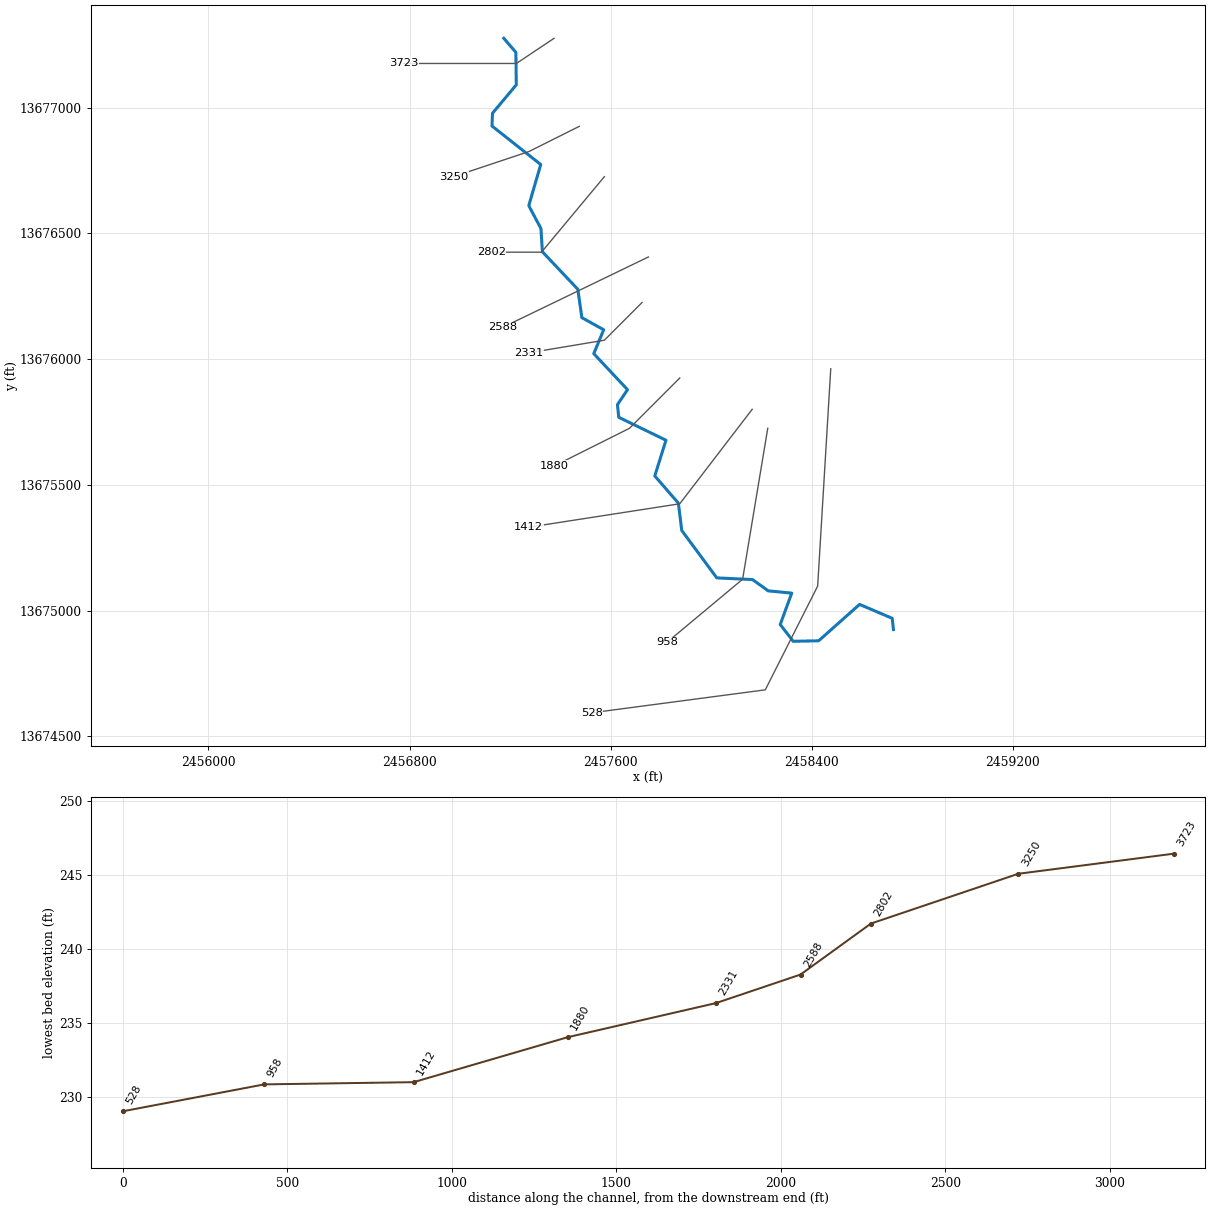
--- Stream0741.prj (project) ---

Proj Title=Stream0741 Base Level Engineering
Current Plan=p01
Default Exp/Contr=0.3,0.1
English Units
Geom File=g01
Flow File=f01
Plan File=p01
BEGIN DESCRIPTION:
Stream0741
END DESCRIPTION:

--- Stream0741.p01 (plan) ---

Plan Title=Multiple Run
Short Identifier=Multiple
Geom File=g01
Flow File=f01
Subcritical Flow
K Sum by GR= 0
Std Step Tol= 0.01
Critical Tol= 0.01
Num of Std Step Trials= 20
Max Error Tol= 0.3
Flow Tol Ratio= 0.001
Split Flow NTrial= 30
Split Flow Tol= 0.02
Split Flow Ratio= 0.02
Log Output Level= 0
Friction Slope Method= 1
Unsteady Friction Slope Method= 2
Unsteady Bridges Friction Slope Method= 1
Parabolic Critical Depth
Global Vel Dist=  1 , 1 , 1
Global Log Level= 0
CheckData=True
Encroach Param= -1, 0, 0, 0
BEGIN DESCRIPTION:
Multiple Run
END DESCRIPTION:

--- Stream0741.f01 (steady flow) ---

Flow Title=Multiple
Number of Profiles=7
Profile Names=10-year,25-year,50-year,1pct_min,100-year,1pct_plu,500-year
River Rch & RM= Stream0741,Reach-1,3723
     323     496     646     408     814    1624    1278
Boundary for River Rch & Prof#=Stream0741,Reach-1,1
Up Type=0
Dn Type=3
Dn Slope=0.005
Boundary for River Rch & Prof#=Stream0741,Reach-1,2
Up Type=0
Dn Type=3
Dn Slope=0.005
Boundary for River Rch & Prof#=Stream0741,Reach-1,3
Up Type=0
Dn Type=3
Dn Slope=0.005
Boundary for River Rch & Prof#=Stream0741,Reach-1,4
Up Type=0
Dn Type=3
Dn Slope=0.005
Boundary for River Rch & Prof#=Stream0741,Reach-1,5
Up Type=0
Dn Type=3
Dn Slope=0.005
Boundary for River Rch & Prof#=Stream0741,Reach-1,6
Up Type=0
Dn Type=3
Dn Slope=0.005
Boundary for River Rch & Prof#=Stream0741,Reach-1,7
Up Type=0
Dn Type=3
Dn Slope=0.005

--- Stream0741.g01 (geometry) ---

Geom Title=Existing Conditions

River Reach=Stream0741,Reach-1
Reach XY= 30
      2457175.00     13677275.00      2457223.12     13677219.21
      2457224.63     13677090.16      2457130.07     13676977.26
      2457128.01     13676926.43      2457321.88     13676773.38
      2457274.29     13676609.94      2457322.64     13676519.02
      2457328.61     13676426.50      2457469.47     13676277.42
      2457485.45     13676164.92      2457572.30     13676116.49
      2457532.83     13676021.61      2457667.18     13675878.41
      2457626.97     13675818.91      2457632.37     13675768.63
      2457820.03     13675677.58      2457775.61     13675535.63
      2457869.46     13675427.42      2457882.88     13675318.84
      2458022.30     13675130.36      2458164.49     13675123.77
      2458226.69     13675078.89      2458320.37     13675069.75
      2458274.56     13674945.02      2458326.22     13674878.37
      2458427.42     13674880.39      2458590.34     13675025.06
      2458720.10     13674969.73      2458725.00     13674925.00

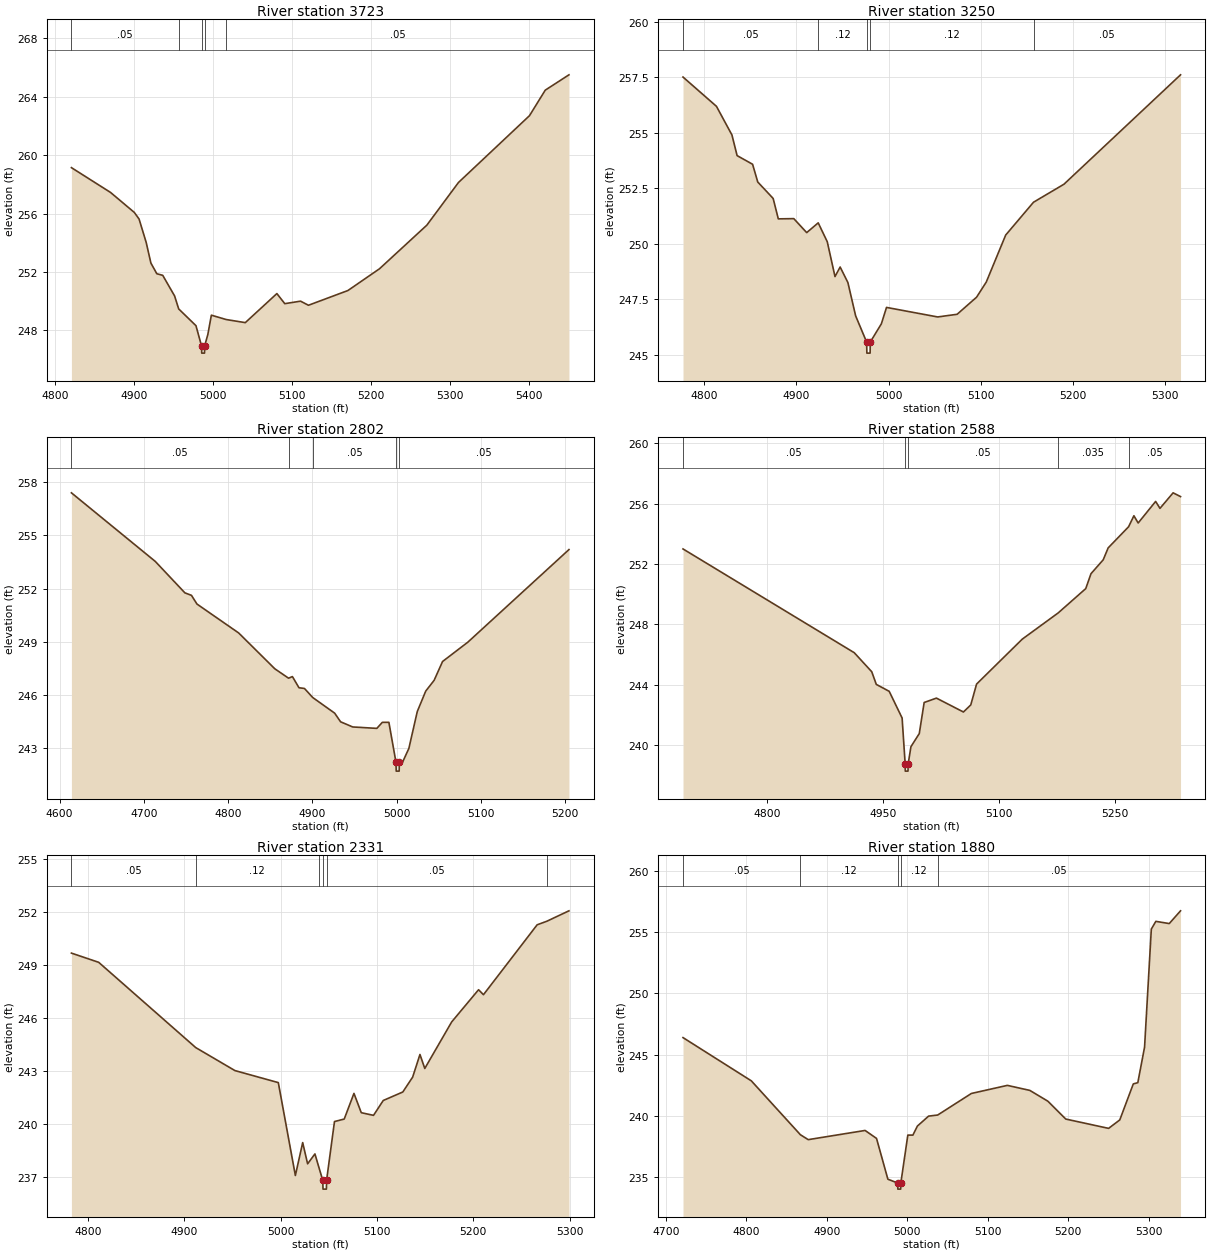
Type RM Length L Ch R = 1,3723,473,473,473
BEGIN DESCRIPTION:
Stream0741 8.0
END DESCRIPTION:
XS GIS Cut Line= 3
      2457375.04     13677275.02      2457225.00     13677175.00
      2456775.02     13677175.00
#Sta/Elev= 30
  4820.2  259.15  4869.8  257.45  4899.9  256.08  4905.9  255.63  4914.9  254.03
  4920.9  252.61  4928.4  251.88  4935.9  251.77  4950.9  250.36  4956.1  249.47
  4978.0  248.32  4985.0  246.94  4985.3  246.44  4988.8  246.44  4989.0  246.94
  4993.0  247.71  4997.5  249.04  5016.4  248.74  5040.5  248.53  5080.5  250.52
  5090.5  249.83  5110.5  250.00  5120.5  249.72  5170.5  250.73  5210.5  252.22
  5270.5  255.21  5310.5  258.13  5400.5  262.71  5420.5  264.46  5450.5  265.51
#Mann=5,-1,0
  4820.2    0.05       0  4956.1    0.12       0  4985.0    0.05       0
  4989.0    0.12       0  5016.4    0.05       0
Bank Sta=4985,4989
Exp/Cntr=0.3,0.1

Type RM Length L Ch R = 1,3250,448,448,448
BEGIN DESCRIPTION:
Stream0741 7.0
END DESCRIPTION:
XS GIS Cut Line= 3
      2457475.00     13676925.00      2457275.00     13676825.00
      2456975.03     13676725.01
#Sta/Elev= 30
  4776.9  257.52  4813.2  256.20  4830.0  254.91  4835.6  253.98  4852.4  253.59
  4858.0  252.79  4874.7  252.05  4880.3  251.13  4897.1  251.14  4911.1  250.51
  4923.6  250.95  4933.4  250.10  4941.8  248.53  4947.4  248.96  4955.8  248.26
  4964.2  246.76  4976.1  245.58  4976.4  245.08  4979.9  245.08  4980.1  245.58
  4992.1  246.40  4997.7  247.14  5053.2  246.71  5074.3  246.83  5095.4  247.60
  5105.9  248.28  5127.0  250.40  5157.2  251.88  5190.2  252.69  5316.7  257.62
#Mann=5,-1,0
  4776.9    0.05       0  4923.6    0.12       0  4976.1    0.05       0
  4980.1    0.12       0  5157.2    0.05       0
Bank Sta=4976.1,4980.1
Exp/Cntr=0.3,0.1

Type RM Length L Ch R = 1,2802,214,214,214
BEGIN DESCRIPTION:
Stream0741 6.0
END DESCRIPTION:
XS GIS Cut Line= 3
      2457574.98     13676724.98      2457325.00     13676425.00
      2457124.99     13676425.00
#Sta/Elev= 30
  4614.1  257.40  4713.7  253.53  4748.8  251.76  4756.6  251.62  4763.1  251.13
  4812.6  249.50  4855.5  247.48  4871.8  246.95  4876.4  247.04  4884.2  246.41
  4890.7  246.37  4900.5  245.86  4926.5  244.98  4933.6  244.49  4948.0  244.20
  4976.6  244.12  4983.1  244.46  4990.9  244.46  4999.3  242.21  4999.6  241.71
  5003.1  241.71  5003.3  242.21  5007.1  242.21  5014.6  242.99  5024.6  245.07
  5034.6  246.22  5044.6  246.83  5054.6  247.89  5084.6  248.98  5204.6  254.20
#Mann=5,-1,0
  4614.1    0.05       0  4871.8    0.12       0  4900.5    0.05       0
  4999.3    0.05       0  5003.3    0.05       0
Bank Sta=4999.3,5003.3
Exp/Cntr=0.3,0.1

Type RM Length L Ch R = 1,2588,257,257,257
BEGIN DESCRIPTION:
E21306
END DESCRIPTION:
XS GIS Cut Line= 2
      2457750.18     13676405.94      2457170.68     13676126.18
#Sta/Elev= 30
  4691.1  252.99  4912.6  246.11  4935.2  244.85  4941.1  244.01  4957.8  243.55
  4974.5  241.78  4978.4  238.76  4978.6  238.26  4982.1  238.26  4982.4  238.76
  4985.9  239.88  4996.7  240.75  5003.0  242.81  5018.9  243.10  5053.8  242.18
  5063.3  242.65  5070.8  244.03  5129.9  247.01  5176.4  248.75  5212.0  250.36
  5218.8  251.35  5234.6  252.27  5241.0  253.06  5267.4  254.46  5274.3  255.19
  5279.8  254.71  5302.4  256.14  5308.0  255.68  5325.0  256.71  5334.6  256.46
#Mann=5,-1,0
  4691.1    0.05       0  4978.4    0.05       0  4982.4    0.05       0
  5176.4   0.035       0  5267.4    0.05       0
Bank Sta=4978.4,4982.4
Exp/Cntr=0.3,0.1

Type RM Length L Ch R = 1,2331,451,451,451
BEGIN DESCRIPTION:
Stream0741 5.0
END DESCRIPTION:
XS GIS Cut Line= 3
      2457724.99     13676224.99      2457575.00     13676075.00
      2457274.96     13676024.99
#Sta/Elev= 30
  4782.9  249.67  4811.2  249.15  4911.9  244.33  4952.6  243.03  4997.6  242.35
  5015.3  237.10  5022.9  238.96  5028.0  237.76  5035.6  238.32  5039.5  237.60
  5043.7  236.83  5044.0  236.33  5047.5  236.33  5047.7  236.83  5055.9  240.15
  5066.0  240.29  5076.1  241.74  5083.7  240.65  5096.4  240.50  5106.5  241.34
  5126.8  241.82  5137.0  242.66  5144.6  243.94  5149.6  243.15  5177.5  245.78
  5205.4  247.60  5210.5  247.32  5266.2  251.27  5276.2  251.47  5299.2  252.06
#Mann=6,-1,0
  4782.9    0.05       0  4911.9    0.12       0  5039.5    0.05       0
  5043.7    0.05       0  5047.7    0.05       0  5276.2   0.035       0
Bank Sta=5043.7,5047.7
Exp/Cntr=0.3,0.1

Type RM Length L Ch R = 1,1880,468,468,468
BEGIN DESCRIPTION:
Stream0741 4.0
END DESCRIPTION:
XS GIS Cut Line= 3
      2457875.03     13675925.03      2457675.00     13675725.00
      2457375.00     13675575.00
#Sta/Elev= 30
  4721.3  246.39  4806.2  242.86  4867.2  238.46  4876.9  238.06  4947.6  238.81
  4961.8  238.16  4975.9  234.83  4988.0  234.52  4988.3  234.02  4991.8  234.02
  4992.0  234.52  5000.7  238.43  5007.0  238.43  5012.6  239.17  5026.5  239.98
  5037.8  240.07  5079.7  241.83  5124.4  242.49  5152.3  242.08  5174.7  241.20
  5197.0  239.74  5250.2  238.98  5264.1  239.67  5280.9  242.61  5286.5  242.71
  5294.9  245.61  5303.3  255.25  5308.9  255.88  5325.6  255.70  5339.6  256.74
#Mann=5,-1,0
  4721.3    0.05       0  4867.2    0.12       0  4988.0    0.05       0
  4992.0    0.12       0  5037.8    0.05       0
Bank Sta=4988,4992
Exp/Cntr=0.3,0.1

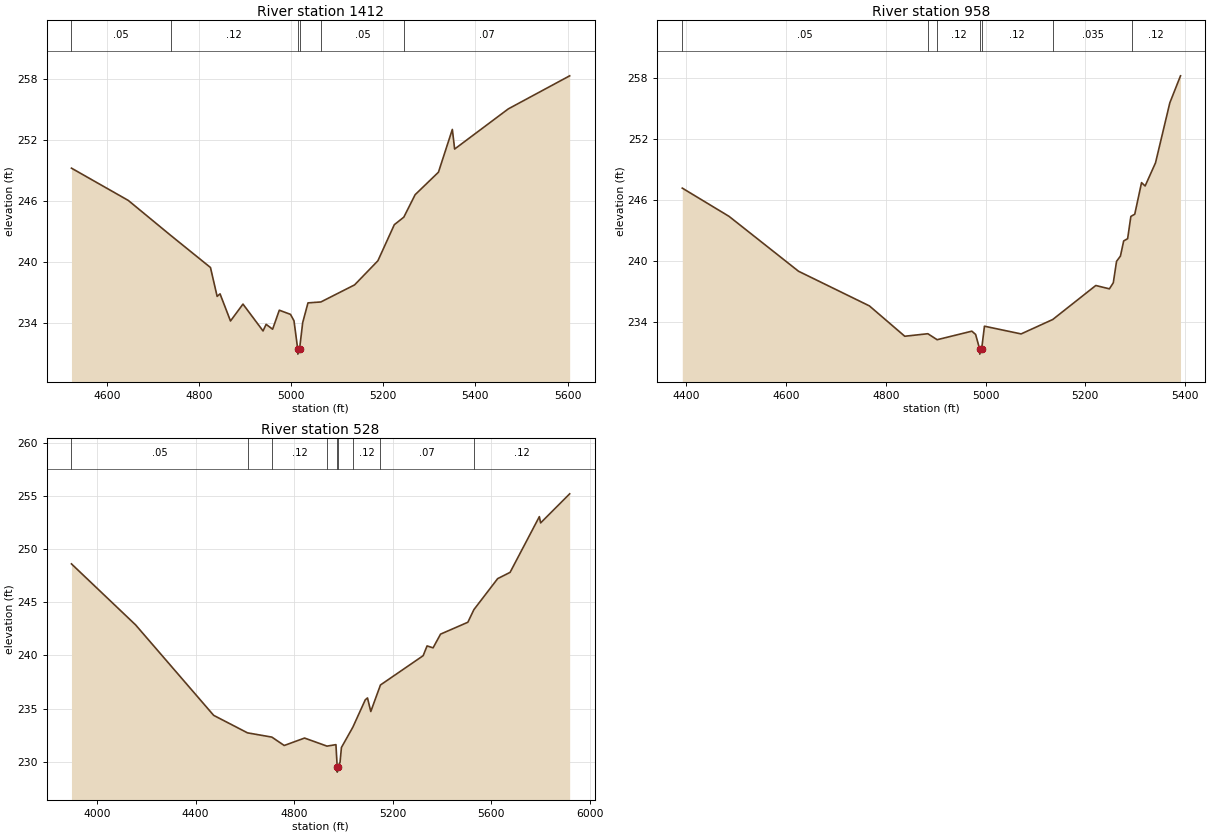
Type RM Length L Ch R = 1,1412,454,454,454
BEGIN DESCRIPTION:
Stream0741 3.0
END DESCRIPTION:
XS GIS Cut Line= 3
      2458163.08     13675800.40      2457875.00     13675425.00
      2457273.39     13675331.69
#Sta/Elev= 30
  4522.7  249.27  4646.0  246.10  4738.2  242.66  4824.6  239.50  4839.1  236.66
  4845.4  236.91  4868.1  234.24  4895.2  235.90  4938.8  233.26  4945.5  233.91
  4959.6  233.43  4974.1  235.30  4998.4  234.89  5006.0  234.26  5014.1  231.48
  5014.4  230.98  5018.1  231.48  5024.9  234.08  5036.4  236.02  5064.4  236.11
  5137.6  237.79  5188.2  240.16  5223.9  243.71  5244.5  244.45  5269.1  246.66
  5319.7  248.87  5349.9  253.08  5354.9  251.15  5471.5  255.10  5604.7  258.35
#Mann=6,-1,0
  4522.7    0.05       0  4738.2    0.12       0  5014.1    0.05       0
  5018.1    0.12       0  5064.4    0.05       0  5244.5    0.07       0
Bank Sta=5014.1,5018.1
Exp/Cntr=0.3,0.1

Type RM Length L Ch R = 1,958,430,430,430
BEGIN DESCRIPTION:
Stream0741 2.0
END DESCRIPTION:
XS GIS Cut Line= 3
      2458224.99     13675724.96      2458125.00     13675125.00
      2457825.03     13674875.03
#Sta/Elev= 30
  4392.1  247.18  4485.8  244.40  4625.2  238.99  4767.2  235.58  4838.1  232.59
  4884.3  232.84  4903.0  232.25  4972.5  233.09  4980.1  232.77  4988.2  231.33
  4988.4  230.83  4992.2  231.33  4997.8  233.58  5071.3  232.82  5134.7  234.24
  5221.0  237.59  5248.3  237.26  5256.1  237.86  5262.6  239.97  5270.4  240.49
  5276.9  241.98  5284.8  242.20  5291.3  244.39  5294.0  244.47  5299.1  244.61
  5312.7  247.72  5319.9  247.39  5340.7  249.67  5369.4  255.58  5390.8  258.24
#Mann=7,-1,0
  4392.1    0.05       0  4884.3    0.07       0  4903.0    0.12       0
  4988.2    0.05       0  4992.2    0.12       0  5134.7   0.035       0
  5294.0    0.12       0
Bank Sta=4988.2,4992.2
Exp/Cntr=0.3,0.1

Type RM Length L Ch R = 1,528,0,0,0
BEGIN DESCRIPTION:
Stream0741 1.0
END DESCRIPTION:
XS GIS Cut Line= 4
      2458475.61     13675961.42      2458423.52     13675097.74
      2458215.19     13674685.42      2457525.10     13674594.27
#Sta/Elev= 30
  3895.9  248.63  4156.5  242.88  4473.4  234.36  4610.9  232.71  4709.7  232.31
  4760.0  231.52  4842.6  232.22  4933.6  231.46  4970.0  231.60  4975.1  229.51
  4975.3  229.01  4979.1  229.51  4986.7  229.94  4992.3  231.33  5038.8  233.25
  5089.1  235.82  5098.2  236.00  5111.5  234.72  5150.8  237.22  5324.2  239.98
  5340.1  240.90  5364.5  240.72  5394.8  242.01  5505.7  243.13  5530.3  244.32
  5626.8  247.24  5677.2  247.83  5796.1  253.08  5801.2  252.49  5919.2  255.23
#Mann=9,-1,0
  3895.9    0.05       0  4610.9    0.07       0  4709.7    0.12       0
  4933.6   0.035       0  4975.1   0.035       0  4979.1   0.035       0
  5038.8    0.12       0  5150.8    0.07       0  5530.3    0.12       0
Bank Sta=4975.1,4979.1
Exp/Cntr=0.3,0.1

Chan Stop Cuts=-1