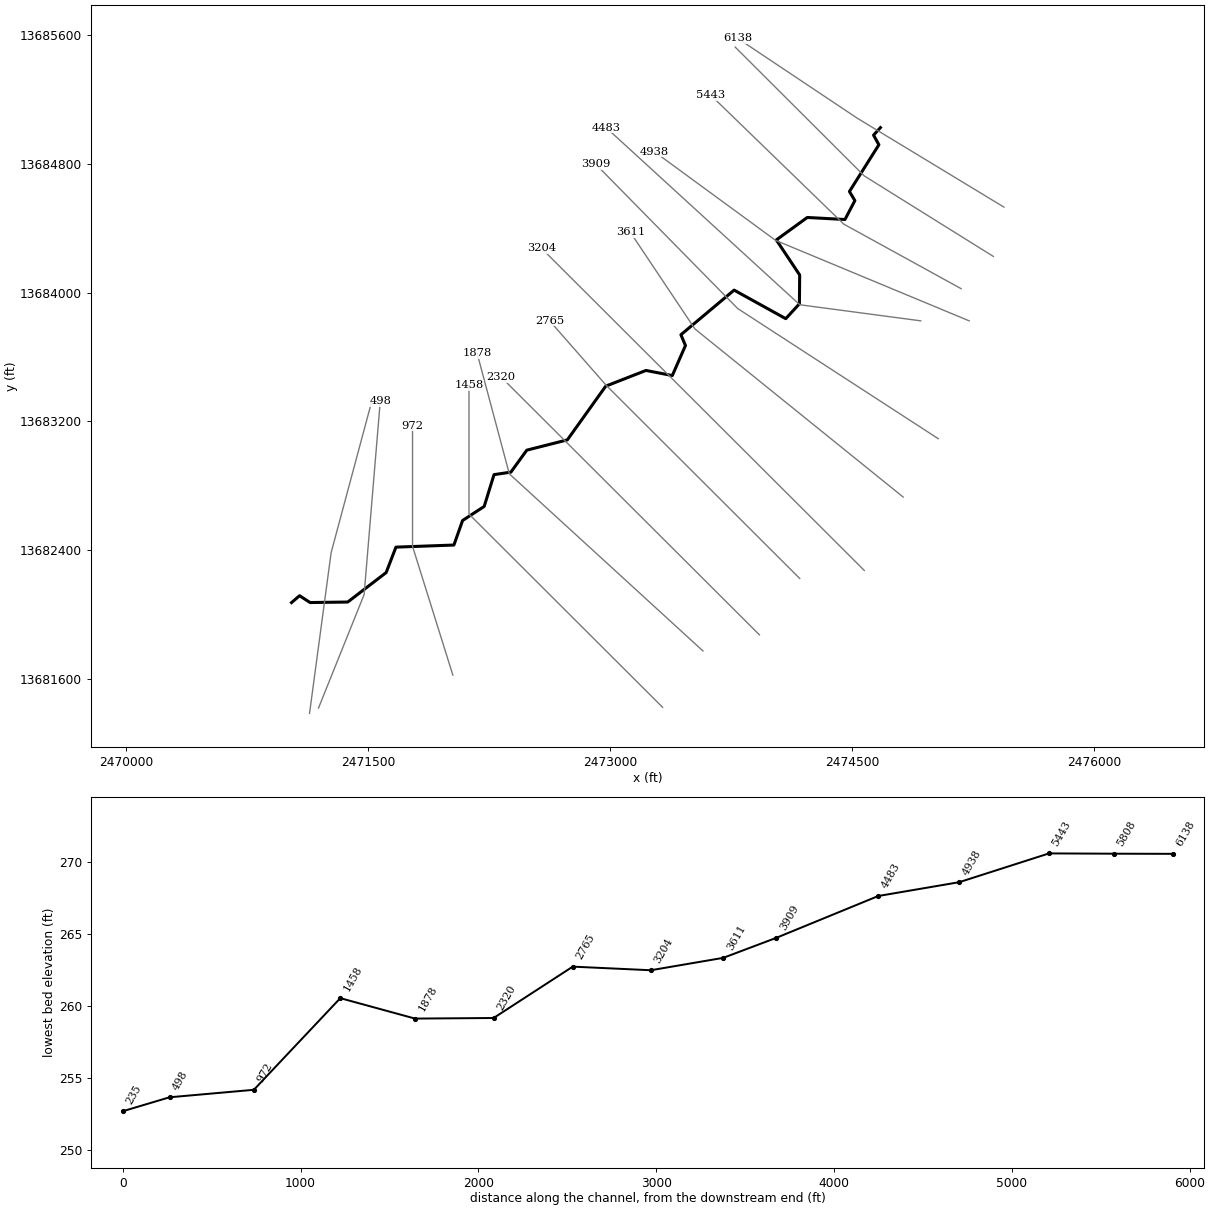
--- Stream0743.prj (project) ---

Proj Title=Stream0743 Base Level Engineering
Current Plan=p01
Default Exp/Contr=0.3,0.1
English Units
Geom File=g01
Flow File=f01
Plan File=p01
BEGIN DESCRIPTION:
Stream0743
END DESCRIPTION:

--- Stream0743.p01 (plan) ---

Plan Title=Multiple Run
Short Identifier=Multiple
Geom File=g01
Flow File=f01
Subcritical Flow
K Sum by GR= 0
Std Step Tol= 0.01
Critical Tol= 0.01
Num of Std Step Trials= 20
Max Error Tol= 0.3
Flow Tol Ratio= 0.001
Split Flow NTrial= 30
Split Flow Tol= 0.02
Split Flow Ratio= 0.02
Log Output Level= 0
Friction Slope Method= 1
Unsteady Friction Slope Method= 2
Unsteady Bridges Friction Slope Method= 1
Parabolic Critical Depth
Global Vel Dist=  1 , 1 , 1
Global Log Level= 0
CheckData=True
Encroach Param= -1, 0, 0, 0
BEGIN DESCRIPTION:
Multiple Run
END DESCRIPTION:

--- Stream0743.f01 (steady flow) ---

Flow Title=Multiple
Number of Profiles=7
Profile Names=10-year,25-year,50-year,1pct_min,100-year,1pct_plu,500-year
River Rch & RM= Stream0743,Reach-1,6138
     601     954    1266     813    1623    3237    2640
River Rch & RM= Stream0743,Reach-1,4938
     775    1239    1653    1066    2127    4245    3490
Boundary for River Rch & Prof#=Stream0743,Reach-1,1
Up Type=0
Dn Type=3
Dn Slope=0.005
Boundary for River Rch & Prof#=Stream0743,Reach-1,2
Up Type=0
Dn Type=3
Dn Slope=0.005
Boundary for River Rch & Prof#=Stream0743,Reach-1,3
Up Type=0
Dn Type=3
Dn Slope=0.005
Boundary for River Rch & Prof#=Stream0743,Reach-1,4
Up Type=0
Dn Type=3
Dn Slope=0.005
Boundary for River Rch & Prof#=Stream0743,Reach-1,5
Up Type=0
Dn Type=3
Dn Slope=0.005
Boundary for River Rch & Prof#=Stream0743,Reach-1,6
Up Type=0
Dn Type=3
Dn Slope=0.005
Boundary for River Rch & Prof#=Stream0743,Reach-1,7
Up Type=0
Dn Type=3
Dn Slope=0.005

--- Stream0743.g01 (geometry) ---

Geom Title=Existing Conditions

River Reach=Stream0743,Reach-1
Reach XY= 30
      2474675.00     13685025.00      2474632.51     13684978.34
      2474665.51     13684918.46      2474483.01     13684628.33
      2474516.75     13684571.77      2474455.38     13684454.32
      2474221.67     13684467.00      2474029.96     13684327.54
      2474174.62     13684109.84      2474172.94     13683930.83
      2474088.41     13683838.50      2473768.28     13684015.87
      2473438.50     13683738.68      2473466.71     13683671.79
      2473385.16     13683485.28      2473221.70     13683516.92
      2472972.45     13683419.27      2472734.71     13683085.75
      2472483.31     13683021.92      2472384.76     13682885.53
      2472280.11     13682869.89      2472219.27     13682672.45
      2472085.39     13682585.10      2472031.52     13682432.68
      2471672.26     13682419.66      2471611.60     13682261.70
      2471373.45     13682078.75      2471140.15     13682075.60
      2471074.86     13682118.09      2471025.00     13682075.00

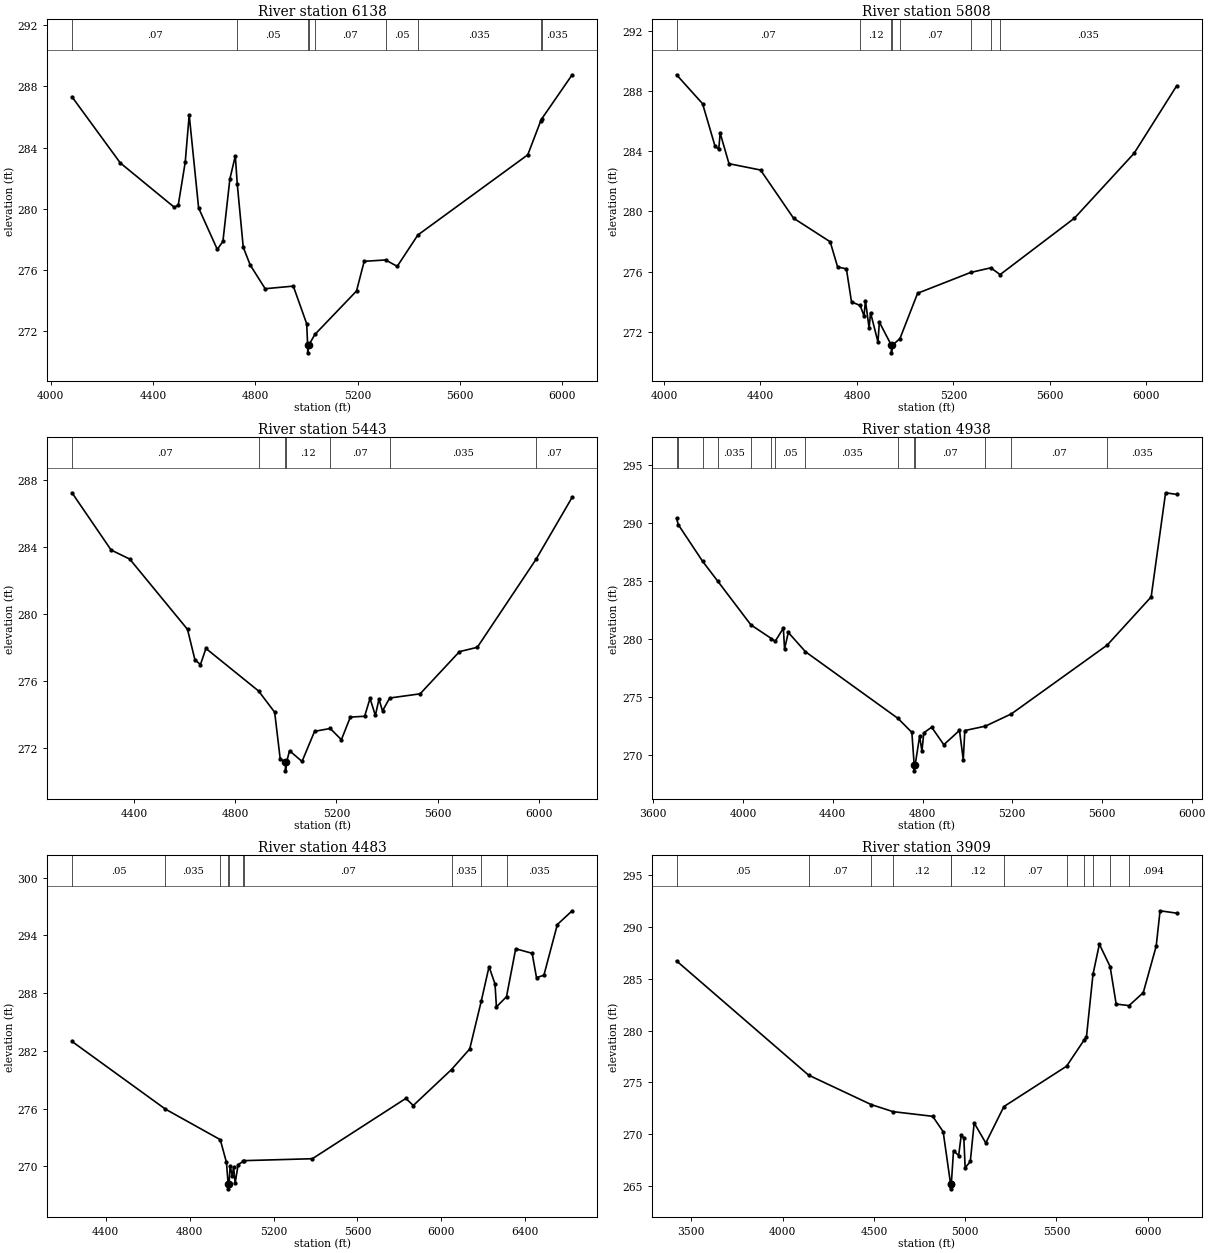
Type RM Length L Ch R = 1,6138,330,330,330
BEGIN DESCRIPTION:
XS7624
END DESCRIPTION:
XS GIS Cut Line= 3
      2475440.45     13684531.42      2474531.77     13685083.33
      2473790.32     13685579.48
#Sta/Elev= 30
  4082.7  287.32  4271.5  283.00  4482.8  280.10  4498.2  280.25  4525.4  283.05
  4540.9  286.14  4577.7  280.06  4650.7  277.35  4672.7  277.87  4699.9  281.95
  4721.2  283.46  4728.8  281.62  4752.2  277.49  4779.4  276.33  4837.9  274.78
  4947.9  274.95  5000.2  272.49  5004.0  271.09  5004.3  270.59  5008.1  271.09
  5032.2  271.79  5195.0  274.63  5225.0  276.57  5308.8  276.66  5354.1  276.24
  5434.8  278.29  5864.5  283.53  5915.7  285.77  5918.7  285.87  6038.0  288.76
#Mann=9,-1,0
  4082.7    0.07       0  4728.8    0.05       0  5004.0    0.05       0
  5008.1    0.05       0  5032.2    0.07       0  5308.8    0.05       0
  5434.8   0.035       0  5915.7    0.07       0  5918.7   0.035       0
Bank Sta=5004,5008.1
Exp/Cntr=0.3,0.1

Type RM Length L Ch R = 1,5808,365,365,365
BEGIN DESCRIPTION:
Stream0743 12.0
END DESCRIPTION:
XS GIS Cut Line= 3
      2475375.01     13684225.00      2474575.00     13684725.00
      2473774.98     13685525.02
#Sta/Elev= 30
  4051.8  289.08  4159.7  287.16  4211.6  284.33  4226.9  284.13  4232.8  285.20
  4269.4  283.17  4400.3  282.75  4537.1  279.55  4689.2  277.98  4719.9  276.31
  4756.4  276.18  4777.6  273.98  4813.5  273.75  4829.5  273.05  4835.4  274.07
  4850.7  272.22  4856.6  273.27  4887.3  271.32  4893.2  272.64  4943.0  271.10
  4943.3  270.60  4947.1  271.10  4978.6  271.55  5051.8  274.56  5271.4  275.94
  5355.3  276.25  5394.1  275.80  5702.3  279.55  5949.8  283.86  6126.6  288.35
#Mann=8,-1,0
  4051.8    0.07       0  4813.5    0.12       0  4943.0    0.05       0
  4947.1    0.12       0  4978.6    0.07       0  5271.4   0.035       0
  5355.3    0.07       0  5394.1   0.035       0
Bank Sta=4943,4947.1
Exp/Cntr=0.3,0.1

Type RM Length L Ch R = 1,5443,505,505,505
BEGIN DESCRIPTION:
Stream0743 11.0
END DESCRIPTION:
XS GIS Cut Line= 3
      2475174.98     13684025.01      2474448.15     13684425.50
      2473624.98     13685225.02
#Sta/Elev= 30
  4154.3  287.23  4309.0  283.81  4382.6  283.27  4611.0  279.07  4640.4  277.25
  4662.2  276.97  4683.9  277.93  4892.0  275.39  4955.6  274.12  4977.4  271.34
  4998.1  271.12  4998.4  270.62  5002.3  271.12  5014.4  271.82  5063.8  271.18
  5113.4  272.98  5175.2  273.15  5219.4  272.48  5254.7  273.83  5311.3  273.88
  5332.6  274.95  5353.7  273.93  5367.9  274.90  5382.0  274.20  5410.3  274.97
  5530.6  275.22  5686.1  277.74  5756.8  278.00  5988.6  283.25  6131.7  286.96
#Mann=7,-1,0
  4154.3    0.07       0  4892.0    0.12       0  4998.1    0.05       0
  5002.3    0.12       0  5175.2    0.07       0  5410.3   0.035       0
  5988.6    0.07       0
Bank Sta=4998.1,5002.3
Exp/Cntr=0.3,0.1

Type RM Length L Ch R = 1,4938,455,455,455
BEGIN DESCRIPTION:
Stream0743 10.0
END DESCRIPTION:
XS GIS Cut Line= 3
      2475225.03     13683824.99      2474025.00     13684325.00
      2473274.99     13684875.01
#Sta/Elev= 30
  3703.3  290.36  3711.2  289.82  3819.1  286.68  3886.9  284.96  4035.0  281.19
  4126.6  280.01  4142.9  279.77  4179.5  280.91  4184.9  279.12  4201.7  280.54
  4278.1  278.88  4691.1  273.13  4752.5  271.93  4762.9  269.12  4763.2  268.62
  4767.2  269.12  4787.2  271.61  4797.5  270.30  4805.6  271.89  4840.8  272.38
  4895.0  270.87  4964.9  272.10  4981.7  269.57  4988.7  272.09  5080.5  272.47
  5196.6  273.53  5623.4  279.45  5819.5  283.60  5883.8  292.57  5933.4  292.43
#Mann=14,-1,0
  3703.3    0.07       0  3711.2   0.035       0  3819.1    0.07       0
  3886.9   0.035       0  4035.0    0.07       0  4126.6   0.035       0
  4142.9    0.05       0  4278.1   0.035       0  4691.1    0.07       0
  4762.9    0.05       0  4767.2    0.07       0  5080.5   0.035       0
  5196.6    0.07       0  5623.4   0.035       0
Bank Sta=4762.9,4767.2
Exp/Cntr=0.3,0.1

Type RM Length L Ch R = 1,4483,574,574,574
BEGIN DESCRIPTION:
Stream0743 9.0
END DESCRIPTION:
XS GIS Cut Line= 3
      2474925.00     13683825.00      2474175.00     13683925.00
      2472975.01     13685024.99
#Sta/Elev= 30
  4239.2  282.98  4684.3  275.95  4946.1  272.77  4975.7  270.40  4983.6  268.16
  4983.9  267.66  4987.9  268.16  4993.3  270.07  5002.9  269.01  5009.7  269.92
  5017.1  268.25  5031.3  270.18  5055.3  270.51  5059.0  270.59  5385.2  270.79
  5831.0  277.06  5866.2  276.32  6048.5  280.06  6135.4  282.20  6190.3  287.16
  6227.5  290.75  6255.9  288.95  6262.7  286.57  6310.7  287.63  6354.6  292.61
  6432.9  292.14  6453.8  289.61  6489.0  289.86  6553.1  295.13  6623.7  296.56
#Mann=10,-1,0
  4239.2    0.05       0  4684.3   0.035       0  4946.1    0.07       0
  4983.6    0.05       0  4987.9    0.07       0  5055.3   0.035       0
  5059.0    0.07       0  6048.5   0.035       0  6190.3   0.094       0
  6310.7   0.035       0
Bank Sta=4983.6,4987.9
Exp/Cntr=0.3,0.1

Type RM Length L Ch R = 1,3909,298,298,298
BEGIN DESCRIPTION:
XS7625
END DESCRIPTION:
XS GIS Cut Line= 3
      2475033.49     13683093.13      2473790.32     13683901.47
      2472909.72     13684798.79
#Sta/Elev= 30
  3418.9  286.72  4142.2  275.71  4485.3  272.87  4605.0  272.19  4822.2  271.74
  4879.5  270.26  4919.9  265.25  4920.2  264.75  4924.3  265.25  4936.3  268.43
  4964.5  267.96  4978.7  269.95  4992.8  269.64  5000.0  266.77  5028.3  267.39
  5049.4  271.10  5113.1  269.17  5212.3  272.68  5555.7  276.57  5650.1  279.05
  5664.6  279.40  5700.4  285.43  5735.3  288.33  5794.2  286.17  5827.3  282.56
  5897.7  282.41  5975.8  283.66  6046.5  288.13  6067.8  291.55  6159.0  291.32
#Mann=12,-1,0
  3418.9    0.05       0  4142.2    0.07       0  4485.3   0.035       0
  4605.0    0.12       0  4919.9    0.05       0  4924.3    0.12       0
  5212.3    0.07       0  5555.7   0.094       0  5650.1   0.035       0
  5700.4   0.094       0  5794.2   0.035       0  5897.7   0.094       0
Bank Sta=4919.9,4924.3
Exp/Cntr=0.3,0.1

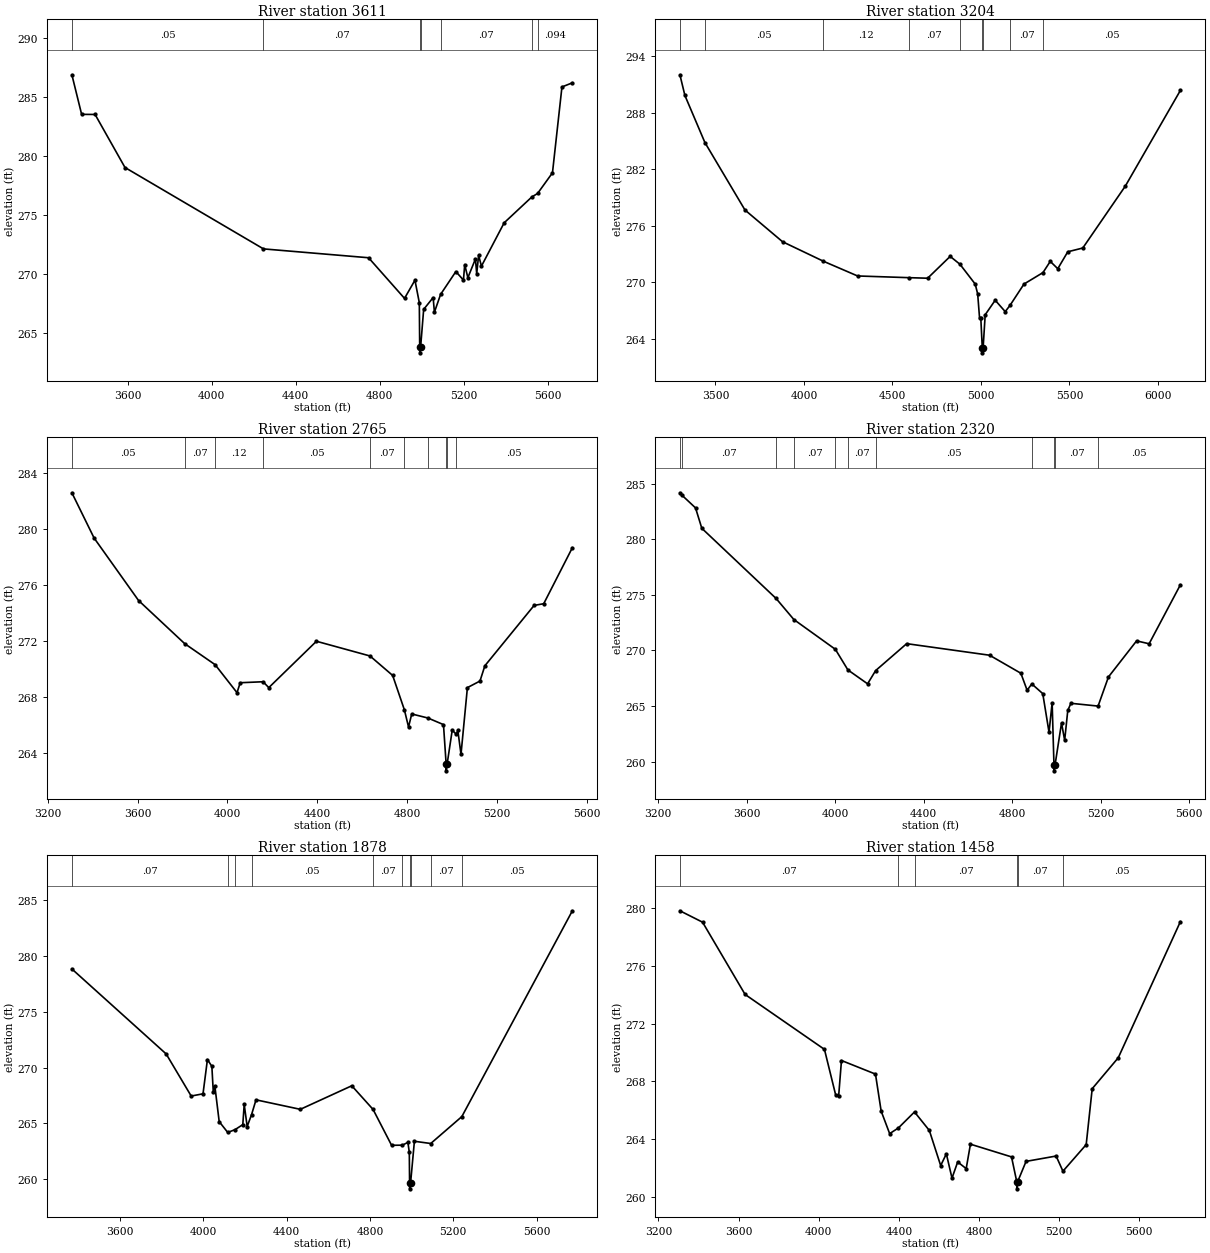
Type RM Length L Ch R = 1,3611,407,407,407
BEGIN DESCRIPTION:
Stream0743 8.0
END DESCRIPTION:
XS GIS Cut Line= 3
      2474816.05     13682730.79      2473525.00     13683775.00
      2473124.99     13684375.01
#Sta/Elev= 30
  3335.2  286.90  3381.6  283.55  3445.6  283.54  3587.9  279.05  4246.9  272.16
  4747.0  271.41  4918.1  267.97  4967.7  269.51  4988.5  267.60  4990.3  263.86
  4990.6  263.36  4994.7  263.86  5009.2  267.04  5054.3  268.04  5060.3  266.80
  5089.8  268.31  5162.4  270.24  5198.5  269.52  5204.5  270.83  5219.5  269.72
  5255.6  271.31  5261.6  270.05  5270.6  271.62  5284.1  270.70  5392.3  274.37
  5524.1  276.56  5551.2  276.85  5622.1  278.60  5667.2  285.87  5716.8  286.22
#Mann=7,-1,0
  3335.2    0.05       0  4246.9    0.07       0  4990.3    0.05       0
  4994.7    0.07       0  5089.8    0.07       0  5524.1    0.05       0
  5551.2   0.094       0
Bank Sta=4990.3,4994.7
Exp/Cntr=0.3,0.1

Type RM Length L Ch R = 1,3204,439,439,439
BEGIN DESCRIPTION:
Stream0743 7.0
END DESCRIPTION:
XS GIS Cut Line= 3
      2474575.02     13682274.98      2473375.00     13683475.00
      2472574.97     13684275.03
#Sta/Elev= 30
  3298.9  292.05  3327.2  289.85  3440.2  284.85  3666.6  277.68  3878.8  274.31
  4110.4  272.23  4303.0  270.67  4591.3  270.49  4699.0  270.43  4826.3  272.75
  4881.8  271.91  4967.7  269.81  4981.8  268.76  4992.5  266.18  4999.5  266.18
  5007.9  263.00  5008.2  262.50  5012.4  263.00  5024.3  266.55  5080.8  268.09
  5137.4  266.88  5164.4  267.54  5243.5  269.81  5350.9  271.03  5392.0  272.22
  5434.4  271.44  5491.0  273.24  5575.8  273.64  5816.2  280.22  6127.4  290.39
#Mann=9,-1,0
  3298.9    0.07       0  3440.2    0.05       0  4110.4    0.12       0
  4591.3    0.07       0  4881.8    0.12       0  5007.9    0.05       0
  5012.4    0.12       0  5164.4    0.07       0  5350.9    0.05       0
Bank Sta=5007.9,5012.4
Exp/Cntr=0.3,0.1

Type RM Length L Ch R = 1,2765,445,445,445
BEGIN DESCRIPTION:
Stream0743 6.0
END DESCRIPTION:
XS GIS Cut Line= 3
      2474174.97     13682225.03      2472975.00     13683425.00
      2472625.01     13683824.99
#Sta/Elev= 30
  3307.6  282.60  3406.5  279.37  3604.5  274.91  3809.9  271.83  3945.3  270.33
  4042.9  268.33  4057.1  269.04  4158.9  269.11  4184.4  268.69  4396.5  272.00
  4635.0  270.95  4735.9  269.56  4788.2  267.10  4806.6  265.88  4820.8  266.81
  4893.2  266.52  4962.2  266.05  4974.0  263.25  4974.4  262.75  4978.6  263.25
  5001.1  265.65  5019.6  265.36  5026.0  265.65  5040.2  263.93  5068.7  268.69
  5124.7  269.16  5146.5  270.25  5365.8  274.56  5408.5  274.68  5536.1  278.68
#Mann=10,-1,0
  3307.6    0.05       0  3809.9    0.07       0  3945.3    0.12       0
  4158.9    0.05       0  4635.0    0.07       0  4788.2    0.05       0
  4893.2    0.07       0  4974.0    0.05       0  4978.6    0.07       0
  5019.6    0.05       0
Bank Sta=4974,4978.6
Exp/Cntr=0.3,0.1

Type RM Length L Ch R = 1,2320,442,442,442
BEGIN DESCRIPTION:
Stream0743 5.0
END DESCRIPTION:
XS GIS Cut Line= 3
      2473924.99     13681875.01      2472725.00     13683075.00
      2472325.02     13683474.98
#Sta/Elev= 30
  3298.2  284.17  3308.1  283.94  3368.9  282.81  3397.2  280.98  3733.1  274.67
  3813.3  272.78  4001.1  270.10  4057.7  268.25  4146.7  267.00  4183.1  268.19
  4323.5  270.61  4698.3  269.57  4839.7  267.95  4868.0  266.42  4889.1  266.99
  4938.7  266.12  4967.0  262.65  4981.1  265.30  4989.4  259.68  4989.7  259.18
  4994.0  259.68  5023.5  263.48  5037.7  261.93  5051.8  264.61  5066.0  265.25
  5188.8  265.00  5235.7  267.62  5362.9  270.86  5419.5  270.60  5560.9  275.90
#Mann=11,-1,0
  3298.2    0.12       0  3308.1    0.07       0  3733.1    0.12       0
  3813.3    0.07       0  4001.1    0.12       0  4057.7    0.07       0
  4183.1    0.05       0  4889.1    0.07       0  4989.4    0.05       0
  4994.0    0.07       0  5188.8    0.05       0
Bank Sta=4989.4,4994
Exp/Cntr=0.3,0.1

Type RM Length L Ch R = 1,1878,420,420,420
BEGIN DESCRIPTION:
Stream0743 4.0
END DESCRIPTION:
XS GIS Cut Line= 3
      2473574.99     13681775.01      2472375.00     13682875.00
      2472174.99     13683625.02
#Sta/Elev= 30
  3368.1  278.83  3821.0  271.22  3941.2  267.45  3998.0  267.65  4019.2  270.72
  4040.5  270.11  4047.3  267.83  4054.7  268.37  4075.7  265.16  4116.8  264.19
  4151.7  264.44  4189.1  264.89  4195.9  266.70  4210.1  264.72  4231.1  265.78
  4252.6  267.11  4465.4  266.26  4712.6  268.37  4814.9  266.25  4903.8  263.04
  4955.4  263.05  4982.1  263.30  4988.9  262.42  4990.3  259.64  4990.6  259.14
  4994.9  259.64  5013.4  263.40  5091.9  263.20  5241.3  265.61  5772.2  284.04
#Mann=10,-1,0
  3368.1    0.07       0  4116.8    0.05       0  4151.7    0.07       0
  4231.1    0.05       0  4814.9    0.07       0  4955.4    0.12       0
  4990.3    0.05       0  4994.9    0.12       0  5091.9    0.07       0
  5241.3    0.05       0
Bank Sta=4990.3,4994.9
Exp/Cntr=0.3,0.1

Type RM Length L Ch R = 1,1458,486,486,486
BEGIN DESCRIPTION:
Stream0743 3.0
END DESCRIPTION:
XS GIS Cut Line= 3
      2473325.00     13681425.00      2472125.00     13682625.00
      2472125.00     13683425.04
#Sta/Elev= 30
  3307.6  279.80  3420.7  279.01  3632.9  274.01  4028.8  270.21  4085.4  267.02
  4099.6  266.97  4113.7  269.44  4283.4  268.50  4311.7  265.94  4354.1  264.38
  4397.5  264.77  4478.1  265.88  4552.1  264.60  4608.7  262.17  4637.0  262.98
  4665.2  261.30  4693.5  262.42  4736.0  261.96  4757.2  263.65  4962.2  262.77
  4988.2  261.06  4988.5  260.56  4992.9  261.06  5034.7  262.46  5184.7  262.83
  5218.7  261.78  5334.7  263.62  5364.7  267.49  5494.7  269.63  5804.7  279.05
#Mann=6,-1,0
  3307.6    0.07       0  4397.5    0.12       0  4478.1    0.07       0
  4988.2    0.05       0  4992.9    0.07       0  5218.7    0.05       0
Bank Sta=4988.2,4992.9
Exp/Cntr=0.3,0.1

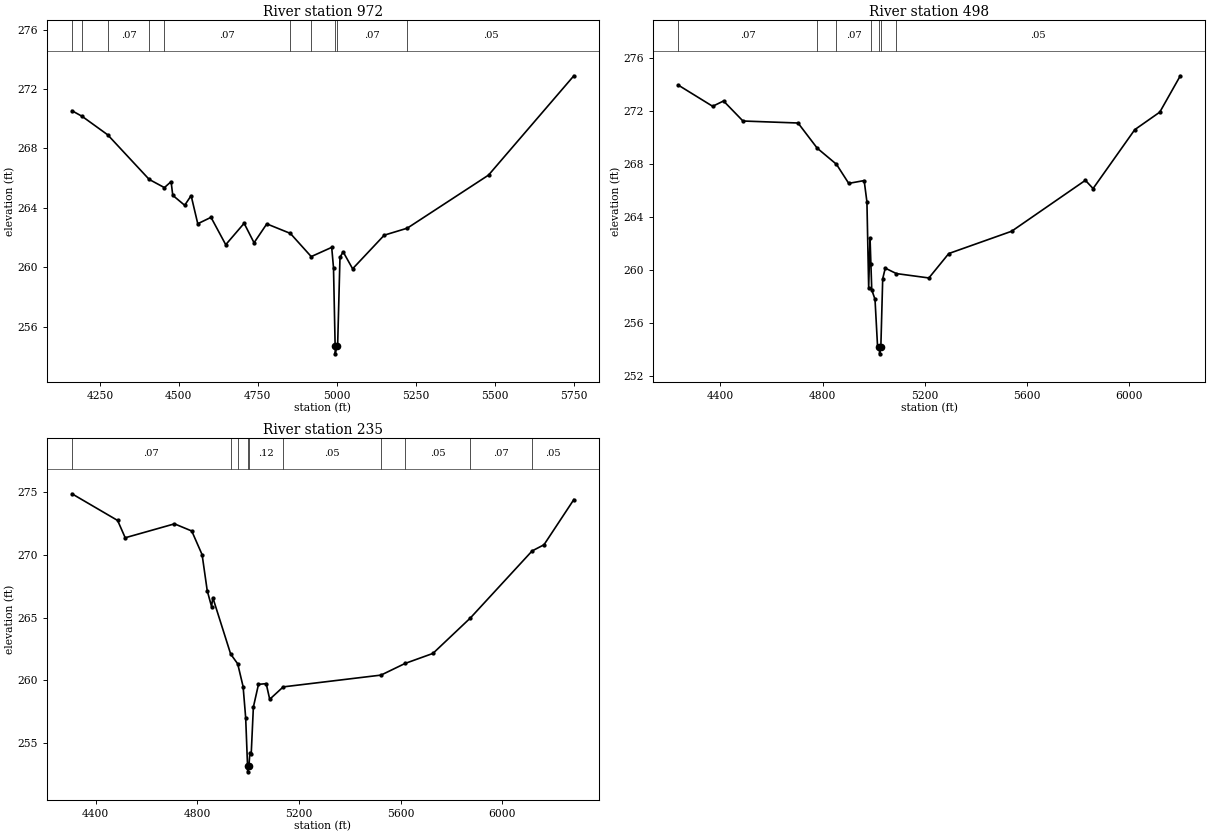
Type RM Length L Ch R = 1,972,474,474,474
BEGIN DESCRIPTION:
Stream0743 2.0
END DESCRIPTION:
XS GIS Cut Line= 3
      2472024.99     13681625.04      2471775.00     13682425.00
      2471775.00     13683174.99
#Sta/Elev= 30
  4161.8  270.54  4194.1  270.16  4274.9  268.92  4406.2  265.92  4454.3  265.37
  4475.5  265.77  4480.8  264.85  4518.5  264.18  4538.9  264.83  4559.9  262.94
  4601.8  263.37  4648.4  261.53  4706.6  262.97  4738.0  261.66  4778.3  262.93
  4852.8  262.29  4918.9  260.73  4983.7  261.35  4989.4  259.98  4994.6  254.69
  4995.0  254.19  4999.9  254.69  5002.4  254.69  5009.9  260.68  5019.9  261.05
  5049.9  259.91  5149.9  262.17  5222.7  262.64  5479.9  266.21  5749.9  272.89
#Mann=10,-1,0
  4161.8    0.07       0  4194.1   0.035       0  4274.9    0.07       0
  4406.2   0.035       0  4454.3    0.07       0  4852.8    0.12       0
  4918.9    0.07       0  4994.6    0.05       0  4999.9    0.07       0
  5222.7    0.05       0
Bank Sta=4994.6,4999.9
Exp/Cntr=0.3,0.1

Type RM Length L Ch R = 1,498,263,263,263
BEGIN DESCRIPTION:
Stream0743 1.0
END DESCRIPTION:
XS GIS Cut Line= 3
      2471192.47     13681420.69      2471475.00     13682125.00
      2471575.00     13683324.98
#Sta/Elev= 30
  4236.2  273.92  4370.1  272.33  4412.7  272.73  4488.7  271.22  4704.1  271.07
  4779.2  269.17  4854.3  267.96  4902.3  266.52  4962.7  266.73  4973.5  265.12
  4980.3  258.67  4985.7  262.38  4989.1  260.41  4992.4  258.49  5005.1  257.78
  5015.1  254.21  5022.4  254.17  5022.8  253.67  5027.9  254.17  5035.2  259.33
  5045.2  260.13  5088.6  259.72  5215.8  259.39  5293.6  261.23  5539.4  262.91
  5827.9  266.75  5858.0  266.13  6021.1  270.57  6118.9  271.89  6199.2  274.63
#Mann=7,-1,0
  4236.2    0.07       0  4779.2    0.12       0  4854.3    0.07       0
  4989.1    0.12       0  5022.4    0.05       0  5027.9    0.12       0
  5088.6    0.05       0
Bank Sta=5022.4,5027.9
Exp/Cntr=0.3,0.1

Type RM Length L Ch R = 1,235,0,0,0
BEGIN DESCRIPTION:
XS7623
END DESCRIPTION:
XS GIS Cut Line= 3
      2471136.73     13681387.26      2471270.52     13682385.13
      2471521.16     13683320.85
#Sta/Elev= 30
  4306.2  274.89  4486.0  272.76  4515.8  271.38  4709.8  272.49  4777.7  271.92
  4818.5  270.03  4838.7  267.15  4855.7  265.89  4860.7  266.60  4930.9  262.10
  4958.6  261.32  4979.9  259.50  4990.0  257.01  4997.3  253.20  4997.7  252.70
  5002.8  253.20  5006.6  254.23  5011.7  254.10  5020.3  257.87  5040.4  259.68
  5070.7  259.74  5084.6  258.49  5137.8  259.48  5522.7  260.42  5617.4  261.35
  5727.0  262.15  5874.0  264.97  6117.5  270.33  6164.1  270.82  6281.7  274.43
#Mann=10,-1,0
  4306.2    0.07       0  4930.9     0.1       0  4958.6    0.12       0
  4997.3    0.05       0  5002.8    0.12       0  5137.8    0.05       0
  5522.7    0.07       0  5617.4    0.05       0  5874.0    0.07       0
  6117.5    0.05       0
Bank Sta=4997.3,5002.8
Exp/Cntr=0.3,0.1

Chan Stop Cuts=-1