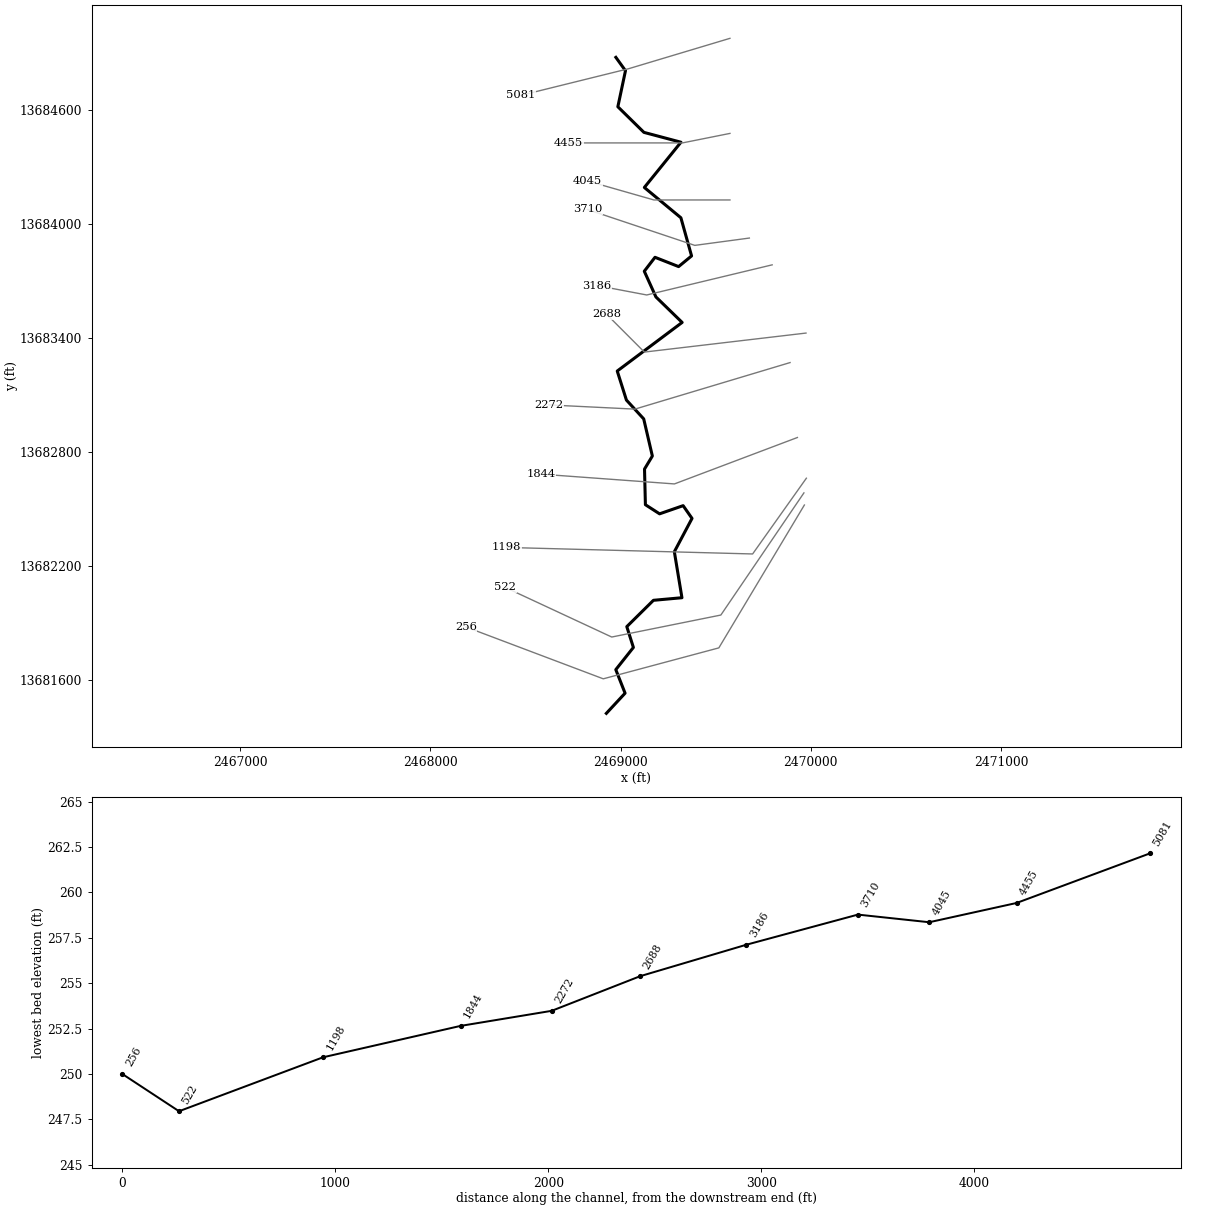
--- Stream0744.prj (project) ---

Proj Title=Stream0744 Base Level Engineering
Current Plan=p01
Default Exp/Contr=0.3,0.1
English Units
Geom File=g01
Flow File=f01
Plan File=p01
BEGIN DESCRIPTION:
Stream0744
END DESCRIPTION:

--- Stream0744.p01 (plan) ---

Plan Title=Multiple Run
Short Identifier=Multiple
Geom File=g01
Flow File=f01
Subcritical Flow
K Sum by GR= 0
Std Step Tol= 0.01
Critical Tol= 0.01
Num of Std Step Trials= 20
Max Error Tol= 0.3
Flow Tol Ratio= 0.001
Split Flow NTrial= 30
Split Flow Tol= 0.02
Split Flow Ratio= 0.02
Log Output Level= 0
Friction Slope Method= 1
Unsteady Friction Slope Method= 2
Unsteady Bridges Friction Slope Method= 1
Parabolic Critical Depth
Global Vel Dist=  1 , 1 , 1
Global Log Level= 0
CheckData=True
Encroach Param= -1, 0, 0, 0
BEGIN DESCRIPTION:
Multiple Run
END DESCRIPTION:

--- Stream0744.f01 (steady flow) ---

Flow Title=Multiple
Number of Profiles=7
Profile Names=10-year,25-year,50-year,1pct_min,100-year,1pct_plu,500-year
River Rch & RM= Stream0744,Reach-1,5081
     463     722     948     603    1203    2401    1918
Boundary for River Rch & Prof#=Stream0744,Reach-1,1
Up Type=0
Dn Type=3
Dn Slope=0.005
Boundary for River Rch & Prof#=Stream0744,Reach-1,2
Up Type=0
Dn Type=3
Dn Slope=0.005
Boundary for River Rch & Prof#=Stream0744,Reach-1,3
Up Type=0
Dn Type=3
Dn Slope=0.005
Boundary for River Rch & Prof#=Stream0744,Reach-1,4
Up Type=0
Dn Type=3
Dn Slope=0.005
Boundary for River Rch & Prof#=Stream0744,Reach-1,5
Up Type=0
Dn Type=3
Dn Slope=0.005
Boundary for River Rch & Prof#=Stream0744,Reach-1,6
Up Type=0
Dn Type=3
Dn Slope=0.005
Boundary for River Rch & Prof#=Stream0744,Reach-1,7
Up Type=0
Dn Type=3
Dn Slope=0.005

--- Stream0744.g01 (geometry) ---

Geom Title=Existing Conditions

River Reach=Stream0744,Reach-1
Reach XY= 30
      2468975.00     13684875.00      2469025.55     13684804.79
      2468985.43     13684615.21      2469122.55     13684480.47
      2469317.35     13684428.70      2469124.74     13684190.70
      2469316.98     13684031.34      2469373.11     13683830.66
      2469304.98     13683774.56      2469180.80     13683823.45
      2469124.46     13683750.14      2469185.63     13683615.00
      2469323.51     13683480.91      2468982.23     13683225.31
      2469030.53     13683072.58      2469121.44     13682973.53
      2469166.92     13682778.30      2469125.66     13682709.84
      2469130.34     13682522.26      2469204.85     13682474.31
      2469328.74     13682517.31      2469375.51     13682450.22
      2469282.56     13682275.00      2469322.49     13682033.11
      2469172.56     13682019.53      2469032.50     13681881.05
      2469067.16     13681771.60      2468974.62     13681654.87
      2469023.44     13681531.03      2468925.00     13681425.00

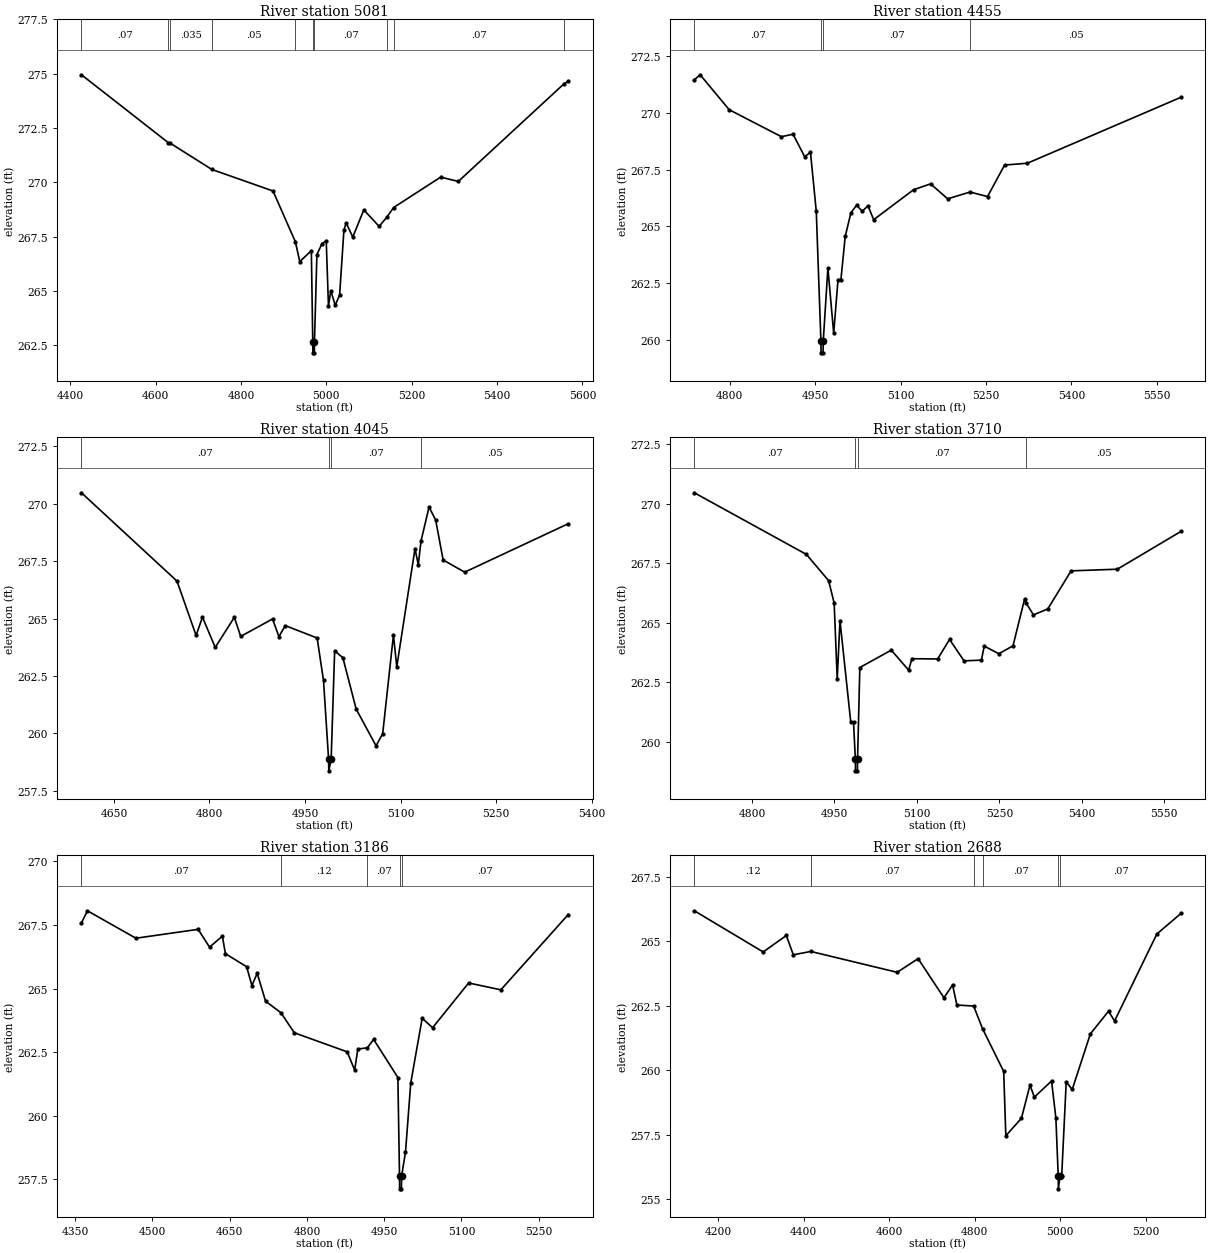
Type RM Length L Ch R = 1,5081,626,626,626
BEGIN DESCRIPTION:
Stream0744 11.0
END DESCRIPTION:
XS GIS Cut Line= 3
      2469575.03     13684975.01      2469043.16     13684815.55
      2468475.05     13684675.01
#Sta/Elev= 30
  4426.1  274.95  4629.9  271.82  4632.5  271.82  4731.8  270.59  4875.0  269.60
  4927.4  267.26  4937.7  266.35  4964.8  266.85  4968.1  262.65  4968.3  262.15
  4971.8  262.15  4972.1  262.65  4977.8  266.67  4989.8  267.18  4999.7  267.30
  5004.9  264.30  5010.4  265.01  5020.7  264.34  5031.0  264.81  5041.1  267.79
  5046.3  268.13  5061.9  267.48  5087.7  268.73  5123.7  267.97  5142.2  268.41
  5157.6  268.84  5267.9  270.24  5309.1  270.04  5557.1  274.54  5566.6  274.65
#Mann=10,-1,0
  4426.1    0.07       0  4629.9    0.05       0  4632.5   0.035       0
  4731.8    0.05       0  4927.4    0.07       0  4968.1    0.05       0
  4972.1    0.07       0  5142.2   0.035       0  5157.6    0.07       0
  5557.1    0.05       0
Bank Sta=4968.1,4972.1
Exp/Cntr=0.3,0.1

Type RM Length L Ch R = 1,4455,410,410,410
BEGIN DESCRIPTION:
Stream0744 10.0
END DESCRIPTION:
XS GIS Cut Line= 3
      2469575.01     13684475.00      2469325.00     13684425.00
      2468724.96     13684425.00
#Sta/Elev= 30
  4737.8  271.46  4748.0  271.68  4799.0  270.14  4890.8  268.95  4911.2  269.06
  4931.6  268.07  4941.8  268.26  4952.0  265.66  4960.2  259.92  4960.4  259.42
  4963.9  259.42  4964.2  259.92  4972.4  263.16  4982.6  260.28  4990.2  262.65
  4995.3  262.65  5002.8  264.55  5012.8  265.59  5022.8  265.93  5032.8  265.66
  5042.8  265.91  5052.8  265.29  5122.8  266.61  5152.8  266.87  5182.8  266.21
  5222.1  266.51  5252.8  266.31  5282.8  267.70  5322.8  267.78  5592.8  270.69
#Mann=4,-1,0
  4737.8    0.07       0  4960.2    0.05       0  4964.2    0.07       0
  5222.1    0.05       0
Bank Sta=4960.2,4964.2
Exp/Cntr=0.3,0.1

Type RM Length L Ch R = 1,4045,335,335,335
BEGIN DESCRIPTION:
Stream0744 9.0
END DESCRIPTION:
XS GIS Cut Line= 3
      2469575.05     13684125.00      2469175.00     13684125.00
      2468824.96     13684225.01
#Sta/Elev= 30
  4599.0  270.48  4749.0  266.63  4779.0  264.26  4789.0  265.06  4809.0  263.74
  4839.0  265.05  4849.0  264.22  4899.0  264.98  4909.0  264.21  4919.0  264.69
  4969.0  264.15  4979.0  262.30  4987.0  258.86  4987.3  258.36  4991.0  258.86
  4996.5  263.59  5009.4  263.29  5030.3  261.05  5061.5  259.45  5071.9  259.98
  5088.8  264.28  5094.0  262.89  5122.6  268.04  5127.8  267.34  5132.0  268.37
  5144.7  269.86  5155.1  269.29  5166.8  267.55  5200.6  267.02  5363.1  269.13
#Mann=4,-1,0
  4599.0    0.07       0  4987.0    0.05       0  4991.0    0.07       0
  5132.0    0.05       0
Bank Sta=4987,4991
Exp/Cntr=0.3,0.1

Type RM Length L Ch R = 1,3710,524,524,524
BEGIN DESCRIPTION:
Stream0744 8.0
END DESCRIPTION:
XS GIS Cut Line= 3
      2469677.04     13683924.67      2469390.08     13683886.13
      2468825.04     13684074.99
#Sta/Elev= 30
  4695.3  270.46  4899.2  267.87  4939.5  266.77  4949.6  265.83  4955.2  262.63
  4960.2  265.09  4979.8  260.83  4984.8  260.83  4988.2  259.28  4988.4  258.78
  4991.9  258.78  4992.2  259.28  4996.3  263.12  5053.5  263.85  5085.1  263.01
  5091.0  263.49  5137.8  263.48  5159.5  264.30  5185.8  263.40  5217.4  263.43
  5222.6  264.02  5249.0  263.70  5274.9  264.03  5296.0  266.00  5299.3  265.81
  5312.1  265.33  5338.1  265.58  5380.6  267.18  5464.7  267.25  5580.6  268.84
#Mann=4,-1,0
  4695.3    0.07       0  4988.2    0.05       0  4992.2    0.07       0
  5299.3    0.05       0
Bank Sta=4988.2,4992.2
Exp/Cntr=0.3,0.1

Type RM Length L Ch R = 1,3186,498,498,498
BEGIN DESCRIPTION:
Stream0744 7.0
END DESCRIPTION:
XS GIS Cut Line= 3
      2469796.94     13683783.75      2469137.38     13683625.29
      2468874.98     13683675.00
#Sta/Elev= 30
  4362.0  267.58  4373.6  268.06  4467.8  266.98  4588.6  267.33  4610.8  266.63
  4635.7  267.06  4641.7  266.37  4682.8  265.86  4693.1  265.12  4703.4  265.60
  4719.7  264.50  4749.4  264.05  4775.4  263.26  4878.2  262.51  4892.7  261.79
  4898.8  262.62  4917.4  262.67  4929.5  263.00  4976.6  261.50  4979.8  257.62
  4980.0  257.12  4983.5  257.12  4983.8  257.62  4991.4  258.56  5001.6  261.28
  5023.8  263.83  5044.1  263.46  5114.0  265.22  5176.6  264.95  5307.4  267.91
#Mann=5,-1,0
  4362.0    0.07       0  4749.4    0.12       0  4917.4    0.07       0
  4979.8    0.05       0  4983.8    0.07       0
Bank Sta=4979.8,4983.8
Exp/Cntr=0.3,0.1

Type RM Length L Ch R = 1,2688,416,416,416
BEGIN DESCRIPTION:
Stream0744 6.0
END DESCRIPTION:
XS GIS Cut Line= 3
      2469974.96     13683425.00      2469125.00     13683325.00
      2468924.98     13683525.02
#Sta/Elev= 30
  4144.5  266.19  4305.6  264.59  4359.7  265.23  4376.0  264.48  4417.0  264.61
  4619.0  263.80  4668.0  264.33  4728.5  262.81  4748.6  263.31  4758.7  262.53
  4797.9  262.49  4819.0  261.60  4868.2  259.95  4873.2  257.45  4909.7  258.13
  4929.8  259.42  4939.9  258.95  4980.2  259.58  4990.3  258.14  4995.8  255.89
  4996.1  255.39  4999.8  255.89  5003.9  255.89  5014.5  259.54  5028.6  259.25
  5071.0  261.41  5113.5  262.29  5127.6  261.91  5226.6  265.29  5283.2  266.09
#Mann=6,-1,0
  4144.5    0.12       0  4417.0    0.07       0  4797.9    0.12       0
  4819.0    0.07       0  4995.8    0.05       0  4999.8    0.07       0
Bank Sta=4995.8,4999.8
Exp/Cntr=0.3,0.1

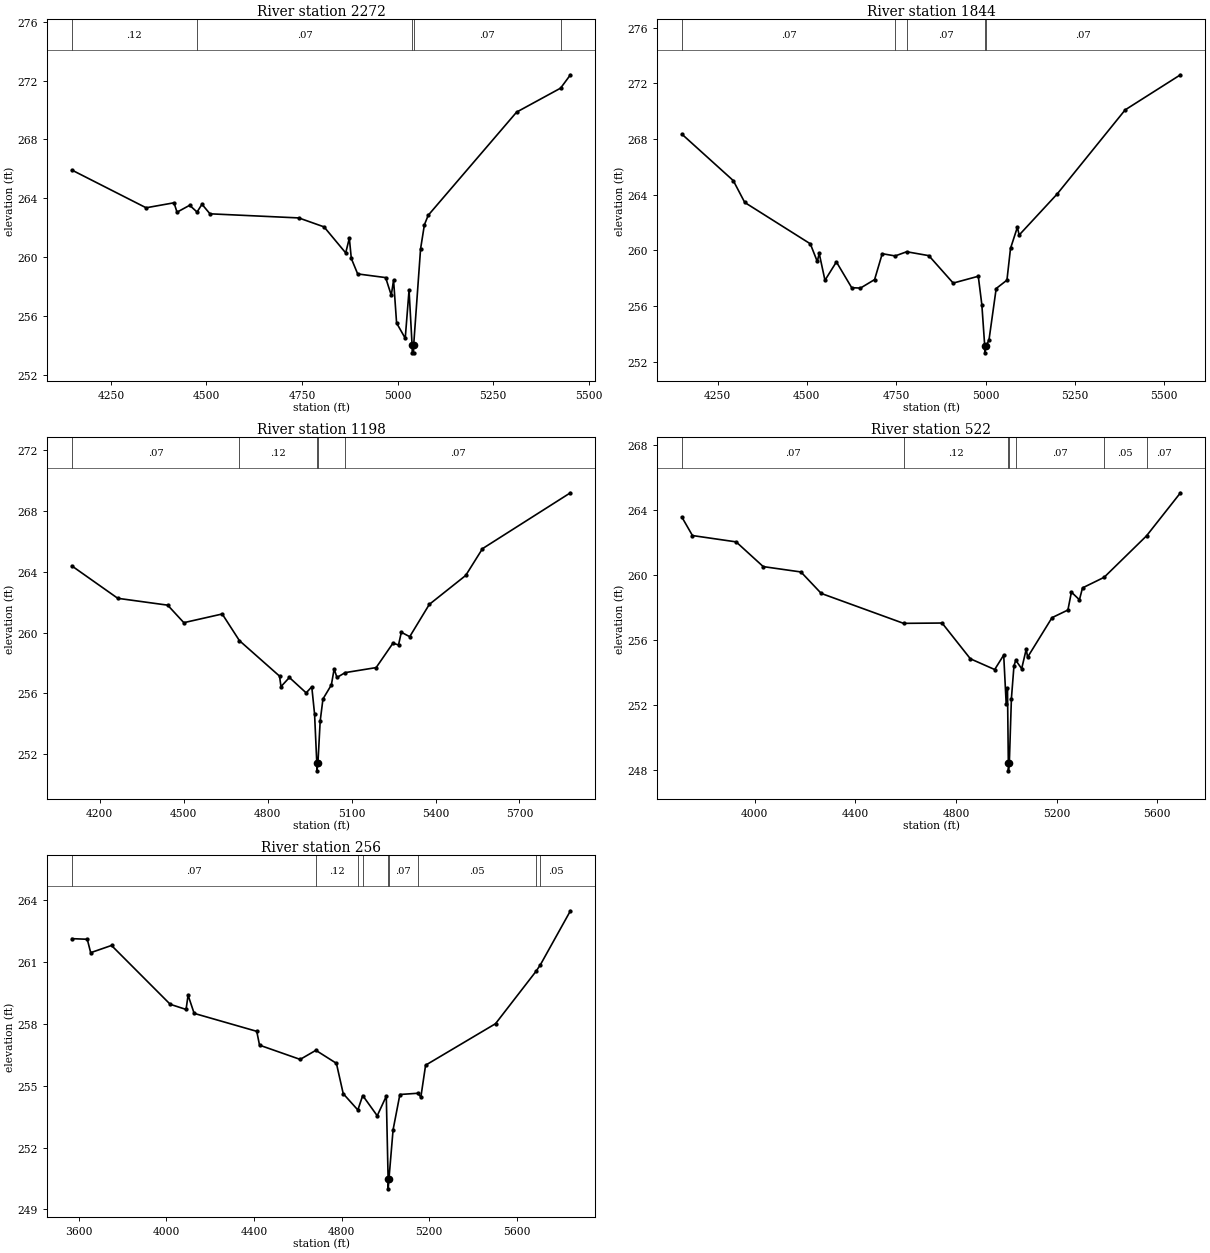
Type RM Length L Ch R = 1,2272,428,428,428
BEGIN DESCRIPTION:
Stream0744 5.0
END DESCRIPTION:
XS GIS Cut Line= 3
      2469891.17     13683269.79      2469075.00     13683025.00
      2468623.43     13683047.07
#Sta/Elev= 30
  4147.9  265.92  4342.3  263.35  4415.3  263.69  4423.1  263.05  4456.2  263.52
  4475.5  263.06  4488.4  263.59  4509.3  262.94  4741.6  262.66  4807.7  262.05
  4864.3  260.28  4873.8  261.28  4879.0  259.90  4895.6  258.85  4968.7  258.60
  4983.5  257.40  4989.5  258.43  4997.4  255.51  5020.0  254.47  5030.0  257.75
  5038.0  253.98  5038.3  253.48  5041.8  253.48  5042.0  253.98  5060.1  260.55
  5070.1  262.19  5080.1  262.84  5311.3  269.86  5426.3  271.49  5452.1  272.40
#Mann=5,-1,0
  4147.9    0.12       0  4475.5    0.07       0  5038.0    0.05       0
  5042.0    0.07       0  5426.3    0.05       0
Bank Sta=5038,5042
Exp/Cntr=0.3,0.1

Type RM Length L Ch R = 1,1844,646,646,646
BEGIN DESCRIPTION:
XS7628
END DESCRIPTION:
XS GIS Cut Line= 3
      2469929.74     13682875.75      2469283.01     13682631.62
      2468580.57     13682683.02
#Sta/Elev= 30
  4150.1  268.36  4294.1  265.02  4326.2  263.45  4509.7  260.48  4529.2  259.21
  4534.6  259.79  4550.7  257.86  4582.7  259.18  4625.5  257.33  4650.0  257.30
  4689.6  257.91  4711.0  259.77  4747.2  259.61  4779.5  259.91  4841.4  259.63
  4909.6  257.66  4979.8  258.15  4989.8  256.10  4997.8  253.15  4998.1  252.65
  5001.8  253.15  5009.8  253.58  5029.9  257.27  5060.0  257.87  5070.0  260.15
  5089.2  261.67  5094.2  261.11  5200.3  264.05  5390.9  270.10  5545.7  272.62
#Mann=5,-1,0
  4150.1    0.07       0  4747.2    0.12       0  4779.5    0.07       0
  4997.8    0.05       0  5001.8    0.07       0
Bank Sta=4997.8,5001.8
Exp/Cntr=0.3,0.1

Type RM Length L Ch R = 1,1198,676,676,676
BEGIN DESCRIPTION:
XS7627
END DESCRIPTION:
XS GIS Cut Line= 3
      2469976.88     13682661.62      2469694.18     13682263.27
      2468400.70     13682297.54
#Sta/Elev= 30
  4099.9  264.38  4264.3  262.25  4442.7  261.80  4500.4  260.65  4637.6  261.22
  4699.1  259.47  4842.5  257.14  4847.6  256.45  4877.7  257.05  4937.7  256.04
  4957.7  256.44  4967.7  254.65  4975.7  251.42  4975.9  250.92  4979.7  251.42
  4987.7  254.18  4997.7  255.64  5027.7  256.56  5037.7  257.61  5047.7  257.05
  5077.1  257.37  5187.8  257.70  5247.8  259.30  5267.8  259.19  5277.8  260.02
  5307.8  259.73  5377.8  261.85  5507.9  263.75  5567.9  265.51  5882.3  269.18
#Mann=5,-1,0
  4099.9    0.07       0  4699.1    0.12       0  4975.7    0.05       0
  4979.7    0.12       0  5077.1    0.07       0
Bank Sta=4975.7,4979.7
Exp/Cntr=0.3,0.1

Type RM Length L Ch R = 1,522,266,266,266
BEGIN DESCRIPTION:
XS7626
END DESCRIPTION:
XS GIS Cut Line= 4
      2469964.00     13682584.48      2469527.14     13681942.04
      2468953.21     13681826.40      2468392.12     13682087.67
#Sta/Elev= 30
  3711.0  263.56  3753.2  262.42  3926.8  262.03  4034.5  260.51  4184.3  260.18
  4265.0  258.86  4592.0  257.02  4745.1  257.04  4857.5  254.84  4954.1  254.18
  4989.9  255.07  4999.8  252.07  5004.9  253.06  5008.3  248.45  5008.6  247.95
  5012.3  248.45  5020.5  252.39  5030.7  254.41  5037.8  254.75  5061.3  254.23
  5079.4  255.43  5084.9  254.94  5181.9  257.37  5245.0  257.84  5258.9  258.94
  5290.8  258.47  5303.0  259.20  5388.8  259.85  5557.3  262.40  5692.3  265.05
#Mann=7,-1,0
  3711.0    0.07       0  4592.0    0.12       0  5008.3    0.05       0
  5012.3    0.12       0  5037.8    0.07       0  5388.8    0.05       0
  5557.3    0.07       0
Bank Sta=5008.3,5012.3
Exp/Cntr=0.3,0.1

Type RM Length L Ch R = 1,256,0,0,0
BEGIN DESCRIPTION:
E21307
END DESCRIPTION:
XS GIS Cut Line= 4
      2469966.36     13682520.65      2469516.53     13681769.35
      2468908.76     13681606.64      2468186.08     13681879.43
#Sta/Elev= 30
  3567.9  262.12  3638.6  262.09  3654.2  261.44  3749.3  261.79  4017.4  258.94
  4089.8  258.69  4099.0  259.38  4126.7  258.50  4412.6  257.63  4425.3  256.96
  4610.8  256.27  4682.6  256.71  4776.4  256.08  4807.5  254.61  4874.3  253.82
  4896.5  254.52  4962.8  253.54  5004.2  254.49  5012.5  250.50  5012.8  250.00
  5016.5  250.50  5035.2  252.86  5066.3  254.57  5147.8  254.63  5162.1  254.45
  5183.7  255.99  5503.0  258.00  5688.2  260.54  5707.7  260.85  5845.2  263.47
#Mann=9,-1,0
  3567.9    0.07       0  4682.6    0.12       0  4874.3     0.1       0
  4896.5    0.07       0  5012.5    0.05       0  5016.5    0.07       0
  5147.8    0.05       0  5688.2    0.07       0  5707.7    0.05       0
Bank Sta=5012.5,5016.5
Exp/Cntr=0.3,0.1

Chan Stop Cuts=-1