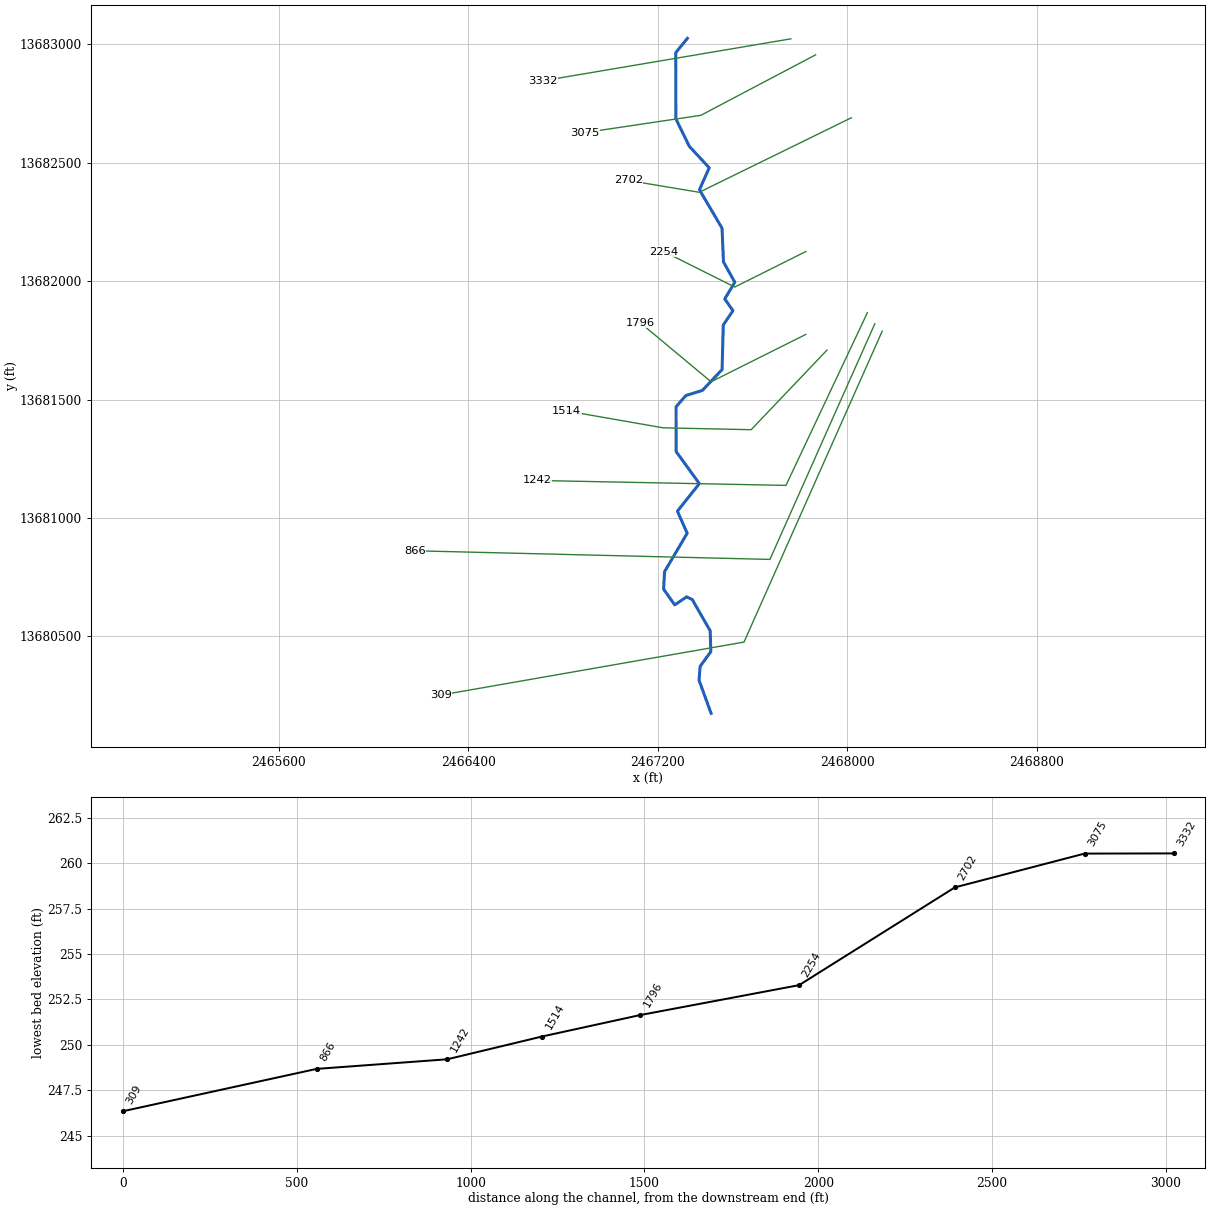
--- Stream0745.prj (project) ---

Proj Title=Stream0745 Base Level Engineering
Current Plan=p01
Default Exp/Contr=0.3,0.1
English Units
Geom File=g01
Flow File=f01
Plan File=p01
BEGIN DESCRIPTION:
Stream0745
END DESCRIPTION:

--- Stream0745.p01 (plan) ---

Plan Title=Multiple Run
Short Identifier=Multiple
Geom File=g01
Flow File=f01
Subcritical Flow
K Sum by GR= 0
Std Step Tol= 0.01
Critical Tol= 0.01
Num of Std Step Trials= 20
Max Error Tol= 0.3
Flow Tol Ratio= 0.001
Split Flow NTrial= 30
Split Flow Tol= 0.02
Split Flow Ratio= 0.02
Log Output Level= 0
Friction Slope Method= 1
Unsteady Friction Slope Method= 2
Unsteady Bridges Friction Slope Method= 1
Parabolic Critical Depth
Global Vel Dist=  1 , 1 , 1
Global Log Level= 0
CheckData=True
Encroach Param= -1, 0, 0, 0
BEGIN DESCRIPTION:
Multiple Run
END DESCRIPTION:

--- Stream0745.f01 (steady flow) ---

Flow Title=Multiple
Number of Profiles=7
Profile Names=10-year,25-year,50-year,1pct_min,100-year,1pct_plu,500-year
River Rch & RM= Stream0745,Reach-1,3332
     307     469     609     384     766    1527    1195
Boundary for River Rch & Prof#=Stream0745,Reach-1,1
Up Type=0
Dn Type=3
Dn Slope=0.005
Boundary for River Rch & Prof#=Stream0745,Reach-1,2
Up Type=0
Dn Type=3
Dn Slope=0.005
Boundary for River Rch & Prof#=Stream0745,Reach-1,3
Up Type=0
Dn Type=3
Dn Slope=0.005
Boundary for River Rch & Prof#=Stream0745,Reach-1,4
Up Type=0
Dn Type=3
Dn Slope=0.005
Boundary for River Rch & Prof#=Stream0745,Reach-1,5
Up Type=0
Dn Type=3
Dn Slope=0.005
Boundary for River Rch & Prof#=Stream0745,Reach-1,6
Up Type=0
Dn Type=3
Dn Slope=0.005
Boundary for River Rch & Prof#=Stream0745,Reach-1,7
Up Type=0
Dn Type=3
Dn Slope=0.005

--- Stream0745.g01 (geometry) ---

Geom Title=Existing Conditions

River Reach=Stream0745,Reach-1
Reach XY= 30
      2467325.00     13683025.00      2467275.96     13682964.60
      2467276.20     13682685.50      2467333.18     13682568.94
      2467417.17     13682478.40      2467375.80     13682385.70
      2467471.24     13682223.44      2467477.30     13682080.93
      2467525.18     13681995.13      2467482.83     13681924.92
      2467517.21     13681875.10      2467476.38     13681814.57
      2467471.47     13681626.45      2467388.23     13681538.62
      2467318.62     13681516.98      2467276.98     13681469.33
      2467277.07     13681280.86      2467375.46     13681145.16
      2467282.84     13681028.40      2467324.20     13680935.70
      2467228.67     13680773.41      2467224.50     13680699.78
      2467271.39     13680632.89      2467321.83     13680666.91
      2467345.39     13680655.79      2467421.33     13680523.42
      2467423.89     13680435.55      2467378.71     13680373.40
      2467374.21     13680314.95      2467425.00     13680175.00

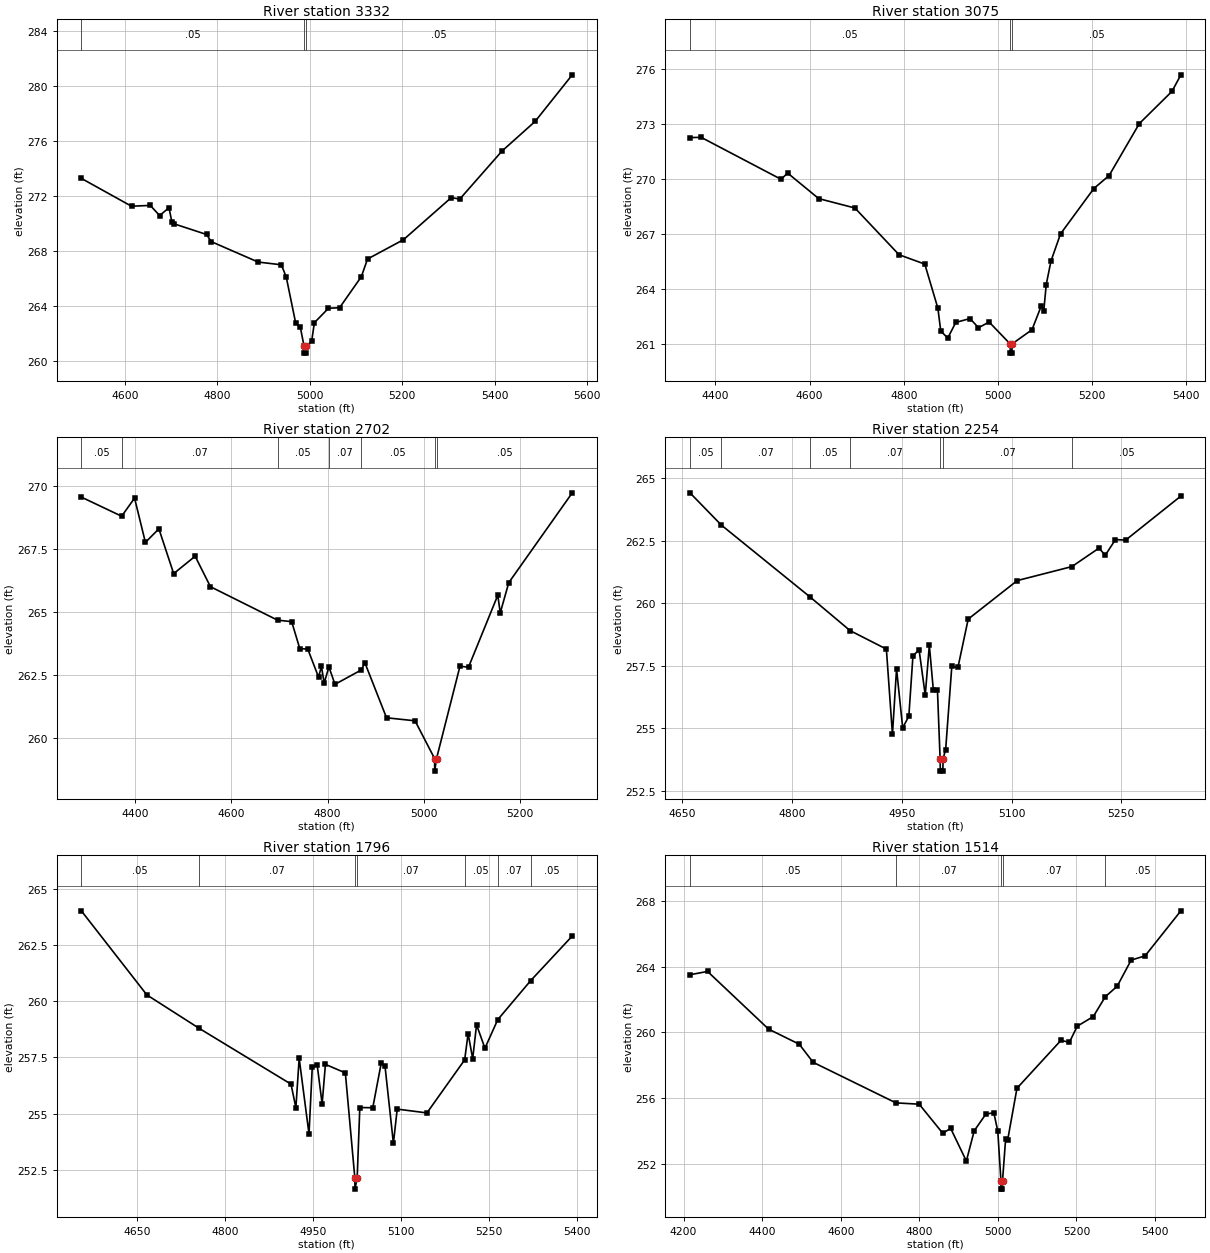
Type RM Length L Ch R = 1,3332,257,257,257
BEGIN DESCRIPTION:
XS7631
END DESCRIPTION:
XS GIS Cut Line= 2
      2467761.97     13683022.92      2466715.14     13682845.84
#Sta/Elev= 30
  4505.7  273.28  4614.2  271.25  4654.8  271.31  4675.0  270.57  4695.3  271.14
  4701.7  270.07  4706.8  269.96  4776.5  269.19  4786.6  268.67  4888.0  267.18
  4938.3  266.98  4948.9  266.08  4969.2  262.74  4979.3  262.43  4987.4  261.04
  4987.7  260.54  4991.2  260.54  4991.4  261.04  5003.8  261.40  5009.7  262.76
  5040.2  263.81  5064.2  263.85  5111.2  266.11  5124.6  267.40  5202.4  268.81
  5305.8  271.88  5324.1  271.77  5415.4  275.27  5487.0  277.43  5567.4  280.83
#Mann=3,-1,0
  4505.7    0.05       0  4987.4    0.05       0  4991.4    0.05       0
Bank Sta=4987.4,4991.4
Exp/Cntr=0.3,0.1

Type RM Length L Ch R = 1,3075,373,373,373
BEGIN DESCRIPTION:
Stream0745 5.0
END DESCRIPTION:
XS GIS Cut Line= 3
      2467866.18     13682955.23      2467381.77     13682700.00
      2466892.21     13682627.09
#Sta/Elev= 30
  4346.0  272.25  4369.9  272.26  4539.5  269.98  4553.4  270.32  4619.5  268.93
  4696.3  268.42  4790.0  265.88  4844.7  265.37  4872.5  262.97  4878.6  261.73
  4893.5  261.35  4910.5  262.20  4940.8  262.41  4958.7  261.91  4981.3  262.22
  5026.0  261.03  5026.3  260.53  5029.8  260.53  5030.0  261.03  5072.3  261.80
  5092.3  263.11  5097.4  262.84  5102.6  264.26  5112.7  265.54  5132.9  267.01
  5203.7  269.48  5236.0  270.18  5300.3  273.01  5369.6  274.76  5388.5  275.66
#Mann=3,-1,0
  4346.0    0.05       0  5026.0    0.05       0  5030.0    0.05       0
Bank Sta=5026,5030
Exp/Cntr=0.3,0.1

Type RM Length L Ch R = 1,2702,448,448,448
BEGIN DESCRIPTION:
Stream0745 4.0
END DESCRIPTION:
XS GIS Cut Line= 3
      2468017.18     13682689.58      2467375.00     13682375.00
      2467075.03     13682424.99
#Sta/Elev= 30
  4288.7  269.56  4372.4  268.80  4399.2  269.52  4421.7  267.76  4449.7  268.30
  4480.4  266.52  4525.0  267.21  4556.7  266.00  4696.0  264.67  4725.4  264.61
  4742.2  263.54  4758.8  263.52  4781.1  262.41  4787.2  262.83  4792.8  262.17
  4802.7  262.81  4815.3  262.12  4869.9  262.69  4877.3  262.98  4922.3  260.79
  4981.5  260.67  5022.1  259.17  5022.3  258.67  5026.1  259.17  5074.8  262.84
  5092.5  262.80  5153.3  265.66  5158.4  264.96  5176.1  266.16  5307.9  269.73
#Mann=7,-1,0
  4288.7    0.05       0  4372.4    0.07       0  4696.0    0.05       0
  4802.7    0.07       0  4869.9    0.05       0  5022.1    0.05       0
  5026.1    0.05       0
Bank Sta=5022.1,5026.1
Exp/Cntr=0.3,0.1

Type RM Length L Ch R = 1,2254,458,458,458
BEGIN DESCRIPTION:
Stream0745 3.0
END DESCRIPTION:
XS GIS Cut Line= 3
      2467825.02     13682125.01      2467525.00     13681975.00
      2467225.04     13682124.98
#Sta/Elev= 30
  4660.6  264.42  4703.5  263.13  4824.5  260.26  4879.4  258.91  4929.0  258.17
  4937.3  254.76  4942.9  257.38  4951.3  255.02  4959.7  255.49  4965.3  257.90
  4973.7  258.14  4982.1  256.33  4987.7  258.32  4993.2  256.52  4998.8  256.52
  5002.4  253.79  5002.7  253.29  5006.2  253.29  5006.4  253.79  5010.0  254.15
  5018.4  257.48  5026.8  257.44  5040.8  259.37  5107.8  260.91  5182.5  261.47
  5219.6  262.21  5228.0  261.92  5242.0  262.55  5256.0  262.53  5331.4  264.29
#Mann=7,-1,0
  4660.6    0.05       0  4703.5    0.07       0  4824.5    0.05       0
  4879.4    0.07       0  5002.4    0.05       0  5006.4    0.07       0
  5182.5    0.05       0
Bank Sta=5002.4,5006.4
Exp/Cntr=0.3,0.1

Type RM Length L Ch R = 1,1796,282,282,282
BEGIN DESCRIPTION:
Stream0745 2.0
END DESCRIPTION:
XS GIS Cut Line= 3
      2467824.99     13681775.00      2467425.00     13681575.00
      2467125.01     13681824.99
#Sta/Elev= 30
  4554.4  264.02  4666.2  260.28  4755.6  258.79  4912.2  256.31  4920.5  255.26
  4926.1  257.46  4942.9  254.09  4948.5  257.09  4956.9  257.15  4965.3  255.43
  4970.9  257.19  5004.9  256.81  5021.1  252.14  5021.3  251.64  5025.1  252.14
  5029.6  255.27  5051.7  255.26  5066.0  257.23  5072.5  257.13  5086.9  253.68
  5093.4  255.20  5144.1  255.03  5208.5  257.39  5214.4  258.56  5222.2  257.44
  5228.8  258.95  5243.1  257.91  5265.0  259.18  5321.0  260.91  5392.1  262.90
#Mann=7,-1,0
  4554.4    0.05       0  4755.6    0.07       0  5021.1    0.05       0
  5025.1    0.07       0  5208.5    0.05       0  5265.0    0.07       0
  5321.0    0.05       0
Bank Sta=5021.1,5025.1
Exp/Cntr=0.3,0.1

Type RM Length L Ch R = 1,1514,272,272,272
BEGIN DESCRIPTION:
E21308
END DESCRIPTION:
XS GIS Cut Line= 4
      2467914.39     13681708.74      2467594.14     13681372.68
      2467222.53     13681380.59      2466815.31     13681451.75
#Sta/Elev= 30
  4216.4  263.51  4261.2  263.71  4416.5  260.20  4494.6  259.28  4529.8  258.18
  4740.5  255.71  4799.8  255.63  4859.8  253.86  4879.8  254.16  4919.8  252.17
  4939.8  254.01  4969.8  255.04  4989.8  255.10  4999.8  253.99  5007.8  250.96
  5008.1  250.46  5011.6  250.46  5011.8  250.96  5019.7  253.50  5024.7  253.42
  5048.6  256.60  5160.7  259.52  5181.8  259.39  5202.1  260.38  5242.7  260.96
  5273.4  262.17  5303.6  262.81  5339.2  264.40  5374.7  264.66  5465.7  267.40
#Mann=5,-1,0
  4216.4    0.05       0  4740.5    0.07       0  5007.8    0.05       0
  5011.8    0.07       0  5273.4    0.05       0
Bank Sta=5007.8,5011.8
Exp/Cntr=0.3,0.1

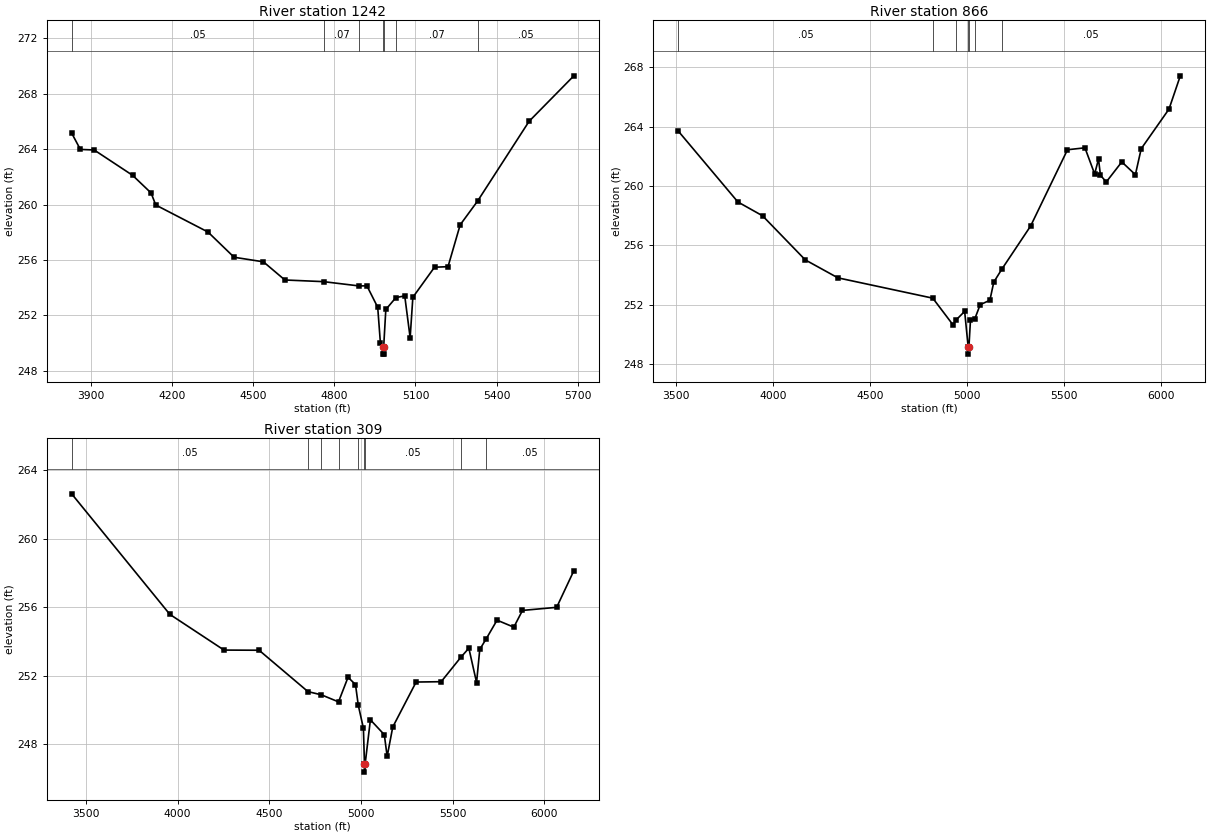
Type RM Length L Ch R = 1,1242,376,376,376
BEGIN DESCRIPTION:
XS7630
END DESCRIPTION:
XS GIS Cut Line= 3
      2468084.89     13681866.65      2467741.15     13681137.50
      2466689.57     13681158.32
#Sta/Elev= 30
  3828.1  265.16  3860.3  263.98  3911.4  263.94  4053.6  262.11  4121.9  260.84
  4139.2  259.97  4332.5  258.02  4429.1  256.20  4537.5  255.87  4616.9  254.56
  4759.9  254.44  4891.7  254.13  4920.4  254.14  4960.4  252.59  4970.4  250.00
  4978.4  249.71  4978.7  249.21  4982.2  249.21  4982.4  249.71  4990.4  252.43
  5027.7  253.29  5060.4  253.41  5080.4  250.40  5090.4  253.31  5170.5  255.48
  5220.5  255.52  5265.5  258.54  5329.8  260.25  5520.5  266.01  5686.0  269.29
#Mann=7,-1,0
  3828.1    0.05       0  4759.9    0.07       0  4891.7    0.12       0
  4978.4    0.05       0  4982.4    0.12       0  5027.7    0.07       0
  5329.8    0.05       0
Bank Sta=4978.4,4982.4
Exp/Cntr=0.3,0.1

Type RM Length L Ch R = 1,866,557,557,557
BEGIN DESCRIPTION:
XS7629
END DESCRIPTION:
XS GIS Cut Line= 3
      2468116.15     13681819.80      2467673.44     13680825.00
      2466173.44     13680861.46
#Sta/Elev= 30
  3510.7  263.72  3819.0  258.93  3946.1  258.00  4166.3  255.03  4334.4  253.82
  4823.8  252.45  4928.1  250.65  4942.3  250.96  4988.1  251.56  5006.1  249.18
  5006.4  248.68  5010.1  249.18  5018.1  250.97  5040.8  251.07  5068.1  252.01
  5118.2  252.31  5138.2  253.53  5179.6  254.40  5328.2  257.31  5518.3  262.45
  5608.3  262.58  5658.3  260.82  5678.3  261.82  5688.3  260.73  5718.3  260.28
  5798.4  261.63  5868.4  260.77  5898.4  262.52  6041.7  265.19  6100.0  267.43
#Mann=7,-1,0
  3510.7    0.05       0  4823.8    0.07       0  4942.3    0.12       0
  5006.1    0.05       0  5010.1    0.12       0  5040.8    0.07       0
  5179.6    0.05       0
Bank Sta=5006.1,5010.1
Exp/Cntr=0.3,0.1

Type RM Length L Ch R = 1,309,0,0,0
BEGIN DESCRIPTION:
Stream0745 1.0
END DESCRIPTION:
XS GIS Cut Line= 3
      2468147.40     13681788.56      2467564.06     13680476.04
      2466282.80     13680252.08
#Sta/Elev= 30
  3423.0  262.63  3958.0  255.58  4253.4  253.49  4444.6  253.48  4710.9  251.06
  4784.6  250.87  4877.4  250.46  4929.4  251.90  4970.0  251.47  4985.2  250.26
  5013.1  248.92  5018.8  246.85  5019.0  246.35  5022.8  246.85  5051.2  249.41
  5127.0  248.54  5142.6  247.27  5173.1  248.99  5300.4  251.62  5437.0  251.64
  5543.5  253.06  5587.8  253.60  5629.9  251.59  5647.3  253.53  5680.9  254.12
  5741.5  255.24  5832.9  254.83  5880.1  255.81  6066.4  255.99  6160.0  258.13
#Mann=9,-1,0
  3423.0    0.05       0  4710.9    0.07       0  4784.6    0.05       0
  4877.4    0.12       0  4985.2    0.05       0  5018.8    0.05       0
  5022.8    0.05       0  5543.5    0.07       0  5680.9    0.05       0
Bank Sta=5018.8,5022.8
Exp/Cntr=0.3,0.1

Chan Stop Cuts=-1