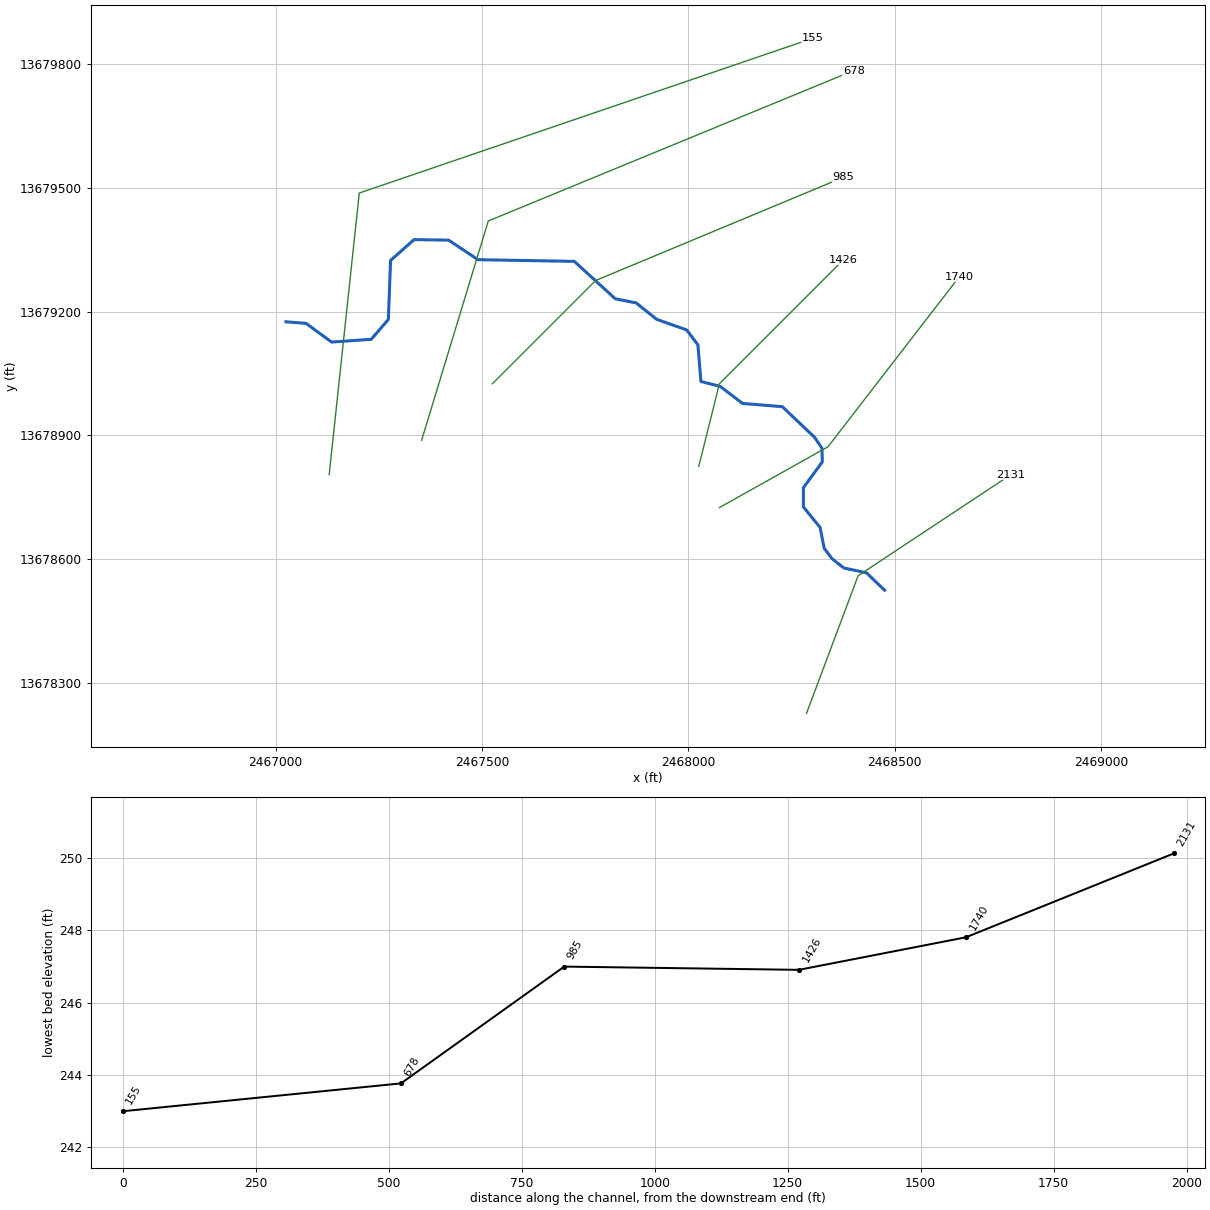
--- Stream0746.prj (project) ---

Proj Title=Stream0746 Base Level Engineering
Current Plan=p01
Default Exp/Contr=0.3,0.1
English Units
Geom File=g01
Flow File=f01
Plan File=p01
BEGIN DESCRIPTION:
Stream0746
END DESCRIPTION:

--- Stream0746.p01 (plan) ---

Plan Title=Multiple Run
Short Identifier=Multiple
Geom File=g01
Flow File=f01
Subcritical Flow
K Sum by GR= 0
Std Step Tol= 0.01
Critical Tol= 0.01
Num of Std Step Trials= 20
Max Error Tol= 0.3
Flow Tol Ratio= 0.001
Split Flow NTrial= 30
Split Flow Tol= 0.02
Split Flow Ratio= 0.02
Log Output Level= 0
Friction Slope Method= 1
Unsteady Friction Slope Method= 2
Unsteady Bridges Friction Slope Method= 1
Parabolic Critical Depth
Global Vel Dist=  1 , 1 , 1
Global Log Level= 0
CheckData=True
Encroach Param= -1, 0, 0, 0
BEGIN DESCRIPTION:
Multiple Run
END DESCRIPTION:

--- Stream0746.f01 (steady flow) ---

Flow Title=Multiple
Number of Profiles=7
Profile Names=10-year,25-year,50-year,1pct_min,100-year,1pct_plu,500-year
River Rch & RM= Stream0746,Reach-1,2131
     569     899    1192     765    1525    3044    2474
Boundary for River Rch & Prof#=Stream0746,Reach-1,1
Up Type=0
Dn Type=3
Dn Slope=0.005
Boundary for River Rch & Prof#=Stream0746,Reach-1,2
Up Type=0
Dn Type=3
Dn Slope=0.005
Boundary for River Rch & Prof#=Stream0746,Reach-1,3
Up Type=0
Dn Type=3
Dn Slope=0.005
Boundary for River Rch & Prof#=Stream0746,Reach-1,4
Up Type=0
Dn Type=3
Dn Slope=0.005
Boundary for River Rch & Prof#=Stream0746,Reach-1,5
Up Type=0
Dn Type=3
Dn Slope=0.005
Boundary for River Rch & Prof#=Stream0746,Reach-1,6
Up Type=0
Dn Type=3
Dn Slope=0.005
Boundary for River Rch & Prof#=Stream0746,Reach-1,7
Up Type=0
Dn Type=3
Dn Slope=0.005

--- Stream0746.g01 (geometry) ---

Geom Title=Existing Conditions

River Reach=Stream0746,Reach-1
Reach XY= 30
      2468475.00     13678525.00      2468431.11     13678567.05
      2468376.34     13678578.71      2468347.83     13678601.14
      2468328.85     13678626.42      2468318.81     13678677.16
      2468278.34     13678726.72      2468278.40     13678773.28
      2468324.26     13678835.71      2468323.38     13678868.97
      2468305.59     13678895.13      2468227.44     13678969.48
      2468130.94     13678977.32      2468076.78     13679018.70
      2468030.25     13679030.44      2468022.89     13679119.20
      2467995.57     13679155.41      2467922.84     13679181.11
      2467873.27     13679220.81      2467822.71     13679230.85
      2467723.53     13679321.45      2467490.22     13679325.52
      2467419.02     13679372.84      2467335.31     13679374.14
      2467278.44     13679323.78      2467273.02     13679180.65
      2467231.50     13679132.62      2467135.52     13679125.99
      2467073.49     13679171.35      2467025.00     13679175.00

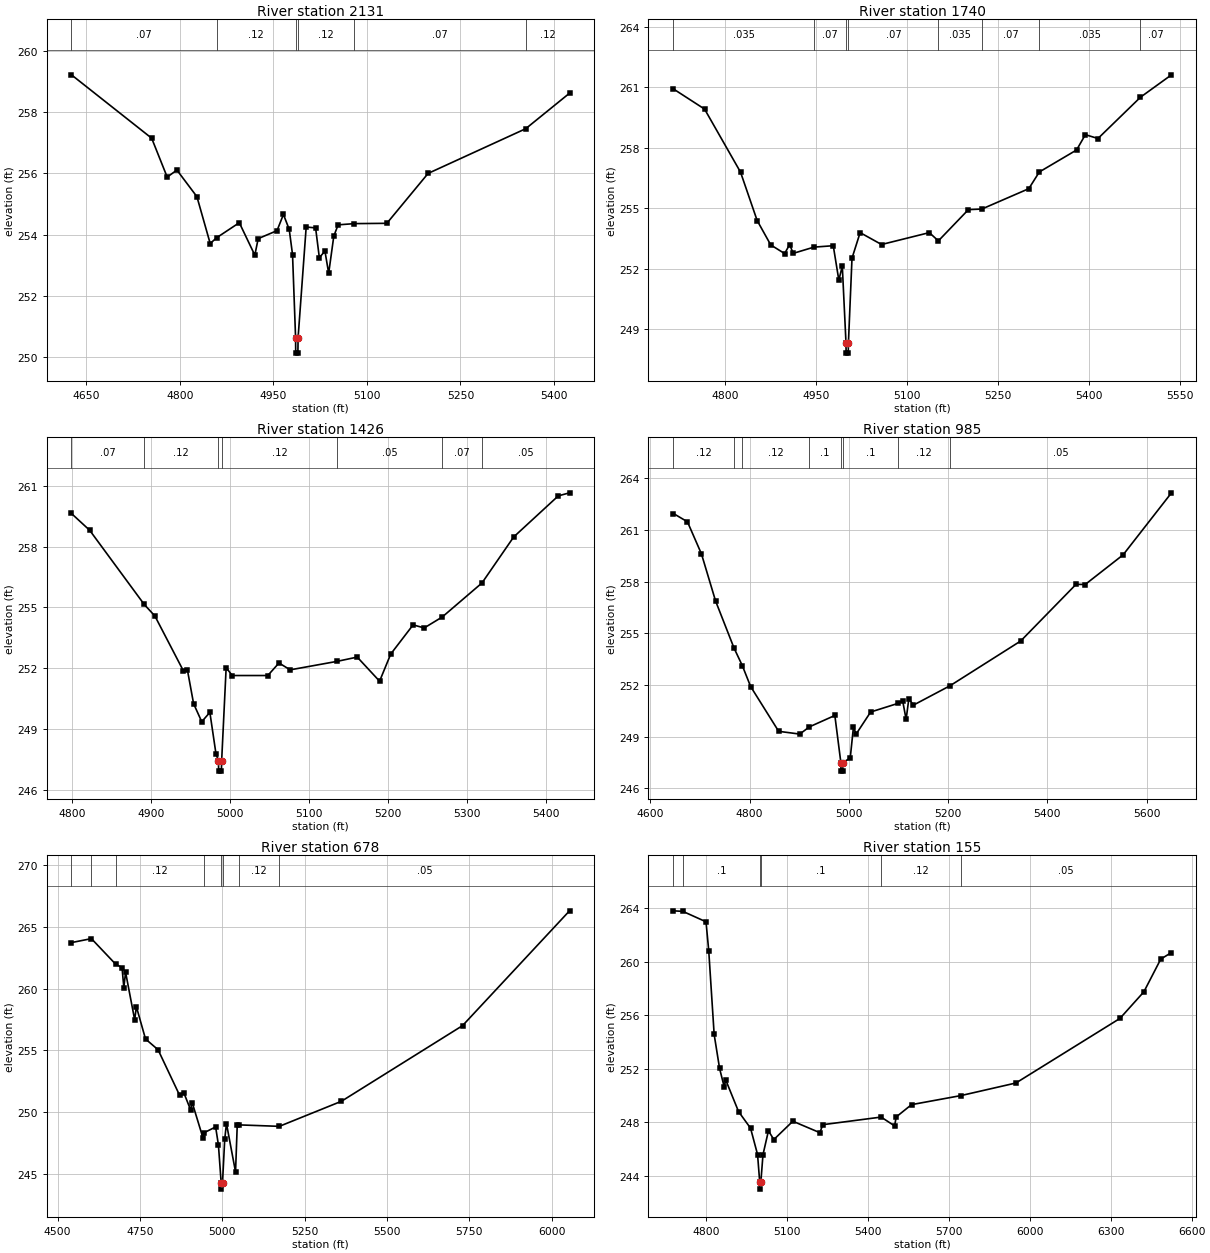
Type RM Length L Ch R = 1,2131,391,391,391
BEGIN DESCRIPTION:
XS7632
END DESCRIPTION:
XS GIS Cut Line= 3
      2468285.93     13678226.54      2468410.94     13678559.90
      2468780.40     13678804.47
#Sta/Elev= 30
  4625.9  259.22  4754.6  257.15  4779.5  255.88  4795.1  256.11  4827.2  255.24
  4848.5  253.71  4858.9  253.90  4895.2  254.39  4920.1  253.33  4925.5  253.87
  4955.7  254.13  4966.0  254.66  4975.3  254.17  4980.6  253.35  4985.5  250.63
  4985.7  250.13  4989.2  250.13  4989.5  250.63  5002.5  254.25  5017.6  254.22
  5023.6  253.25  5032.6  253.46  5038.6  252.74  5046.8  253.95  5053.7  254.32
  5080.0  254.36  5131.9  254.37  5198.1  256.00  5354.7  257.46  5425.0  258.62
#Mann=6,-1,0
  4625.9    0.07       0  4858.9    0.12       0  4985.5    0.05       0
  4989.5    0.12       0  5080.0    0.07       0  5354.7    0.12       0
Bank Sta=4985.5,4989.5
Exp/Cntr=0.3,0.1

Type RM Length L Ch R = 1,1740,314,314,314
BEGIN DESCRIPTION:
Stream0746 3.0
END DESCRIPTION:
XS GIS Cut Line= 3
      2468075.01     13678725.00      2468338.02     13678872.40
      2468655.70     13679283.82
#Sta/Elev= 30
  4714.2  260.92  4765.6  259.92  4824.9  256.79  4852.3  254.39  4874.7  253.18
  4897.6  252.75  4905.9  253.20  4911.7  252.76  4945.9  253.07  4977.8  253.14
  4987.0  251.43  4992.7  252.13  4998.8  248.31  4999.0  247.81  5002.5  247.81
  5002.8  248.31  5008.7  252.52  5022.1  253.79  5057.4  253.20  5136.2  253.79
  5151.1  253.38  5200.6  254.93  5222.8  254.96  5300.2  255.97  5317.6  256.80
  5379.0  257.89  5393.5  258.65  5414.3  258.46  5484.4  260.51  5535.5  261.62
#Mann=8,-1,0
  4714.2   0.035       0  4945.9    0.07       0  4998.8    0.05       0
  5002.8    0.07       0  5151.1   0.035       0  5222.8    0.07       0
  5317.6   0.035       0  5484.4    0.07       0
Bank Sta=4998.8,5002.8
Exp/Cntr=0.3,0.1

Type RM Length L Ch R = 1,1426,441,441,441
BEGIN DESCRIPTION:
Stream0746 2.0
END DESCRIPTION:
XS GIS Cut Line= 3
      2468025.01     13678825.04      2468075.00     13679025.00
      2468375.02     13679325.02
#Sta/Elev= 30
  4798.9  259.63  4822.0  258.80  4891.0  255.14  4904.5  254.57  4940.6  251.86
  4945.7  251.90  4953.5  250.24  4963.8  249.35  4974.1  249.81  4981.8  247.77
  4985.0  247.41  4985.2  246.91  4988.7  246.91  4989.0  247.41  4994.7  252.02
  5002.4  251.63  5047.4  251.63  5061.6  252.25  5075.7  251.91  5135.2  252.33
  5160.6  252.54  5188.9  251.35  5203.0  252.69  5231.3  254.13  5245.4  253.98
  5268.2  254.52  5318.5  256.20  5358.6  258.47  5415.1  260.50  5429.3  260.65
#Mann=7,-1,0
  4798.9    0.07       0  4891.0    0.12       0  4985.0    0.05       0
  4989.0    0.12       0  5135.2    0.05       0  5268.2    0.07       0
  5318.5    0.05       0
Bank Sta=4985,4989
Exp/Cntr=0.3,0.1

Type RM Length L Ch R = 1,985,307,307,307
BEGIN DESCRIPTION:
Stream0746 1.0
END DESCRIPTION:
XS GIS Cut Line= 3
      2467524.99     13679024.99      2467775.00     13679275.00
      2468375.03     13679525.01
#Sta/Elev= 30
  4646.4  261.95  4674.7  261.47  4703.0  259.60  4731.3  256.88  4768.6  254.14
  4785.3  253.12  4802.0  251.91  4858.5  249.31  4901.0  249.15  4920.5  249.57
  4971.7  250.23  4983.8  247.50  4984.1  247.00  4987.6  247.00  4987.8  247.50
  5002.7  247.76  5009.2  249.56  5014.6  249.15  5043.8  250.43  5098.8  250.93
  5108.3  251.09  5115.3  250.00  5120.8  251.20  5130.0  250.83  5204.1  251.96
  5346.1  254.55  5457.7  257.84  5476.1  257.83  5552.5  259.55  5650.0  263.15
#Mann=8,-1,0
  4646.4    0.12       0  4768.6    0.07       0  4785.3    0.12       0
  4920.5     0.1       0  4983.8    0.05       0  4987.8     0.1       0
  5098.8    0.12       0  5204.1    0.05       0
Bank Sta=4983.8,4987.8
Exp/Cntr=0.3,0.1

Type RM Length L Ch R = 1,678,523,523,523
BEGIN DESCRIPTION:
XS7634
END DESCRIPTION:
XS GIS Cut Line= 3
      2467353.64     13678888.02      2467515.10     13679419.27
      2468400.25     13679783.74
#Sta/Elev= 30
  4542.2  263.72  4602.8  264.04  4676.5  261.97  4695.8  261.70  4701.3  260.08
  4706.6  261.32  4734.2  257.47  4739.4  258.53  4767.1  255.92  4805.2  255.05
  4870.9  251.35  4884.0  251.53  4903.8  250.20  4909.0  250.76  4941.9  247.89
  4945.4  248.34  4980.0  248.80  4988.5  247.35  4996.9  244.27  4997.2  243.77
  5000.9  244.27  5007.6  247.79  5012.9  249.08  5040.5  245.16  5045.7  248.99
  5049.6  248.97  5173.4  248.85  5362.1  250.88  5729.8  257.00  6054.7  266.29
#Mann=8,-1,0
  4542.2    0.07       0  4602.8     0.1       0  4676.5    0.12       0
  4945.4     0.1       0  4996.9    0.05       0  5000.9     0.1       0
  5049.6    0.12       0  5173.4    0.05       0
Bank Sta=4996.9,5000.9
Exp/Cntr=0.3,0.1

Type RM Length L Ch R = 1,155,0,0,0
BEGIN DESCRIPTION:
XS7633
END DESCRIPTION:
XS GIS Cut Line= 3
      2467129.69     13678804.74      2467202.60     13679486.98
      2468300.80     13679861.72
#Sta/Elev= 30
  4678.7  263.82  4713.7  263.78  4799.6  263.00  4809.7  260.84  4829.8  254.57
  4849.9  252.03  4867.4  250.62  4872.4  251.18  4920.3  248.80  4964.7  247.56
  4990.7  245.59  4998.8  243.50  4999.0  243.00  5002.8  243.50  5010.8  245.58
  5031.0  247.36  5051.1  246.71  5121.5  248.08  5222.0  247.22  5232.1  247.82
  5448.8  248.39  5498.7  247.73  5504.7  248.40  5561.4  249.32  5745.1  250.00
  5948.5  250.94  6334.1  255.77  6422.8  257.76  6485.5  260.21  6525.2  260.70
#Mann=6,-1,0
  4678.7    0.07       0  4713.7     0.1       0  4998.8    0.05       0
  5002.8     0.1       0  5448.8    0.12       0  5745.1    0.05       0
Bank Sta=4998.8,5002.8
Exp/Cntr=0.3,0.1

Chan Stop Cuts=-1