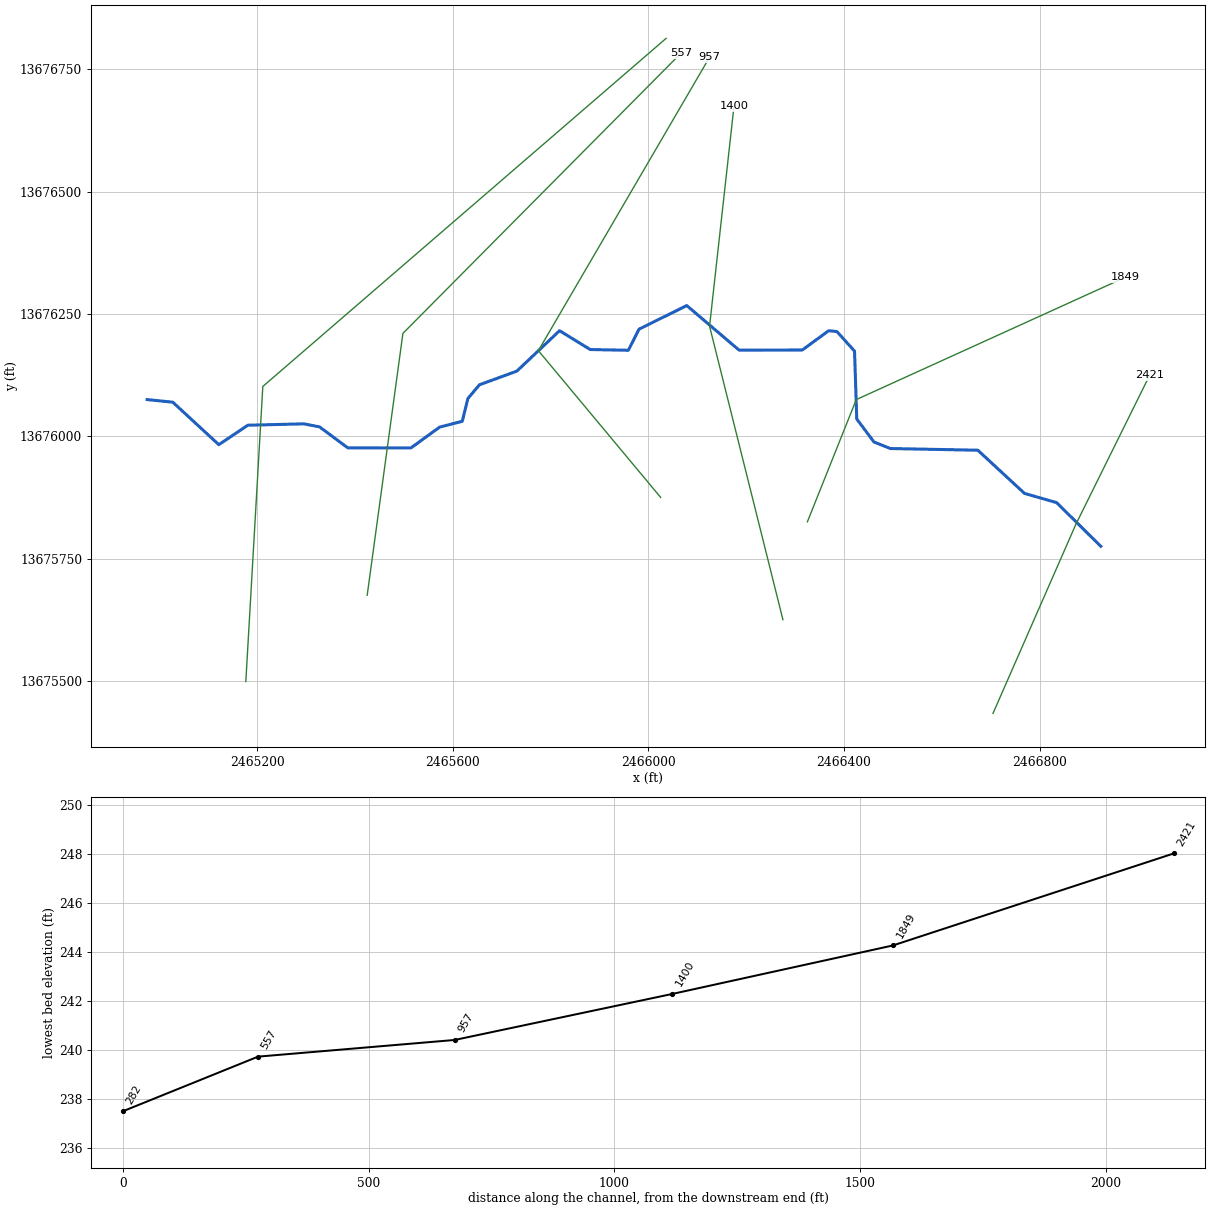
--- Stream0747.prj (project) ---

Proj Title=Stream0747 Base Level Engineering
Current Plan=p01
Default Exp/Contr=0.3,0.1
English Units
Geom File=g01
Flow File=f01
Plan File=p01
BEGIN DESCRIPTION:
Stream0747
END DESCRIPTION:

--- Stream0747.p01 (plan) ---

Plan Title=Multiple Run
Short Identifier=Multiple
Geom File=g01
Flow File=f01
Subcritical Flow
K Sum by GR= 0
Std Step Tol= 0.01
Critical Tol= 0.01
Num of Std Step Trials= 20
Max Error Tol= 0.3
Flow Tol Ratio= 0.001
Split Flow NTrial= 30
Split Flow Tol= 0.02
Split Flow Ratio= 0.02
Log Output Level= 0
Friction Slope Method= 1
Unsteady Friction Slope Method= 2
Unsteady Bridges Friction Slope Method= 1
Parabolic Critical Depth
Global Vel Dist=  1 , 1 , 1
Global Log Level= 0
CheckData=True
Encroach Param= -1, 0, 0, 0
BEGIN DESCRIPTION:
Multiple Run
END DESCRIPTION:

--- Stream0747.f01 (steady flow) ---

Flow Title=Multiple
Number of Profiles=7
Profile Names=10-year,25-year,50-year,1pct_min,100-year,1pct_plu,500-year
River Rch & RM= Stream0747,Reach-1,2421
     257     388     499     312     623    1243     957
Boundary for River Rch & Prof#=Stream0747,Reach-1,1
Up Type=0
Dn Type=3
Dn Slope=0.005
Boundary for River Rch & Prof#=Stream0747,Reach-1,2
Up Type=0
Dn Type=3
Dn Slope=0.005
Boundary for River Rch & Prof#=Stream0747,Reach-1,3
Up Type=0
Dn Type=3
Dn Slope=0.005
Boundary for River Rch & Prof#=Stream0747,Reach-1,4
Up Type=0
Dn Type=3
Dn Slope=0.005
Boundary for River Rch & Prof#=Stream0747,Reach-1,5
Up Type=0
Dn Type=3
Dn Slope=0.005
Boundary for River Rch & Prof#=Stream0747,Reach-1,6
Up Type=0
Dn Type=3
Dn Slope=0.005
Boundary for River Rch & Prof#=Stream0747,Reach-1,7
Up Type=0
Dn Type=3
Dn Slope=0.005

--- Stream0747.g01 (geometry) ---

Geom Title=Existing Conditions

River Reach=Stream0747,Reach-1
Reach XY= 30
      2466925.00     13675775.00      2466834.70     13675864.28
      2466768.96     13675883.17      2466673.53     13675971.45
      2466494.87     13675974.91      2466461.26     13675988.20
      2466425.99     13676035.27      2466421.46     13676174.01
      2466385.44     13676214.06      2466368.65     13676215.79
      2466314.57     13676176.38      2466185.44     13676176.05
      2466078.38     13676267.22      2465980.80     13676218.99
      2465959.00     13676175.79      2465880.98     13676177.34
      2465818.27     13676215.85      2465731.03     13676133.20
      2465654.57     13676105.27      2465630.89     13676077.20
      2465619.38     13676030.62      2465573.16     13676018.72
      2465514.52     13675976.18      2465385.51     13675976.21
      2465327.33     13676019.26      2465295.13     13676025.39
      2465180.86     13676022.54      2465121.58     13675982.78
      2465027.52     13676069.65      2464975.00     13676075.00

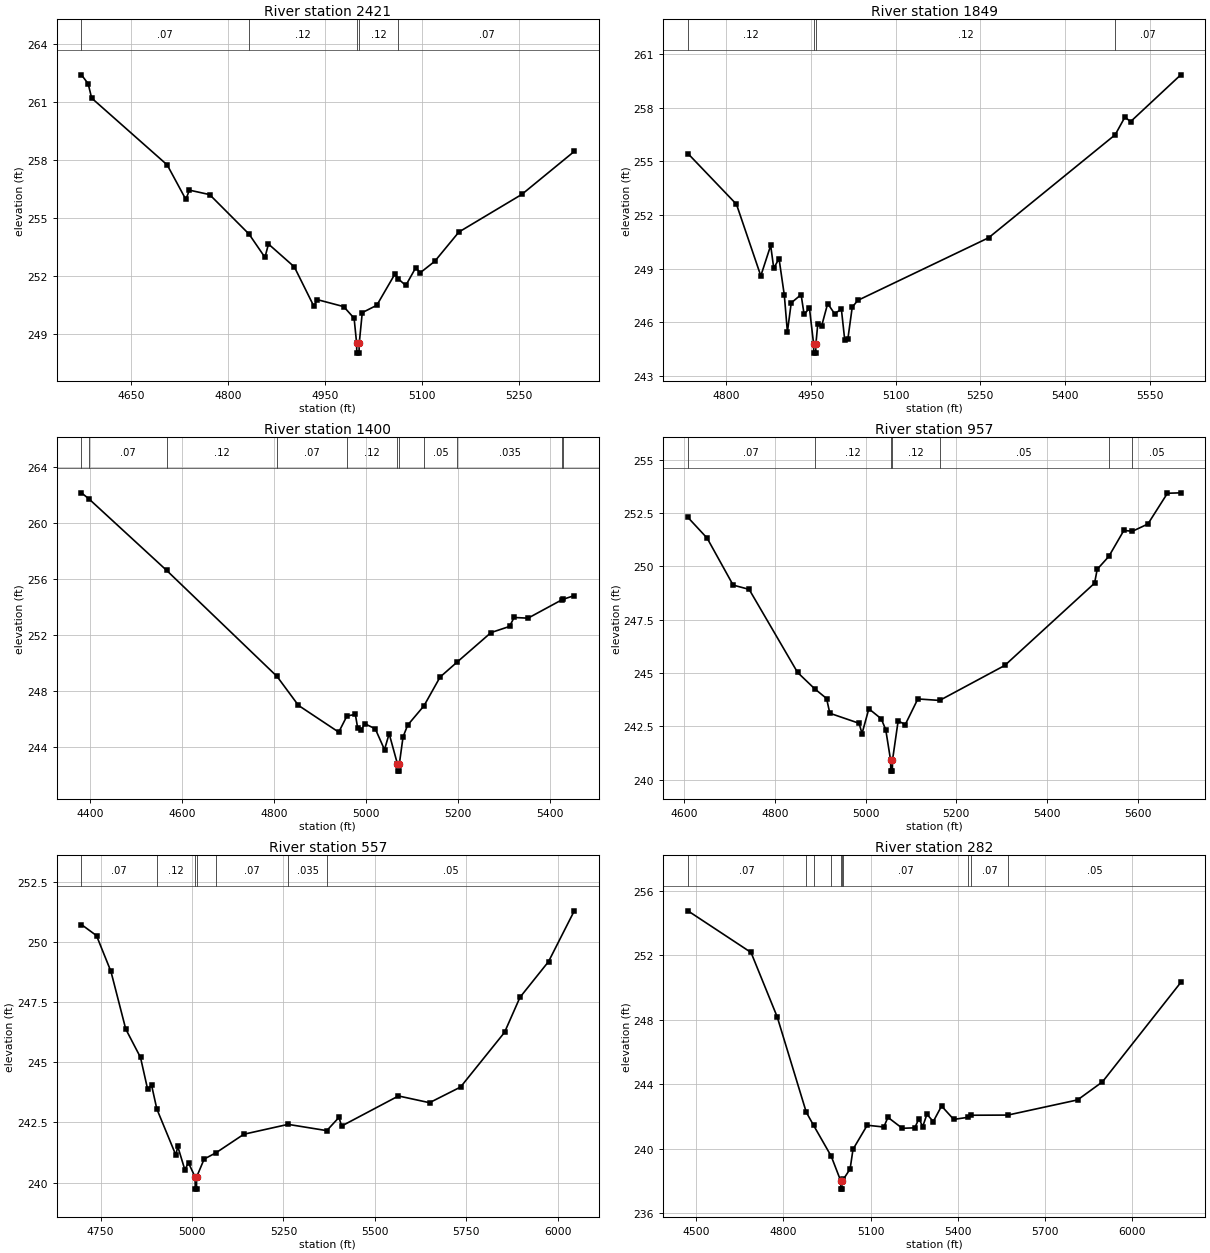
Type RM Length L Ch R = 1,2421,572,572,572
BEGIN DESCRIPTION:
Stream0747 5.0
END DESCRIPTION:
XS GIS Cut Line= 3
      2466704.58     13675433.38      2466873.87     13675819.70
      2467024.98     13676124.96
#Sta/Elev= 30
  4573.1  262.39  4583.5  261.93  4588.9  261.19  4705.8  257.74  4734.6  255.96
  4740.1  256.44  4771.4  256.21  4832.4  254.17  4857.0  252.97  4862.4  253.66
  4902.4  252.48  4932.6  250.45  4938.0  250.79  4978.8  250.43  4994.9  249.83
  4998.8  248.53  4999.0  248.03  5002.5  248.03  5002.8  248.53  5007.5  250.12
  5030.0  250.50  5058.0  252.11  5063.3  251.86  5074.8  251.52  5090.1  252.43
  5097.3  252.18  5119.7  252.77  5157.0  254.28  5254.3  256.22  5335.5  258.44
#Mann=5,-1,0
  4573.1    0.07       0  4832.4    0.12       0  4998.8    0.05       0
  5002.8    0.12       0  5063.3    0.07       0
Bank Sta=4998.8,5002.8
Exp/Cntr=0.3,0.1

Type RM Length L Ch R = 1,1849,449,449,449
BEGIN DESCRIPTION:
Stream0747 4.0
END DESCRIPTION:
XS GIS Cut Line= 3
      2466325.01     13675825.03      2466425.00     13676075.00
      2466975.02     13676325.01
#Sta/Elev= 30
  4731.8  255.43  4817.9  252.59  4861.0  248.59  4878.5  250.29  4883.9  249.02
  4893.3  249.55  4902.7  247.50  4908.1  245.45  4914.9  247.08  4932.4  247.54
  4937.7  246.44  4947.2  246.78  4954.6  244.77  4954.8  244.27  4958.3  244.27
  4958.6  244.77  4962.0  245.92  4968.7  245.78  4979.5  247.04  4991.6  246.48
  5003.8  246.72  5009.8  244.98  5015.3  245.07  5023.0  246.84  5032.9  247.22
  5264.7  250.72  5489.0  256.48  5506.3  257.47  5516.2  257.21  5605.2  259.83
#Mann=4,-1,0
  4731.8    0.12       0  4954.6    0.05       0  4958.6    0.12       0
  5489.0    0.07       0
Bank Sta=4954.6,4958.6
Exp/Cntr=0.3,0.1

Type RM Length L Ch R = 1,1400,443,443,443
BEGIN DESCRIPTION:
Stream0747 3.0
END DESCRIPTION:
XS GIS Cut Line= 3
      2466275.00     13675624.99      2466125.00     13676225.00
      2466174.99     13676674.95
#Sta/Elev= 30
  4381.4  262.14  4397.6  261.71  4566.5  256.61  4806.6  249.04  4853.0  246.98
  4940.6  245.07  4958.4  246.22  4976.7  246.34  4981.8  245.36  4989.6  245.23
  4997.3  245.67  5020.0  245.31  5040.1  243.82  5050.2  244.96  5068.3  242.79
  5068.6  242.29  5072.1  242.29  5072.3  242.79  5080.4  244.73  5090.4  245.57
  5125.9  246.95  5160.9  249.00  5198.7  250.09  5271.5  252.17  5311.8  252.61
  5321.8  253.25  5352.0  253.20  5425.6  254.51  5428.6  254.55  5452.6  254.81
#Mann=11,-1,0
  4381.4    0.05       0  4397.6    0.07       0  4566.5    0.12       0
  4806.6    0.07       0  4958.4    0.12       0  5068.3    0.05       0
  5072.3    0.12       0  5125.9    0.05       0  5198.7   0.035       0
  5425.6    0.07       0  5428.6    0.05       0
Bank Sta=5068.3,5072.3
Exp/Cntr=0.3,0.1

Type RM Length L Ch R = 1,957,400,400,400
BEGIN DESCRIPTION:
Stream0747 2.0
END DESCRIPTION:
XS GIS Cut Line= 3
      2466025.03     13675874.97      2465775.00     13676175.00
      2466125.01     13676775.02
#Sta/Elev= 30
  4608.9  252.29  4651.2  251.32  4708.5  249.12  4743.7  248.92  4850.4  245.03
  4887.8  244.27  4914.2  243.81  4921.4  243.12  4985.8  242.65  4992.3  242.17
  5007.3  243.33  5034.6  242.86  5044.5  242.35  5055.3  240.91  5055.6  240.41
  5059.1  240.41  5059.3  240.91  5071.8  242.76  5087.5  242.59  5115.2  243.79
  5163.1  243.72  5306.7  245.36  5504.3  249.21  5510.1  249.86  5535.6  250.46
  5568.8  251.68  5587.6  251.64  5621.7  251.98  5664.7  253.42  5694.1  253.44
#Mann=7,-1,0
  4608.9    0.07       0  4887.8    0.12       0  5055.3    0.05       0
  5059.3    0.12       0  5163.1    0.05       0  5535.6   0.035       0
  5587.6    0.05       0
Bank Sta=5055.3,5059.3
Exp/Cntr=0.3,0.1

Type RM Length L Ch R = 1,557,275,275,275
BEGIN DESCRIPTION:
Stream0747 1.0
END DESCRIPTION:
XS GIS Cut Line= 3
      2465425.00     13675675.02      2465498.00     13676210.33
      2466066.56     13676783.23
#Sta/Elev= 30
  4697.7  250.72  4738.9  250.26  4778.4  248.77  4818.8  246.38  4859.2  245.20
  4878.5  243.89  4889.4  244.05  4903.8  243.06  4955.9  241.14  4960.9  241.51
  4980.3  240.54  4990.4  240.82  5008.5  240.23  5008.8  239.73  5012.3  239.73
  5012.5  240.23  5033.2  240.98  5065.6  241.24  5141.7  242.01  5262.7  242.42
  5368.4  242.16  5401.8  242.71  5408.9  242.35  5564.4  243.60  5649.3  243.32
  5734.1  243.97  5854.3  246.24  5896.7  247.70  5974.6  249.18  6045.1  251.29
#Mann=7,-1,0
  4697.7    0.07       0  4903.8    0.12       0  5008.5    0.05       0
  5012.5    0.12       0  5065.6    0.07       0  5262.7   0.035       0
  5368.4    0.05       0
Bank Sta=5008.5,5012.5
Exp/Cntr=0.3,0.1

Type RM Length L Ch R = 1,282,0,0,0
BEGIN DESCRIPTION:
XS7635
END DESCRIPTION:
XS GIS Cut Line= 3
      2465176.82     13675498.51      2465211.55     13676101.82
      2466036.21     13676813.64
#Sta/Elev= 30
  4472.3  254.75  4689.2  252.17  4779.3  248.17  4879.0  242.27  4904.3  241.45
  4964.8  239.54  4997.7  238.00  4997.9  237.50  5001.4  237.50  5001.7  238.00
  5006.6  238.11  5029.7  238.75  5039.7  239.97  5088.5  241.46  5145.5  241.35
  5159.7  241.95  5209.1  241.27  5251.9  241.30  5266.1  241.86  5279.4  241.38
  5293.6  242.14  5315.5  241.69  5344.0  242.65  5385.8  241.82  5433.8  241.95
  5444.9  242.08  5571.8  242.09  5811.4  243.03  5896.9  244.15  6166.0  250.31
#Mann=10,-1,0
  4472.3    0.07       0  4879.0    0.12       0  4904.3     0.1       0
  4964.8    0.12       0  4997.7    0.05       0  5001.7    0.12       0
  5006.6    0.07       0  5433.8   0.035       0  5444.9    0.07       0
  5571.8    0.05       0
Bank Sta=4997.7,5001.7
Exp/Cntr=0.3,0.1

Chan Stop Cuts=-1