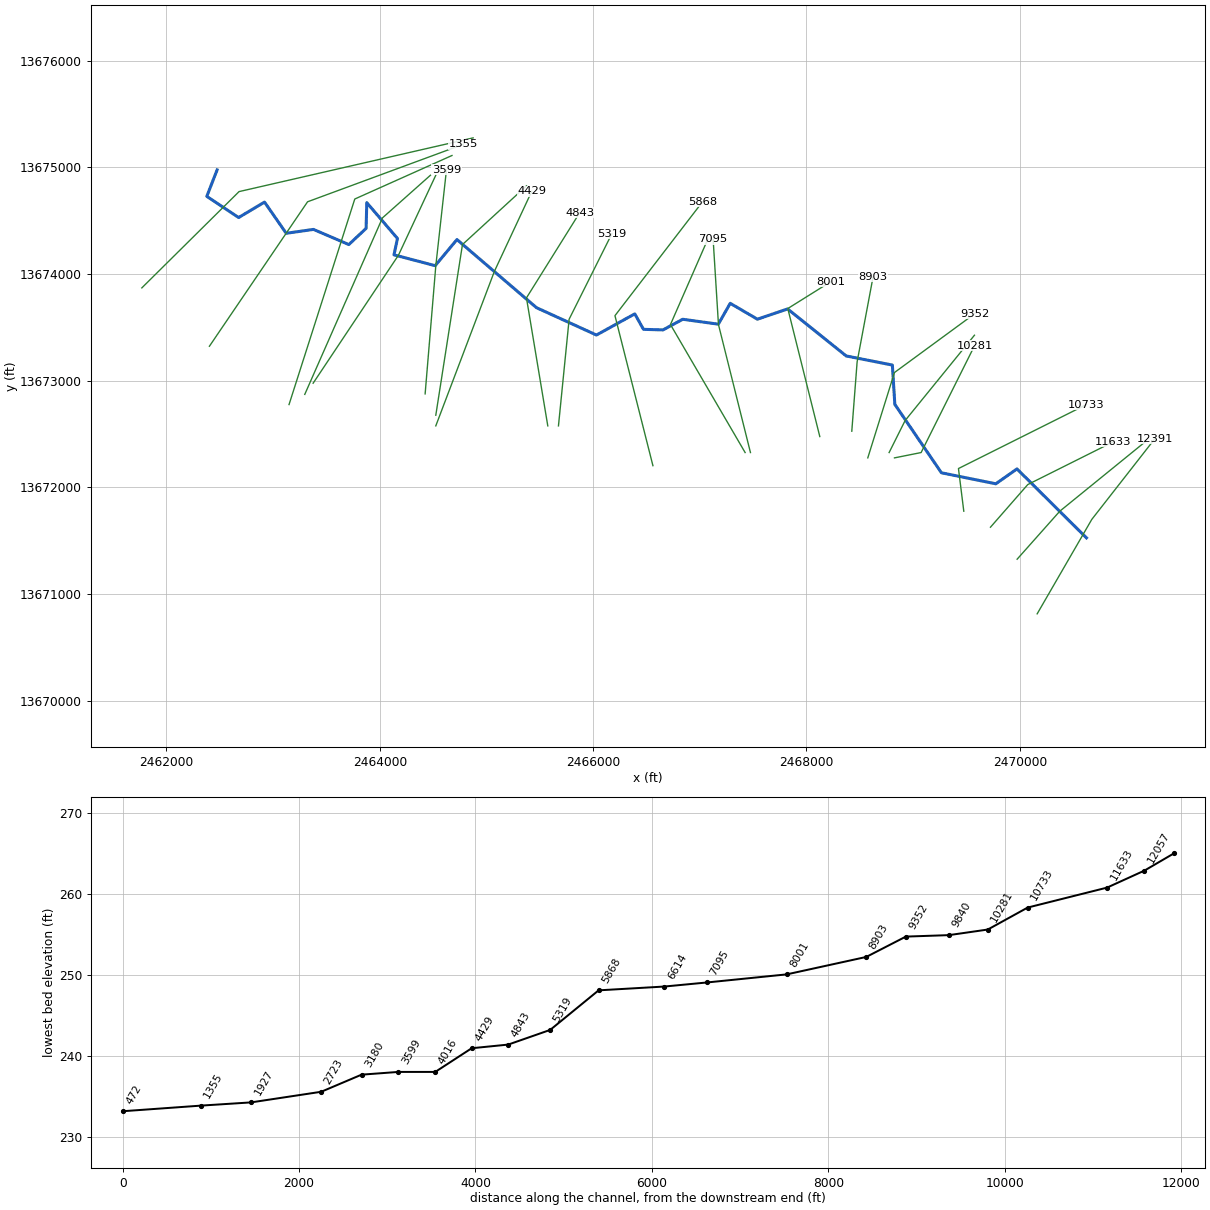
--- Stream0748.prj (project) ---

Proj Title=Stream0748 Base Level Engineering
Current Plan=p01
Default Exp/Contr=0.3,0.1
English Units
Geom File=g01
Flow File=f01
Plan File=p01
Y Axis Title=Elevation
X Axis Title(PF)=Main Channel Distance
X Axis Title(XS)=Station
BEGIN DESCRIPTION:
Stream0748
END DESCRIPTION:
DSS Export Rating Curves= 0
DSS Export Rating Curve Sorted= 0
DSS Export Volume Flow Curves= 0
DXF OffsetX= 0
DXF OffsetY= 0
DXF ScaleX= 1
DXF ScaleY= 10

--- Stream0748.p01 (plan) ---

Plan Title=Multiple Run
Short Identifier=Multiple
Geom File=g01
Flow File=f01
Subcritical Flow
K Sum by GR= 0
Std Step Tol= 0.01
Critical Tol= 0.01
Num of Std Step Trials= 20
Max Error Tol= 0.3
Flow Tol Ratio= 0.001
Split Flow NTrial= 30
Split Flow Tol= 0.02
Split Flow Ratio= 0.02
Log Output Level= 0
Friction Slope Method= 1
Unsteady Friction Slope Method= 2
Unsteady Bridges Friction Slope Method= 1
Parabolic Critical Depth
Global Vel Dist=  1 , 1 , 1
Global Log Level= 0
CheckData=True
Encroach Param= -1, 0, 0, 0
BEGIN DESCRIPTION:
Multiple Run
END DESCRIPTION:

--- Stream0748.f01 (steady flow) ---

Flow Title=Multiple
Number of Profiles=7
Profile Names=10-year,25-year,50-year,1pct_min,100-year,1pct_plu,500-year
River Rch & RM= Stream0748,Reach-1,12391
     786    1282    1735    1137    2270    4528    3844
River Rch & RM= Stream0748,Reach-1,10281
    1137    1886    2582    1709    3410    6804    5893
River Rch & RM= Stream0748,Reach-1,7095
    1281    2120    2895    1910    3811    7604    6543
Boundary for River Rch & Prof#=Stream0748,Reach-1,1
Up Type=0
Dn Type=3
Dn Slope=0.005
Boundary for River Rch & Prof#=Stream0748,Reach-1,2
Up Type=0
Dn Type=3
Dn Slope=0.005
Boundary for River Rch & Prof#=Stream0748,Reach-1,3
Up Type=0
Dn Type=3
Dn Slope=0.005
Boundary for River Rch & Prof#=Stream0748,Reach-1,4
Up Type=0
Dn Type=3
Dn Slope=0.005
Boundary for River Rch & Prof#=Stream0748,Reach-1,5
Up Type=0
Dn Type=3
Dn Slope=0.005
Boundary for River Rch & Prof#=Stream0748,Reach-1,6
Up Type=0
Dn Type=3
Dn Slope=0.005
Boundary for River Rch & Prof#=Stream0748,Reach-1,7
Up Type=0
Dn Type=3
Dn Slope=0.005

--- Stream0748.g01 (geometry) ---

Geom Title=Existing Conditions
Program Version=4.10

River Reach=Stream0748      ,Reach-1
Reach XY= 30
        2470625.       13671525.      2469973.51     13672171.55
      2469775.21     13672032.01      2469265.32     13672135.19
      2468828.55     13672776.47      2468805.41     13673145.21
      2468372.43     13673230.69      2467823.41     13673671.33
      2467540.09     13673575.18      2467285.27     13673724.04
      2467173.77     13673528.43      2466840.22     13673574.51
       2466654.8     13673474.78      2466472.17     13673480.11
      2466390.48      13673625.1      2466031.12     13673426.76
      2465468.95     13673683.16      2464723.34     13674321.92
      2464519.29     13674076.88      2464133.03     13674178.37
      2464165.85     13674331.73       2463878.1     13674667.49
      2463871.54      13674426.5      2463709.64     13674274.89
       2463378.3     13674416.92      2463122.55     13674380.46
      2462919.31     13674673.13      2462676.76      13674528.3
      2462378.12     13674726.62        2462475.       13674975.

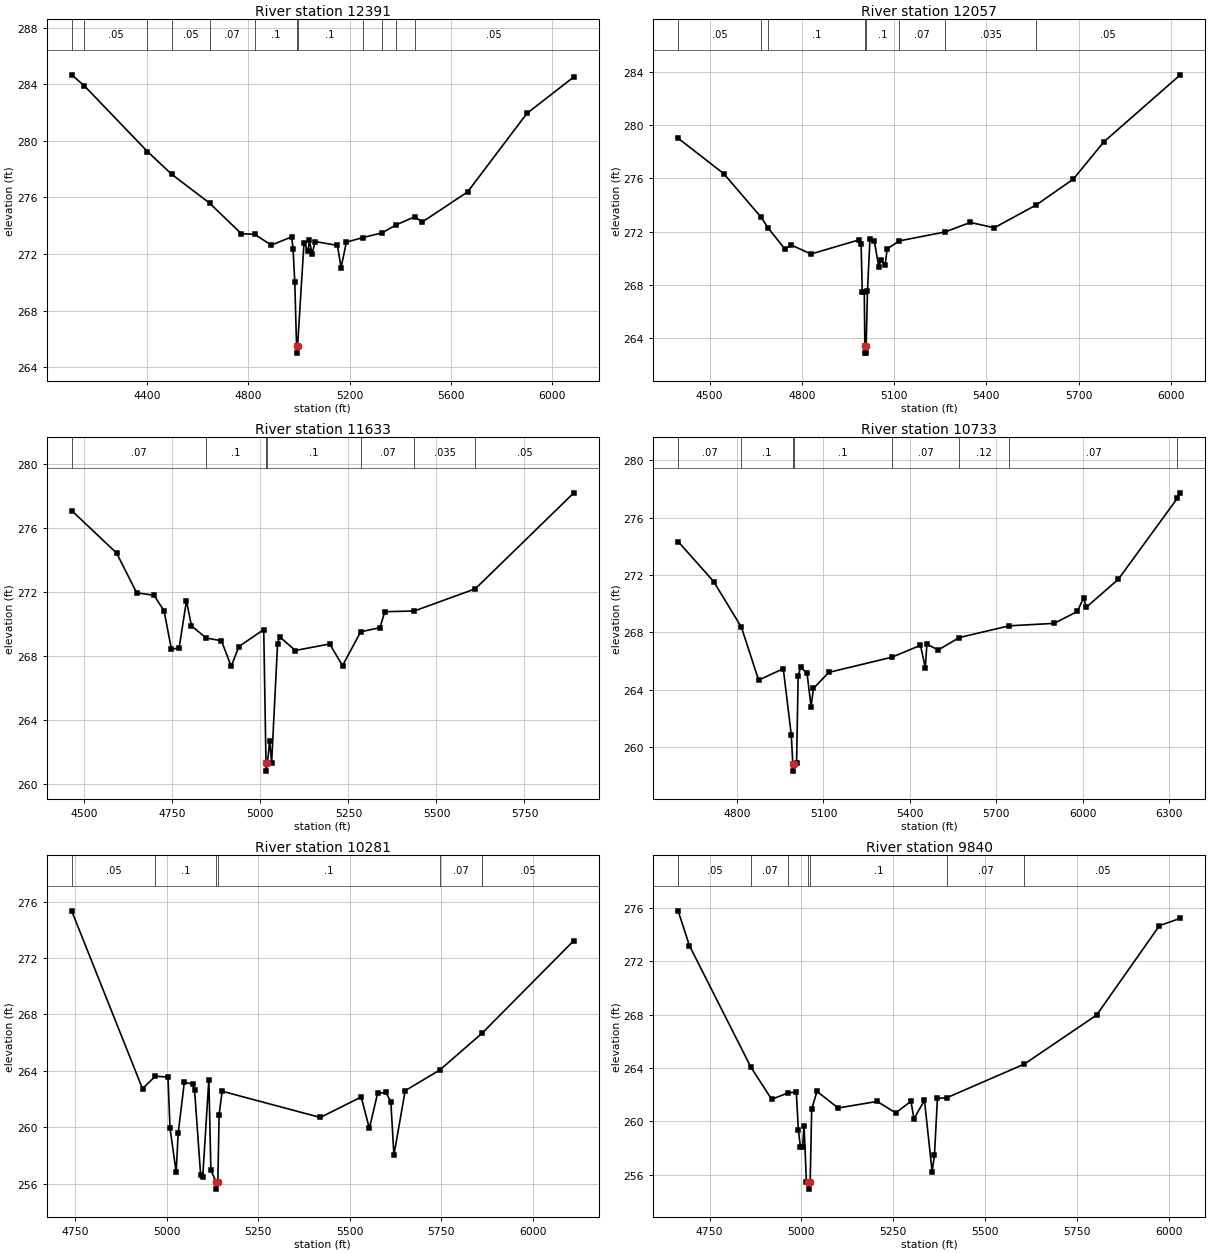
Type RM Length L Ch R = 1 ,12391   ,334,334,334
BEGIN DESCRIPTION:
XS7638
END DESCRIPTION:
XS GIS Cut Line= 3
        2470163.     13670812.99      2470675.17     13671698.44
      2471265.44     13672453.63
#Sta/Elev= 30
  4103.7  284.66  4152.8   283.9  4402.8  279.24  4499.4  277.62  4647.7   275.6
  4773.5  273.43  4825.3   273.4  4891.2  272.63  4971.6  273.21  4977.3  272.37
    4984  270.04  4991.1   265.5  4991.4     265  4995.1   265.5  5020.4  272.79
  5036.2  272.22    5042  272.96  5051.9  272.01  5064.9  272.88  5152.3  272.61
  5166.8  271.04  5187.6  272.84  5252.2  273.16  5328.9   273.5  5382.7  274.05
  5456.8  274.63  5487.8  274.27    5666  276.39  5900.2  281.94  6085.1  284.51
#Mann= 12 ,-1 , 0
  4103.7    .035       0  4152.8     .05       0  4402.8     .07       0
  4499.4     .05       0  4647.7     .07       0  4825.3      .1       0
  4991.1     .05       0  4995.1      .1       0  5252.2     .07       0
  5328.9    .035       0  5382.7     .07       0  5456.8     .05       0
Bank Sta=4991.1,4995.1
XS Rating Curve= 0 ,0
Exp/Cntr=0.3,0.1

Type RM Length L Ch R = 1 ,12057   ,424,424,424
BEGIN DESCRIPTION:
Stream0748 19.0
END DESCRIPTION:
XS GIS Cut Line= 3
      2469974.99     13671324.98        2470375.       13671775.
      2471175.02     13672425.01
#Sta/Elev= 30
  4397.9  279.01  4546.3  276.35  4668.2  273.07  4691.5  272.24  4745.4  270.69
  4766.3  270.99  4829.8  270.32  4986.2  271.38  4992.9  271.04  4996.7  267.47
  5003.2  267.47  5005.1  263.38  5005.4  262.88  5008.9  262.88  5009.2  263.38
  5013.6  267.52  5021.6  271.44  5035.9   271.3  5050.3  269.35  5056.7  269.84
  5071.1  269.51  5077.6   270.7  5116.3   271.3  5266.5  271.98  5347.9  272.69
  5425.9  272.29  5562.2     274  5682.9  275.94  5782.3  278.74  6030.8  283.77
#Mann= 8 ,-1 , 0
  4397.9     .05       0  4668.2     .07       0  4691.5      .1       0
  5005.1     .05       0  5009.2      .1       0  5116.3     .07       0
  5266.5    .035       0  5562.2     .05       0
Bank Sta=5005.1,5009.2
XS Rating Curve= 0 ,0
Exp/Cntr=0.3,0.1

Type RM Length L Ch R = 1 ,11633   ,900,900,900
BEGIN DESCRIPTION:
Stream0748 18.0
END DESCRIPTION:
XS GIS Cut Line= 3
      2469725.02     13671625.03        2470075.       13672025.
        2470875.       13672425.
#Sta/Elev= 30
  4464.2  277.09  4591.8  274.43  4648.8  271.94  4698.1  271.79  4726.6  270.81
  4747.5  268.41  4769.3  268.49  4790.2  271.44  4804.4  269.87  4846.4  269.11
  4889.4  268.94  4917.4  267.34  4939.2  268.58  5009.6  269.64    5016  261.28
  5016.2  260.78  5020.1  261.28  5026.4  262.68    5032   261.3  5048.8  268.73
  5054.4   269.2  5099.1  268.33  5196.9  268.74  5233.3  267.38  5284.8   269.5
  5339.5  269.76  5353.4  270.76  5436.5   270.8  5610.2  272.19  5890.1   278.2
#Mann= 7 ,-1 , 0
  4464.2     .07       0  4846.4      .1       0    5016     .05       0
  5020.1      .1       0  5284.8     .07       0  5436.5    .035       0
  5610.2     .05       0
Bank Sta=5016,5020.1
XS Rating Curve= 0 ,0
Exp/Cntr=0.3,0.1

Type RM Length L Ch R = 1 ,10733   ,452,452,452
BEGIN DESCRIPTION:
Stream0748 17.0
END DESCRIPTION:
XS GIS Cut Line= 3
      2469475.01     13671774.95        2469425.       13672175.
        2470625.       13672775.
#Sta/Elev= 30
    4595  274.34  4718.5  271.55    4815  268.36  4874.7  264.67  4960.4  265.47
  4988.1  260.86  4993.5  258.82  4993.8  258.32  4997.7  258.82  5006.5   258.9
  5012.1  264.97  5020.5  265.56  5042.9  265.16  5056.9  262.82  5065.2  264.09
  5118.4  265.21  5337.9  266.27    5437   267.1  5453.8  265.54  5459.4  267.18
  5498.5  266.77  5571.8  267.64  5745.2  268.46    5901  268.63    5982  269.46
  6004.4  270.43  6012.8  269.75  6124.6  271.71  6329.9  277.37  6339.8  277.74
#Mann= 8 ,-1 , 0
    4595     .07       0    4815      .1       0  4993.5     .07       0
  4997.7      .1       0  5337.9     .07       0  5571.8     .12       0
  5745.2     .07       0  6329.9    .035       0
Bank Sta=4993.5,4997.7
XS Rating Curve= 0 ,0
Exp/Cntr=0.3,0.1

Type RM Length L Ch R = 1 ,10281   ,441,441,441
BEGIN DESCRIPTION:
Stream0748 16.0
END DESCRIPTION:
XS GIS Cut Line= 3
      2468825.03     13672275.01        2469075.       13672325.
      2469574.98     13673324.96
#Sta/Elev= 30
  4739.8  275.34  4933.5  262.73  4968.7  263.62  5003.1  263.55  5008.7  259.94
  5025.5  256.81  5031.1   259.6  5047.8  263.17  5070.2  263.07  5075.8  262.64
  5092.5  256.59  5098.1  256.49  5114.9  263.37  5120.5  256.94    5135  256.11
  5135.3  255.61  5139.5  256.11  5142.9   260.9  5151.2  262.55  5419.6  260.69
  5531.4  262.14  5553.7  259.92  5576.1  262.39  5598.5  262.47  5612.4  261.81
  5620.8  258.02  5651.6  262.59    5746  264.05  5861.3  266.65  6112.7  273.23
#Mann= 6 ,-1 , 0
  4739.8     .05       0  4968.7      .1       0    5135     .05       0
  5139.5      .1       0    5746     .07       0  5861.3     .05       0
Bank Sta=5135,5139.5
XS Rating Curve= 0 ,0
Exp/Cntr=0.3,0.1

Type RM Length L Ch R = 1 ,9840    ,488,488,488
BEGIN DESCRIPTION:
Stream0748 15.0
END DESCRIPTION:
XS GIS Cut Line= 3
      2468774.99     13672324.97        2468925.       13672625.
      2469574.99     13673424.99
#Sta/Elev= 30
  4664.6  275.77  4695.4  273.16  4862.7  264.05    4919  261.65    4963  262.12
  4986.1   262.2  4991.7  259.36  4997.2  258.11  5003.3  258.11  5007.2  259.66
  5013.7  255.43  5019.3  255.42  5019.6  254.92  5023.8  255.42    5028  260.92
  5042.4  262.24  5099.9     261  5206.2  261.49  5256.5  260.63  5298.1   261.5
  5306.1  260.19  5334.8  261.57  5355.6  256.23    5362  257.45    5370  261.72
    5395  261.76  5606.5  264.29  5803.1  267.96  5974.1  274.66  6030.8  275.21
#Mann= 7 ,-1 , 0
  4664.6     .05       0  4862.7     .07       0    4963      .1       0
  5019.3     .05       0  5023.8      .1       0    5395     .07       0
  5606.5     .05       0
Bank Sta=5019.3,5023.8
XS Rating Curve= 0 ,0
Exp/Cntr=0.3,0.1

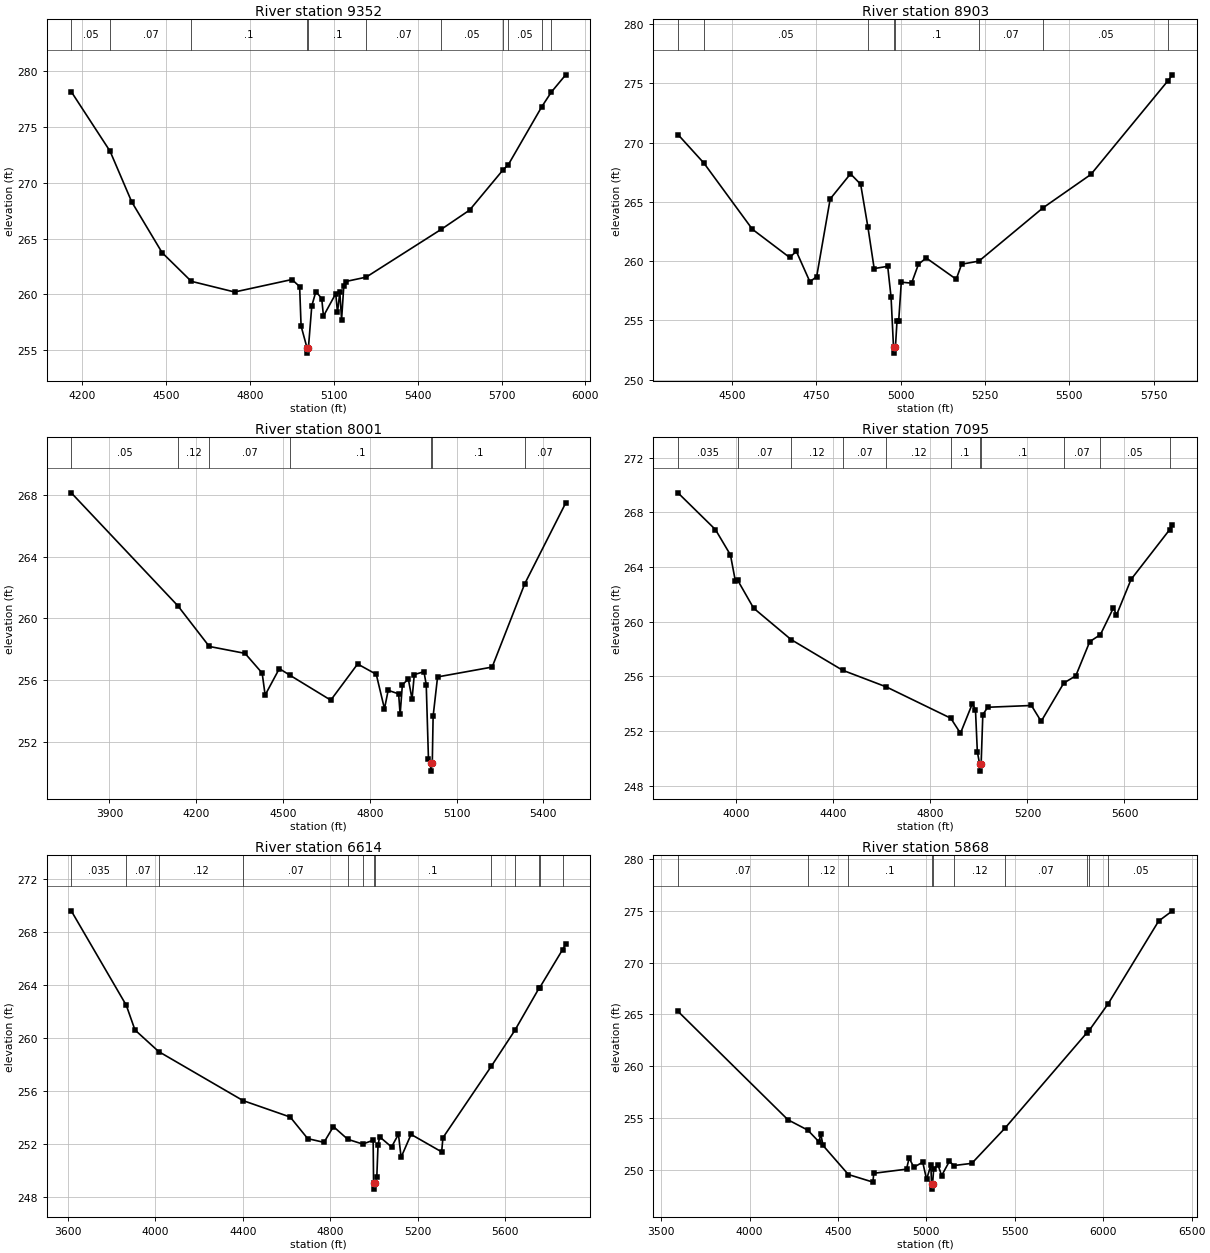
Type RM Length L Ch R = 1 ,9352    ,449,449,449
BEGIN DESCRIPTION:
Stream0748 14.0
END DESCRIPTION:
XS GIS Cut Line= 3
        2468575.     13672274.99        2468825.       13673075.
      2469574.99     13673624.99
#Sta/Elev= 30
  4161.3  278.18  4300.1  272.84  4377.7  268.29  4486.1  263.75  4590.4  261.18
  4745.4  260.22  4950.7  261.34    4978   260.7  4983.2  257.17  5004.1  255.24
  5004.5  254.74  5009.5  255.24  5021.4  258.97  5036.1  260.26    5057  259.63
  5063.2  258.06  5107.1  260.07  5113.3  258.41  5121.8  260.18    5128  257.74
  5135.9  260.75  5142.6  261.16  5215.7  261.55  5485.1  265.85  5585.7  267.56
  5704.8  271.15  5724.2  271.63  5843.7  276.82    5878  278.14  5929.5  279.69
#Mann= 11 ,-1 , 0
  4161.3     .05       0  4300.1     .07       0  4590.4      .1       0
  5004.1     .05       0  5009.5      .1       0  5215.7     .07       0
  5485.1     .05       0  5704.8     .07       0  5724.2     .05       0
  5843.7    .035       0    5878     .05       0
Bank Sta=5004.1,5009.5
XS Rating Curve= 0 ,0
Exp/Cntr=0.3,0.1

Type RM Length L Ch R = 1 ,8903    ,902,902,902
BEGIN DESCRIPTION:
Stream0748 13.0
END DESCRIPTION:
XS GIS Cut Line= 3
        2468425.     13672525.02        2468475.       13673175.
      2468624.99     13673974.96
#Sta/Elev= 30
  4340.2  270.69  4417.3  268.27  4560.8  262.69  4671.2  260.31  4691.2  260.82
  4731.3  258.26  4751.4  258.69  4791.5  265.25  4851.7  267.37  4881.8  266.49
  4903.5  262.84  4921.9  259.37    4962  259.56    4972  256.94  4979.2  252.73
  4979.7  252.23  4984.9  252.73  4989.6  254.95  4994.6  254.95  5002.3  258.22
  5032.8  258.14  5053.1  259.73    5076  260.27  5165.1  258.47  5181.2  259.74
  5232.4     260  5422.5   264.5  5564.4  267.32  5793.4  275.25    5806  275.73
#Mann= 8 ,-1 , 0
  4340.2     .07       0  4417.3     .05       0  4903.5      .1       0
  4979.2     .05       0  4984.9      .1       0  5232.4     .07       0
  5422.5     .05       0  5793.4    .035       0
Bank Sta=4979.2,4984.9
XS Rating Curve= 0 ,0
Exp/Cntr=0.3,0.1

Type RM Length L Ch R = 1 ,8001    ,906,906,906
BEGIN DESCRIPTION:
Stream0748 12.0
END DESCRIPTION:
XS GIS Cut Line= 3
      2468125.01     13672474.96        2467825.       13673675.
      2468225.02     13673925.01
#Sta/Elev= 30
  3768.3  268.16  4136.7  260.82  4245.2  258.18  4368.8  257.73    4428  256.45
  4438.3  255.02  4487.3  256.74  4524.8   256.3  4665.1  254.69  4757.9  257.04
  4822.3  256.37  4850.7  254.13  4863.5  255.33  4899.6   255.1  4904.8  253.76
  4912.5  255.68  4933.1  256.07    4946  254.75  4953.7  256.35  4987.2  256.54
    4995   255.7  5002.7  250.88    5010  250.58  5010.5  250.08  5015.9  250.58
  5018.8  253.64  5034.2   256.2  5222.8  256.84  5335.4  262.25    5477   267.5
#Mann= 7 ,-1 , 0
  3768.3     .05       0  4136.7     .12       0  4245.2     .07       0
  4524.8      .1       0    5010     .05       0  5015.9      .1       0
  5335.4     .07       0
Bank Sta=5010,5015.9
XS Rating Curve= 0 ,0
Exp/Cntr=0.3,0.1

Type RM Length L Ch R = 1 ,7095    ,481,481,481
BEGIN DESCRIPTION:
Stream0748 11.0
END DESCRIPTION:
XS GIS Cut Line= 3
      2467474.99     13672325.04        2467175.       13673525.
        2467125.     13674325.05
#Sta/Elev= 30
  3759.2  269.43  3913.8  266.74  3975.6  264.89  3996.2  262.95  4005.6  263.03
    4071     261  4225.6   258.7  4437.7  256.46  4618.1  255.24  4883.9  252.95
  4923.9  251.85  4972.9  254.01  4985.8  253.57  4993.5   250.5  5003.1  249.58
  5003.6  249.08  5009.1  249.58  5016.1  253.21  5036.2  253.75  5216.5  253.88
  5256.6  252.72  5349.9  255.52  5399.4  256.05    5457  258.55  5500.9  259.06
  5554.7  261.02  5567.2  260.49  5627.3   263.1  5786.5  266.74  5797.7  267.09
#Mann= 11 ,-1 , 0
  3759.2    .035       0  4005.6     .07       0  4225.6     .12       0
  4437.7     .07       0  4618.1     .12       0  4883.9      .1       0
  5003.1     .05       0  5009.1      .1       0  5349.9     .07       0
  5500.9     .05       0  5786.5    .035       0
Bank Sta=5003.1,5009.1
XS Rating Curve= 0 ,0
Exp/Cntr=0.3,0.1

Type RM Length L Ch R = 1 ,6614    ,746,746,746
BEGIN DESCRIPTION:
Stream0748 10.0
END DESCRIPTION:
XS GIS Cut Line= 3
        2467425.       13672325.        2466725.       13673525.
      2467075.02     13674325.04
#Sta/Elev= 30
  3615.4  269.58  3867.2  262.45  3906.9  260.59  4015.4  258.96  4401.4  255.26
  4617.2  254.02  4697.4  252.39  4771.9  252.11  4814.9   253.3  4880.6  252.34
  4949.2  251.98  4996.8  252.27  4998.7  249.08  4999.2  248.58  5004.8  249.08
  5013.6  249.53  5019.1  251.89  5026.5  252.53    5081  251.76  5112.6  252.72
  5124.7  250.98  5170.3  252.71  5310.3  251.39  5316.1  252.46  5537.4  257.85
  5644.8  260.55  5755.1  263.72  5758.5  263.77  5863.9  266.66  5877.9  267.05
#Mann= 13 ,-1 , 0
  3615.4    .035       0  3867.2     .07       0  4015.4     .12       0
  4401.4     .07       0  4880.6     .12       0  4949.2      .1       0
  4998.7     .05       0  5004.8      .1       0  5537.4     .07       0
  5644.8     .05       0  5755.1    .035       0  5758.5     .05       0
  5863.9    .035       0
Bank Sta=4998.7,5004.8
XS Rating Curve= 0 ,0
Exp/Cntr=0.3,0.1

Type RM Length L Ch R = 1 ,5868    ,549,549,549
BEGIN DESCRIPTION:
Stream0748 9.0
END DESCRIPTION:
XS GIS Cut Line= 3
       2466560.6     13672201.88      2466204.69     13673608.16
      2467025.01     13674675.02
#Sta/Elev= 30
  3594.7  265.29  4216.8  254.81  4329.1  253.81  4392.2  252.68  4402.5  253.45
  4415.1  252.33  4558.5  249.52  4697.1  248.79  4702.2  249.64  4887.3  250.04
  4902.1  251.12  4928.6  250.23    4979  250.71  5000.8  249.05  5025.1  250.43
  5028.7  248.61  5029.2  248.11  5034.8  248.61  5041.1  250.09  5065.3  250.44
  5086.2  249.42  5129.6  250.79  5155.9  250.39  5256.5   250.6  5443.6  253.99
  5906.7   263.2  5921.6  263.47  6028.6  266.04  6313.2  274.01  6391.1     275
#Mann= 10 ,-1 , 0
  3594.7     .07       0  4329.1     .12       0  4558.5      .1       0
  5028.7     .05       0  5034.8      .1       0  5155.9     .12       0
  5443.6     .07       0  5906.7     .05       0  5921.6    .035       0
  6028.6     .05       0
Bank Sta=5028.7,5034.8
XS Rating Curve= 0 ,0
Exp/Cntr=0.3,0.1

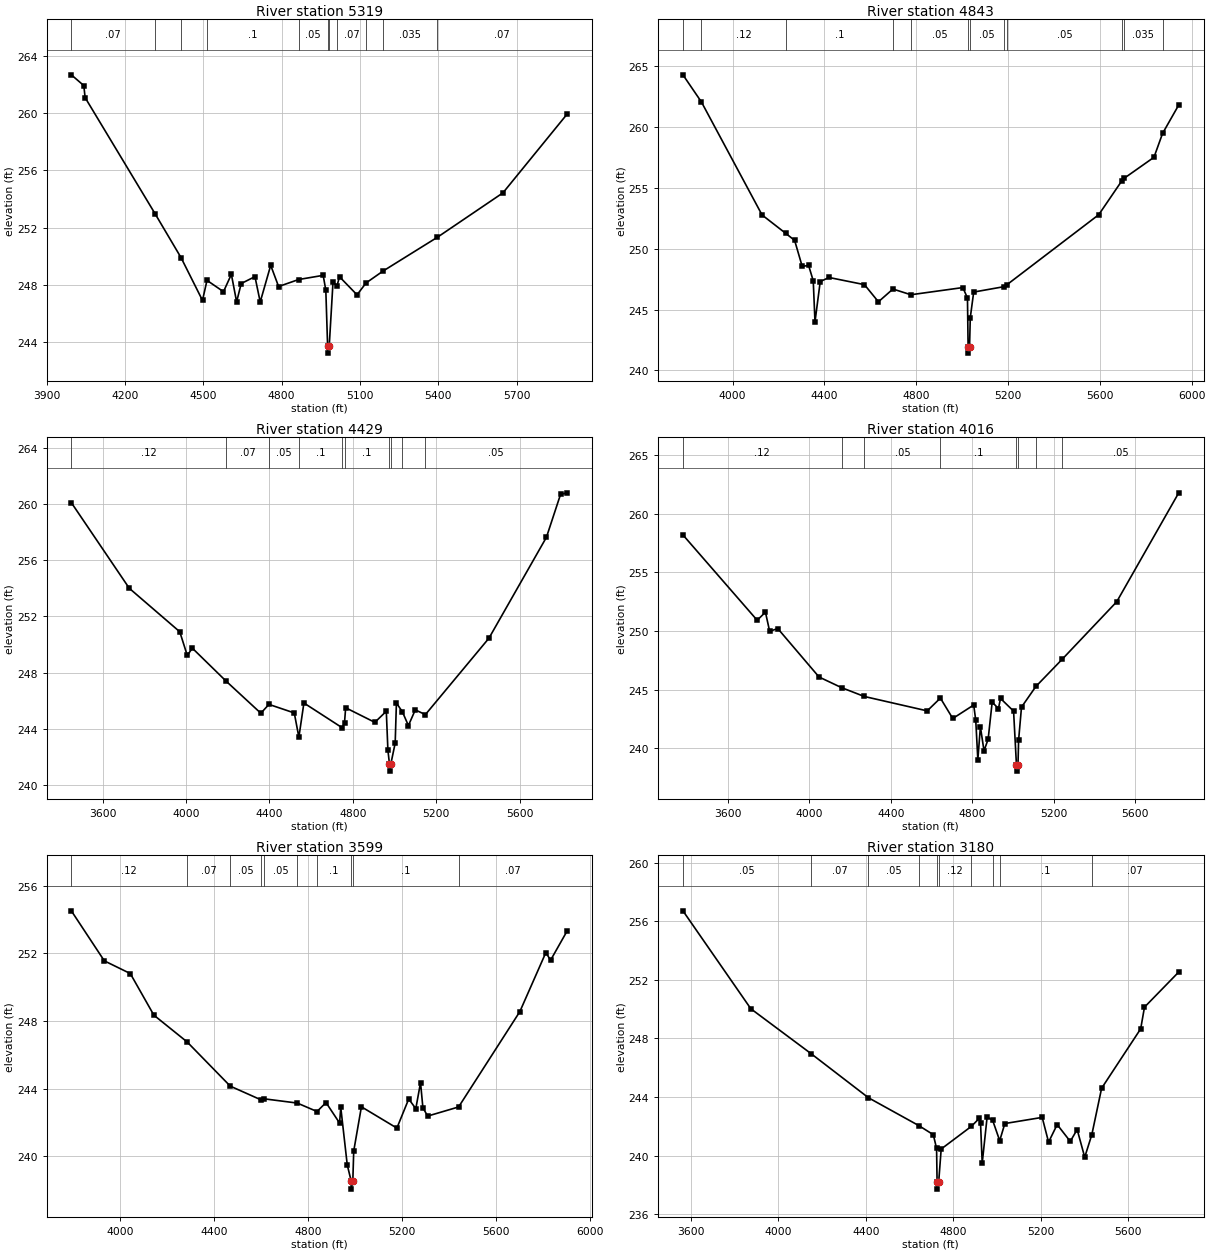
Type RM Length L Ch R = 1 ,5319    ,476,476,476
BEGIN DESCRIPTION:
Stream0748 8.0
END DESCRIPTION:
XS GIS Cut Line= 3
        2465675.     13672574.97        2465775.       13673575.
      2466174.98     13674374.96
#Sta/Elev= 30
  3994.5  262.66  4042.3  261.91  4047.3  261.07  4315.7  252.95    4415  249.89
    4497  246.91  4514.2  248.31  4577.4  247.52  4607.6  248.73  4627.7  246.81
  4645.3  248.09    4698  248.57  4718.1   246.8  4758.3  249.36  4788.5  247.88
  4865.5  248.37  4959.3  248.66  4969.4  247.63  4976.3  243.73  4976.8  243.23
  4982.5  243.73    4997   248.2  5011.9  247.91  5021.9  248.56    5089   247.3
  5123.6  248.13  5188.7  248.96  5396.9  251.32    5648  254.42  5893.9  259.92
#Mann= 11 ,-1 , 0
  3994.5     .07       0  4315.7      .1       0    4415     .12       0
  4514.2      .1       0  4865.5     .05       0  4976.3     .05       0
  4982.5     .05       0  5011.9     .07       0  5123.6     .05       0
  5188.7    .035       0  5396.9     .07       0
Bank Sta=4976.3,4982.5
XS Rating Curve= 0 ,0
Exp/Cntr=0.3,0.1

Type RM Length L Ch R = 1 ,4843    ,414,414,414
BEGIN DESCRIPTION:
Stream0748 7.0
END DESCRIPTION:
XS GIS Cut Line= 3
        2465575.     13672574.99        2465375.       13673775.
      2465875.02     13674575.03
#Sta/Elev= 30
  3783.8   264.3  3864.3  262.07  4128.5  252.78  4232.1  251.26  4270.4  250.69
  4303.4  248.55  4331.3  248.63  4351.5  247.37  4359.1  243.99  4381.9   247.3
    4420  247.64  4574.6  247.05  4635.4  245.64  4698.7  246.69  4776.9  246.22
  5003.3  246.81  5023.4  245.95  5026.2  241.92  5026.7  241.42  5032.4  241.92
  5035.7  244.34  5050.5  246.44  5181.4  246.88  5195.1  247.04  5595.3   252.8
  5695.7  255.58  5705.7  255.79  5835.9  257.52  5873.3  259.48  5943.8  261.82
#Mann= 12 ,-1 , 0
  3783.8     .07       0  3864.3     .12       0  4232.1      .1       0
  4698.7     .07       0  4776.9     .05       0  5026.2     .05       0
  5032.4     .05       0  5181.4     .07       0  5195.1     .05       0
  5695.7     .07       0  5705.7    .035       0  5873.3     .07       0
Bank Sta=5026.2,5032.4
XS Rating Curve= 0 ,0
Exp/Cntr=0.3,0.1

Type RM Length L Ch R = 1 ,4429    ,413,413,413
BEGIN DESCRIPTION:
Stream0748 6.0
END DESCRIPTION:
XS GIS Cut Line= 3
      2464524.99     13672574.98        2465075.       13674025.
      2465425.01     13674775.02
#Sta/Elev= 30
  3449.4  260.12  3727.5  254.01  3969.6  250.91  4005.6  249.22  4029.9  249.74
  4191.8  247.39  4358.5   245.1  4397.4  245.73  4518.9  245.12    4541  243.39
  4565.1  245.83  4749.2  244.06  4759.9  244.42  4765.4  245.49  4905.4  244.45
  4960.4  245.24  4968.1  242.46  4975.7  241.47  4976.2  240.97    4982  241.47
    5003  242.97  5008.9  245.83  5037.6   245.2  5066.4  244.22  5099.5  245.34
  5147.8     245  5452.7  250.45  5728.6  257.65  5796.3  260.71  5827.9  260.82
#Mann= 10 ,-1 , 0
  3449.4     .12       0  4191.8     .07       0  4397.4     .05       0
    4541      .1       0  4749.2     .05       0  4759.9      .1       0
  4975.7     .05       0    4982      .1       0  5037.6     .07       0
  5147.8     .05       0
Bank Sta=4975.7,4982
XS Rating Curve= 0 ,0
Exp/Cntr=0.3,0.1

Type RM Length L Ch R = 1 ,4016    ,417,417,417
BEGIN DESCRIPTION:
Stream0748 5.0
END DESCRIPTION:
XS GIS Cut Line= 3
        2464525.     13672674.99        2464775.       13674275.
      2465375.02     13674825.02
#Sta/Elev= 30
  3380.1   258.2  3744.5  250.92    3785  251.61  3805.7  249.98  3845.7  250.21
  4048.1  246.08  4158.9  245.17    4270  244.42    4579  243.19  4643.7  244.28
  4704.5  242.54  4807.2  243.69  4817.3  242.38  4827.5  239.03  4840.1  241.83
  4857.8  239.78  4878.1  240.78  4897.8  243.93  4928.7  243.39  4938.8  244.25
  5002.9  243.17  5017.1  238.55  5017.6  238.05  5024.5  238.55  5027.6   240.7
  5041.8  243.51  5112.3  245.27  5242.4  247.61  5509.2   252.5  5813.5  261.79
#Mann= 8 ,-1 , 0
  3380.1     .12       0  4158.9     .07       0    4270     .05       0
  4643.7      .1       0  5017.1     .05       0  5024.5      .1       0
  5112.3     .07       0  5242.4     .05       0
Bank Sta=5017.1,5024.5
XS Rating Curve= 0 ,0
Exp/Cntr=0.3,0.1

Type RM Length L Ch R = 1 ,3599    ,419,419,419
BEGIN DESCRIPTION:
Stream0748 4.0
END DESCRIPTION:
XS GIS Cut Line= 3
        2464425.     13672875.01        2464525.       13674075.
        2464625.     13674975.01
#Sta/Elev= 30
  3791.6  254.51  3932.1  251.55  4042.5   250.8  4142.8  248.34    4284  246.76
    4468  244.14  4597.2  243.34  4612.7  243.39  4753.1  243.14  4837.1  242.64
  4875.3  243.17    4933  241.96  4938.1  242.88  4965.7  239.48    4982  238.55
  4982.5  238.05  4989.4  238.55  4993.2   240.3  5025.9  242.92  5176.9  241.66
  5227.2  243.38  5257.4  242.81  5277.5  244.35  5287.5  242.87  5307.7  242.37
  5439.5  242.91  5700.1  248.55  5810.7  252.04  5830.9  251.59  5901.3  253.32
#Mann= 10 ,-1 , 0
  3791.6     .12       0    4284     .07       0    4468     .05       0
  4597.2     .07       0  4612.7     .05       0  4753.1     .12       0
  4837.1      .1       0    4982     .05       0  4989.4      .1       0
  5439.5     .07       0
Bank Sta=4982,4989.4
XS Rating Curve= 0 ,0
Exp/Cntr=0.3,0.1

Type RM Length L Ch R = 1 ,3180    ,457,457,457
BEGIN DESCRIPTION:
Stream0748 3.0
END DESCRIPTION:
XS GIS Cut Line= 3
      2463375.03     13672975.04        2464175.       13674175.
      2464524.99     13674924.98
#Sta/Elev= 30
  3562.9  256.72  3873.8  250.03  4149.9  246.96  4412.4  243.95  4642.7  242.05
  4709.1  241.43  4724.1  240.49  4726.4  238.21  4726.9  237.71  4733.8  238.21
  4745.2  240.45  4882.7  241.99  4919.4  242.54  4925.4   242.2    4933  239.48
  4955.5  242.64  4980.8  242.41  5013.1  241.02  5036.6  242.19  5207.6  242.61
  5236.8  240.92  5276.2  242.12  5336.1  240.97  5367.7  241.78  5402.3  239.89
    5435  241.44  5479.6   244.6  5658.5  248.66  5675.9  250.14  5832.7  252.54
#Mann= 10 ,-1 , 0
  3562.9     .05       0  4149.9     .07       0  4412.4     .05       0
  4642.7     .12       0  4726.4     .05       0  4733.8     .12       0
  4882.7      .1       0  4980.8     .12       0  5013.1      .1       0
    5435     .07       0
Bank Sta=4726.4,4733.8
XS Rating Curve= 0 ,0
Exp/Cntr=0.3,0.1

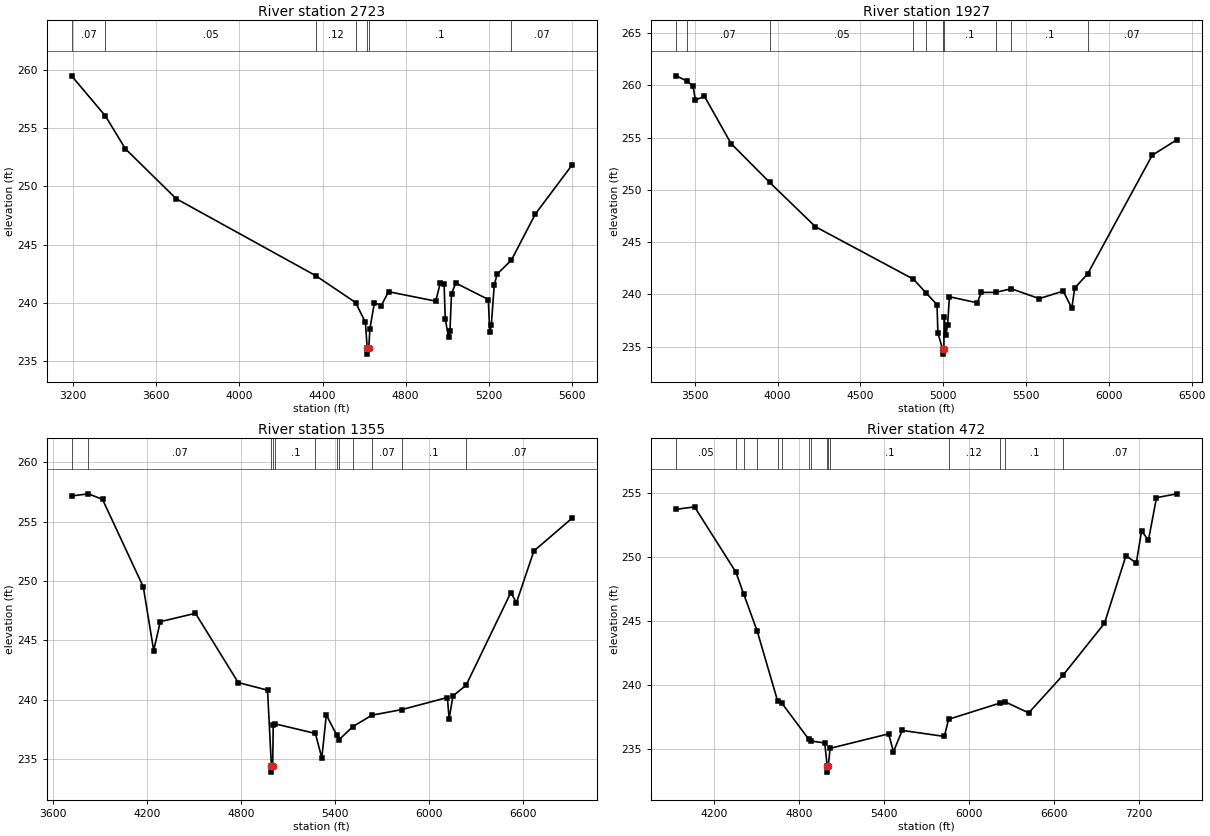
Type RM Length L Ch R = 1 ,2723    ,796,796,796
BEGIN DESCRIPTION:
Stream0748 2.0
END DESCRIPTION:
XS GIS Cut Line= 3
       2463296.7      13672870.3        2464025.       13674525.
      2464475.02     13674925.02
#Sta/Elev= 30
  3191.9   259.5  3354.8  256.05  3451.1  253.23  3695.4  248.95  4368.2  242.33
  4559.4  240.03  4606.5  238.33  4615.2   236.1  4615.7   235.6  4622.7   236.1
  4628.3   237.8  4650.2  240.03  4682.9  239.76  4717.8  240.96  4945.2  240.15
  4967.5  241.74  4985.4  241.61  4990.9  238.64  5006.9  237.03  5013.6  237.55
  5021.1   240.8    5042   241.7  5198.4  240.29  5205.1  237.47  5212.6  238.06
  5226.8  241.53  5240.6  242.47  5309.6  243.68    5425  247.64  5601.9  251.85
#Mann= 7 ,-1 , 0
  3191.9     .07       0  3354.8     .05       0  4368.2     .12       0
  4559.4      .1       0  4615.2     .05       0  4622.7      .1       0
  5309.6     .07       0
Bank Sta=4615.2,4622.7
XS Rating Curve= 0 ,0
Exp/Cntr=0.3,0.1

Type RM Length L Ch R = 1 ,1927    ,572,572,572
BEGIN DESCRIPTION:
XS7637
END DESCRIPTION:
XS GIS Cut Line= 3
      2463149.12      13672774.8      2463765.45     13674701.91
      2464676.94     13675109.91
#Sta/Elev= 30
  3388.7  260.91  3451.3  260.42  3489.4  259.95  3504.4  258.59  3558.9  258.95
  3719.7  254.43  3952.9  250.71  4228.8  246.48  4820.4  241.46  4895.4  240.17
  4962.9  239.02  4968.2  236.29  4996.4  234.79  4996.9  234.29  5004.2  234.79
  5005.7  237.86  5016.2  236.09  5026.7  237.07  5037.7  239.78  5205.2   239.2
  5230.7  240.19  5316.7   240.2  5412.1  240.54    5580   239.6  5724.6  240.32
  5776.5  238.69  5794.2  240.61  5872.7  241.98  6262.3  253.32  6410.6  254.79
#Mann= 10 ,-1 , 0
  3388.7     .12       0  3451.3     .07       0  3952.9     .05       0
  4820.4     .12       0  4895.4      .1       0  4996.4     .05       0
  5004.2      .1       0  5316.7     .07       0  5412.1      .1       0
  5872.7     .07       0
Bank Sta=4996.4,5004.2
XS Rating Curve= 0 ,0
Exp/Cntr=0.3,0.1

Type RM Length L Ch R = 1 ,1355    ,883,883,883
BEGIN DESCRIPTION:
XS7636
END DESCRIPTION:
XS GIS Cut Line= 3
      2462402.62     13673321.73      2463322.74     13674675.87
      2464780.57     13675213.87
#Sta/Elev= 30
  3719.7  257.17  3827.3  257.35  3917.1  256.88    4177   249.5  4243.2  244.14
  4285.1  246.57  4509.5  247.28  4782.1  241.44  4968.9   240.8  4993.7  234.39
  4994.2  233.89  5001.6  234.39  5005.2  237.84  5019.7  237.95    5274  237.15
    5315  235.08  5343.7  238.71  5409.5  237.03  5425.7  236.63  5513.3  237.73
    5634  238.69  5824.8  239.16  6115.3  240.18  6126.7  238.39    6151  240.32
  6234.7  241.21    6520  249.03  6555.7  248.17  6666.8  252.53  6910.8   255.3
#Mann= 12 ,-1 , 0
  3719.7    .035       0  3827.3     .07       0  4993.7     .05       0
  5001.6     .07       0  5019.7      .1       0    5274     .07       0
  5409.5     .12       0  5425.7     .07       0  5513.3     .12       0
    5634     .07       0  5824.8      .1       0  6234.7     .07       0
Bank Sta=4993.7,5001.6
XS Rating Curve= 0 ,0
Exp/Cntr=0.3,0.1

Type RM Length L Ch R = 1 ,472     ,0,0,0
BEGIN DESCRIPTION:
Stream0748 1.0
END DESCRIPTION:
XS GIS Cut Line= 3
       2461768.9     13673868.55      2462680.38     13674771.35
      2464875.02       13675275.
#Sta/Elev= 30
  3933.4  253.74  4062.5  253.93  4354.9  248.82  4408.9  247.14  4505.5   244.2
  4649.7  238.74  4678.3   238.6  4870.4  235.75  4883.8  235.63  4981.8  235.48
  4998.9   233.7  4999.4   233.2    5007   233.7  5019.7  235.06  5432.6  236.19
  5467.3   234.8  5528.8  236.46  5826.4  235.99  5856.4  237.33  6220.1   238.6
  6255.9  238.69    6422  237.83  6667.6  240.82    6957  244.83  7108.9  250.12
  7181.6  249.54  7219.3  252.06  7267.4  251.31  7324.3  254.65    7468  254.95
#Mann= 15 ,-1 , 0
  3933.4     .05       0  4354.9     .12       0  4408.9     .07       0
  4505.5     .12       0  4649.7     .07       0  4678.3     .12       0
  4870.4     .07       0  4883.8     .12       0  4998.9     .05       0
    5007     .12       0  5019.7      .1       0  5856.4     .12       0
  6220.1     .07       0  6255.9      .1       0  6667.6     .07       0
Bank Sta=4998.9,5007
XS Rating Curve= 0 ,0
Exp/Cntr=0.3,0.1

Chan Stop Cuts=-1
Use User Specified Reach Order=0
Composite Channel Slope=5