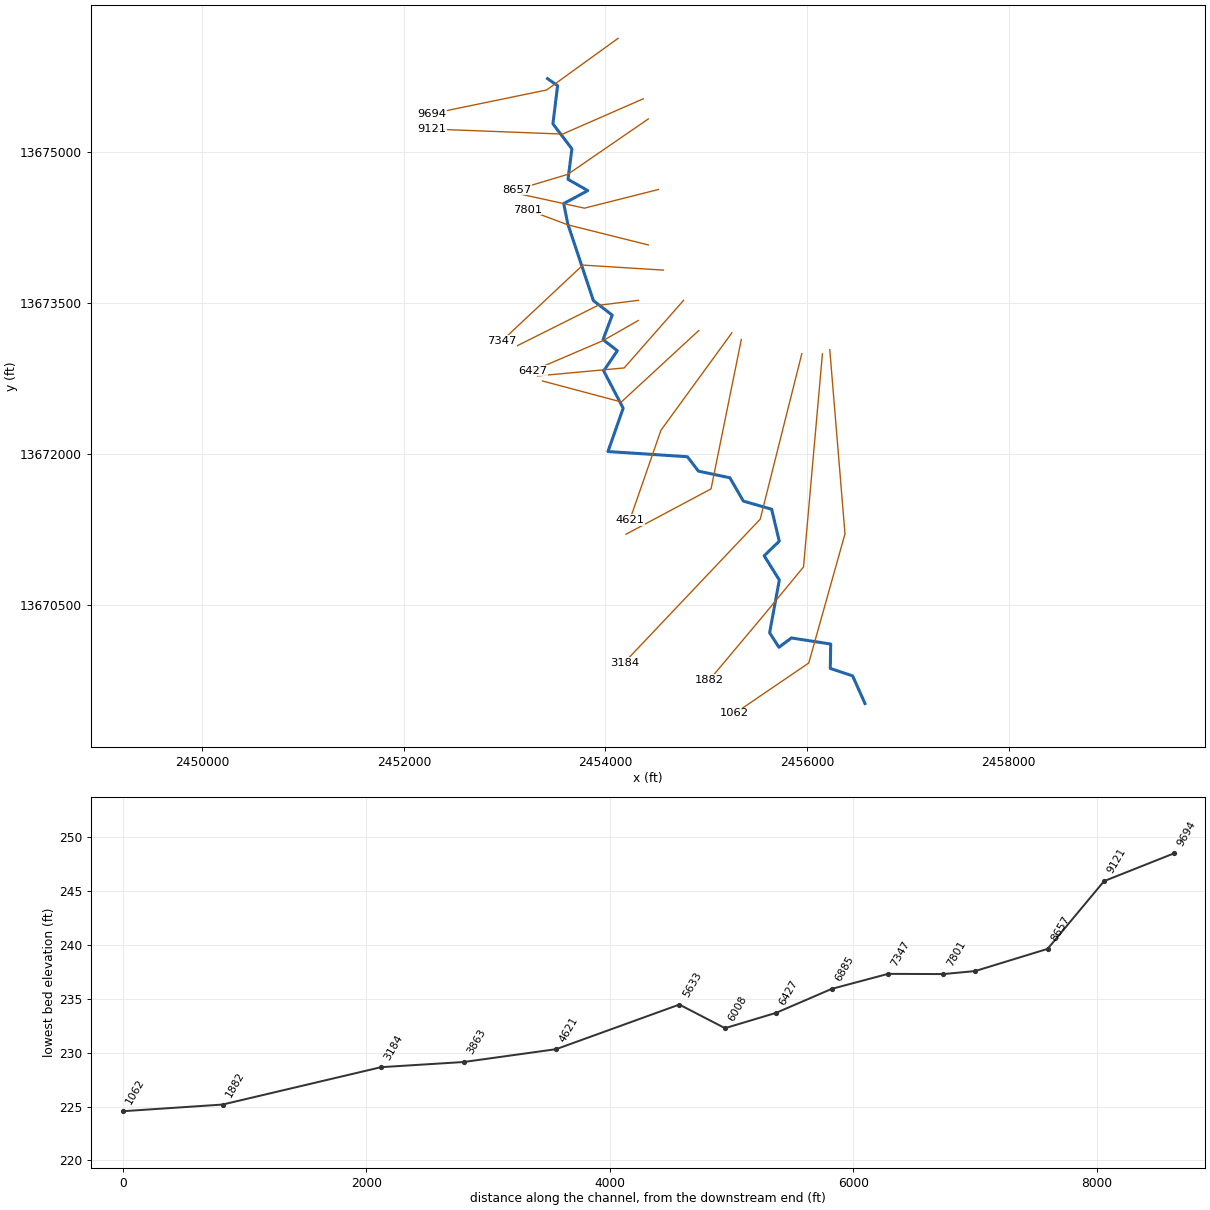
--- Stream0749.prj (project) ---

Proj Title=Stream0749 Base Level Engineering
Current Plan=p01
Default Exp/Contr=0.3,0.1
English Units
Geom File=g01
Flow File=f01
Plan File=p01
BEGIN DESCRIPTION:
Stream0749
END DESCRIPTION:

--- Stream0749.p01 (plan) ---

Plan Title=Multiple Run
Short Identifier=Multiple
Geom File=g01
Flow File=f01
Subcritical Flow
K Sum by GR= 0
Std Step Tol= 0.01
Critical Tol= 0.01
Num of Std Step Trials= 20
Max Error Tol= 0.3
Flow Tol Ratio= 0.001
Split Flow NTrial= 30
Split Flow Tol= 0.02
Split Flow Ratio= 0.02
Log Output Level= 0
Friction Slope Method= 1
Unsteady Friction Slope Method= 2
Unsteady Bridges Friction Slope Method= 1
Parabolic Critical Depth
Global Vel Dist=  1 , 1 , 1
Global Log Level= 0
CheckData=True
Encroach Param= -1, 0, 0, 0
BEGIN DESCRIPTION:
Multiple Run
END DESCRIPTION:

--- Stream0749.f01 (steady flow) ---

Flow Title=Multiple
Number of Profiles=7
Profile Names=10-year,25-year,50-year,1pct_min,100-year,1pct_plu,500-year
River Rch & RM= Stream0749,Reach-1,9694
     729    1177    1581    1029    2052    4095    3423
River Rch & RM= Stream0749,Reach-1,8657
     834    1353    1823    1189    2372    4733    3976
River Rch & RM= Stream0749,Reach-1,4621
    1172    1933    2633    1733    3458    6900    5910
River Rch & RM= Stream0749,Reach-1,1062
    1244    2053    2800    1844    3679    7340    6294
Boundary for River Rch & Prof#=Stream0749,Reach-1,1
Up Type=0
Dn Type=3
Dn Slope=0.005
Boundary for River Rch & Prof#=Stream0749,Reach-1,2
Up Type=0
Dn Type=3
Dn Slope=0.005
Boundary for River Rch & Prof#=Stream0749,Reach-1,3
Up Type=0
Dn Type=3
Dn Slope=0.005
Boundary for River Rch & Prof#=Stream0749,Reach-1,4
Up Type=0
Dn Type=3
Dn Slope=0.005
Boundary for River Rch & Prof#=Stream0749,Reach-1,5
Up Type=0
Dn Type=3
Dn Slope=0.005
Boundary for River Rch & Prof#=Stream0749,Reach-1,6
Up Type=0
Dn Type=3
Dn Slope=0.005
Boundary for River Rch & Prof#=Stream0749,Reach-1,7
Up Type=0
Dn Type=3
Dn Slope=0.005

--- Stream0749.g01 (geometry) ---

Geom Title=Existing Conditions

River Reach=Stream0749,Reach-1
Reach XY= 30
      2453425.00     13675725.00      2453525.01     13675654.86
      2453478.53     13675276.45      2453666.92     13675028.31
      2453628.44     13674726.22      2453824.68     13674614.14
      2453585.81     13674485.37      2453626.67     13674281.05
      2453880.36     13673522.30      2454067.41     13673378.35
      2453975.97     13673135.29      2454117.80     13673025.30
      2453982.30     13672825.08      2454175.68     13672454.92
      2454025.00     13672025.00      2454813.17     13671973.38
      2454922.56     13671830.40      2455234.70     13671764.23
      2455368.50     13671532.73      2455649.04     13671452.33
      2455724.51     13671135.49      2455574.87     13670990.42
      2455725.42     13670750.00      2455628.75     13670226.55
      2455721.41     13670082.49      2455844.98     13670175.03
      2456235.25     13670114.56      2456230.69     13669872.43
      2456452.33     13669799.02      2456575.00     13669525.00

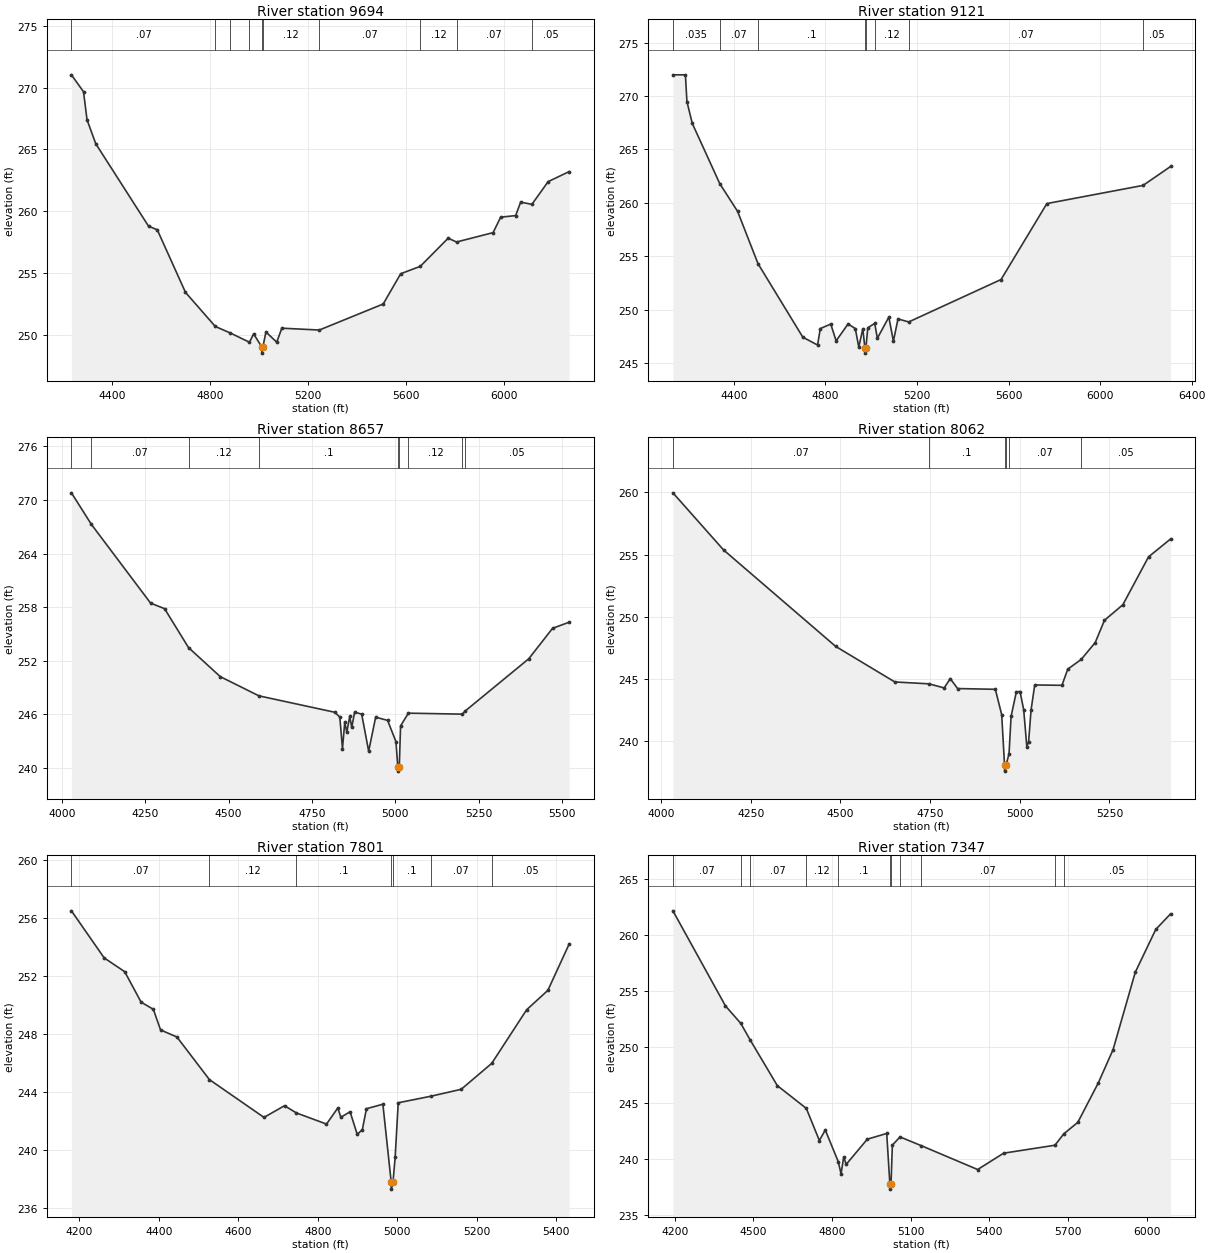
Type RM Length L Ch R = 1,9694,573,573,573
BEGIN DESCRIPTION:
Stream0749 16.0
END DESCRIPTION:
XS GIS Cut Line= 3
      2454124.99     13676125.00      2453416.33     13675612.71
      2452281.15     13675378.17
#Sta/Elev= 30
  4232.2  271.04  4281.6  269.67  4296.0  267.40  4331.6  265.46  4547.4  258.78
  4583.0  258.49  4698.3  253.42  4820.1  250.66  4881.4  250.13  4959.8  249.38
  4976.7  250.06  5010.1  249.00  5010.4  248.50  5014.5  249.00  5027.0  250.21
  5071.1  249.39  5092.0  250.52  5245.0  250.37  5506.2  252.48  5577.7  254.93
  5657.8  255.53  5771.7  257.81  5805.8  257.50  5955.3  258.26  5986.2  259.51
  6047.4  259.64  6067.9  260.73  6113.8  260.55  6180.2  262.39  6265.8  263.20
#Mann=10,-1,0
  4232.2    0.07       0  4820.1    0.12       0  4881.4     0.1       0
  4959.8    0.12       0  5010.1    0.05       0  5014.5    0.12       0
  5245.0    0.07       0  5657.8    0.12       0  5805.8    0.07       0
  6113.8    0.05       0
Bank Sta=5010.1,5014.5
Exp/Cntr=0.3,0.1

Type RM Length L Ch R = 1,9121,464,464,464
BEGIN DESCRIPTION:
Stream0749 15.0
END DESCRIPTION:
XS GIS Cut Line= 3
      2454375.01     13675525.01      2453575.00     13675175.00
      2452274.99     13675225.00
#Sta/Elev= 30
  4133.7  271.98  4188.3  271.98  4194.9  269.48  4218.3  267.43  4338.5  261.79
  4416.3  259.20  4505.5  254.30  4701.3  247.42  4765.6  246.69  4777.7  248.23
  4823.3  248.65  4846.7  247.08  4898.9  248.66  4930.5  248.23  4945.7  246.49
  4963.3  248.22  4972.4  246.43  4972.7  245.93  4976.8  246.43  4985.1  248.30
  5015.3  248.71  5026.9  247.32  5077.0  249.30  5097.0  247.05  5117.0  249.13
  5163.9  248.85  5567.3  252.82  5767.5  259.93  6187.7  261.63  6307.9  263.40
#Mann=8,-1,0
  4133.7   0.035       0  4338.5    0.07       0  4505.5     0.1       0
  4972.4    0.05       0  4976.8     0.1       0  5015.3    0.12       0
  5163.9    0.07       0  6187.7    0.05       0
Bank Sta=4972.4,4976.8
Exp/Cntr=0.3,0.1

Type RM Length L Ch R = 1,8657,595,595,595
BEGIN DESCRIPTION:
Stream0749 14.0
END DESCRIPTION:
XS GIS Cut Line= 3
      2454425.01     13675325.01      2453625.00     13674775.00
      2453124.96     13674624.99
#Sta/Elev= 30
  4028.7  270.80  4088.7  267.26  4266.2  258.45  4308.1  257.83  4380.0  253.47
  4475.2  250.22  4591.1  248.07  4818.9  246.23  4833.8  245.69  4841.8  242.16
  4848.7  245.15  4854.7  243.99  4863.6  245.77  4869.6  244.54  4878.2  246.24
  4899.4  246.02  4920.4  241.87  4941.3  245.68  4977.2  245.32  5002.2  242.94
  5007.7  240.14  5008.1  239.64  5012.2  240.14  5016.1  244.71  5039.6  246.13
  5201.7  246.02  5209.2  246.35  5400.6  252.22  5472.0  255.63  5521.6  256.31
#Mann=9,-1,0
  4028.7   0.035       0  4088.7    0.07       0  4380.0    0.12       0
  4591.1     0.1       0  5007.7    0.05       0  5012.2     0.1       0
  5039.6    0.12       0  5201.7    0.07       0  5209.2    0.05       0
Bank Sta=5007.7,5012.2
Exp/Cntr=0.3,0.1

Type RM Length L Ch R = 1,8062,261,261,261
BEGIN DESCRIPTION:
Stream0749 13.0
END DESCRIPTION:
XS GIS Cut Line= 3
      2454524.97     13674624.99      2453791.61     13674439.96
      2453174.97     13674575.01
#Sta/Elev= 30
  4032.8  259.96  4173.9  255.37  4486.6  247.61  4651.6  244.75  4746.8  244.60
  4789.1  244.27  4806.1  245.02  4826.6  244.22  4931.8  244.16  4949.5  242.12
  4957.4  238.08  4957.8  237.58  4962.0  238.08  4970.0  238.99  4975.7  241.98
  4990.4  243.96  5000.6  243.98  5010.9  242.51  5019.5  239.56  5024.6  239.95
  5031.4  242.50  5041.6  244.51  5117.5  244.48  5133.7  245.78  5171.1  246.56
  5210.3  247.92  5236.1  249.71  5287.3  250.96  5358.9  254.81  5420.4  256.25
#Mann=6,-1,0
  4032.8    0.07       0  4746.8     0.1       0  4957.4    0.05       0
  4962.0     0.1       0  4970.0    0.07       0  5171.1    0.05       0
Bank Sta=4957.4,4962
Exp/Cntr=0.3,0.1

Type RM Length L Ch R = 1,7801,454,454,454
BEGIN DESCRIPTION:
Stream0749 12.0
END DESCRIPTION:
XS GIS Cut Line= 3
      2454424.98     13674075.00      2453625.00     13674275.00
      2453225.00     13674425.00
#Sta/Elev= 30
  4180.1  256.51  4262.5  253.26  4314.1  252.31  4355.3  250.21  4386.2  249.71
  4404.3  248.29  4445.5  247.80  4527.2  244.86  4664.5  242.25  4716.1  243.06
  4745.9  242.56  4821.7  241.79  4850.1  242.90  4857.8  242.26  4881.0  242.64
  4899.0  241.08  4911.9  241.41  4922.2  242.85  4963.5  243.16  4984.4  237.80
  4984.7  237.30  4989.0  237.80  4994.4  239.49  5002.1  243.26  5083.8  243.71
  5160.5  244.19  5237.3  245.98  5325.1  249.68  5378.5  251.02  5431.9  254.21
#Mann=7,-1,0
  4180.1    0.07       0  4527.2    0.12       0  4745.9     0.1       0
  4984.4    0.05       0  4989.0     0.1       0  5083.8    0.07       0
  5237.3    0.05       0
Bank Sta=4984.4,4989
Exp/Cntr=0.3,0.1

Type RM Length L Ch R = 1,7347,462,462,462
BEGIN DESCRIPTION:
Stream0749 11.0
END DESCRIPTION:
XS GIS Cut Line= 3
      2454575.03     13673825.00      2453775.00     13673875.00
      2452974.98     13673124.98
#Sta/Elev= 30
  4193.4  262.17  4393.8  253.68  4452.0  252.13  4487.6  250.66  4591.7  246.56
  4702.2  244.53  4752.0  241.66  4774.6  242.60  4824.2  239.76  4834.7  238.69
  4844.7  240.17  4854.7  239.54  4934.9  241.78  5008.9  242.29  5020.8  237.82
  5021.1  237.32  5025.4  237.82  5030.4  241.25  5059.6  241.98  5140.8  241.20
  5355.7  239.07  5454.9  240.53  5650.5  241.24  5684.4  242.26  5737.7  243.28
  5815.8  246.80  5872.3  249.78  5957.0  256.69  6035.1  260.51  6091.6  261.90
#Mann=11,-1,0
  4193.4    0.07       0  4452.0    0.05       0  4487.6    0.07       0
  4702.2    0.12       0  4824.2     0.1       0  5020.8    0.05       0
  5025.4     0.1       0  5059.6    0.05       0  5140.8    0.07       0
  5650.5   0.035       0  5684.4    0.05       0
Bank Sta=5020.8,5025.4
Exp/Cntr=0.3,0.1

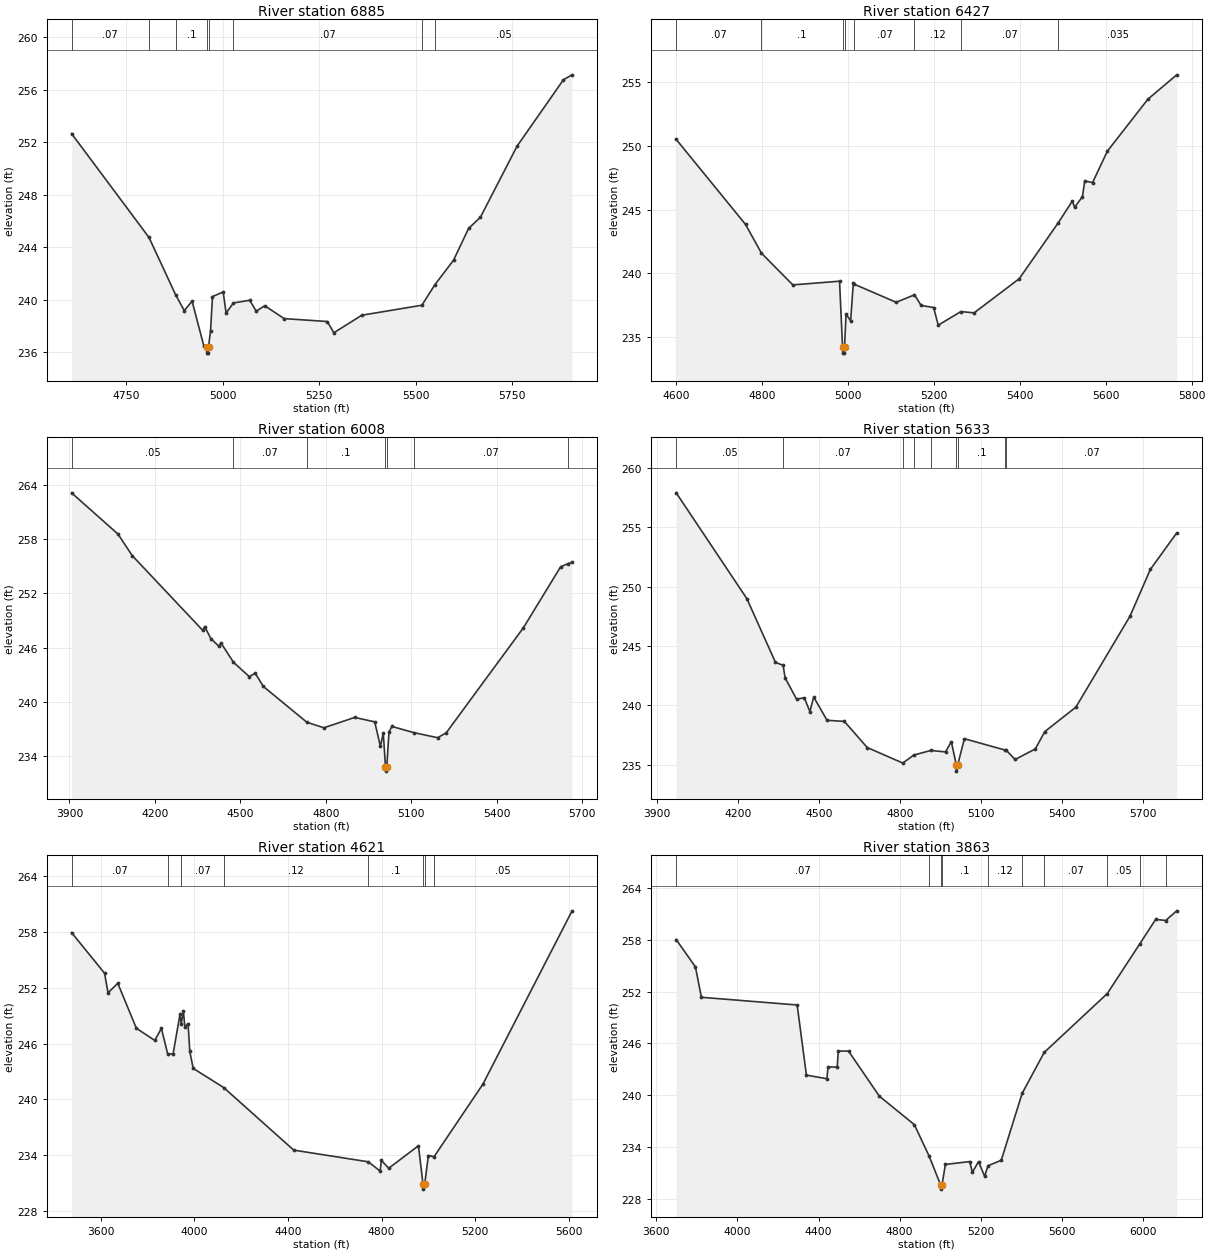
Type RM Length L Ch R = 1,6885,458,458,458
BEGIN DESCRIPTION:
Stream0749 10.0
END DESCRIPTION:
XS GIS Cut Line= 3
      2454324.98     13673525.00      2453925.00     13673475.00
      2453125.02     13673075.01
#Sta/Elev= 30
  4608.1  252.66  4808.7  244.75  4878.3  240.35  4900.3  239.17  4920.5  239.89
  4950.7  236.51  4958.5  236.43  4958.8  235.93  4962.8  235.93  4963.2  236.43
  4968.4  237.64  4973.4  240.24  5001.1  240.59  5008.7  238.98  5027.5  239.75
  5069.9  239.96  5086.7  239.13  5109.0  239.54  5159.3  238.56  5271.1  238.34
  5287.9  237.48  5360.6  238.82  5516.2  239.58  5550.3  241.16  5598.2  243.01
  5637.3  245.43  5668.0  246.29  5763.1  251.71  5883.3  256.77  5905.6  257.14
#Mann=8,-1,0
  4608.1    0.07       0  4808.7    0.12       0  4878.3     0.1       0
  4958.5    0.05       0  4963.2     0.1       0  5027.5    0.07       0
  5516.2   0.035       0  5550.3    0.05       0
Bank Sta=4958.5,4963.2
Exp/Cntr=0.3,0.1

Type RM Length L Ch R = 1,6427,419,419,419
BEGIN DESCRIPTION:
Stream0749 9.0
END DESCRIPTION:
XS GIS Cut Line= 3
      2454325.02     13673325.01      2453975.00     13673125.00
      2453275.01     13672825.00
#Sta/Elev= 30
  4600.6  250.52  4761.9  243.83  4799.1  241.56  4872.0  239.07  4980.7  239.36
  4987.7  234.20  4988.1  233.70  4992.1  233.70  4992.4  234.20  4995.8  236.78
  5006.5  236.24  5012.8  239.25  5015.2  239.12  5112.5  237.70  5155.1  238.29
  5170.6  237.45  5199.6  237.29  5210.4  235.90  5263.1  236.97  5293.9  236.87
  5399.0  239.56  5489.7  243.96  5522.3  245.66  5527.8  245.18  5545.9  246.01
  5551.3  247.25  5569.5  247.12  5603.9  249.59  5698.2  253.68  5765.3  255.60
#Mann=8,-1,0
  4600.6    0.07       0  4799.1     0.1       0  4987.7    0.05       0
  4992.4     0.1       0  5015.2    0.07       0  5155.1    0.12       0
  5263.1    0.07       0  5489.7   0.035       0
Bank Sta=4987.7,4992.4
Exp/Cntr=0.3,0.1

Type RM Length L Ch R = 1,6008,375,375,375
BEGIN DESCRIPTION:
Stream0749 8.0
END DESCRIPTION:
XS GIS Cut Line= 3
      2454775.00     13673525.00      2454185.65     13672854.41
      2453324.97     13672775.00
#Sta/Elev= 30
  3907.6  263.17  4070.3  258.60  4120.6  256.20  4368.3  247.90  4374.9  248.33
  4396.7  246.98  4425.2  246.13  4431.8  246.52  4476.0  244.36  4531.5  242.77
  4552.3  243.14  4580.8  241.68  4733.4  237.71  4793.3  237.09  4901.4  238.24
  4971.7  237.75  4991.8  235.04  5001.9  236.49  5009.6  232.78  5009.9  232.28
  5014.3  232.78  5021.9  236.62  5032.0  237.24  5108.3  236.56  5192.7  235.99
  5222.8  236.53  5493.9  248.20  5624.5  254.96  5651.0  255.32  5664.7  255.45
#Mann=7,-1,0
  3907.6    0.05       0  4476.0    0.07       0  4733.4     0.1       0
  5009.6    0.05       0  5014.3     0.1       0  5108.3    0.07       0
  5651.0   0.035       0
Bank Sta=5009.6,5014.3
Exp/Cntr=0.3,0.1

Type RM Length L Ch R = 1,5633,1012,1012,1012
BEGIN DESCRIPTION:
Stream0749 7.0
END DESCRIPTION:
XS GIS Cut Line= 3
      2454925.02     13673225.01      2454157.50     13672516.66
      2453375.00     13672725.00
#Sta/Elev= 30
  3971.8  257.91  4233.5  249.00  4339.6  243.63  4368.0  243.38  4375.3  242.32
  4417.8  240.53  4446.2  240.65  4467.1  239.49  4481.3  240.71  4530.6  238.75
  4594.7  238.66  4679.4  236.46  4811.2  235.15  4851.8  235.82  4914.6  236.21
  4969.5  236.09  4991.1  236.95  5009.7  234.97  5010.1  234.47  5014.4  234.97
  5039.5  237.20  5190.8  236.24  5194.8  236.22  5227.3  235.45  5302.3  236.34
  5337.3  237.80  5452.5  239.86  5653.2  247.53  5728.3  251.46  5826.0  254.53
#Mann=9,-1,0
  3971.8    0.05       0  4368.0    0.07       0  4811.2    0.12       0
  4851.8    0.07       0  4914.6     0.1       0  5009.7    0.05       0
  5014.4     0.1       0  5190.8    0.12       0  5194.8    0.07       0
Bank Sta=5009.7,5014.4
Exp/Cntr=0.3,0.1

Type RM Length L Ch R = 1,4621,758,758,758
BEGIN DESCRIPTION:
XS7641
END DESCRIPTION:
XS GIS Cut Line= 3
      2455254.25     13673202.48      2454550.61     13672236.14
      2454241.00     13671344.86
#Sta/Elev= 30
  3474.8  257.95  3615.9  253.57  3630.6  251.46  3672.3  252.49  3751.9  247.64
  3830.4  246.34  3858.6  247.64  3885.8  244.86  3908.8  244.90  3938.1  249.15
  3943.2  248.13  3952.8  249.46  3959.0  247.78  3972.7  248.16  3979.9  245.17
  3994.5  243.33  4125.1  241.26  4424.2  234.53  4742.9  233.27  4793.5  232.27
  4798.8  233.42  4830.2  232.58  4957.2  235.00  4976.8  230.83  4977.3  230.33
  4983.7  230.83  4999.6  233.95  5023.8  233.82  5232.4  241.62  5613.7  260.29
#Mann=8,-1,0
  3474.8    0.07       0  3885.8    0.05       0  3943.2    0.07       0
  4125.1    0.12       0  4742.9     0.1       0  4976.8    0.05       0
  4983.7     0.1       0  5023.8    0.05       0
Bank Sta=4976.8,4983.7
Exp/Cntr=0.3,0.1

Type RM Length L Ch R = 1,3863,679,679,679
BEGIN DESCRIPTION:
XS7640
END DESCRIPTION:
XS GIS Cut Line= 3
      2455348.08     13673136.83      2455047.85     13671654.46
      2454203.50     13671204.14
#Sta/Elev= 30
  3697.7  258.03  3792.6  254.87  3822.0  251.35  4294.5  250.46  4340.1  242.34
  4441.5  241.92  4446.6  243.29  4492.2  243.27  4497.3  245.13  4548.0  245.12
  4700.1  239.90  4872.9  236.60  4945.6  232.96  5002.0  229.64  5002.5  229.14
  5009.1  229.64  5026.0  232.00  5146.1  232.33  5158.6  231.08  5189.2  232.32
  5219.4  230.63  5236.0  231.85  5301.5  232.48  5404.5  240.23  5513.5  244.97
  5824.5  251.78  5985.3  257.55  6063.4  260.37  6112.7  260.24  6167.1  261.36
#Mann=10,-1,0
  3697.7    0.07       0  4945.6     0.1       0  5002.0    0.05       0
  5009.1     0.1       0  5236.0    0.12       0  5404.5    0.05       0
  5513.5    0.07       0  5824.5    0.05       0  5985.3    0.07       0
  6112.7    0.05       0
Bank Sta=5002,5009.1
Exp/Cntr=0.3,0.1

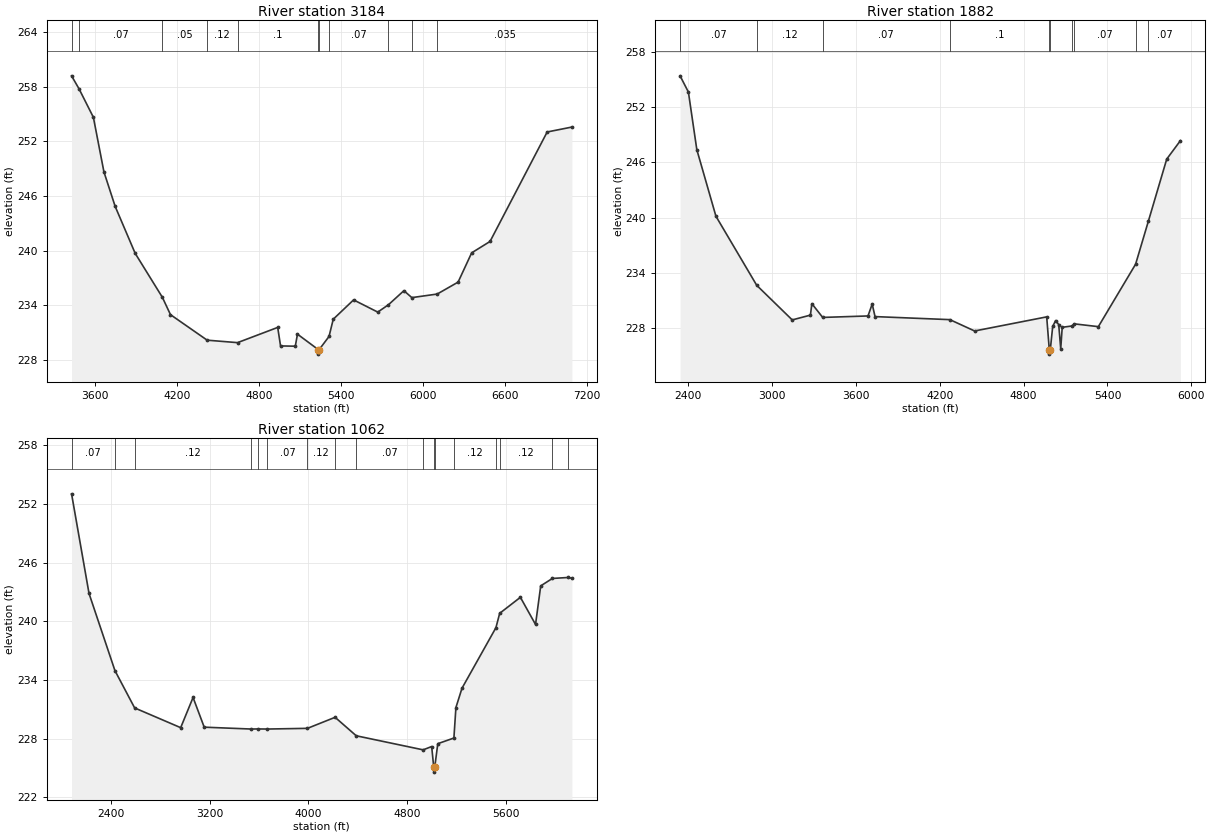
Type RM Length L Ch R = 1,3184,1302,1302,1302
BEGIN DESCRIPTION:
XS7639
END DESCRIPTION:
XS GIS Cut Line= 3
      2455948.52     13672996.10      2455535.71     13671354.24
      2454185.58     13669929.09
#Sta/Elev= 30
  3431.5  259.19  3486.2  257.76  3591.0  254.64  3668.1  248.65  3750.3  244.86
  3896.6  239.71  4094.8  234.90  4154.4  232.99  4422.5  230.19  4644.5  229.92
  4937.9  231.59  4958.7  229.56  5066.4  229.53  5082.4  230.85  5233.9  229.16
  5234.4  228.66  5241.1  229.16  5313.0  230.60  5343.8  232.49  5492.4  234.61
  5669.1  233.27  5747.4  234.08  5860.1  235.62  5918.0  234.86  6103.3  235.25
  6256.1  236.56  6355.2  239.77  6489.5  241.02  6907.0  253.03  7087.6  253.57
#Mann=11,-1,0
  3431.5   0.035       0  3486.2    0.07       0  4094.8    0.05       0
  4422.5    0.12       0  4644.5     0.1       0  5233.9    0.05       0
  5241.1     0.1       0  5313.0    0.07       0  5747.4   0.035       0
  5918.0    0.07       0  6103.3   0.035       0
Bank Sta=5233.9,5241.1
Exp/Cntr=0.3,0.1

Type RM Length L Ch R = 1,1882,820,820,820
BEGIN DESCRIPTION:
E21310
END DESCRIPTION:
XS GIS Cut Line= 4
      2456152.78     13672994.39      2455965.28     13670879.83
      2455574.66     13670405.87      2455032.97     13669760.00
#Sta/Elev= 30
  2342.0  255.37  2401.6  253.61  2461.9  247.36  2598.7  240.14  2890.6  232.65
  3144.5  228.90  3274.6  229.42  3285.1  230.66  3362.5  229.17  3686.6  229.33
  3716.8  230.62  3737.0  229.26  4272.5  228.93  4449.6  227.70  4965.3  229.23
  4983.8  225.69  4984.3  225.19  4991.2  225.69  5008.3  228.19  5029.1  228.83
  5051.3  228.39  5065.7  225.77  5076.4  228.10  5144.7  228.24  5163.9  228.47
  5335.0  228.17  5601.4  234.94  5693.7  239.65  5824.2  246.34  5922.0  248.34
#Mann=10,-1,0
  2342.0    0.07       0  2890.6    0.12       0  3362.5    0.07       0
  4272.5     0.1       0  4983.8    0.05       0  4991.2     0.1       0
  5144.7    0.12       0  5163.9    0.07       0  5601.4   0.035       0
  5693.7    0.07       0
Bank Sta=4983.8,4991.2
Exp/Cntr=0.3,0.1

Type RM Length L Ch R = 1,1062,0,0,0
BEGIN DESCRIPTION:
E21309
END DESCRIPTION:
XS GIS Cut Line= 4
      2456225.70     13673036.08      2456376.74     13671207.95
      2456017.37     13669926.70      2455282.98     13669426.69
#Sta/Elev= 30
  2082.0  253.05  2223.6  242.85  2433.4  234.96  2593.1  231.14  2966.1  229.12
  3066.4  232.21  3156.7  229.17  3536.4  228.98  3589.4  228.99  3668.9  228.98
  3993.1  229.05  4217.2  230.18  4388.4  228.29  4930.4  226.85  4999.6  227.19
  5016.3  225.07  5016.8  224.57  5024.3  225.07  5049.2  227.48  5179.6  228.06
  5196.0  231.18  5245.3  233.16  5520.1  239.35  5550.5  240.82  5718.3  242.46
  5841.0  239.68  5883.0  243.63  5977.5  244.39  6105.9  244.49  6135.5  244.41
#Mann=17,-1,0
  2082.0    0.07       0  2433.4    0.05       0  2593.1    0.12       0
  3536.4    0.07       0  3589.4    0.12       0  3668.9    0.07       0
  3993.1    0.12       0  4217.2   0.035       0  4388.4    0.07       0
  4930.4     0.1       0  5016.3    0.05       0  5024.3     0.1       0
  5179.6    0.12       0  5520.1    0.07       0  5550.5    0.12       0
  5977.5    0.07       0  6105.9    0.12       0
Bank Sta=5016.3,5024.3
Exp/Cntr=0.3,0.1

Chan Stop Cuts=-1