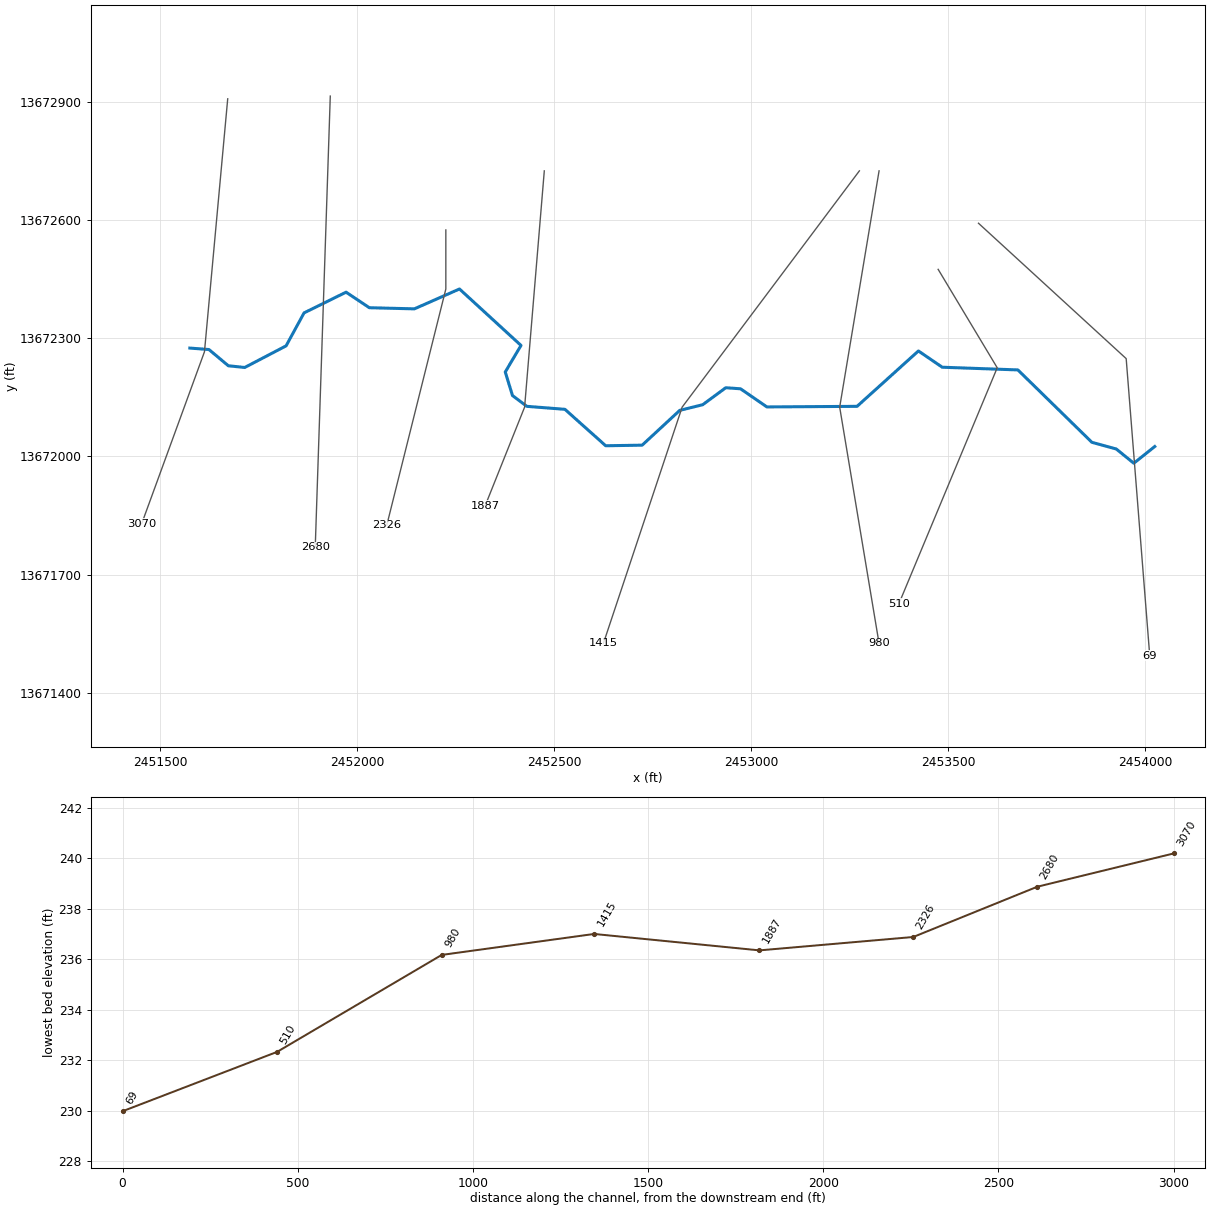
--- Stream0750.prj (project) ---

Proj Title=Stream0750 Base Level Engineering
Current Plan=p01
Default Exp/Contr=0.3,0.1
English Units
Geom File=g01
Flow File=f01
Plan File=p01
BEGIN DESCRIPTION:
Stream0750
END DESCRIPTION:

--- Stream0750.p01 (plan) ---

Plan Title=Multiple Run
Short Identifier=Multiple
Geom File=g01
Flow File=f01
Subcritical Flow
K Sum by GR= 0
Std Step Tol= 0.01
Critical Tol= 0.01
Num of Std Step Trials= 20
Max Error Tol= 0.3
Flow Tol Ratio= 0.001
Split Flow NTrial= 30
Split Flow Tol= 0.02
Split Flow Ratio= 0.02
Log Output Level= 0
Friction Slope Method= 1
Unsteady Friction Slope Method= 2
Unsteady Bridges Friction Slope Method= 1
Parabolic Critical Depth
Global Vel Dist=  1 , 1 , 1
Global Log Level= 0
CheckData=True
Encroach Param= -1, 0, 0, 0
BEGIN DESCRIPTION:
Multiple Run
END DESCRIPTION:

--- Stream0750.f01 (steady flow) ---

Flow Title=Multiple
Number of Profiles=7
Profile Names=10-year,25-year,50-year,1pct_min,100-year,1pct_plu,500-year
River Rch & RM= Stream0750,Reach-1,3070
     605     970    1296     840    1677    3345    2774
Boundary for River Rch & Prof#=Stream0750,Reach-1,1
Up Type=0
Dn Type=3
Dn Slope=0.005
Boundary for River Rch & Prof#=Stream0750,Reach-1,2
Up Type=0
Dn Type=3
Dn Slope=0.005
Boundary for River Rch & Prof#=Stream0750,Reach-1,3
Up Type=0
Dn Type=3
Dn Slope=0.005
Boundary for River Rch & Prof#=Stream0750,Reach-1,4
Up Type=0
Dn Type=3
Dn Slope=0.005
Boundary for River Rch & Prof#=Stream0750,Reach-1,5
Up Type=0
Dn Type=3
Dn Slope=0.005
Boundary for River Rch & Prof#=Stream0750,Reach-1,6
Up Type=0
Dn Type=3
Dn Slope=0.005
Boundary for River Rch & Prof#=Stream0750,Reach-1,7
Up Type=0
Dn Type=3
Dn Slope=0.005

--- Stream0750.g01 (geometry) ---

Geom Title=Existing Conditions

River Reach=Stream0750,Reach-1
Reach XY= 30
      2451575.00     13672275.00      2451623.51     13672271.31
      2451672.75     13672230.11      2451714.34     13672225.71
      2451819.38     13672280.62      2451865.03     13672364.33
      2451971.68     13672416.96      2452030.86     13672377.45
      2452145.14     13672374.62      2452259.66     13672425.05
      2452415.85     13672281.73      2452375.87     13672214.31
      2452394.23     13672154.43      2452430.66     13672127.08
      2452527.42     13672119.46      2452630.90     13672026.97
      2452723.50     13672028.47      2452818.95     13672116.84
      2452877.19     13672131.18      2452935.68     13672174.25
      2452973.26     13672171.63      2453040.21     13672125.54
      2453269.15     13672127.06      2453424.90     13672267.68
      2453485.43     13672226.39      2453677.45     13672219.54
      2453865.32     13672035.75      2453927.31     13672018.70
      2453971.80     13671982.58      2454025.00     13672025.00

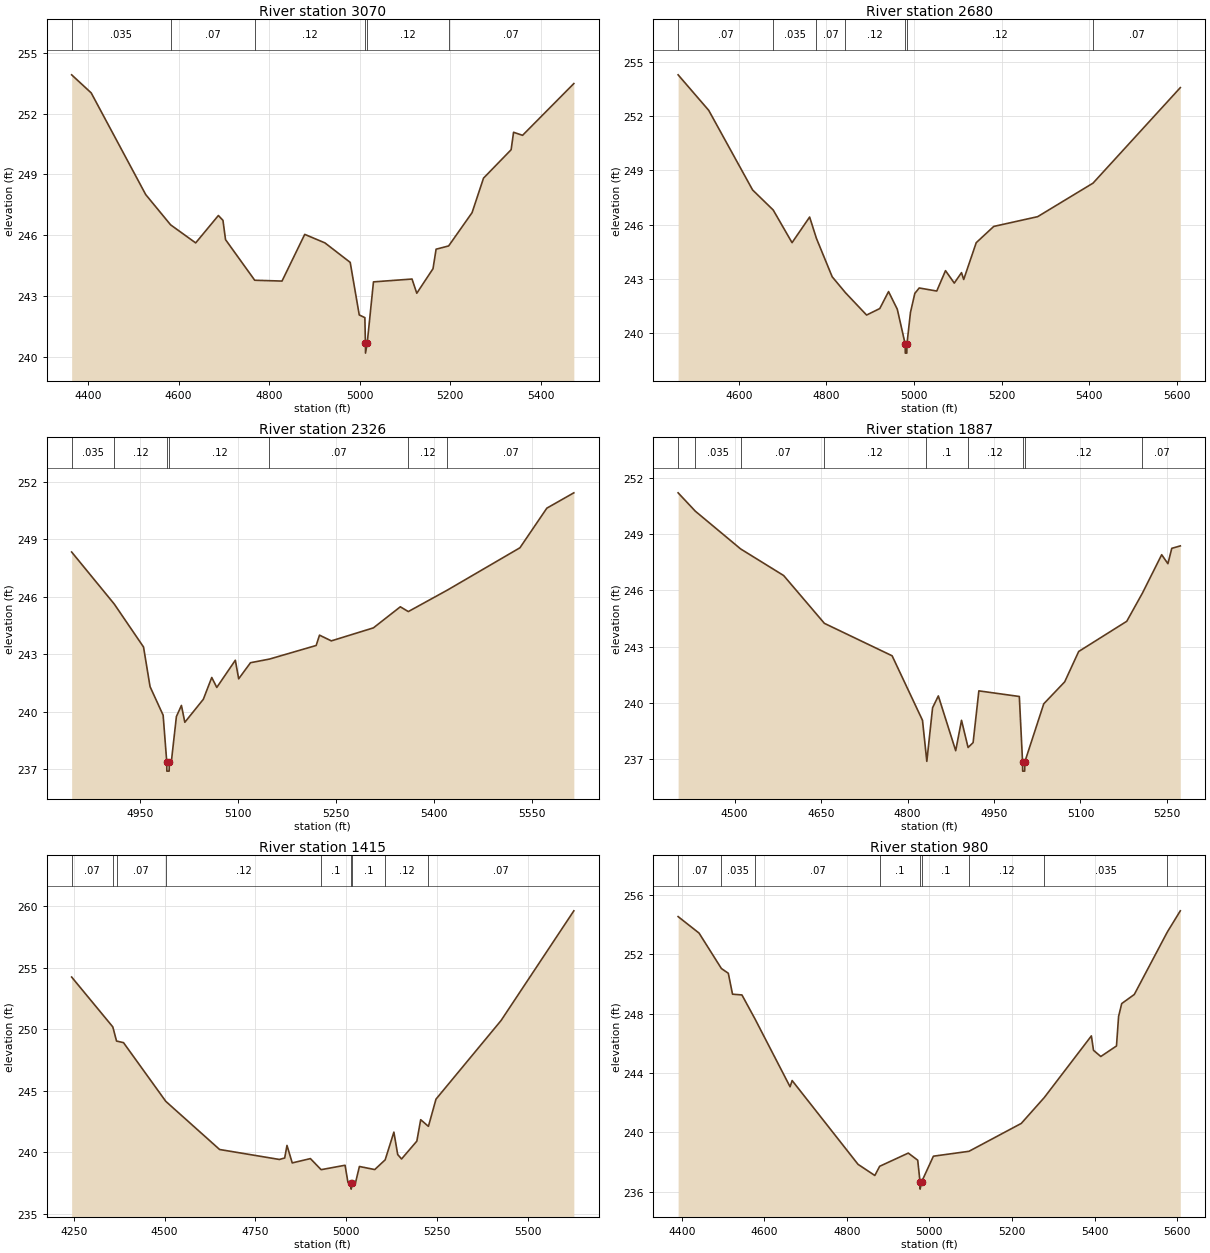
Type RM Length L Ch R = 1,3070,390,390,390
BEGIN DESCRIPTION:
XS7643
END DESCRIPTION:
XS GIS Cut Line= 3
      2451671.18     13672907.97      2451612.15     13672265.63
      2451452.77     13671829.06
#Sta/Elev= 30
  4363.5  253.91  4406.7  253.02  4527.2  248.01  4582.2  246.52  4637.6  245.63
  4687.8  246.98  4697.9  246.74  4703.6  245.79  4768.1  243.79  4828.4  243.75
  4878.6  246.05  4923.3  245.63  4979.1  244.67  4999.1  242.08  5011.5  241.95
  5012.7  240.70  5012.9  240.20  5016.7  240.70  5030.5  243.71  5115.7  243.85
  5126.2  243.15  5162.1  244.36  5168.9  245.32  5196.6  245.48  5248.4  247.12
  5273.7  248.82  5334.7  250.22  5340.1  251.08  5360.0  250.93  5473.3  253.48
#Mann=6,-1,0
  4363.5   0.035       0  4582.2    0.07       0  4768.1    0.12       0
  5012.7    0.05       0  5016.7    0.12       0  5196.6    0.07       0
Bank Sta=5012.7,5016.7
Exp/Cntr=0.3,0.1

Type RM Length L Ch R = 1,2680,354,354,354
BEGIN DESCRIPTION:
XS7644
END DESCRIPTION:
XS GIS Cut Line= 2
      2451931.60     13672914.90      2451893.42     13671769.53
#Sta/Elev= 30
  4461.6  254.30  4531.5  252.33  4631.6  247.92  4678.6  246.81  4721.6  245.00
  4761.7  246.42  4777.2  245.24  4813.2  243.11  4843.4  242.23  4891.7  240.99
  4921.8  241.35  4941.8  242.29  4961.8  241.31  4979.8  239.38  4980.0  238.88
  4983.5  238.88  4983.8  239.38  4991.8  241.13  5001.8  242.19  5011.8  242.49
  5051.8  242.32  5071.8  243.45  5091.8  242.76  5108.3  243.34  5113.3  242.96
  5141.9  245.00  5181.9  245.90  5282.0  246.44  5408.5  248.30  5607.6  253.59
#Mann=7,-1,0
  4461.6    0.07       0  4678.6   0.035       0  4777.2    0.07       0
  4843.4    0.12       0  4979.8    0.05       0  4983.8    0.12       0
  5408.5    0.07       0
Bank Sta=4979.8,4983.8
Exp/Cntr=0.3,0.1

Type RM Length L Ch R = 1,2326,439,439,439
BEGIN DESCRIPTION:
Stream0750 5.0
END DESCRIPTION:
XS GIS Cut Line= 3
      2452225.00     13672574.99      2452225.00     13672425.00
      2452074.99     13671824.96
#Sta/Elev= 30
  4845.0  248.33  4910.3  245.61  4955.0  243.37  4965.0  241.30  4985.0  239.81
  4990.5  237.39  4990.7  236.89  4994.2  236.89  4994.5  237.39  4997.6  237.39
  5005.3  239.74  5013.0  240.32  5018.2  239.44  5046.5  240.64  5059.4  241.78
  5067.1  241.26  5095.5  242.68  5100.6  241.71  5118.7  242.55  5147.7  242.74
  5219.2  243.45  5224.3  243.99  5242.4  243.69  5306.8  244.37  5348.0  245.47
  5360.2  245.22  5419.9  246.34  5531.0  248.55  5572.2  250.62  5613.5  251.42
#Mann=7,-1,0
  4845.0   0.035       0  4910.3    0.12       0  4990.5    0.05       0
  4994.5    0.12       0  5147.7    0.07       0  5360.2    0.12       0
  5419.9    0.07       0
Bank Sta=4990.5,4994.5
Exp/Cntr=0.3,0.1

Type RM Length L Ch R = 1,1887,472,472,472
BEGIN DESCRIPTION:
Stream0750 4.0
END DESCRIPTION:
XS GIS Cut Line= 3
      2452475.00     13672724.99      2452425.00     13672125.00
      2452325.01     13671875.02
#Sta/Elev= 30
  4401.9  251.20  4431.8  250.22  4510.3  248.21  4585.0  246.79  4655.7  244.24
  4773.2  242.51  4825.9  239.07  4831.8  237.35  4833.4  236.88  4843.4  239.74
  4853.4  240.37  4883.5  237.45  4893.6  239.07  4905.0  237.62  4913.7  237.88
  4923.7  240.64  4993.9  240.34  4999.5  236.86  4999.7  236.36  5003.2  236.36
  5003.5  236.86  5036.3  239.95  5072.6  241.12  5096.9  242.74  5180.3  244.35
  5207.6  245.86  5240.9  247.90  5251.7  247.42  5258.4  248.24  5273.2  248.37
#Mann=9,-1,0
  4401.9    0.07       0  4431.8   0.035       0  4510.3    0.07       0
  4655.7    0.12       0  4831.8     0.1       0  4905.0    0.12       0
  4999.5    0.05       0  5003.5    0.12       0  5207.6    0.07       0
Bank Sta=4999.5,5003.5
Exp/Cntr=0.3,0.1

Type RM Length L Ch R = 1,1415,435,435,435
BEGIN DESCRIPTION:
Stream0750 3.0
END DESCRIPTION:
XS GIS Cut Line= 3
      2453275.03     13672725.04      2452825.00     13672125.00
      2452625.00     13671525.00
#Sta/Elev= 30
  4244.0  254.24  4357.3  250.19  4367.6  249.04  4386.8  248.91  4503.2  244.14
  4651.3  240.23  4815.9  239.42  4830.5  239.54  4836.8  240.56  4851.3  239.14
  4901.3  239.49  4930.8  238.59  4996.7  238.95  5004.6  237.56  5013.1  237.51
  5013.4  237.01  5017.1  237.51  5025.7  237.56  5036.2  238.85  5078.4  238.60
  5107.1  239.39  5131.1  241.64  5141.6  239.82  5152.2  239.46  5194.3  240.91
  5204.9  242.65  5226.2  242.11  5247.0  244.32  5426.2  250.71  5626.5  259.62
#Mann=9,-1,0
  4244.0    0.07       0  4357.3   0.035       0  4367.6    0.07       0
  4503.2    0.12       0  4930.8     0.1       0  5013.1    0.05       0
  5017.1     0.1       0  5107.1    0.12       0  5226.2    0.07       0
Bank Sta=5013.1,5017.1
Exp/Cntr=0.3,0.1

Type RM Length L Ch R = 1,980,470,470,470
BEGIN DESCRIPTION:
Stream0750 2.0
END DESCRIPTION:
XS GIS Cut Line= 3
      2453325.00     13672724.98      2453225.00     13672125.00
      2453324.99     13671525.03
#Sta/Elev= 30
  4391.3  254.55  4442.0  253.44  4496.2  251.05  4512.9  250.73  4523.1  249.32
  4545.9  249.27  4577.4  247.66  4662.5  243.08  4667.5  243.50  4827.2  237.85
  4867.8  237.10  4879.6  237.72  4948.9  238.61  4971.7  238.13  4977.3  236.68
  4977.5  236.18  4981.3  236.68  5009.7  238.40  5095.9  238.73  5222.6  240.61
  5278.2  242.35  5392.4  246.51  5397.5  245.54  5415.2  245.12  5453.2  245.83
  5458.3  247.82  5465.9  248.69  5496.3  249.30  5576.3  253.51  5607.8  254.94
#Mann=9,-1,0
  4391.3    0.07       0  4496.2   0.035       0  4577.4    0.07       0
  4879.6     0.1       0  4977.3    0.05       0  4981.3     0.1       0
  5095.9    0.12       0  5278.2   0.035       0  5576.3    0.07       0
Bank Sta=4977.3,4981.3
Exp/Cntr=0.3,0.1

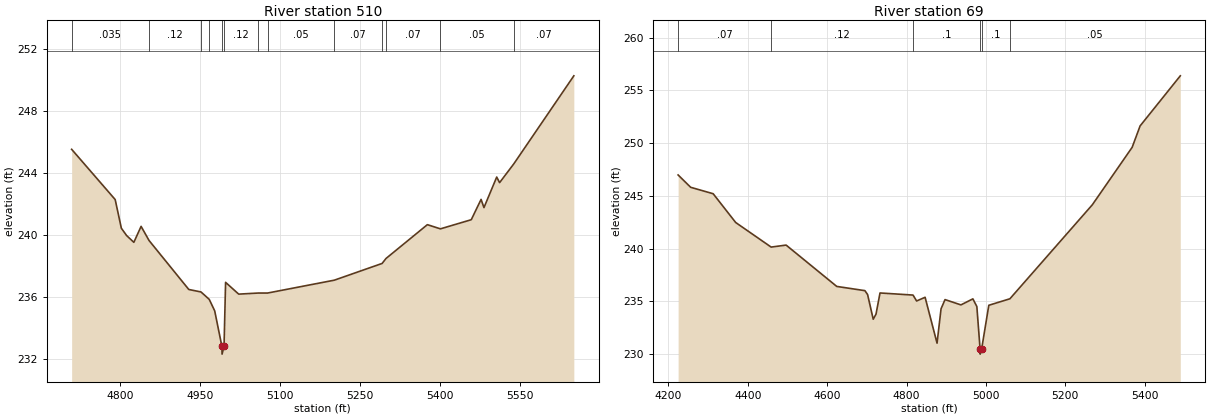
Type RM Length L Ch R = 1,510,441,441,441
BEGIN DESCRIPTION:
Stream0750 1.0
END DESCRIPTION:
XS GIS Cut Line= 3
      2453475.02     13672474.96      2453625.00     13672225.00
      2453375.00     13671625.00
#Sta/Elev= 30
  4709.0  245.55  4790.6  242.31  4802.2  240.46  4812.0  239.99  4825.6  239.55
  4839.2  240.58  4854.1  239.67  4928.6  236.51  4951.5  236.35  4967.0  235.87
  4977.2  235.13  4990.7  232.84  4991.0  232.34  4994.7  232.84  4997.6  236.97
  5022.2  236.21  5059.0  236.28  5076.4  236.28  5201.5  237.11  5291.1  238.19
  5298.4  238.51  5375.9  240.69  5400.4  240.42  5458.2  241.01  5476.6  242.32
  5482.0  241.79  5505.9  243.76  5511.3  243.40  5537.9  244.61  5650.5  250.29
#Mann=13,-1,0
  4709.0   0.035       0  4854.1    0.12       0  4951.5    0.07       0
  4967.0    0.12       0  4990.7    0.05       0  4994.7    0.12       0
  5059.0    0.07       0  5076.4    0.05       0  5201.5    0.07       0
  5291.1    0.05       0  5298.4    0.07       0  5400.4    0.05       0
  5537.9    0.07       0
Bank Sta=4990.7,4994.7
Exp/Cntr=0.3,0.1

Type RM Length L Ch R = 1,69,0,0,0
BEGIN DESCRIPTION:
XS7642
END DESCRIPTION:
XS GIS Cut Line= 3
      2453577.43     13672592.01      2453952.43     13672248.26
      2454012.24     13671494.04
#Sta/Elev= 30
  4224.4  246.98  4256.0  245.81  4312.7  245.20  4369.5  242.47  4458.8  240.14
  4496.5  240.33  4624.1  236.41  4695.0  236.01  4701.8  235.64  4716.0  233.30
  4723.0  233.78  4733.1  235.79  4816.3  235.59  4825.3  235.03  4846.7  235.38
  4876.8  231.03  4886.9  234.29  4896.9  235.16  4937.0  234.66  4967.1  235.23
  4977.1  234.50  4985.2  230.49  4985.4  229.99  4989.2  230.49  5007.2  234.62
  5060.4  235.24  5268.0  244.15  5368.4  249.60  5388.4  251.63  5489.7  256.38
#Mann=6,-1,0
  4224.4    0.07       0  4458.8    0.12       0  4816.3     0.1       0
  4985.2    0.05       0  4989.2     0.1       0  5060.4    0.05       0
Bank Sta=4985.2,4989.2
Exp/Cntr=0.3,0.1

Chan Stop Cuts=-1