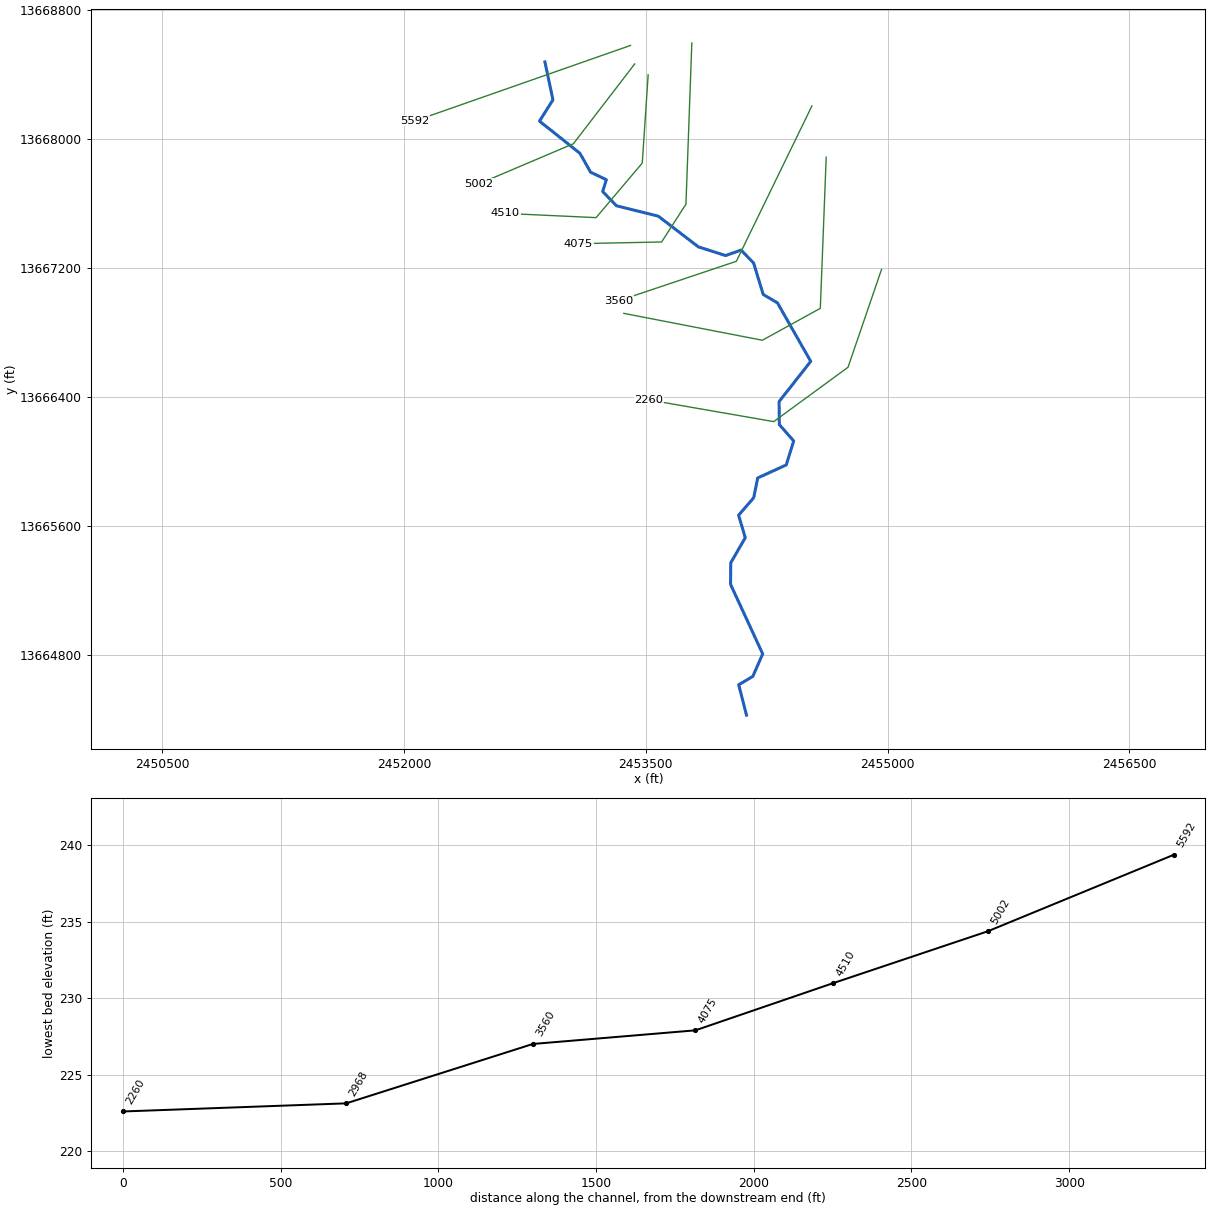
--- Stream0751.prj (project) ---

Proj Title=Stream0751 Base Level Engineering
Current Plan=p01
Default Exp/Contr=0.3,0.1
English Units
Geom File=g01
Flow File=f01
Plan File=p01
BEGIN DESCRIPTION:
Stream0751
END DESCRIPTION:

--- Stream0751.p01 (plan) ---

Plan Title=Multiple Run
Short Identifier=Multiple
Geom File=g01
Flow File=f01
Subcritical Flow
K Sum by GR= 0
Std Step Tol= 0.01
Critical Tol= 0.01
Num of Std Step Trials= 20
Max Error Tol= 0.3
Flow Tol Ratio= 0.001
Split Flow NTrial= 30
Split Flow Tol= 0.02
Split Flow Ratio= 0.02
Log Output Level= 0
Friction Slope Method= 1
Unsteady Friction Slope Method= 2
Unsteady Bridges Friction Slope Method= 1
Parabolic Critical Depth
Global Vel Dist=  1 , 1 , 1
Global Log Level= 0
CheckData=True
Encroach Param= -1, 0, 0, 0
BEGIN DESCRIPTION:
Multiple Run
END DESCRIPTION:

--- Stream0751.f01 (steady flow) ---

Flow Title=Multiple
Number of Profiles=7
Profile Names=10-year,25-year,50-year,1pct_min,100-year,1pct_plu,500-year
River Rch & RM= Stream0751,Reach-1,5592
     346     532     693     439     875    1746    1377
Boundary for River Rch & Prof#=Stream0751,Reach-1,1
Up Type=0
Dn Type=3
Dn Slope=0.005
Boundary for River Rch & Prof#=Stream0751,Reach-1,2
Up Type=0
Dn Type=3
Dn Slope=0.005
Boundary for River Rch & Prof#=Stream0751,Reach-1,3
Up Type=0
Dn Type=3
Dn Slope=0.005
Boundary for River Rch & Prof#=Stream0751,Reach-1,4
Up Type=0
Dn Type=3
Dn Slope=0.005
Boundary for River Rch & Prof#=Stream0751,Reach-1,5
Up Type=0
Dn Type=3
Dn Slope=0.005
Boundary for River Rch & Prof#=Stream0751,Reach-1,6
Up Type=0
Dn Type=3
Dn Slope=0.005
Boundary for River Rch & Prof#=Stream0751,Reach-1,7
Up Type=0
Dn Type=3
Dn Slope=0.005

--- Stream0751.g01 (geometry) ---

Geom Title=Existing Conditions

River Reach=Stream0751,Reach-1
Reach XY= 30
      2452875.00     13668475.00      2452924.62     13668240.16
      2452841.20     13668108.33      2453092.08     13667908.57
      2453157.97     13667791.50      2453255.78     13667745.38
      2453233.00     13667671.66      2453318.91     13667583.14
      2453577.35     13667519.29      2453826.50     13667328.61
      2453995.21     13667274.79      2454091.74     13667308.71
      2454169.48     13667227.46      2454228.53     13667033.49
      2454316.91     13666981.31      2454523.31     13666618.53
      2454327.05     13666369.14      2454328.55     13666226.47
      2454417.67     13666125.10      2454371.49     13665976.25
      2454194.43     13665895.64      2454169.46     13665772.58
      2454075.95     13665664.51      2454117.47     13665524.99
      2454027.23     13665369.07      2454026.19     13665235.50
      2454225.29     13664804.82      2454164.31     13664665.02
      2454076.52     13664613.12      2454125.00     13664425.00

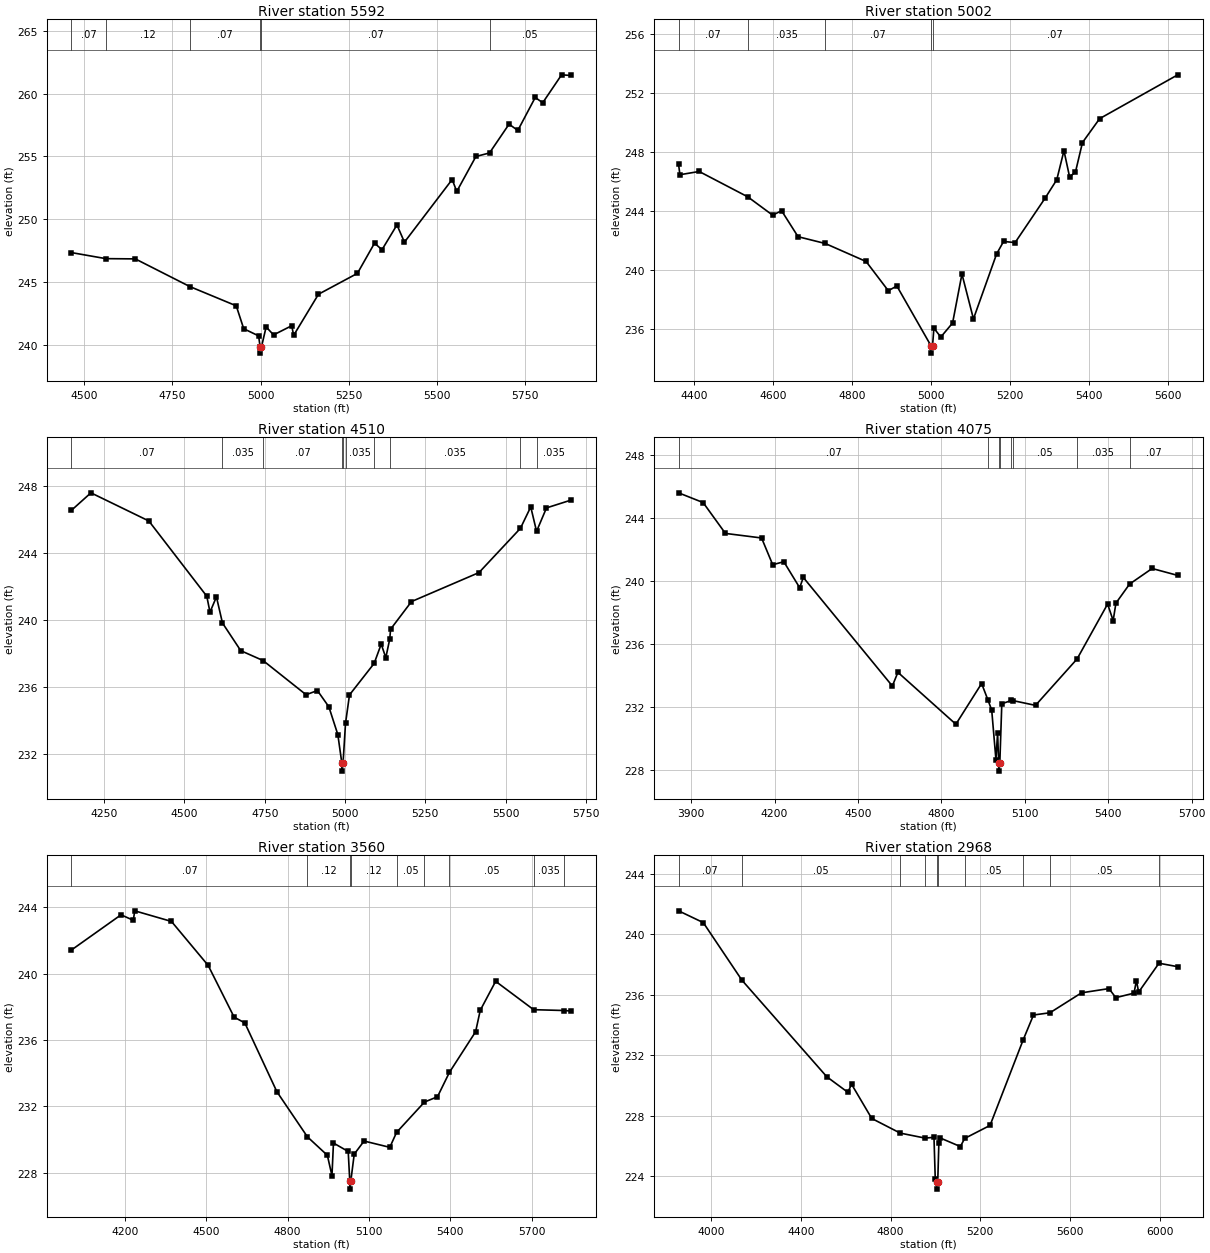
Type RM Length L Ch R = 1,5592,590,590,590
BEGIN DESCRIPTION:
XS7650
END DESCRIPTION:
XS GIS Cut Line= 2
      2453405.72     13668577.60      2452070.24     13668109.92
#Sta/Elev= 30
  4464.2  247.36  4561.6  246.88  4645.1  246.86  4799.7  244.66  4931.2  243.13
  4952.4  241.31  4994.7  240.74  4998.8  239.87  4999.0  239.37  5002.8  239.87
  5015.9  241.45  5037.1  240.82  5088.6  241.55  5093.9  240.78  5164.3  244.05
  5274.7  245.71  5323.2  248.11  5344.4  247.59  5386.8  249.56  5408.0  248.19
  5543.3  253.17  5556.3  252.22  5610.6  255.00  5649.2  255.28  5704.6  257.57
  5729.4  257.07  5778.8  259.69  5800.0  259.27  5853.5  261.49  5879.2  261.44
#Mann=6,-1,0
  4464.2    0.07       0  4561.6    0.12       0  4799.7    0.07       0
  4998.8    0.05       0  5002.8    0.07       0  5649.2    0.05       0
Bank Sta=4998.8,5002.8
Exp/Cntr=0.3,0.1

Type RM Length L Ch R = 1,5002,492,492,492
BEGIN DESCRIPTION:
XS7649
END DESCRIPTION:
XS GIS Cut Line= 3
      2453431.75     13668463.00      2453051.56     13667968.23
      2452463.03     13667718.23
#Sta/Elev= 30
  4360.5  247.16  4363.8  246.46  4412.6  246.68  4535.7  244.96  4598.5  243.72
  4621.2  244.02  4662.9  242.26  4731.7  241.80  4835.1  240.58  4891.3  238.60
  4912.9  238.92  4999.3  234.87  4999.5  234.37  5003.3  234.87  5006.7  236.06
  5024.2  235.46  5054.0  236.41  5077.7  239.73  5106.8  236.69  5165.4  241.09
  5183.1  241.94  5212.2  241.86  5288.6  244.89  5317.7  246.12  5335.9  248.09
  5350.1  246.32  5365.0  246.64  5382.7  248.64  5426.2  250.26  5623.9  253.23
#Mann=5,-1,0
  4360.5    0.07       0  4535.7   0.035       0  4731.7    0.07       0
  4999.3    0.05       0  5003.3    0.07       0
Bank Sta=4999.3,5003.3
Exp/Cntr=0.3,0.1

Type RM Length L Ch R = 1,4510,435,435,435
BEGIN DESCRIPTION:
XS7648
END DESCRIPTION:
XS GIS Cut Line= 4
      2453515.11     13668395.35      2453478.65     13667848.44
      2453192.19     13667509.90      2452629.79     13667535.93
#Sta/Elev= 30
  4148.3  246.54  4208.8  247.58  4389.2  245.90  4569.6  241.41  4579.6  240.46
  4599.7  241.37  4618.5  239.81  4675.4  238.16  4744.9  237.57  4878.9  235.53
  4914.1  235.78  4949.8  234.81  4977.8  233.15  4990.1  231.47  4990.3  230.97
  4994.1  231.47  5001.7  233.82  5014.1  235.52  5090.9  237.40  5112.9  238.55
  5127.2  237.74  5139.5  238.86  5142.1  239.44  5207.2  241.09  5417.4  242.82
  5546.4  245.46  5578.6  246.74  5596.7  245.28  5627.6  246.68  5702.9  247.14
#Mann=10,-1,0
  4148.3    0.07       0  4618.5   0.035       0  4744.9    0.07       0
  4990.1    0.05       0  4994.1    0.07       0  5001.7   0.035       0
  5090.9    0.07       0  5139.5   0.035       0  5546.4    0.07       0
  5596.7   0.035       0
Bank Sta=4990.1,4994.1
Exp/Cntr=0.3,0.1

Type RM Length L Ch R = 1,4075,515,515,515
BEGIN DESCRIPTION:
XS7647
END DESCRIPTION:
XS GIS Cut Line= 4
      2453785.94     13668593.27      2453749.48     13667593.23
      2453598.44     13667358.85      2453082.77     13667348.44
#Sta/Elev= 30
  3854.8  245.59  3943.1  244.97  4023.2  243.01  4153.3  242.72  4193.3  241.02
  4233.3  241.21  4290.3  239.56  4303.4  240.21  4623.6  233.31  4643.6  234.18
  4852.1  230.88  4944.7  233.47  4967.9  232.40  4981.0  231.78  4996.2  228.63
  5002.2  230.34  5006.1  228.40  5006.4  227.90  5010.1  228.40  5017.3  232.18
  5051.1  232.39  5058.1  232.38  5138.5  232.08  5288.0  235.03  5397.8  238.52
  5417.8  237.47  5427.8  238.58  5476.9  239.79  5557.9  240.78  5650.1  240.34
#Mann=8,-1,0
  3854.8    0.07       0  4967.9    0.12       0  5006.1    0.05       0
  5010.1    0.12       0  5051.1    0.07       0  5058.1    0.05       0
  5288.0   0.035       0  5476.9    0.07       0
Bank Sta=5006.1,5010.1
Exp/Cntr=0.3,0.1

Type RM Length L Ch R = 1,3560,592,592,592
BEGIN DESCRIPTION:
XS7646
END DESCRIPTION:
XS GIS Cut Line= 3
      2454530.72     13668202.58      2454061.98     13667239.06
      2453332.77     13666994.26
#Sta/Elev= 30
  4003.1  241.43  4185.8  243.55  4230.9  243.22  4236.4  243.79  4371.7  243.15
  4507.0  240.50  4602.8  237.38  4642.3  237.03  4760.6  232.88  4873.2  230.16
  4946.6  229.05  4963.6  227.82  4969.1  229.79  5023.5  229.28  5029.2  227.51
  5029.5  227.01  5033.2  227.51  5045.7  229.12  5082.0  229.91  5176.9  229.53
  5201.8  230.43  5304.7  232.26  5352.7  232.58  5396.7  234.05  5493.3  236.50
  5510.4  237.79  5567.2  239.54  5707.2  237.83  5818.8  237.78  5843.8  237.75
#Mann=9,-1,0
  4003.1    0.07       0  4873.2    0.12       0  5029.2    0.05       0
  5033.2    0.12       0  5201.8    0.05       0  5304.7   0.035       0
  5396.7    0.05       0  5707.2   0.035       0  5818.8    0.05       0
Bank Sta=5029.2,5033.2
Exp/Cntr=0.3,0.1

Type RM Length L Ch R = 1,2968,708,708,708
BEGIN DESCRIPTION:
XS7645
END DESCRIPTION:
XS GIS Cut Line= 4
      2454619.27     13667884.87      2454582.81     13666947.40
      2454223.44     13666749.48      2453364.10     13666916.14
#Sta/Elev= 30
  3855.8  241.56  3965.8  240.78  4137.8  236.97  4516.2  230.57  4610.1  229.54
  4626.3  230.08  4716.3  227.81  4843.2  226.84  4953.8  226.51  4993.6  226.56
  4999.3  223.79  5006.4  223.63  5006.6  223.13  5010.4  223.63  5015.4  226.21
  5021.1  226.52  5111.1  225.95  5130.6  226.49  5243.4  227.35  5391.1  233.02
  5436.9  234.66  5510.4  234.81  5650.9  236.13  5773.1  236.41  5803.7  235.81
  5884.9  236.11  5895.3  236.94  5905.5  236.18  5996.0  238.09  6079.6  237.86
#Mann=10,-1,0
  3855.8    0.07       0  4137.8    0.05       0  4843.2    0.07       0
  4953.8    0.12       0  5006.4    0.05       0  5010.4    0.12       0
  5130.6    0.05       0  5391.1   0.035       0  5510.4    0.05       0
  5996.0   0.035       0
Bank Sta=5006.4,5010.4
Exp/Cntr=0.3,0.1

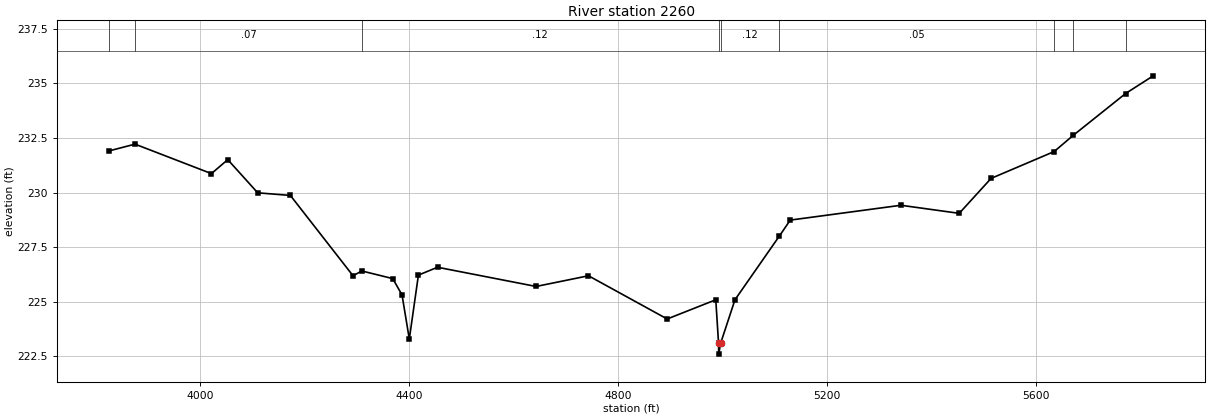
Type RM Length L Ch R = 1,2260,0,0,0
BEGIN DESCRIPTION:
E21311
END DESCRIPTION:
XS GIS Cut Line= 4
      2454962.40     13667188.72      2454754.55     13666582.02
      2454293.88     13666244.95      2453519.34     13666379.65
#Sta/Elev= 30
  3825.8  231.91  3875.6  232.22  4021.8  230.87  4053.1  231.51  4110.4  229.99
  4172.9  229.87  4292.8  226.19  4309.6  226.41  4368.8  226.06  4386.6  225.31
  4400.5  223.29  4417.9  226.22  4454.5  226.58  4643.1  225.70  4743.4  226.19
  4894.0  224.21  4987.0  225.09  4992.3  223.10  4992.6  222.60  4996.3  223.10
  5023.7  225.09  5108.4  228.00  5129.5  228.74  5341.3  229.42  5452.9  229.05
  5513.8  230.65  5634.5  231.88  5670.9  232.62  5771.3  234.54  5824.1  235.35
#Mann=9,-1,0
  3825.8    0.12       0  3875.6    0.07       0  4309.6    0.12       0
  4992.3    0.05       0  4996.3    0.12       0  5108.4    0.05       0
  5634.5    0.07       0  5670.9   0.035       0  5771.3    0.07       0
Bank Sta=4992.3,4996.3
Exp/Cntr=0.3,0.1

Chan Stop Cuts=-1