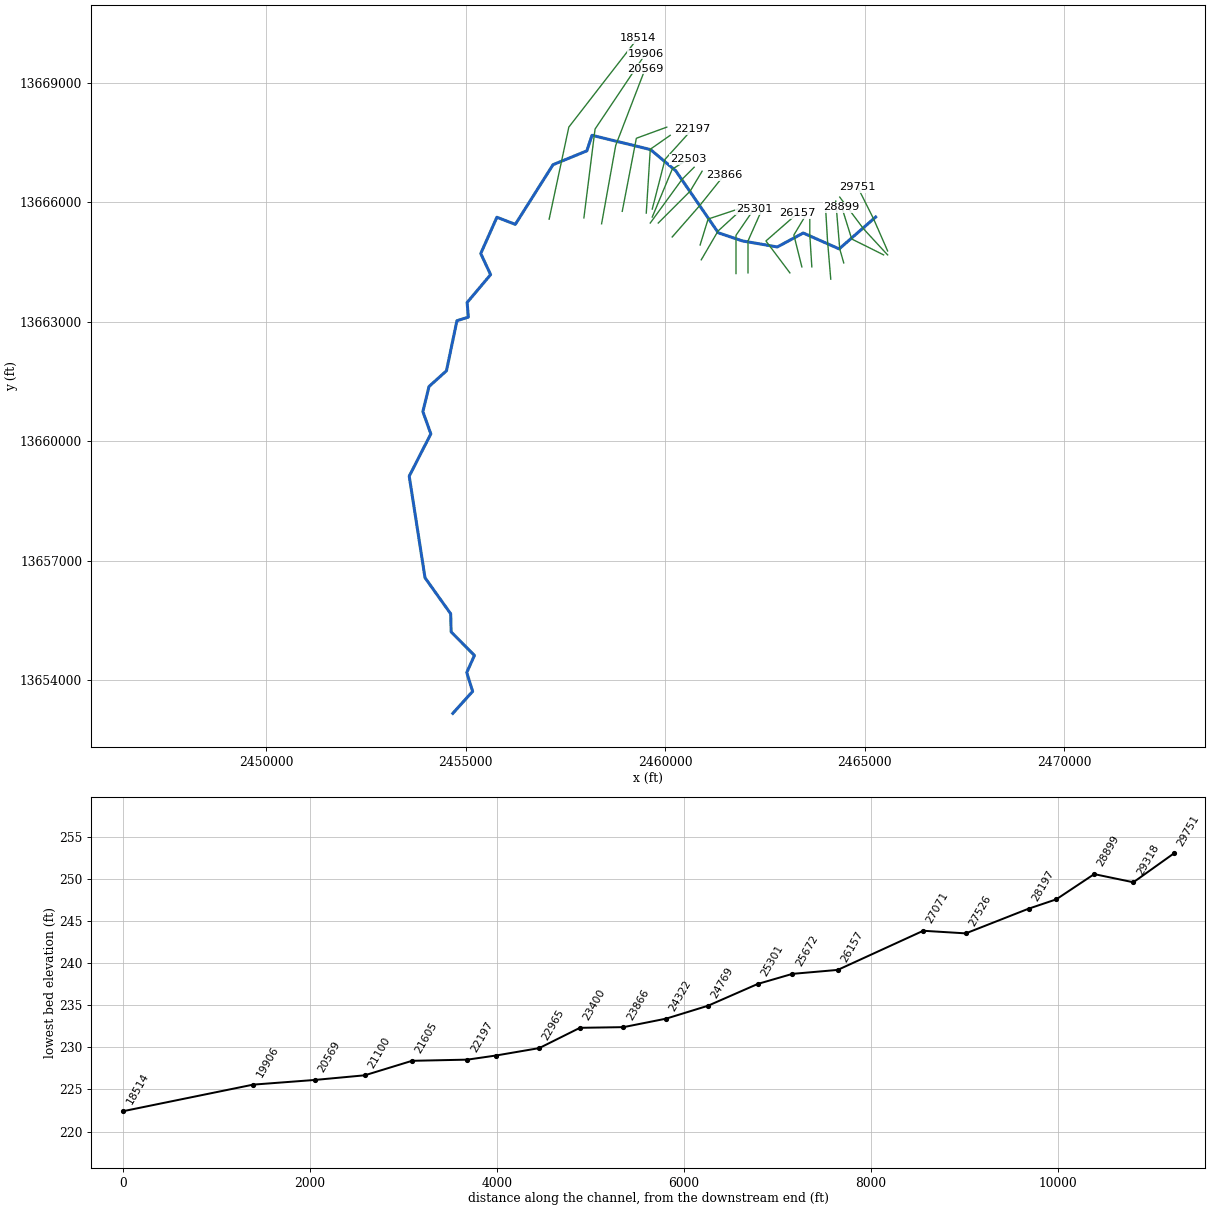
--- Stream0752.prj (project) ---

Proj Title=Stream0752 Base Level Engineering
Current Plan=p01
Default Exp/Contr=0.3,0.1
English Units
Geom File=g01
Flow File=f01
Plan File=p01
BEGIN DESCRIPTION:
Stream0752
END DESCRIPTION:

--- Stream0752.p01 (plan) ---

Plan Title=Multiple Run
Short Identifier=Multiple
Geom File=g01
Flow File=f01
Subcritical Flow
K Sum by GR= 0
Std Step Tol= 0.01
Critical Tol= 0.01
Num of Std Step Trials= 20
Max Error Tol= 0.3
Flow Tol Ratio= 0.001
Split Flow NTrial= 30
Split Flow Tol= 0.02
Split Flow Ratio= 0.02
Log Output Level= 0
Friction Slope Method= 1
Unsteady Friction Slope Method= 2
Unsteady Bridges Friction Slope Method= 1
Parabolic Critical Depth
Global Vel Dist=  1 , 1 , 1
Global Log Level= 0
CheckData=True
Encroach Param= -1, 0, 0, 0
BEGIN DESCRIPTION:
Multiple Run
END DESCRIPTION:

--- Stream0752.f01 (steady flow) ---

Flow Title=Multiple
Number of Profiles=7
Profile Names=10-year,25-year,50-year,1pct_min,100-year,1pct_plu,500-year
River Rch & RM= Stream0752,Reach-1,29751
     847    1390    1889    1244    2482    4952    4239
River Rch & RM= Stream0752,Reach-1,28493
    1069    1758    2392    1573    3139    6263    5356
Boundary for River Rch & Prof#=Stream0752,Reach-1,1
Up Type=0
Dn Type=3
Dn Slope=0.005
Boundary for River Rch & Prof#=Stream0752,Reach-1,2
Up Type=0
Dn Type=3
Dn Slope=0.005
Boundary for River Rch & Prof#=Stream0752,Reach-1,3
Up Type=0
Dn Type=3
Dn Slope=0.005
Boundary for River Rch & Prof#=Stream0752,Reach-1,4
Up Type=0
Dn Type=3
Dn Slope=0.005
Boundary for River Rch & Prof#=Stream0752,Reach-1,5
Up Type=0
Dn Type=3
Dn Slope=0.005
Boundary for River Rch & Prof#=Stream0752,Reach-1,6
Up Type=0
Dn Type=3
Dn Slope=0.005
Boundary for River Rch & Prof#=Stream0752,Reach-1,7
Up Type=0
Dn Type=3
Dn Slope=0.005

--- Stream0752.g01 (geometry) ---

Geom Title=Existing Conditions

River Reach=Stream0752,Reach-1
Reach XY= 30
      2465275.00     13665625.00      2464360.29     13664825.90
      2463459.58     13665224.85      2462809.79     13664874.89
      2461930.68     13665027.00      2461330.44     13665230.25
      2460261.60     13666788.73      2459631.06     13667317.52
      2458164.81     13667675.55      2458035.16     13667285.36
      2457187.92     13666938.50      2456241.67     13665441.20
      2455780.55     13665620.23      2455375.38     13664709.72
      2455622.84     13664180.45      2455034.29     13663481.67
      2455064.94     13663114.88      2454778.37     13663023.72
      2454516.02     13661768.34      2454078.15     13661373.36
      2453924.60     13660745.13      2454124.44     13660185.64
      2453582.45     13659125.21      2453978.37     13656576.73
      2454621.88     13655673.38      2454633.02     13655218.66
      2455217.39     13654628.33      2455024.77     13654200.07
      2455171.87     13653726.63      2454675.00     13653175.00

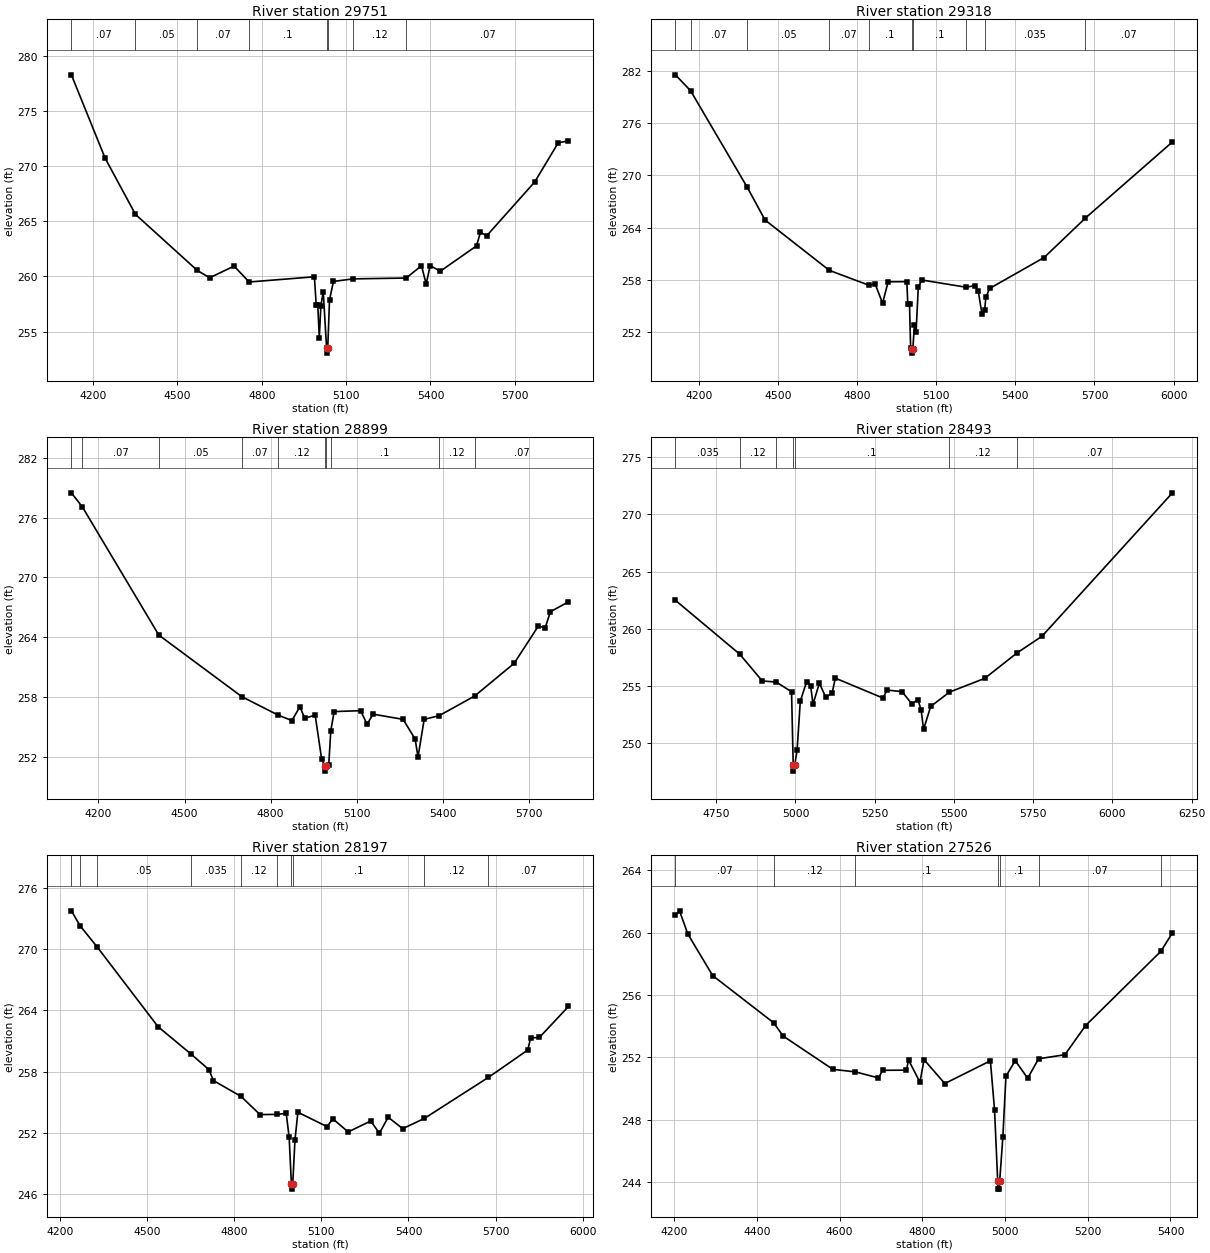
Type RM Length L Ch R = 1,29751,433,433,433
BEGIN DESCRIPTION:
Stream0752 43.0
END DESCRIPTION:
XS GIS Cut Line= 3
      2465574.99     13664775.02      2465225.00     13665575.00
      2464825.01     13666374.98
#Sta/Elev= 30
  4123.1  278.27  4243.1  270.71  4350.9  265.62  4570.6  260.54  4614.7  259.87
  4701.6  260.93  4755.3  259.49  4987.3  259.96  4993.6  257.43  4999.1  257.43
  5004.7  254.45  5010.3  257.32  5018.7  258.62  5030.5  253.54  5030.8  253.04
  5034.8  253.54  5041.0  257.86  5055.0  259.54  5124.3  259.77  5314.1  259.85
  5368.0  260.97  5384.8  259.30  5398.8  260.97  5435.1  260.47  5563.7  262.76
  5577.7  263.99  5600.0  263.68  5770.5  268.55  5854.4  272.11  5890.7  272.28
#Mann=8,-1,0
  4123.1    0.07       0  4350.9    0.05       0  4570.6    0.07       0
  4755.3     0.1       0  5030.5    0.05       0  5034.8     0.1       0
  5124.3    0.12       0  5314.1    0.07       0
Bank Sta=5030.5,5034.8
Exp/Cntr=0.3,0.1

Type RM Length L Ch R = 1,29318,419,419,419
BEGIN DESCRIPTION:
Stream0752 42.0
END DESCRIPTION:
XS GIS Cut Line= 3
      2465575.00     13664675.00      2464975.00     13665325.00
      2464374.99     13666125.01
#Sta/Elev= 30
  4111.0  281.51  4168.6  279.69  4383.7  268.61  4450.9  264.87  4695.0  259.09
  4843.5  257.41  4868.3  257.55  4896.6  255.33  4917.6  257.79  4988.5  257.80
  4992.2  255.27  4998.7  255.27  5002.9  250.21  5007.0  250.11  5007.3  249.61
  5011.3  250.11  5017.5  252.85  5023.7  252.05  5032.0  257.20  5045.6  257.99
  5212.3  257.17  5245.6  257.33  5259.1  256.76  5273.7  254.06  5283.5  254.52
  5288.3  256.04  5302.9  257.03  5509.1  260.57  5665.9  265.10  5995.6  273.82
#Mann=10,-1,0
  4111.0    0.05       0  4168.6    0.07       0  4383.7    0.05       0
  4695.0    0.07       0  4843.5     0.1       0  5007.0    0.05       0
  5011.3     0.1       0  5212.3    0.07       0  5283.5   0.035       0
  5665.9    0.07       0
Bank Sta=5007,5011.3
Exp/Cntr=0.3,0.1

Type RM Length L Ch R = 1,28899,406,406,406
BEGIN DESCRIPTION:
Stream0752 41.0
END DESCRIPTION:
XS GIS Cut Line= 3
      2465474.98     13664675.01      2464675.00     13665075.00
      2464424.99     13665875.05
#Sta/Elev= 30
  4105.6  278.48  4144.2  277.05  4410.3  264.22  4700.0  258.04  4827.4  256.18
  4874.2  255.65  4902.2  257.04  4918.9  255.87  4955.3  256.20  4977.6  251.83
  4989.5  251.08  4989.8  250.58  4993.8  251.08  5002.6  251.21  5009.8  254.63
  5021.5  256.55  5113.7  256.64  5136.2  255.28  5157.2  256.29  5261.9  255.77
  5303.8  253.79  5313.8  251.99  5335.3  255.77  5387.6  256.14  5511.3  258.11
  5649.0  261.39  5733.4  265.13  5757.0  264.94  5775.3  266.56  5838.2  267.55
#Mann=10,-1,0
  4105.6    0.05       0  4144.2    0.07       0  4410.3    0.05       0
  4700.0    0.07       0  4827.4    0.12       0  4989.5    0.05       0
  4993.8    0.12       0  5009.8     0.1       0  5387.6    0.12       0
  5511.3    0.07       0
Bank Sta=4989.5,4993.8
Exp/Cntr=0.3,0.1

Type RM Length L Ch R = 1,28493,296,296,296
BEGIN DESCRIPTION:
Stream0752 40.0
END DESCRIPTION:
XS GIS Cut Line= 3
      2464474.99     13664475.03      2464375.00     13664825.00
      2464275.00     13666024.96
#Sta/Elev= 30
  4621.1  262.50  4824.2  257.79  4895.4  255.45  4939.1  255.36  4987.6  254.51
  4992.9  248.08  4993.2  247.58  4997.4  248.08  5005.1  249.40  5015.2  253.69
  5035.3  255.39  5047.8  255.04  5055.3  253.43  5075.4  255.26  5095.5  254.03
  5115.5  254.39  5125.6  255.70  5276.1  253.96  5288.6  254.66  5336.3  254.52
  5366.4  253.47  5386.5  253.80  5396.5  252.91  5404.0  251.22  5426.6  253.23
  5485.8  254.48  5597.2  255.68  5698.4  257.89  5777.8  259.36  6189.2  271.88
#Mann=7,-1,0
  4621.1   0.035       0  4824.2    0.12       0  4939.1     0.1       0
  4992.9    0.05       0  4997.4     0.1       0  5485.8    0.12       0
  5698.4    0.07       0
Bank Sta=4992.9,4997.4
Exp/Cntr=0.3,0.1

Type RM Length L Ch R = 1,28197,671,671,671
BEGIN DESCRIPTION:
Stream0752 39.0
END DESCRIPTION:
XS GIS Cut Line= 3
      2464149.62     13664067.65      2464067.44     13665045.58
      2464025.00     13665774.97
#Sta/Elev= 30
  4239.0  273.76  4269.1  272.29  4327.7  270.22  4537.4  262.40  4650.3  259.73
  4712.6  258.19  4728.1  257.12  4823.3  255.56  4888.6  253.78  4946.2  253.80
  4978.9  253.90  4989.0  251.56  4996.7  246.97  4997.1  246.47  5001.3  246.97
  5009.1  251.31  5019.1  254.01  5119.4  252.60  5139.5  253.36  5192.3  252.08
  5269.9  253.15  5299.9  251.95  5330.0  253.52  5380.1  252.40  5454.5  253.40
  5675.5  257.43  5810.8  260.11  5820.8  261.30  5850.9  261.34  5951.0  264.38
#Mann=10,-1,0
  4239.0    0.05       0  4269.1    0.07       0  4327.7    0.05       0
  4650.3   0.035       0  4823.3    0.12       0  4946.2     0.1       0
  4996.7    0.05       0  5001.3     0.1       0  5454.5    0.12       0
  5675.5    0.07       0
Bank Sta=4996.7,5001.3
Exp/Cntr=0.3,0.1

Type RM Length L Ch R = 1,27526,455,455,455
BEGIN DESCRIPTION:
Stream0752 38.0
END DESCRIPTION:
XS GIS Cut Line= 3
      2463675.00     13664374.99      2463625.00     13665175.00
      2463625.00     13665575.03
#Sta/Elev= 30
  4203.2  261.12  4213.2  261.41  4233.3  259.92  4293.4  257.25  4440.9  254.22
  4463.7  253.37  4584.0  251.23  4638.3  251.07  4694.2  250.68  4704.2  251.17
  4761.8  251.18  4766.8  251.83  4794.4  250.41  4804.4  251.85  4854.5  250.32
  4964.7  251.78  4974.7  248.65  4982.4  244.04  4982.7  243.54  4986.7  243.54
  4987.1  244.04  4994.8  246.86  5002.3  250.79  5024.8  251.79  5054.8  250.66
  5081.3  251.91  5144.8  252.17  5194.8  254.04  5376.8  258.81  5404.8  260.00
#Mann=7,-1,0
  4203.2    0.07       0  4440.9    0.12       0  4638.3     0.1       0
  4982.4    0.05       0  4987.1     0.1       0  5081.3    0.07       0
  5376.8   0.035       0
Bank Sta=4982.4,4987.1
Exp/Cntr=0.3,0.1

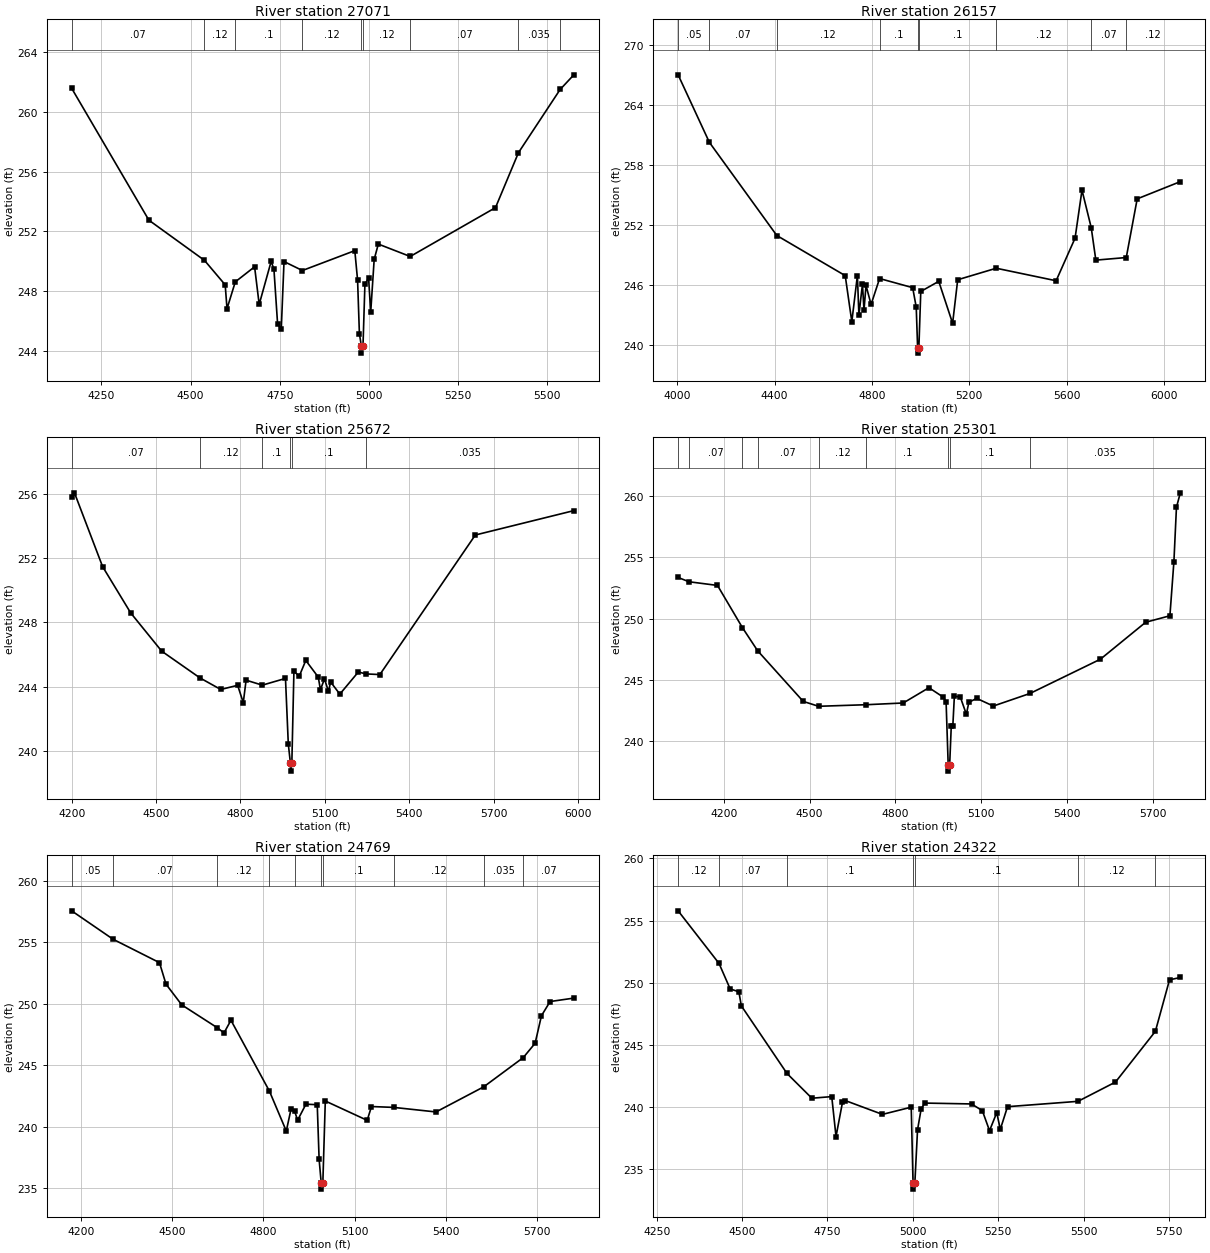
Type RM Length L Ch R = 1,27071,914,914,914
BEGIN DESCRIPTION:
Stream0752 37.0
END DESCRIPTION:
XS GIS Cut Line= 3
      2463425.01     13664374.97      2463225.00     13665175.00
      2463524.98     13665674.96
#Sta/Elev= 30
  4166.4  261.58  4382.9  252.75  4538.7  250.06  4596.8  248.42  4601.9  246.82
  4625.1  248.62  4679.2  249.63  4692.1  247.11  4725.6  249.99  4733.4  249.47
  4743.7  245.80  4754.0  245.47  4761.7  249.98  4813.2  249.38  4960.1  250.71
  4967.9  248.74  4973.0  245.15  4978.4  244.35  4978.7  243.85  4983.1  244.35
  4988.5  248.48  4998.8  248.86  5004.7  246.59  5014.4  250.12  5026.0  251.15
  5115.4  250.32  5354.5  253.59  5418.9  257.27  5535.7  261.50  5574.1  262.48
#Mann=9,-1,0
  4166.4    0.07       0  4538.7    0.12       0  4625.1     0.1       0
  4813.2    0.12       0  4978.4    0.05       0  4983.1    0.12       0
  5115.4    0.07       0  5418.9   0.035       0  5535.7    0.07       0
Bank Sta=4978.4,4983.1
Exp/Cntr=0.3,0.1

Type RM Length L Ch R = 1,26157,485,485,485
BEGIN DESCRIPTION:
Stream0752 36.0
END DESCRIPTION:
XS GIS Cut Line= 3
      2463125.02     13664224.97      2462525.00     13665025.00
      2463325.04     13665725.03
#Sta/Elev= 30
  4003.9  267.00  4132.2  260.26  4409.3  250.95  4690.4  246.94  4717.5  242.34
  4740.4  246.95  4746.6  243.02  4761.2  246.08  4767.5  243.50  4775.8  245.96
  4796.6  244.06  4831.6  246.65  4967.5  245.74  4982.1  243.80  4987.9  239.70
  4988.2  239.20  4992.9  239.70  5000.8  245.36  5074.6  246.37  5131.6  242.18
  5152.5  246.53  5310.8  247.68  5556.8  246.43  5634.6  250.68  5663.1  255.48
  5701.0  251.74  5720.0  248.49  5845.0  248.75  5889.9  254.61  6067.0  256.33
#Mann=9,-1,0
  4003.9    0.05       0  4132.2    0.07       0  4409.3    0.12       0
  4831.6     0.1       0  4987.9    0.05       0  4992.9     0.1       0
  5310.8    0.12       0  5701.0    0.07       0  5845.0    0.12       0
Bank Sta=4987.9,4992.9
Exp/Cntr=0.3,0.1

Type RM Length L Ch R = 1,25672,371,371,371
BEGIN DESCRIPTION:
Stream0752 35.0
END DESCRIPTION:
XS GIS Cut Line= 3
      2462075.00     13664224.96      2462075.00     13665025.00
      2462474.99     13665924.98
#Sta/Elev= 30
  4200.0  255.84  4210.0  256.08  4310.0  251.48  4410.0  248.59  4520.0  246.21
  4656.2  244.54  4730.0  243.82  4790.0  244.08  4810.0  243.00  4820.0  244.40
  4877.7  244.09  4960.0  244.51  4970.0  240.43  4977.5  239.23  4977.9  238.73
  4982.6  239.23  4990.0  244.95  5008.9  244.65  5032.2  245.63  5076.6  244.59
  5084.2  243.80  5098.5  244.48  5112.9  243.70  5120.4  244.29  5153.2  243.53
  5218.9  244.91  5246.4  244.79  5295.5  244.75  5634.7  253.45  5984.9  254.97
#Mann=6,-1,0
  4200.0    0.07       0  4656.2    0.12       0  4877.7     0.1       0
  4977.5    0.05       0  4982.6     0.1       0  5246.4   0.035       0
Bank Sta=4977.5,4982.6
Exp/Cntr=0.3,0.1

Type RM Length L Ch R = 1,25301,532,532,532
BEGIN DESCRIPTION:
Stream0752 34.0
END DESCRIPTION:
XS GIS Cut Line= 3
      2461773.87     13664207.21      2461773.87     13665166.31
      2462225.02     13665825.03
#Sta/Elev= 30
  4039.6  253.36  4077.8  253.01  4177.4  252.71  4264.9  249.25  4317.9  247.37
  4477.4  243.23  4531.2  242.83  4698.7  242.96  4827.4  243.10  4917.4  244.35
  4967.4  243.58  4977.4  243.21  4984.8  238.03  4985.2  237.53  4989.9  238.03
  4995.5  241.19  5000.9  241.19  5006.4  243.66  5027.3  243.58  5048.3  242.18
  5057.1  243.15  5084.2  243.48  5142.6  242.85  5271.1  243.88  5517.5  246.68
  5675.9  249.70  5760.7  250.23  5774.7  254.65  5783.6  259.09  5797.1  260.28
#Mann=9,-1,0
  4039.6    0.05       0  4077.8    0.07       0  4264.9    0.05       0
  4317.9    0.07       0  4531.2    0.12       0  4698.7     0.1       0
  4984.8    0.05       0  4989.9     0.1       0  5271.1   0.035       0
Bank Sta=4984.8,4989.9
Exp/Cntr=0.3,0.1

Type RM Length L Ch R = 1,24769,447,447,447
BEGIN DESCRIPTION:
Stream0752 33.0
END DESCRIPTION:
XS GIS Cut Line= 3
      2460903.47     13664552.53      2461325.00     13665275.00
      2461925.00     13665825.00
#Sta/Elev= 30
  4170.0  257.55  4306.2  255.24  4458.6  253.34  4480.1  251.59  4531.8  249.91
  4649.3  248.04  4670.7  247.63  4693.5  248.66  4820.0  242.90  4875.4  239.66
  4890.7  241.41  4903.1  241.25  4912.6  240.54  4939.9  241.84  4977.1  241.80
  4983.3  237.35  4990.2  235.44  4990.6  234.94  4995.5  235.44  5003.6  242.10
  5141.2  240.53  5155.4  241.65  5228.4  241.58  5367.5  241.21  5524.2  243.25
  5654.3  245.63  5693.1  246.79  5714.0  249.03  5742.4  250.18  5820.4  250.46
#Mann=10,-1,0
  4170.0    0.05       0  4306.2    0.07       0  4649.3    0.12       0
  4820.0    0.07       0  4903.1     0.1       0  4990.2    0.05       0
  4995.5     0.1       0  5228.4    0.12       0  5524.2   0.035       0
  5654.3    0.07       0
Bank Sta=4990.2,4995.5
Exp/Cntr=0.3,0.1

Type RM Length L Ch R = 1,24322,456,456,456
BEGIN DESCRIPTION:
Stream0752 32.0
END DESCRIPTION:
XS GIS Cut Line= 3
      2460874.99     13664924.97      2461075.00     13665575.00
      2461825.02     13665825.01
#Sta/Elev= 30
  4312.6  255.79  4432.4  251.56  4465.0  249.51  4490.5  249.28  4497.7  248.15
  4631.5  242.71  4704.3  240.72  4762.5  240.85  4775.0  237.64  4793.9  240.38
  4802.4  240.53  4911.0  239.42  4995.3  240.00  5000.6  233.91  5001.0  233.41
  5005.9  233.91  5013.8  238.19  5024.3  239.85  5034.9  240.33  5171.9  240.26
  5203.5  239.72  5224.6  238.11  5245.7  239.56  5256.2  238.22  5277.3  240.04
  5483.7  240.47  5593.5  242.02  5710.3  246.10  5751.7  250.24  5783.3  250.43
#Mann=7,-1,0
  4312.6    0.12       0  4432.4    0.07       0  4631.5     0.1       0
  5000.6    0.05       0  5005.9     0.1       0  5483.7    0.12       0
  5710.3    0.07       0
Bank Sta=5000.6,5005.9
Exp/Cntr=0.3,0.1

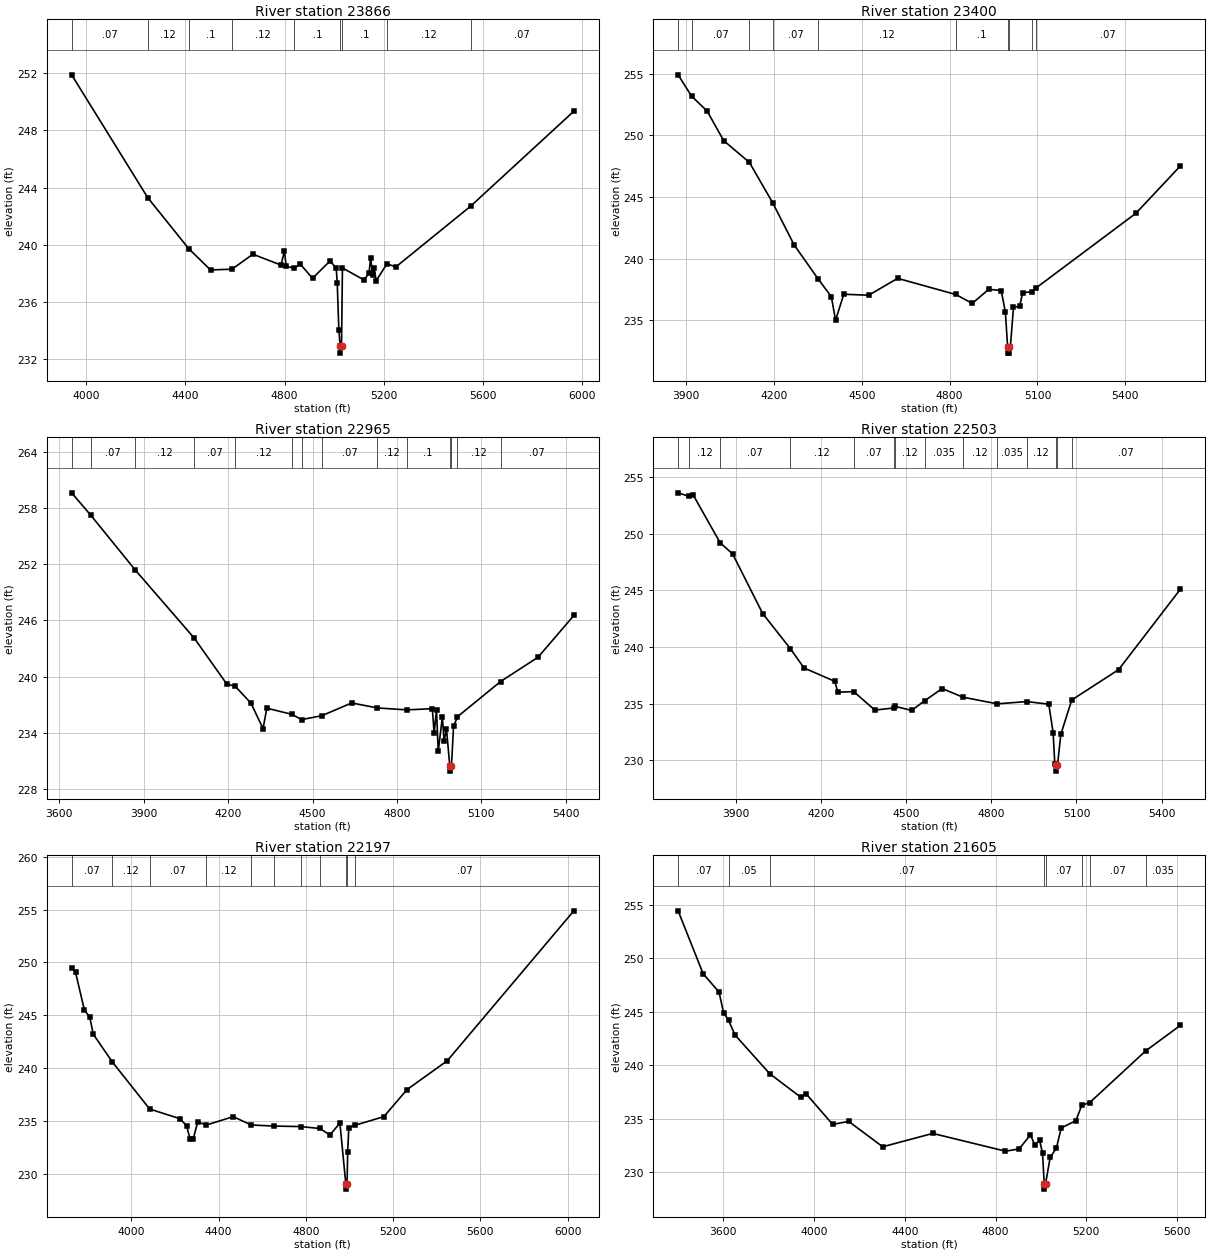
Type RM Length L Ch R = 1,23866,466,466,466
BEGIN DESCRIPTION:
Stream0752 31.0
END DESCRIPTION:
XS GIS Cut Line= 3
      2460174.98     13665124.98      2460875.00     13665925.00
      2461474.99     13666674.99
#Sta/Elev= 30
  3941.8  251.90  4248.5  243.29  4413.5  239.72  4501.3  238.23  4587.7  238.28
  4672.2  239.33  4785.1  238.57  4799.4  239.54  4806.0  238.48  4839.4  238.36
  4863.0  238.64  4912.3  237.64  4983.5  238.87  5008.0  238.33  5012.0  237.29
  5018.5  234.00  5023.8  232.90  5024.2  232.40  5029.2  232.90  5032.9  238.37
  5119.3  237.53  5140.1  237.99  5146.5  239.09  5154.5  237.87  5160.9  238.35
  5168.9  237.47  5212.6  238.67  5247.4  238.43  5549.7  242.70  5965.3  249.35
#Mann=9,-1,0
  3941.8    0.07       0  4248.5    0.12       0  4413.5     0.1       0
  4587.7    0.12       0  4839.4     0.1       0  5023.8    0.05       0
  5029.2     0.1       0  5212.6    0.12       0  5549.7    0.07       0
Bank Sta=5023.8,5029.2
Exp/Cntr=0.3,0.1

Type RM Length L Ch R = 1,23400,435,435,435
BEGIN DESCRIPTION:
Stream0752 30.0
END DESCRIPTION:
XS GIS Cut Line= 3
      2459825.03     13665475.03      2460625.00     13666275.00
      2460924.99     13666774.98
#Sta/Elev= 30
  3873.3  254.91  3919.2  253.18  3972.3  251.97  4028.8  249.57  4116.7  247.80
  4196.2  244.52  4269.2  241.11  4350.7  238.36  4396.5  236.90  4410.7  234.99
  4438.9  237.10  4523.8  237.02  4622.8  238.39  4821.0  237.08  4877.4  236.36
  4933.9  237.50  4976.3  237.40  4990.5  235.65  4998.2  232.82  4998.7  232.32
  5003.5  232.32  5003.9  232.82  5007.5  232.82  5018.2  236.03  5039.6  236.14
  5049.3  237.22  5080.5  237.30  5093.6  237.58  5436.1  243.67  5587.7  247.51
#Mann=10,-1,0
  3873.3    0.05       0  3919.2    0.07       0  4116.7    0.12       0
  4196.2    0.07       0  4350.7    0.12       0  4821.0     0.1       0
  4998.2    0.05       0  5003.9     0.1       0  5080.5    0.12       0
  5093.6    0.07       0
Bank Sta=4998.2,5003.9
Exp/Cntr=0.3,0.1

Type RM Length L Ch R = 1,22965,462,462,462
BEGIN DESCRIPTION:
Stream0752 29.0
END DESCRIPTION:
XS GIS Cut Line= 3
      2459625.02     13665475.03      2460425.00     13666575.00
      2460725.02     13666875.02
#Sta/Elev= 30
  3644.0  259.63  3711.9  257.24  3870.3  251.38  4079.7  244.11  4195.4  239.20
  4224.9  238.98  4281.1  237.17  4324.0  234.45  4337.6  236.63  4426.0  235.98
  4461.3  235.41  4532.9  235.83  4639.0  237.19  4730.1  236.66  4834.4  236.45
  4925.7  236.58  4931.9  233.98  4940.4  236.44  4946.5  232.01  4961.2  235.68
  4967.4  233.15  4975.9  234.42  4987.7  230.41  4988.2  229.91  4993.4  230.41
  5001.0  234.68  5015.0  235.72  5168.1  239.48  5301.1  242.07  5428.4  246.53
#Mann=14,-1,0
  3644.0    0.05       0  3711.9    0.07       0  3870.3    0.12       0
  4079.7    0.07       0  4224.9    0.12       0  4426.0    0.07       0
  4461.3    0.12       0  4532.9    0.07       0  4730.1    0.12       0
  4834.4     0.1       0  4987.7    0.05       0  4993.4     0.1       0
  5015.0    0.12       0  5168.1    0.07       0
Bank Sta=4987.7,4993.4
Exp/Cntr=0.3,0.1

Type RM Length L Ch R = 1,22503,306,306,306
BEGIN DESCRIPTION:
Stream0752 28.0
END DESCRIPTION:
XS GIS Cut Line= 3
      2459675.01     13665625.02      2460175.00     13666825.00
      2460575.02     13667075.01
#Sta/Elev= 30
  3694.6  253.60  3733.7  253.28  3748.7  253.37  3842.8  249.19  3886.9  248.21
  3993.0  242.94  4090.4  239.85  4138.7  238.14  4247.1  236.96  4258.5  236.00
  4314.2  236.05  4388.5  234.42  4457.3  234.61  4459.6  234.75  4518.5  234.39
  4565.3  235.26  4626.2  236.32  4699.1  235.56  4820.5  234.97  4924.4  235.17
  5002.2  234.94  5017.6  232.44  5023.5  229.68  5027.1  229.53  5027.6  229.03
  5032.9  229.53  5044.7  232.27  5083.3  235.31  5248.7  237.99  5466.3  245.08
#Mann=14,-1,0
  3694.6    0.07       0  3733.7    0.12       0  3842.8    0.07       0
  4090.4    0.12       0  4314.2    0.07       0  4457.3   0.035       0
  4459.6    0.12       0  4565.3   0.035       0  4699.1    0.12       0
  4820.5   0.035       0  4924.4    0.12       0  5027.1    0.05       0
  5032.9    0.12       0  5083.3    0.07       0
Bank Sta=5027.1,5032.9
Exp/Cntr=0.3,0.1

Type RM Length L Ch R = 1,22197,592,592,592
BEGIN DESCRIPTION:
Stream0752 27.0
END DESCRIPTION:
XS GIS Cut Line= 3
      2459675.00     13665825.00      2459995.82     13667073.67
      2460674.98     13667824.98
#Sta/Elev= 30
  3726.4  249.48  3744.2  249.06  3784.9  245.48  3809.0  244.83  3825.7  243.20
  3911.7  240.61  4084.1  236.12  4222.0  235.21  4253.0  234.56  4268.7  233.31
  4283.9  233.31  4304.3  234.90  4344.4  234.61  4467.2  235.40  4549.3  234.61
  4651.7  234.51  4775.6  234.46  4864.3  234.28  4910.2  233.67  4956.1  234.79
  4983.1  229.04  4983.6  228.54  4988.9  229.04  4991.7  232.10  4996.9  234.37
  5024.3  234.58  5157.5  235.40  5263.6  237.96  5448.2  240.69  6028.4  254.88
#Mann=11,-1,0
  3726.4    0.07       0  3911.7    0.12       0  4084.1    0.07       0
  4344.4    0.12       0  4549.3   0.035       0  4651.7    0.12       0
  4775.6   0.035       0  4864.3    0.12       0  4983.1    0.05       0
  4988.9    0.12       0  5024.3    0.07       0
Bank Sta=4983.1,4988.9
Exp/Cntr=0.3,0.1

Type RM Length L Ch R = 1,21605,505,505,505
BEGIN DESCRIPTION:
Stream0752 26.0
END DESCRIPTION:
XS GIS Cut Line= 3
      2459525.00     13665724.99      2459625.00     13667325.00
      2460125.03     13667675.02
#Sta/Elev= 30
  3400.7  254.43  3510.9  248.55  3581.1  246.83  3601.1  244.90  3622.9  244.20
  3651.2  242.82  3804.7  239.19  3941.8  236.99  3964.3  237.33  4082.0  234.45
  4152.2  234.74  4302.5  232.36  4522.9  233.61  4843.5  231.95  4903.6  232.16
  4953.7  233.47  4973.8  232.51  4993.8  232.98  5006.9  231.77  5014.4  228.90
  5014.9  228.40  5020.3  228.90  5040.5  231.36  5067.9  232.23  5089.3  234.12
  5154.2  234.81  5179.7  236.24  5215.3  236.50  5461.5  241.33  5614.2  243.71
#Mann=8,-1,0
  3400.7    0.07       0  3622.9    0.05       0  3804.7    0.07       0
  5014.4    0.05       0  5020.3    0.07       0  5179.7    0.05       0
  5215.3    0.07       0  5461.5   0.035       0
Bank Sta=5014.4,5020.3
Exp/Cntr=0.3,0.1

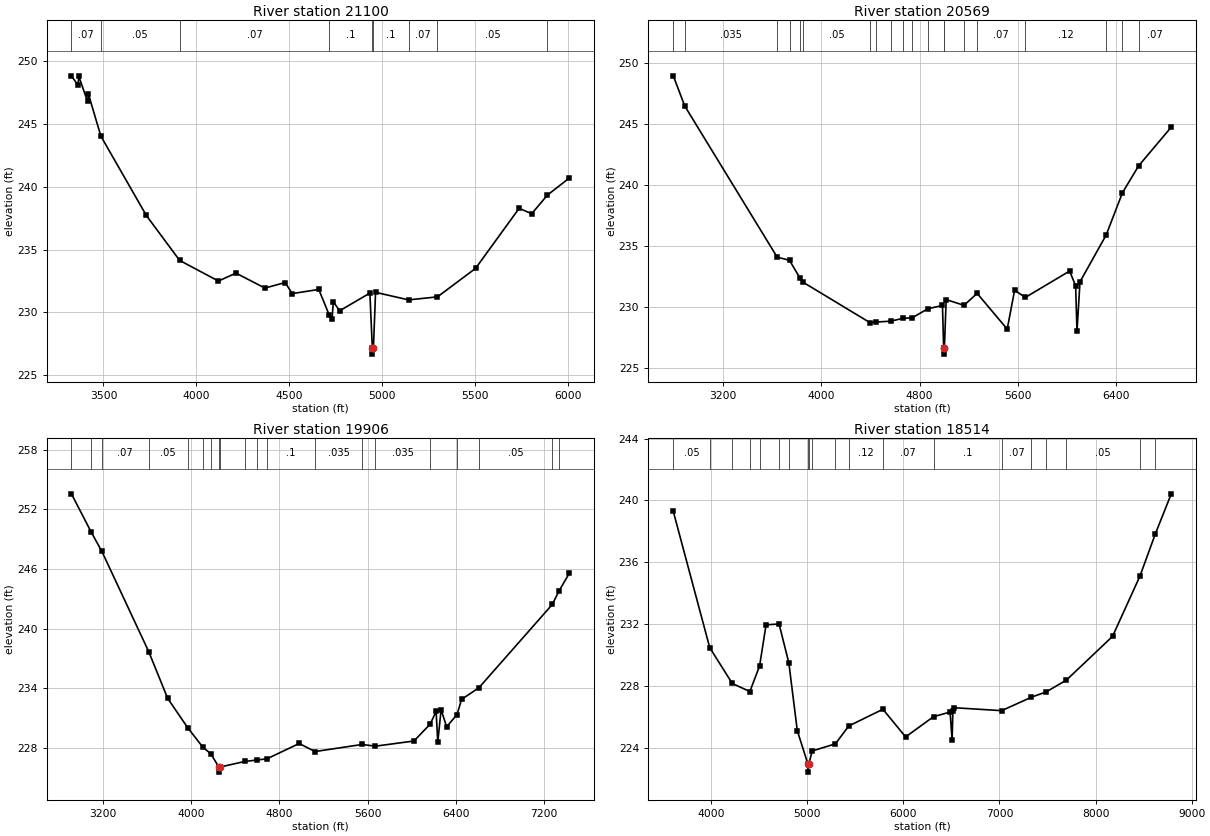
Type RM Length L Ch R = 1,21100,531,531,531
BEGIN DESCRIPTION:
E21312
END DESCRIPTION:
XS GIS Cut Line= 3
      2458922.86     13665768.79      2459276.24     13667601.44
      2460039.06     13667880.31
#Sta/Elev= 30
  3327.7  248.84  3362.4  248.10  3367.5  248.79  3414.3  246.80  3419.4  247.36
  3486.3  244.03  3730.6  237.72  3909.8  234.14  4118.2  232.50  4212.7  233.13
  4368.3  231.94  4477.1  232.38  4515.4  231.50  4658.0  231.83  4714.7  229.78
  4729.3  229.48  4736.5  230.85  4770.0  230.13  4932.9  231.54  4946.1  227.18
  4946.6  226.68  4952.0  227.18  4963.5  231.60  5141.0  231.00  5296.5  231.24
  5501.6  233.51  5735.8  238.29  5803.3  237.86  5888.3  239.35  6006.3  240.71
#Mann=9,-1,0
  3327.7    0.07       0  3486.3    0.05       0  3909.8    0.07       0
  4714.7     0.1       0  4946.1    0.05       0  4952.0     0.1       0
  5141.0    0.07       0  5296.5    0.05       0  5888.3    0.07       0
Bank Sta=4946.1,4952
Exp/Cntr=0.3,0.1

Type RM Length L Ch R = 1,20569,663,663,663
BEGIN DESCRIPTION:
Stream0752 25.0
END DESCRIPTION:
XS GIS Cut Line= 3
      2458405.11     13665456.44      2458758.50     13667420.64
      2459497.41     13669341.80
#Sta/Elev= 30
  2795.0  248.94  2888.0  246.47  3640.6  234.08  3741.2  233.82  3825.1  232.38
  3853.6  232.01  4396.2  228.71  4445.3  228.76  4563.9  228.83  4663.3  229.06
  4739.9  229.11  4867.7  229.85  4986.4  230.12  4995.9  226.63  4996.4  226.13
  5002.0  226.63  5016.4  230.60  5161.9  230.13  5268.5  231.11  5513.3  228.18
  5573.5  231.36  5661.5  230.78  6021.4  232.94  6070.4  231.73  6081.4  228.00
  6106.0  232.06  6318.7  235.89  6451.6  239.36  6583.9  241.57  6849.1  244.74
#Mann=20,-1,0
  2795.0    0.07       0  2888.0   0.035       0  3640.6    0.05       0
  3741.2    0.07       0  3825.1    0.05       0  3853.6    0.05       0
  4396.2    0.07       0  4445.3    0.05       0  4563.9    0.07       0
  4663.3     0.1       0  4739.9    0.07       0  4867.7     0.1       0
  4995.9    0.05       0  5002.0     0.1       0  5161.9    0.12       0
  5268.5    0.07       0  5661.5    0.12       0  6318.7    0.07       0
  6451.6   0.035       0  6583.9    0.07       0
Bank Sta=4995.9,5002
Exp/Cntr=0.3,0.1

Type RM Length L Ch R = 1,19906,1392,1392,1392
BEGIN DESCRIPTION:
Stream0752 24.0
END DESCRIPTION:
XS GIS Cut Line= 3
      2457961.33     13665604.39      2458240.75     13667831.54
      2459505.75     13669720.83
#Sta/Elev= 30
  2912.7  253.56  3089.6  249.76  3189.2  247.76  3613.4  237.70  3785.4  233.00
  3966.5  230.05  4107.1  228.05  4176.5  227.43  4250.7  226.07  4251.2  225.57
  4256.8  226.07  4484.3  226.64  4596.2  226.79  4686.8  226.91  4979.4  228.45
  5122.7  227.64  5549.3  228.35  5670.2  228.18  6020.3  228.70  6167.8  230.40
  6221.5  231.68  6236.5  228.57  6266.5  231.85  6316.8  230.13  6411.2  231.36
  6452.6  232.89  6610.1  234.06  7276.0  242.44  7334.1  243.75  7431.0  245.59
#Mann=20,-1,0
  2912.7    0.07       0  3089.6   0.035       0  3189.2    0.07       0
  3613.4    0.05       0  3966.5    0.07       0  4107.1    0.05       0
  4176.5    0.07       0  4250.7    0.05       0  4256.8    0.07       0
  4484.3   0.035       0  4596.2    0.07       0  4686.8     0.1       0
  5122.7   0.035       0  5549.3    0.07       0  5670.2   0.035       0
  6167.8    0.12       0  6411.2    0.05       0  6610.1    0.05       0
  7276.0    0.07       0  7334.1    0.05       0
Bank Sta=4250.7,4256.8
Exp/Cntr=0.3,0.1

Type RM Length L Ch R = 1,18514,0,0,0
BEGIN DESCRIPTION:
Stream0752 23.0
END DESCRIPTION:
XS GIS Cut Line= 3
      2457090.21     13665571.58      2457583.30     13667880.85
      2459309.13     13670108.00
#Sta/Elev= 30
  3608.6  239.29  3987.5  230.47  4221.9  228.15  4404.7  227.63  4506.0  229.28
  4573.3  231.95  4708.7  232.00  4810.0  229.49  4898.0  225.10  5009.8  222.91
  5010.3  222.41  5016.2  222.91  5053.3  223.78  5293.8  224.24  5433.7  225.40
  5788.6  226.48  6024.7  224.69  6314.6  226.00  6487.0  226.30  6508.1  224.48
  6516.2  226.40  6530.7  226.58  7022.9  226.39  7332.8  227.26  7487.8  227.61
  7696.8  228.37  8176.5  231.20  8461.4  235.10  8623.0  237.86  8787.5  240.43
#Mann=20,-1,0
  3608.6    0.05       0  3987.5    0.07       0  4221.9   0.035       0
  4404.7    0.07       0  4506.0    0.12       0  4708.7    0.07       0
  4810.0     0.1       0  5009.8    0.05       0  5016.2    0.07       0
  5053.3     0.1       0  5293.8     0.1       0  5433.7    0.12       0
  5788.6    0.07       0  6314.6     0.1       0  7022.9    0.07       0
  7332.8     0.1       0  7487.8     0.1       0  7696.8    0.05       0
  8461.4    0.05       0  8623.0   0.035       0
Bank Sta=5009.8,5016.2
Exp/Cntr=0.3,0.1

Chan Stop Cuts=-1