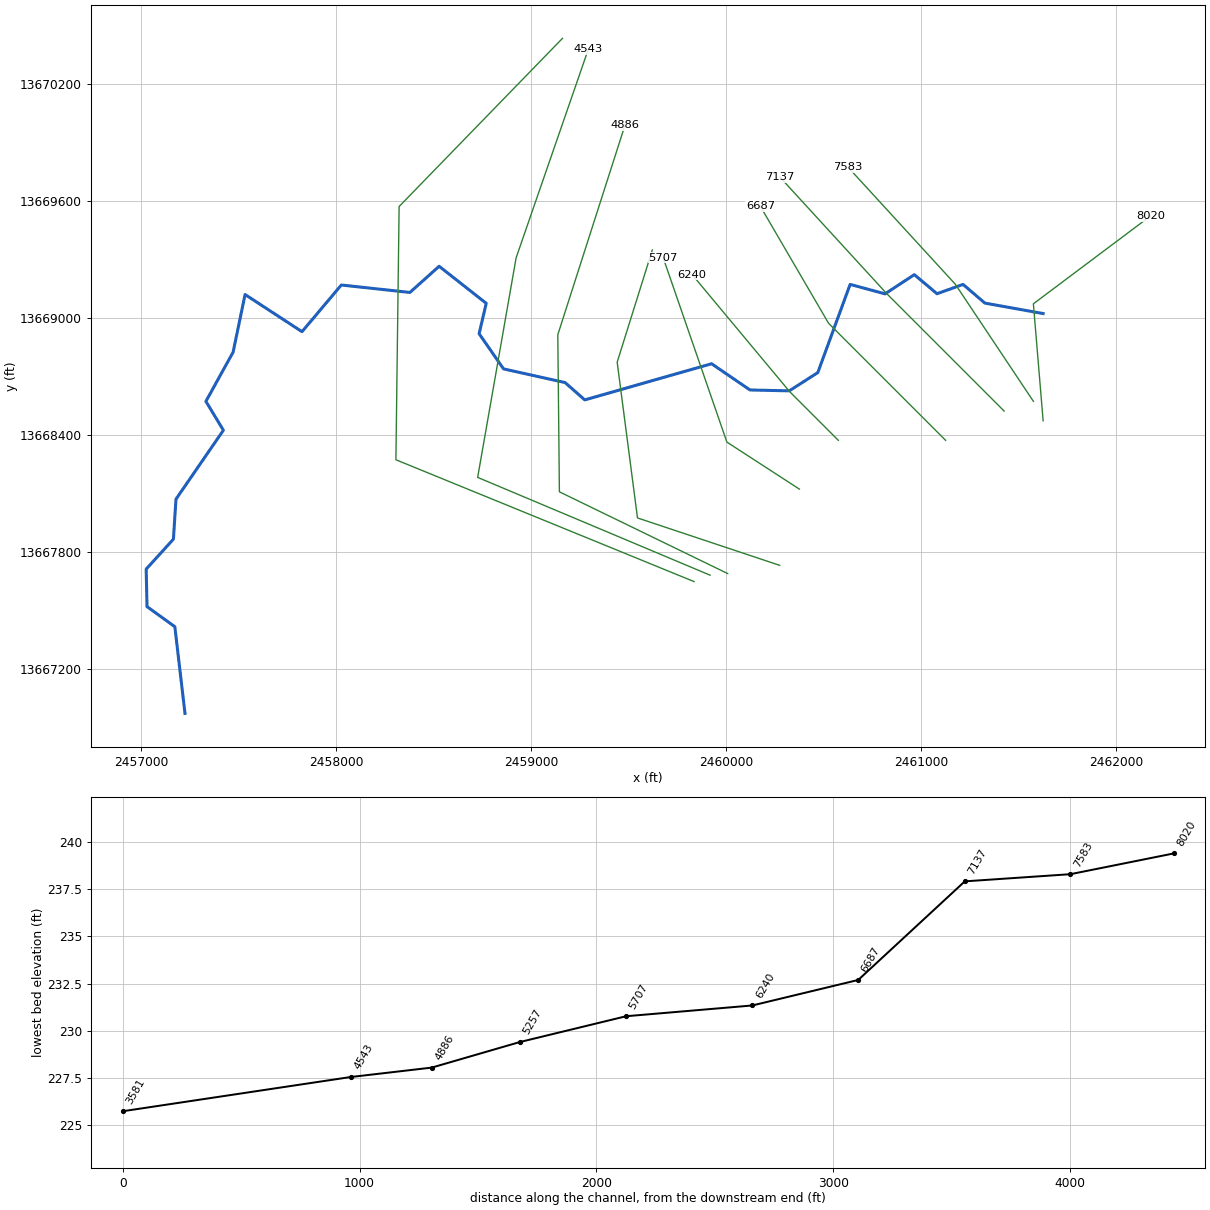
--- Stream0753.prj (project) ---

Proj Title=Stream0753 Base Level Engineering
Current Plan=p01
Default Exp/Contr=0.3,0.1
English Units
Geom File=g01
Flow File=f01
Plan File=p01
BEGIN DESCRIPTION:
Stream0753
END DESCRIPTION:

--- Stream0753.p01 (plan) ---

Plan Title=Multiple Run
Short Identifier=Multiple
Geom File=g01
Flow File=f01
Subcritical Flow
K Sum by GR= 0
Std Step Tol= 0.01
Critical Tol= 0.01
Num of Std Step Trials= 20
Max Error Tol= 0.3
Flow Tol Ratio= 0.001
Split Flow NTrial= 30
Split Flow Tol= 0.02
Split Flow Ratio= 0.02
Log Output Level= 0
Friction Slope Method= 1
Unsteady Friction Slope Method= 2
Unsteady Bridges Friction Slope Method= 1
Parabolic Critical Depth
Global Vel Dist=  1 , 1 , 1
Global Log Level= 0
CheckData=True
Encroach Param= -1, 0, 0, 0
BEGIN DESCRIPTION:
Multiple Run
END DESCRIPTION:

--- Stream0753.f01 (steady flow) ---

Flow Title=Multiple
Number of Profiles=7
Profile Names=10-year,25-year,50-year,1pct_min,100-year,1pct_plu,500-year
River Rch & RM= Stream0753,Reach-1,8020
     428     664     867     549    1096    2187    1732
Boundary for River Rch & Prof#=Stream0753,Reach-1,1
Up Type=0
Dn Type=3
Dn Slope=0.005
Boundary for River Rch & Prof#=Stream0753,Reach-1,2
Up Type=0
Dn Type=3
Dn Slope=0.005
Boundary for River Rch & Prof#=Stream0753,Reach-1,3
Up Type=0
Dn Type=3
Dn Slope=0.005
Boundary for River Rch & Prof#=Stream0753,Reach-1,4
Up Type=0
Dn Type=3
Dn Slope=0.005
Boundary for River Rch & Prof#=Stream0753,Reach-1,5
Up Type=0
Dn Type=3
Dn Slope=0.005
Boundary for River Rch & Prof#=Stream0753,Reach-1,6
Up Type=0
Dn Type=3
Dn Slope=0.005
Boundary for River Rch & Prof#=Stream0753,Reach-1,7
Up Type=0
Dn Type=3
Dn Slope=0.005

--- Stream0753.g01 (geometry) ---

Geom Title=Existing Conditions

River Reach=Stream0753,Reach-1
Reach XY= 30
      2461625.00     13669025.00      2461326.47     13669078.55
      2461214.37     13669174.39      2461081.04     13669126.63
      2460964.36     13669224.44      2460814.52     13669125.94
      2460635.45     13669174.47      2460469.64     13668722.30
      2460323.42     13668628.68      2460121.77     13668633.24
      2459925.10     13668767.68      2459274.90     13668582.33
      2459173.50     13668671.36      2458858.20     13668741.42
      2458733.04     13668921.68      2458769.61     13669077.44
      2458528.15     13669267.45      2458378.27     13669133.23
      2458026.55     13669171.34      2457825.01     13668932.07
      2457533.15     13669122.51      2457471.63     13668826.74
      2457332.30     13668574.92      2457421.89     13668426.65
      2457178.82     13668073.41      2457165.70     13667868.33
      2457026.05     13667714.57      2457030.36     13667522.30
      2457173.02     13667419.33      2457225.00     13666975.00

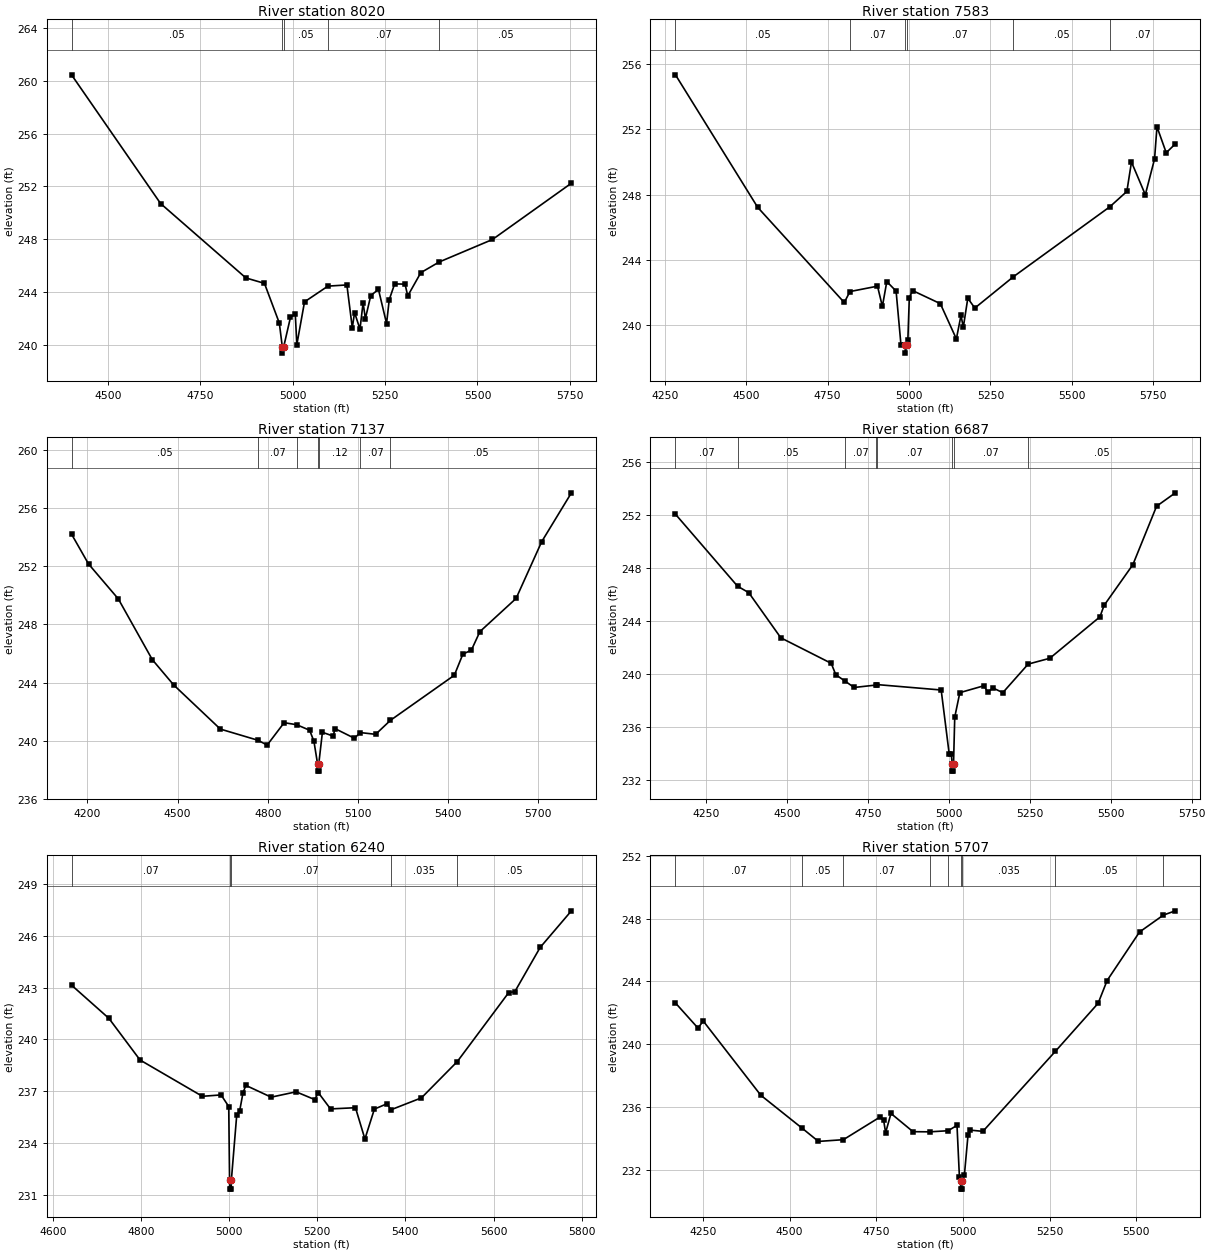
Type RM Length L Ch R = 1,8020,437,437,437
BEGIN DESCRIPTION:
Stream0753 9.0
END DESCRIPTION:
XS GIS Cut Line= 3
      2461625.00     13668474.98      2461575.00     13669075.00
      2462175.00     13669525.00
#Sta/Elev= 30
  4402.0  260.45  4642.9  250.71  4873.6  245.08  4923.8  244.67  4964.0  241.67
  4972.0  239.89  4972.2  239.39  4976.0  239.89  4994.1  242.09  5007.2  242.35
  5011.4  240.03  5032.2  243.27  5095.5  244.46  5146.8  244.55  5161.4  241.31
  5167.6  242.46  5182.2  241.20  5190.6  243.20  5196.8  242.00  5211.4  243.75
  5232.2  244.21  5254.1  241.63  5261.4  243.44  5276.0  244.63  5304.1  244.61
  5311.4  243.72  5346.8  245.48  5396.7  246.29  5540.6  247.99  5754.1  252.25
#Mann=5,-1,0
  4402.0    0.05       0  4972.0    0.05       0  4976.0    0.05       0
  5095.5    0.07       0  5396.7    0.05       0
Bank Sta=4972,4976
Exp/Cntr=0.3,0.1

Type RM Length L Ch R = 1,7583,446,446,446
BEGIN DESCRIPTION:
Stream0753 8.0
END DESCRIPTION:
XS GIS Cut Line= 3
      2461574.98     13668575.03      2461175.00     13669175.00
      2460625.01     13669774.99
#Sta/Elev= 30
  4282.8  255.33  4535.2  247.22  4801.1  241.39  4818.7  242.06  4903.2  242.39
  4918.2  241.15  4931.8  242.67  4960.3  242.09  4975.3  238.79  4988.4  238.79
  4988.6  238.29  4992.4  238.79  4996.4  239.08  5000.9  241.68  5011.0  242.12
  5096.1  241.32  5145.4  239.16  5159.6  240.60  5166.7  239.87  5180.5  241.65
  5202.1  241.05  5320.7  242.97  5616.6  247.25  5668.9  248.19  5683.1  249.99
  5725.6  247.99  5754.0  250.18  5761.4  252.15  5789.8  250.56  5817.8  251.10
#Mann=6,-1,0
  4282.8    0.05       0  4818.7    0.07       0  4988.4    0.05       0
  4992.4    0.07       0  5320.7    0.05       0  5616.6    0.07       0
Bank Sta=4988.4,4992.4
Exp/Cntr=0.3,0.1

Type RM Length L Ch R = 1,7137,450,450,450
BEGIN DESCRIPTION:
Stream0753 7.0
END DESCRIPTION:
XS GIS Cut Line= 3
      2461424.97     13668525.03      2460825.00     13669125.00
      2460275.02     13669724.98
#Sta/Elev= 30
  4147.4  254.20  4203.9  252.15  4302.9  249.75  4416.1  245.57  4486.8  243.84
  4642.3  240.80  4767.6  240.03  4797.9  239.70  4854.5  241.24  4896.2  241.10
  4939.3  240.72  4953.5  239.96  4965.6  238.41  4965.8  237.91  4969.3  237.91
  4969.6  238.41  4981.7  240.58  5017.2  240.32  5023.9  240.83  5088.1  240.17
  5107.9  240.56  5158.7  240.44  5207.8  241.40  5420.4  244.50  5448.8  245.95
  5477.2  246.23  5505.5  247.50  5625.8  249.78  5710.9  253.68  5809.8  257.04
#Mann=7,-1,0
  4147.4    0.05       0  4767.6    0.07       0  4896.2    0.12       0
  4965.6    0.05       0  4969.6    0.12       0  5107.9    0.07       0
  5207.8    0.05       0
Bank Sta=4965.6,4969.6
Exp/Cntr=0.3,0.1

Type RM Length L Ch R = 1,6687,447,447,447
BEGIN DESCRIPTION:
Stream0753 6.0
END DESCRIPTION:
XS GIS Cut Line= 3
      2461125.01     13668374.99      2460525.00     13668975.00
      2460174.98     13669575.03
#Sta/Elev= 30
  4156.5  252.04  4348.1  246.62  4382.8  246.13  4481.8  242.73  4637.3  240.81
  4651.5  239.95  4680.0  239.47  4708.1  238.99  4774.4  239.17  4777.7  239.21
  4976.8  238.80  5001.5  234.00  5007.9  234.00  5010.9  233.19  5011.1  232.69
  5014.6  232.69  5014.9  233.19  5018.7  236.76  5034.4  238.60  5108.8  239.12
  5120.8  238.63  5136.1  238.96  5167.1  238.60  5245.3  240.75  5312.2  241.19
  5466.9  244.31  5479.7  245.17  5568.6  248.24  5641.8  252.64  5699.7  253.65
#Mann=8,-1,0
  4156.5    0.07       0  4348.1    0.05       0  4680.0    0.07       0
  4774.4    0.05       0  4777.7    0.07       0  5010.9    0.05       0
  5014.9    0.07       0  5245.3    0.05       0
Bank Sta=5010.9,5014.9
Exp/Cntr=0.3,0.1

Type RM Length L Ch R = 1,6240,533,533,533
BEGIN DESCRIPTION:
Stream0753 5.0
END DESCRIPTION:
XS GIS Cut Line= 3
      2460574.99     13668375.01      2460325.00     13668625.00
      2459824.97     13669225.03
#Sta/Elev= 30
  4642.2  243.14  4727.0  241.22  4797.7  238.81  4939.2  236.71  4981.6  236.79
  4999.0  236.12  5000.9  231.84  5001.1  231.34  5004.6  231.34  5004.9  231.84
  5017.2  235.64  5023.7  235.85  5031.5  236.93  5038.0  237.34  5095.3  236.66
  5151.9  236.97  5194.2  236.52  5202.1  236.93  5230.0  235.98  5286.7  236.05
  5308.1  234.24  5329.6  235.97  5358.3  236.28  5367.1  235.93  5436.4  236.62
  5517.8  238.72  5634.2  242.70  5648.5  242.77  5705.8  245.32  5776.8  247.44
#Mann=5,-1,0
  4642.2    0.07       0  5000.9    0.05       0  5004.9    0.07       0
  5367.1   0.035       0  5517.8    0.05       0
Bank Sta=5000.9,5004.9
Exp/Cntr=0.3,0.1

Type RM Length L Ch R = 1,5707,450,450,450
BEGIN DESCRIPTION:
Stream0753 4.0
END DESCRIPTION:
XS GIS Cut Line= 3
      2460375.02     13668124.99      2460003.47     13668365.97
      2459677.15     13669310.22
#Sta/Elev= 30
  4170.9  242.63  4235.9  241.03  4251.0  241.48  4417.1  236.75  4536.9  234.64
  4583.3  233.81  4655.3  233.92  4760.8  235.36  4771.4  235.15  4777.1  234.37
  4792.6  235.59  4856.1  234.43  4904.1  234.42  4957.3  234.49  4983.0  234.83
  4990.0  231.53  4993.3  231.27  4993.6  230.77  4997.1  230.77  4997.3  231.27
  5004.2  231.64  5014.8  234.22  5021.2  234.53  5057.7  234.45  5266.8  239.55
  5390.1  242.61  5416.0  244.06  5509.5  247.15  5578.4  248.23  5612.8  248.50
#Mann=9,-1,0
  4170.9    0.07       0  4536.9    0.05       0  4655.3    0.07       0
  4904.1    0.05       0  4957.3   0.035       0  4993.3   0.035       0
  4997.3   0.035       0  5266.8    0.05       0  5578.4    0.07       0
Bank Sta=4993.3,4997.3
Exp/Cntr=0.3,0.1

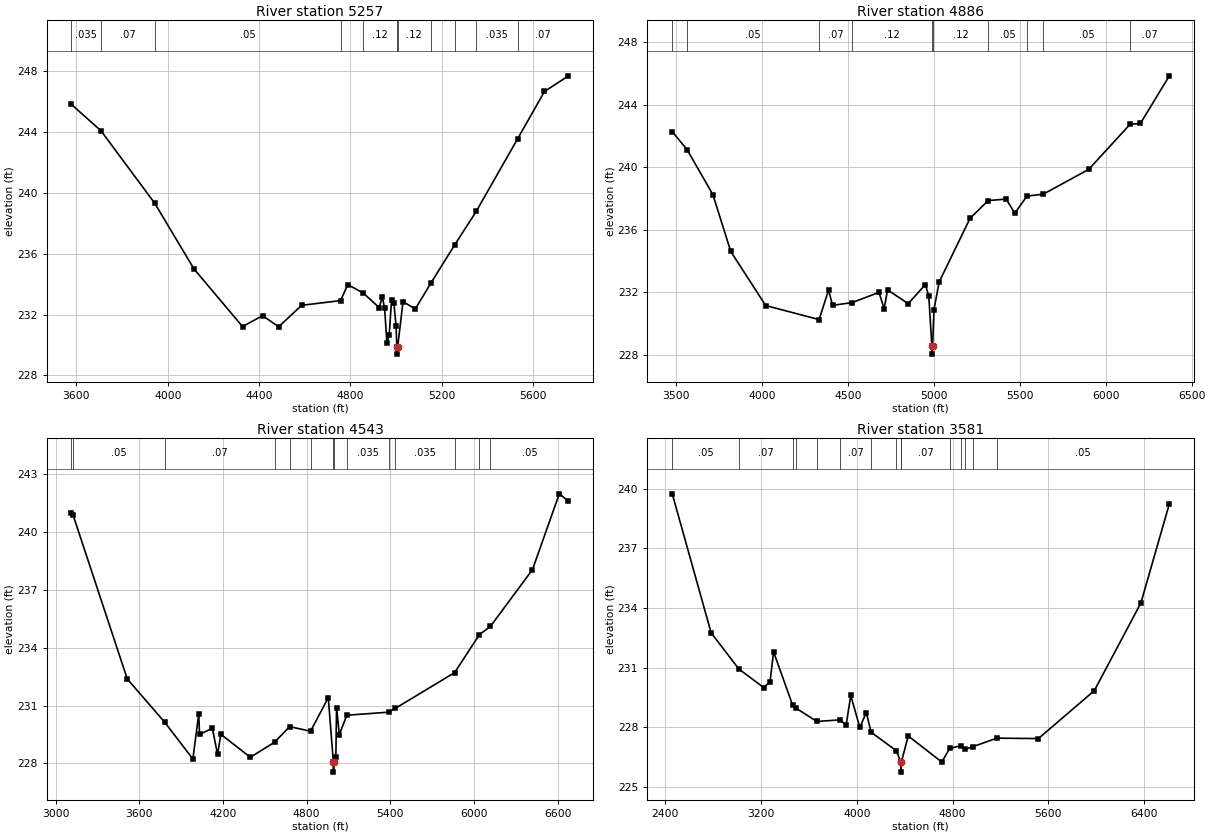
Type RM Length L Ch R = 1,5257,371,371,371
BEGIN DESCRIPTION:
XS7651
END DESCRIPTION:
XS GIS Cut Line= 4
      2460274.33     13667734.02      2459545.14     13667977.08
      2459440.97     13668775.69      2459621.19     13669351.02
#Sta/Elev= 30
  3578.0  245.82  3708.0  244.08  3942.5  239.33  4114.9  235.00  4327.6  231.21
  4415.1  231.93  4485.7  231.20  4586.6  232.61  4756.8  232.92  4788.3  233.97
  4855.7  233.42  4926.0  232.46  4939.5  233.16  4949.6  232.44  4959.7  230.13
  4969.8  230.68  4979.9  232.93  4990.0  232.79  4999.9  231.23  5003.0  229.90
  5003.2  229.40  5007.0  229.90  5030.3  232.85  5084.0  232.37  5152.6  234.08
  5256.8  236.59  5351.0  238.79  5531.7  243.55  5649.8  246.67  5754.9  247.70
#Mann=11,-1,0
  3578.0   0.035       0  3708.0    0.07       0  3942.5    0.05       0
  4756.8    0.07       0  4855.7    0.12       0  5003.0    0.05       0
  5007.0    0.12       0  5152.6   0.035       0  5256.8    0.07       0
  5351.0   0.035       0  5531.7    0.07       0
Bank Sta=5003,5007
Exp/Cntr=0.3,0.1

Type RM Length L Ch R = 1,4886,343,343,343
BEGIN DESCRIPTION:
E21315
END DESCRIPTION:
XS GIS Cut Line= 4
      2460007.69     13667691.82      2459144.75     13668110.96
      2459136.54     13668916.34      2459481.23     13669991.48
#Sta/Elev= 30
  3476.4  242.29  3563.5  241.12  3712.8  238.26  3817.0  234.62  4020.1  231.16
  4331.3  230.26  4386.6  232.16  4409.2  231.17  4523.8  231.35  4679.8  232.00
  4709.8  230.96  4729.8  232.16  4849.8  231.28  4949.8  232.50  4969.8  231.75
  4987.8  228.55  4988.1  228.05  4991.8  228.55  4999.8  230.89  5029.8  232.66
  5209.8  236.74  5316.1  237.88  5419.9  237.97  5470.8  237.07  5540.9  238.16
  5637.3  238.29  5901.3  239.88  6141.5  242.76  6201.5  242.81  6370.2  245.86
#Mann=10,-1,0
  3476.4   0.035       0  3563.5    0.05       0  4331.3    0.07       0
  4523.8    0.12       0  4987.8    0.05       0  4991.8    0.12       0
  5316.1    0.05       0  5540.9    0.07       0  5637.3    0.05       0
  6141.5    0.07       0
Bank Sta=4987.8,4991.8
Exp/Cntr=0.3,0.1

Type RM Length L Ch R = 1,4543,962,962,962
BEGIN DESCRIPTION:
E21314
END DESCRIPTION:
XS GIS Cut Line= 4
      2459917.25     13667683.62      2458725.63     13668184.93
      2458922.86     13669310.82      2459292.69     13670379.21
#Sta/Elev= 30
  3112.2  240.96  3125.2  240.86  3513.0  232.38  3780.2  230.15  3983.8  228.23
  4025.9  230.58  4031.3  229.51  4123.6  229.82  4160.9  228.47  4184.6  229.51
  4396.2  228.32  4569.8  229.10  4678.0  229.91  4827.8  229.67  4955.1  231.41
  4991.9  228.05  4992.1  227.55  4995.9  228.05  5009.5  228.33  5014.6  230.89
  5034.5  229.50  5088.0  230.50  5389.5  230.66  5434.7  230.85  5861.7  232.71
  6039.7  234.68  6118.8  235.11  6420.2  238.05  6612.6  241.98  6678.6  241.60
#Mann=14,-1,0
  3112.2    0.07       0  3125.2    0.05       0  3780.2    0.07       0
  4569.8    0.12       0  4678.0   0.035       0  4827.8    0.12       0
  4991.9    0.05       0  4995.9    0.12       0  5088.0   0.035       0
  5389.5    0.12       0  5434.7   0.035       0  5861.7    0.05       0
  6039.7   0.035       0  6118.8    0.05       0
Bank Sta=4991.9,4995.9
Exp/Cntr=0.3,0.1

Type RM Length L Ch R = 1,3581,0,0,0
BEGIN DESCRIPTION:
E21313
END DESCRIPTION:
XS GIS Cut Line= 4
      2459835.13     13667650.73      2458306.50     13668275.33
      2458322.94     13669573.80      2459160.62     13670436.12
#Sta/Elev= 30
  2459.0  239.75  2783.2  232.76  3015.1  230.93  3222.2  230.00  3275.7  230.28
  3305.1  231.80  3464.3  229.11  3492.2  228.96  3667.0  228.29  3859.5  228.37
  3911.6  228.12  3949.9  229.60  4025.5  227.99  4079.5  228.74  4119.9  227.75
  4331.8  226.81  4368.0  226.24  4368.3  225.74  4372.0  226.24  4430.0  227.56
  4710.0  226.25  4776.1  226.93  4874.7  227.08  4903.9  226.88  4973.2  227.03
  5170.3  227.45  5517.3  227.43  5983.9  229.84  6372.9  234.25  6611.1  239.25
#Mann=15,-1,0
  2459.0    0.05       0  3015.1    0.07       0  3464.3    0.12       0
  3492.2    0.07       0  3667.0     0.1       0  3859.5    0.07       0
  4119.9    0.12       0  4331.8    0.07       0  4368.0    0.05       0
  4372.0    0.07       0  4776.1    0.12       0  4874.7     0.1       0
  4903.9    0.12       0  4973.2     0.1       0  5170.3    0.05       0
Bank Sta=4368,4372
Exp/Cntr=0.3,0.1

Chan Stop Cuts=-1