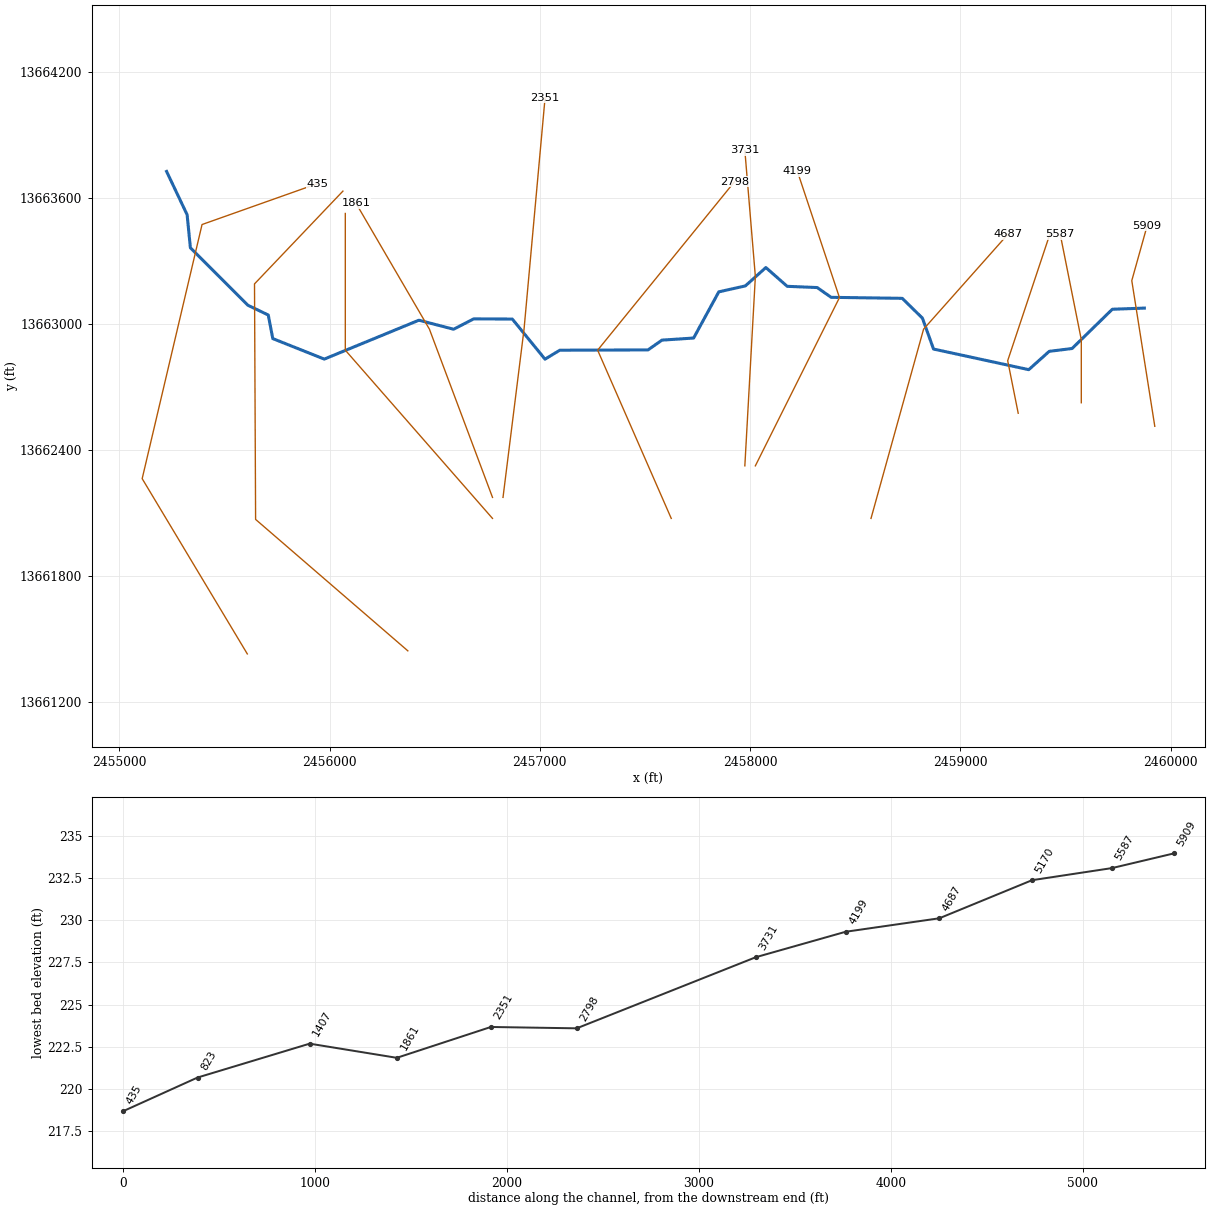
--- Stream0754.prj (project) ---

Proj Title=Stream0754 Base Level Engineering
Current Plan=p01
Default Exp/Contr=0.3,0.1
English Units
Geom File=g01
Flow File=f01
Plan File=p01
BEGIN DESCRIPTION:
Stream0754
END DESCRIPTION:

--- Stream0754.p01 (plan) ---

Plan Title=Multiple Run
Short Identifier=Multiple
Geom File=g01
Flow File=f01
Subcritical Flow
K Sum by GR= 0
Std Step Tol= 0.01
Critical Tol= 0.01
Num of Std Step Trials= 20
Max Error Tol= 0.3
Flow Tol Ratio= 0.001
Split Flow NTrial= 30
Split Flow Tol= 0.02
Split Flow Ratio= 0.02
Log Output Level= 0
Friction Slope Method= 1
Unsteady Friction Slope Method= 2
Unsteady Bridges Friction Slope Method= 1
Parabolic Critical Depth
Global Vel Dist=  1 , 1 , 1
Global Log Level= 0
CheckData=True
Encroach Param= -1, 0, 0, 0
BEGIN DESCRIPTION:
Multiple Run
END DESCRIPTION:

--- Stream0754.f01 (steady flow) ---

Flow Title=Multiple
Number of Profiles=7
Profile Names=10-year,25-year,50-year,1pct_min,100-year,1pct_plu,500-year
River Rch & RM= Stream0754,Reach-1,5909
     581     920    1220     784    1564    3120    2542
River Rch & RM= Stream0754,Reach-1,2798
     605     957    1267     812    1620    3231    2621
Boundary for River Rch & Prof#=Stream0754,Reach-1,1
Up Type=0
Dn Type=3
Dn Slope=0.005
Boundary for River Rch & Prof#=Stream0754,Reach-1,2
Up Type=0
Dn Type=3
Dn Slope=0.005
Boundary for River Rch & Prof#=Stream0754,Reach-1,3
Up Type=0
Dn Type=3
Dn Slope=0.005
Boundary for River Rch & Prof#=Stream0754,Reach-1,4
Up Type=0
Dn Type=3
Dn Slope=0.005
Boundary for River Rch & Prof#=Stream0754,Reach-1,5
Up Type=0
Dn Type=3
Dn Slope=0.005
Boundary for River Rch & Prof#=Stream0754,Reach-1,6
Up Type=0
Dn Type=3
Dn Slope=0.005
Boundary for River Rch & Prof#=Stream0754,Reach-1,7
Up Type=0
Dn Type=3
Dn Slope=0.005

--- Stream0754.g01 (geometry) ---

Geom Title=Existing Conditions

River Reach=Stream0754,Reach-1
Reach XY= 30
      2459875.00     13663075.00      2459722.54     13663069.57
      2459531.17     13662882.86      2459422.57     13662869.45
      2459325.10     13662782.33      2458872.27     13662880.35
      2458819.48     13663027.44      2458723.55     13663121.47
      2458385.50     13663126.22      2458319.06     13663172.73
      2458176.47     13663178.57      2458075.00     13663267.90
      2457977.42     13663180.56      2457851.10     13663152.28
      2457731.48     13662932.70      2457580.94     13662922.73
      2457514.50     13662876.22      2457094.98     13662874.81
      2457024.68     13662832.23      2456869.16     13663022.95
      2456685.51     13663023.78      2456590.16     13662974.53
      2456425.00     13663017.44      2455974.99     13662832.53
      2455730.11     13662930.11      2455708.69     13663042.10
      2455611.80     13663088.64      2455338.37     13663361.68
      2455322.73     13663519.06      2455225.00     13663725.00

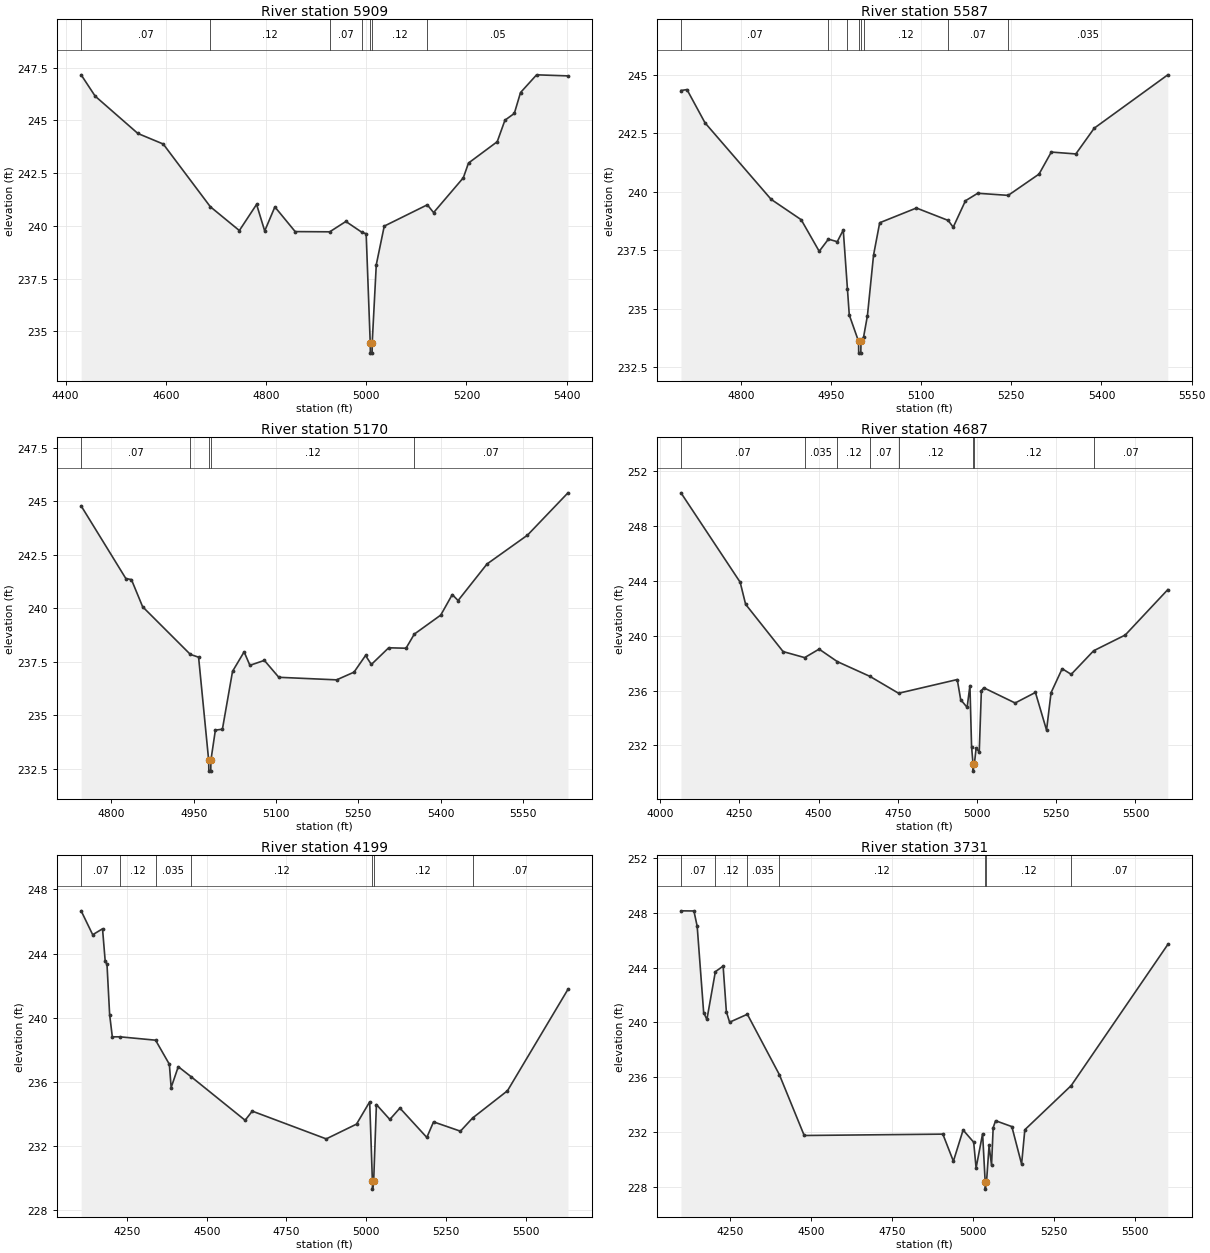
Type RM Length L Ch R = 1,5909,322,322,322
BEGIN DESCRIPTION:
XS7653
END DESCRIPTION:
XS GIS Cut Line= 3
      2459924.47     13662513.06      2459815.10     13663205.73
      2459888.03     13663466.17
#Sta/Elev= 30
  4431.0  247.16  4459.0  246.15  4544.3  244.38  4594.9  243.88  4688.8  240.91
  4746.8  239.78  4781.2  241.02  4797.4  239.76  4817.7  240.90  4858.2  239.73
  4927.2  239.72  4959.4  240.21  4991.8  239.69  4999.9  239.63  5008.0  234.47
  5008.3  233.97  5011.8  233.97  5012.0  234.47  5020.1  238.16  5036.0  239.99
  5122.0  241.00  5134.5  240.63  5193.8  242.28  5204.2  242.98  5261.5  243.99
  5276.9  245.01  5295.6  245.33  5308.0  246.32  5340.1  247.16  5402.7  247.11
#Mann=7,-1,0
  4431.0    0.07       0  4688.8    0.12       0  4927.2    0.07       0
  4991.8    0.12       0  5008.0    0.05       0  5012.0    0.12       0
  5122.0    0.05       0
Bank Sta=5008,5012
Exp/Cntr=0.3,0.1

Type RM Length L Ch R = 1,5587,417,417,417
BEGIN DESCRIPTION:
Stream0754 11.0
END DESCRIPTION:
XS GIS Cut Line= 3
      2459575.00     13662625.04      2459575.00     13662925.00
      2459474.99     13663425.04
#Sta/Elev= 30
  4700.4  244.32  4710.4  244.36  4740.4  242.94  4850.4  239.67  4900.4  238.80
  4930.4  237.45  4945.7  237.97  4960.4  237.86  4970.4  238.36  4977.3  235.86
  4980.4  234.73  4995.9  233.60  4996.1  233.10  4999.6  233.10  4999.9  233.60
  5004.3  233.80  5010.6  234.70  5020.8  237.29  5031.0  238.67  5092.1  239.30
  5144.9  238.77  5153.3  238.48  5173.7  239.61  5194.1  239.93  5244.8  239.84
  5296.1  240.75  5316.5  241.69  5357.3  241.61  5387.9  242.71  5510.3  244.99
#Mann=8,-1,0
  4700.4    0.07       0  4945.7    0.12       0  4977.3   0.035       0
  4995.9   0.035       0  4999.9   0.035       0  5004.3    0.12       0
  5144.9    0.07       0  5244.8   0.035       0
Bank Sta=4995.9,4999.9
Exp/Cntr=0.3,0.1

Type RM Length L Ch R = 1,5170,483,483,483
BEGIN DESCRIPTION:
Stream0754 10.0
END DESCRIPTION:
XS GIS Cut Line= 3
      2459274.99     13662575.04      2459225.00     13662825.00
      2459425.01     13663425.03
#Sta/Elev= 30
  4744.7  244.79  4826.2  241.39  4836.4  241.34  4856.8  240.07  4943.8  237.84
  4958.8  237.71  4977.2  232.88  4977.5  232.38  4981.0  232.38  4981.2  232.88
  4989.4  234.30  5002.2  234.34  5020.7  237.05  5041.8  237.96  5052.3  237.33
  5078.7  237.56  5105.0  236.77  5210.4  236.65  5242.1  237.01  5263.1  237.79
  5273.7  237.37  5305.3  238.15  5336.9  238.13  5352.0  238.79  5400.2  239.68
  5421.2  240.64  5431.8  240.36  5484.5  242.07  5558.3  243.42  5632.1  245.40
#Mann=5,-1,0
  4744.7    0.07       0  4943.8    0.12       0  4977.2    0.05       0
  4981.2    0.12       0  5352.0    0.07       0
Bank Sta=4977.2,4981.2
Exp/Cntr=0.3,0.1

Type RM Length L Ch R = 1,4687,488,488,488
BEGIN DESCRIPTION:
Stream0754 9.0
END DESCRIPTION:
XS GIS Cut Line= 3
      2458574.99     13662074.98      2458825.00     13662975.00
      2459225.01     13663425.02
#Sta/Elev= 30
  4065.9  250.42  4252.7  243.90  4269.9  242.29  4388.2  238.84  4456.2  238.40
  4501.8  239.02  4559.2  238.11  4662.3  237.03  4752.6  235.80  4937.7  236.80
  4948.6  235.33  4968.9  234.77  4977.7  236.36  4982.9  231.91  4987.6  230.62
  4987.9  230.12  4991.6  230.62  4997.4  231.82  5007.1  231.50  5013.8  235.98
  5021.3  236.20  5120.4  235.09  5184.4  235.86  5219.5  233.11  5233.7  235.84
  5268.8  237.59  5297.3  237.18  5368.1  238.90  5467.9  240.05  5602.1  243.36
#Mann=8,-1,0
  4065.9    0.07       0  4456.2   0.035       0  4559.2    0.12       0
  4662.3    0.07       0  4752.6    0.12       0  4987.6    0.05       0
  4991.6    0.12       0  5368.1    0.07       0
Bank Sta=4987.6,4991.6
Exp/Cntr=0.3,0.1

Type RM Length L Ch R = 1,4199,468,468,468
BEGIN DESCRIPTION:
Stream0754 8.0
END DESCRIPTION:
XS GIS Cut Line= 3
      2458025.00     13662324.99      2458425.00     13663125.00
      2458225.00     13663725.01
#Sta/Elev= 30
  4106.0  246.66  4142.3  245.17  4173.1  245.54  4181.5  243.52  4187.1  243.33
  4195.4  240.19  4203.8  238.81  4227.8  238.81  4339.5  238.60  4382.7  237.10
  4388.3  235.65  4410.7  236.95  4451.2  236.32  4620.3  233.61  4642.7  234.18
  4874.7  232.45  4969.7  233.37  5011.0  234.76  5019.5  229.82  5019.8  229.32
  5023.5  229.82  5032.1  234.59  5074.2  233.66  5105.8  234.37  5190.2  232.54
  5211.3  233.51  5295.6  232.93  5333.7  233.75  5443.2  235.45  5632.9  241.77
#Mann=7,-1,0
  4106.0    0.07       0  4227.8    0.12       0  4339.5   0.035       0
  4451.2    0.12       0  5019.5    0.05       0  5023.5    0.12       0
  5333.7    0.07       0
Bank Sta=5019.5,5023.5
Exp/Cntr=0.3,0.1

Type RM Length L Ch R = 1,3731,933,933,933
BEGIN DESCRIPTION:
Stream0754 7.0
END DESCRIPTION:
XS GIS Cut Line= 3
      2457975.00     13662325.03      2458025.00     13663225.00
      2457975.00     13663824.96
#Sta/Elev= 30
  4098.5  248.15  4138.5  248.14  4148.6  247.02  4168.6  240.71  4178.6  240.21
  4204.7  243.70  4228.7  244.11  4238.7  240.78  4248.7  240.01  4303.5  240.59
  4402.3  236.18  4479.1  231.73  4907.2  231.83  4939.8  229.85  4969.8  232.13
  5002.4  231.24  5009.9  229.36  5030.0  231.86  5038.0  228.31  5038.3  227.81
  5042.0  228.31  5050.0  231.00  5057.6  229.55  5062.6  232.30  5070.1  232.81
  5120.3  232.38  5150.4  229.64  5160.4  232.15  5303.7  235.38  5601.9  245.69
#Mann=7,-1,0
  4098.5    0.07       0  4204.7    0.12       0  4303.5   0.035       0
  4402.3    0.12       0  5038.0    0.05       0  5042.0    0.12       0
  5303.7    0.07       0
Bank Sta=5038,5042
Exp/Cntr=0.3,0.1

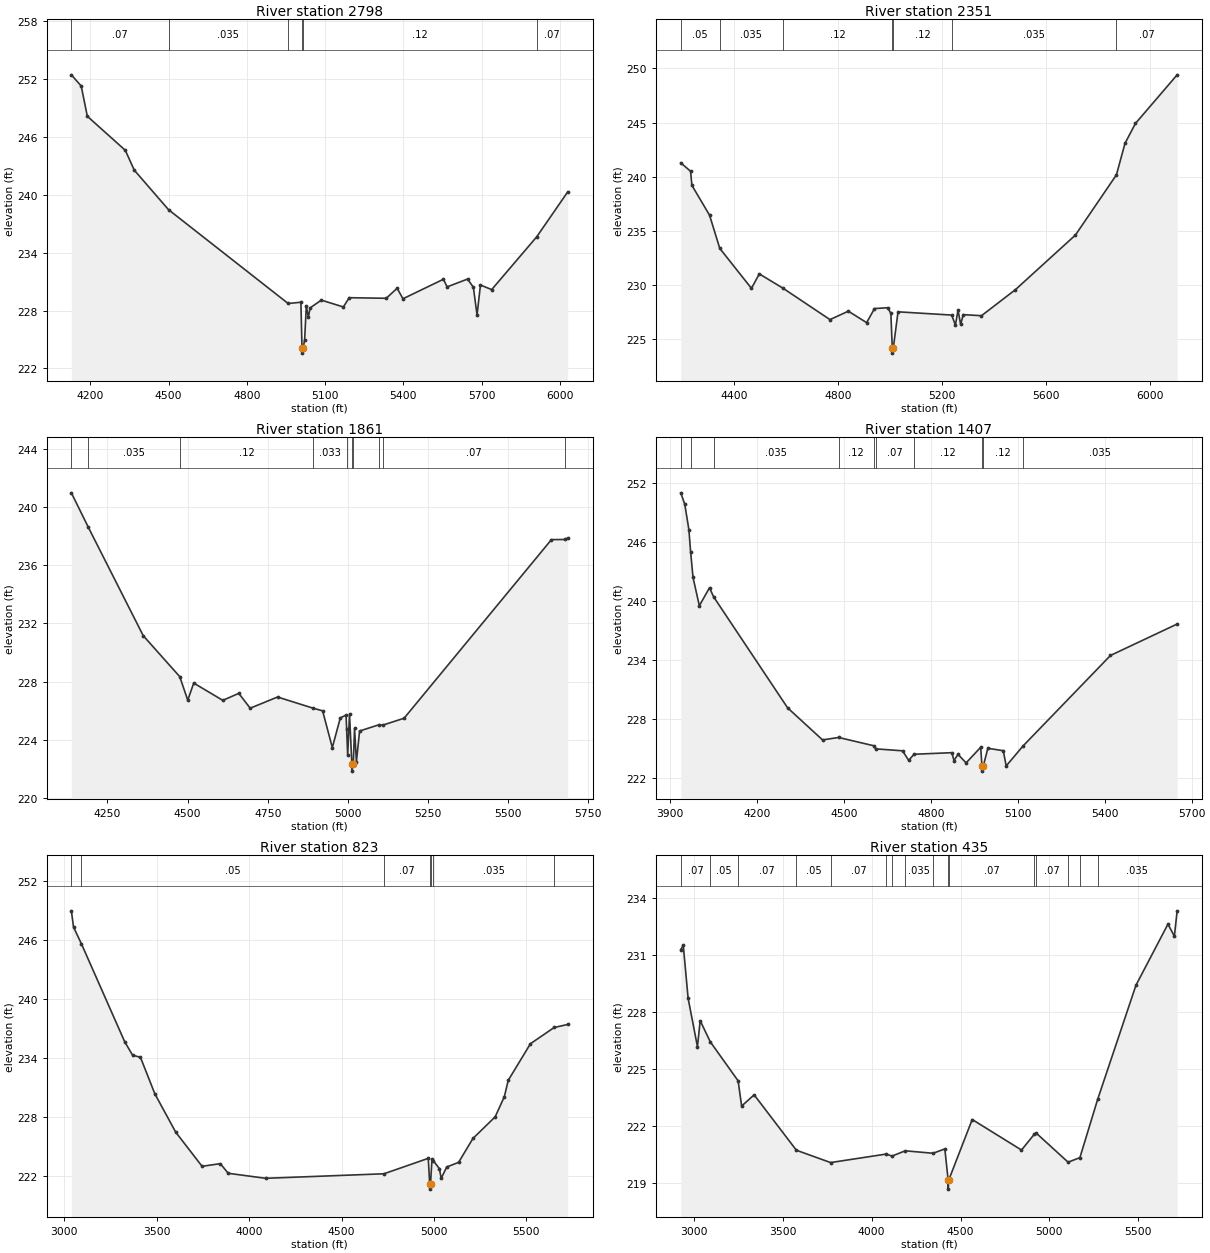
Type RM Length L Ch R = 1,2798,447,447,447
BEGIN DESCRIPTION:
Stream0754 6.0
END DESCRIPTION:
XS GIS Cut Line= 3
      2457624.99     13662075.01      2457275.00     13662875.00
      2457925.02     13663675.02
#Sta/Elev= 30
  4126.8  252.41  4164.6  251.25  4188.0  248.12  4333.8  244.59  4368.1  242.54
  4499.7  238.44  4958.3  228.73  5007.2  228.86  5011.6  224.09  5011.8  223.59
  5015.7  224.09  5021.6  224.97  5028.0  228.48  5035.9  227.29  5042.4  228.27
  5085.5  229.08  5170.2  228.37  5192.5  229.33  5334.8  229.27  5376.4  230.31
  5398.7  229.22  5554.0  231.24  5568.2  230.45  5646.5  231.26  5668.8  230.41
  5682.9  227.54  5696.0  230.64  5739.1  230.17  5911.9  235.64  6030.8  240.29
#Mann=6,-1,0
  4126.8    0.07       0  4499.7   0.035       0  4958.3    0.12       0
  5011.6    0.05       0  5015.7    0.12       0  5911.9    0.07       0
Bank Sta=5011.6,5015.7
Exp/Cntr=0.3,0.1

Type RM Length L Ch R = 1,2351,490,490,490
BEGIN DESCRIPTION:
Stream0754 5.0
END DESCRIPTION:
XS GIS Cut Line= 3
      2456825.00     13662175.02      2456925.00     13662975.00
      2457025.00     13664074.96
#Sta/Elev= 30
  4193.2  241.27  4231.0  240.49  4236.0  239.19  4304.0  236.43  4343.3  233.36
  4465.3  229.66  4495.5  231.00  4587.0  229.67  4767.6  226.77  4838.2  227.55
  4908.7  226.49  4938.9  227.79  4989.3  227.87  5001.9  227.36  5007.3  224.17
  5007.6  223.67  5011.5  224.17  5029.5  227.49  5236.1  227.19  5250.4  226.26
  5260.5  227.65  5270.5  226.33  5280.6  227.23  5350.8  227.13  5481.4  229.54
  5712.3  234.59  5870.2  240.16  5903.1  243.07  5943.3  244.91  6103.9  249.41
#Mann=7,-1,0
  4193.2    0.05       0  4343.3   0.035       0  4587.0    0.12       0
  5007.3    0.05       0  5011.5    0.12       0  5236.1   0.035       0
  5870.2    0.07       0
Bank Sta=5007.3,5011.5
Exp/Cntr=0.3,0.1

Type RM Length L Ch R = 1,1861,454,454,454
BEGIN DESCRIPTION:
Stream0754 4.0
END DESCRIPTION:
XS GIS Cut Line= 3
      2456775.02     13662174.96      2456475.00     13662975.00
      2456124.98     13663575.03
#Sta/Elev= 30
  4137.3  240.99  4190.0  238.63  4361.6  231.16  4475.6  228.34  4500.5  226.72
  4519.2  227.90  4609.9  226.71  4659.8  227.19  4695.4  226.17  4780.8  226.94
  4891.9  226.17  4921.4  225.99  4951.7  223.46  4976.6  225.50  4994.6  225.70
  4996.4  224.71  4999.6  222.94  5005.4  225.74  5012.7  222.34  5013.0  221.84
  5017.1  222.34  5021.1  224.78  5026.9  222.49  5036.8  224.60  5098.6  225.04
  5108.5  225.00  5175.7  225.48  5635.5  237.77  5679.0  237.78  5686.4  237.88
#Mann=10,-1,0
  4137.3    0.05       0  4190.0   0.035       0  4475.6    0.12       0
  4891.9   0.033       0  4996.4    0.07       0  5012.7    0.05       0
  5017.1    0.07       0  5098.6    0.12       0  5108.5    0.07       0
  5679.0   0.035       0
Bank Sta=5012.7,5017.1
Exp/Cntr=0.3,0.1

Type RM Length L Ch R = 1,1407,584,584,584
BEGIN DESCRIPTION:
Stream0754 3.0
END DESCRIPTION:
XS GIS Cut Line= 3
      2456775.01     13662074.99      2456075.00     13662875.00
      2456075.00     13663524.97
#Sta/Elev= 30
  3937.0  251.04  3950.8  249.88  3965.0  247.29  3970.9  245.06  3979.3  242.42
  4001.1  239.53  4036.2  241.37  4050.2  240.45  4305.7  229.13  4426.3  225.86
  4481.7  226.11  4602.5  225.27  4609.4  224.95  4702.5  224.75  4723.4  223.78
  4742.1  224.40  4872.4  224.56  4880.0  223.76  4893.7  224.39  4921.7  223.52
  4972.0  225.11  4976.5  223.18  4976.8  222.68  4980.9  223.18  4996.7  225.01
  5050.0  224.76  5060.0  223.21  5119.0  225.27  5420.0  234.47  5650.0  237.67
#Mann=10,-1,0
  3937.0    0.07       0  3970.9    0.05       0  4050.2   0.035       0
  4481.7    0.12       0  4602.5    0.05       0  4609.4    0.07       0
  4742.1    0.12       0  4976.5    0.05       0  4980.9    0.12       0
  5119.0   0.035       0
Bank Sta=4976.5,4980.9
Exp/Cntr=0.3,0.1

Type RM Length L Ch R = 1,823,388,388,388
BEGIN DESCRIPTION:
XS7652
END DESCRIPTION:
XS GIS Cut Line= 4
      2456372.41     13661445.30      2455648.44     13662070.31
      2455643.23     13663190.10      2456063.75     13663631.39
#Sta/Elev= 30
  3038.3  248.96  3050.1  247.31  3093.1  245.59  3326.5  235.67  3369.3  234.29
  3412.1  234.07  3490.0  230.36  3603.0  226.46  3745.5  222.99  3844.3  223.26
  3887.1  222.28  4089.4  221.77  4729.7  222.23  4969.4  223.80  4977.2  221.17
  4977.5  220.67  4981.6  221.17  4989.4  223.70  4996.1  223.57  5029.4  222.76
  5039.4  221.77  5069.4  222.92  5133.5  223.39  5211.2  225.82  5331.4  228.02
  5381.1  230.07  5402.1  231.73  5522.3  235.45  5650.5  237.10  5724.1  237.41
#Mann=7,-1,0
  3038.3    0.07       0  3093.1    0.05       0  4729.7    0.07       0
  4977.2   0.035       0  4981.6    0.07       0  4996.1   0.035       0
  5650.5    0.07       0
Bank Sta=4977.2,4981.6
Exp/Cntr=0.3,0.1

Type RM Length L Ch R = 1,435,0,0,0
BEGIN DESCRIPTION:
E21316
END DESCRIPTION:
XS GIS Cut Line= 4
      2455609.01     13661430.77      2455109.03     13662264.08
      2455393.75     13663472.41      2455941.16     13663666.43
#Sta/Elev= 30
  2925.4  231.30  2939.5  231.52  2966.8  228.73  3019.2  226.18  3034.8  227.55
  3091.2  226.44  3248.2  224.38  3268.0  223.05  3338.5  223.64  3576.2  220.72
  3768.8  220.07  4082.8  220.52  4114.0  220.41  4188.8  220.69  4345.6  220.56
  4411.8  220.79  4430.2  219.17  4430.5  218.67  4434.6  219.17  4565.9  222.34
  4843.3  220.73  4914.2  221.55  4925.4  221.63  5105.7  220.09  5172.0  220.33
  5271.9  223.40  5487.7  229.42  5667.7  232.64  5703.8  232.00  5719.4  233.34
#Mann=16,-1,0
  2925.4    0.07       0  3091.2    0.05       0  3248.2    0.07       0
  3576.2    0.05       0  3768.8    0.07       0  4082.8   0.035       0
  4114.0    0.05       0  4188.8   0.035       0  4345.6    0.07       0
  4430.2    0.05       0  4434.6    0.07       0  4914.2   0.035       0
  4925.4    0.07       0  5105.7    0.12       0  5172.0    0.07       0
  5271.9   0.035       0
Bank Sta=4430.2,4434.6
Exp/Cntr=0.3,0.1

Chan Stop Cuts=-1