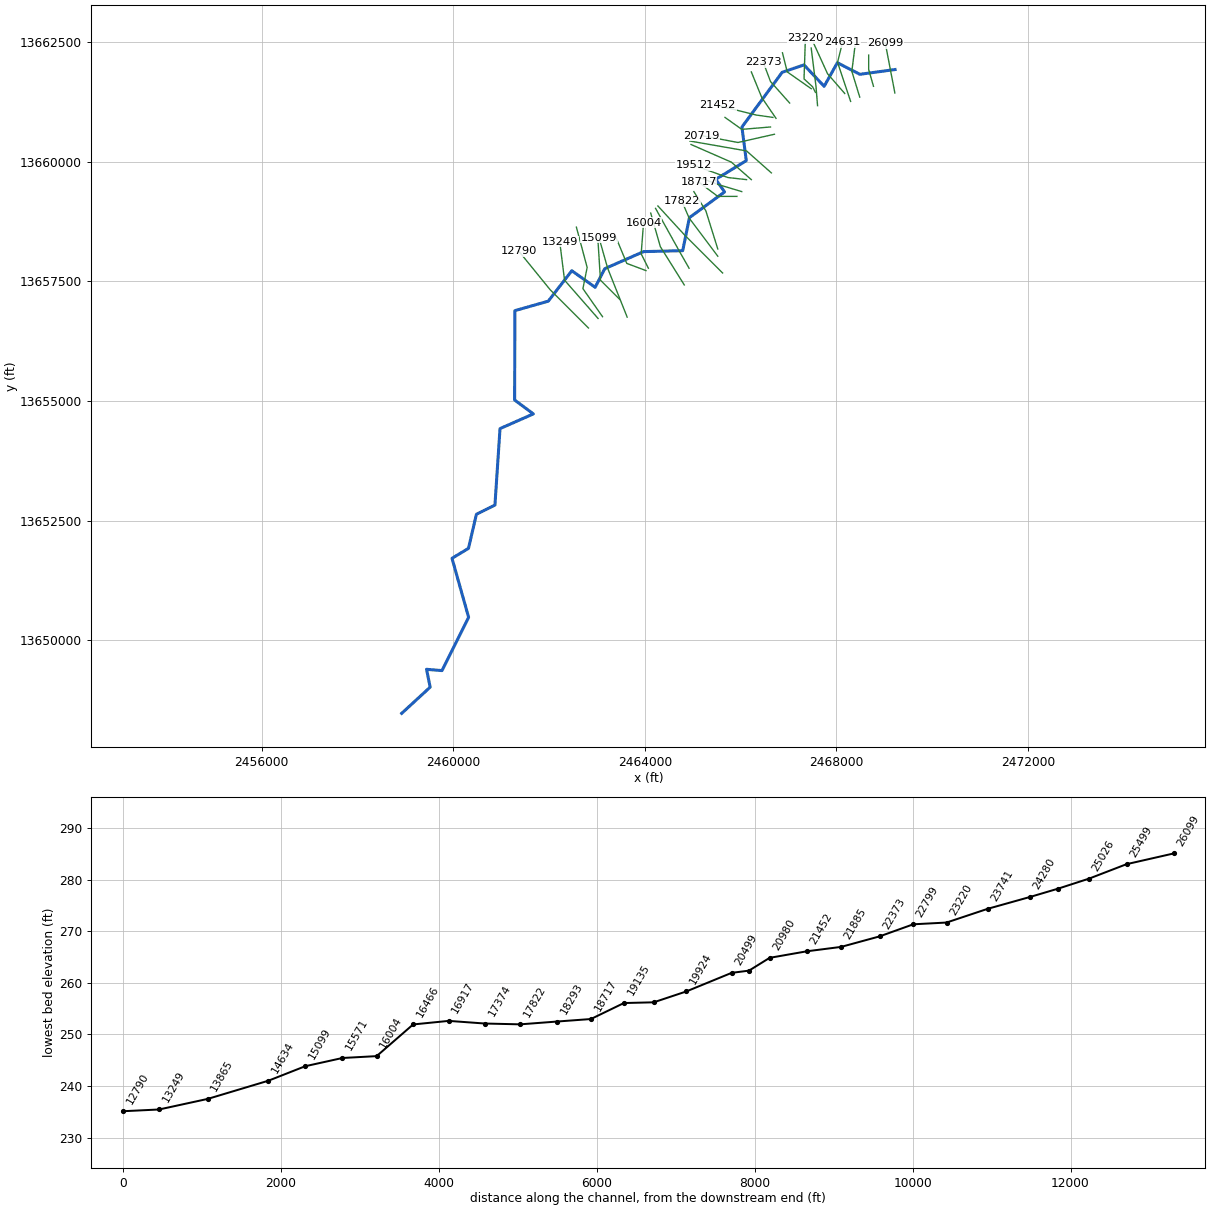
--- Stream0755.prj (project) ---

Proj Title=Stream0755 Base Level Engineering
Current Plan=p01
Default Exp/Contr=0.3,0.1
English Units
Geom File=g01
Flow File=f01
Plan File=p01
Y Axis Title=Elevation
X Axis Title(PF)=Main Channel Distance
X Axis Title(XS)=Station
BEGIN DESCRIPTION:
Stream0755
END DESCRIPTION:
DSS Export Rating Curves= 0
DSS Export Rating Curve Sorted= 0
DSS Export Volume Flow Curves= 0
DXF OffsetX= 0
DXF OffsetY= 0
DXF ScaleX= 1
DXF ScaleY= 10

--- Stream0755.p01 (plan) ---

Plan Title=Multiple Run
Short Identifier=Multiple
Geom File=g01
Flow File=f01
Subcritical Flow
K Sum by GR= 0
Std Step Tol= 0.01
Critical Tol= 0.01
Num of Std Step Trials= 20
Max Error Tol= 0.3
Flow Tol Ratio= 0.001
Split Flow NTrial= 30
Split Flow Tol= 0.02
Split Flow Ratio= 0.02
Log Output Level= 0
Friction Slope Method= 1
Unsteady Friction Slope Method= 2
Unsteady Bridges Friction Slope Method= 1
Parabolic Critical Depth
Global Vel Dist=  1 , 1 , 1
Global Log Level= 0
CheckData=True
Encroach Param= -1, 0, 0, 0
BEGIN DESCRIPTION:
Multiple Run
END DESCRIPTION:

--- Stream0755.f01 (steady flow) ---

Flow Title=Multiple
Number of Profiles=7
Profile Names=10-year,25-year,50-year,1pct_min,100-year,1pct_plu,500-year
River Rch & RM= Stream0755,Reach-1,26099
     676    1085    1452     941    1878    3747    3110
River Rch & RM= Stream0755,Reach-1,23220
     892    1451    1960    1281    2555    5098    4301
River Rch & RM= Stream0755,Reach-1,17374
    1193    1966    2678    1762    3515    7013    6000
River Rch & RM= Stream0755,Reach-1,11479
    1354    2242    3063    2021    4032    8044    6919
River Rch & RM= Stream0755,Reach-1,6018
    1948    3274    4518    3006    5998   11969   10481
Boundary for River Rch & Prof#=Stream0755,Reach-1,1
Up Type=0
Dn Type=3
Dn Slope=0.005
Boundary for River Rch & Prof#=Stream0755,Reach-1,2
Up Type=0
Dn Type=3
Dn Slope=0.005
Boundary for River Rch & Prof#=Stream0755,Reach-1,3
Up Type=0
Dn Type=3
Dn Slope=0.005
Boundary for River Rch & Prof#=Stream0755,Reach-1,4
Up Type=0
Dn Type=3
Dn Slope=0.005
Boundary for River Rch & Prof#=Stream0755,Reach-1,5
Up Type=0
Dn Type=3
Dn Slope=0.005
Boundary for River Rch & Prof#=Stream0755,Reach-1,6
Up Type=0
Dn Type=3
Dn Slope=0.005
Boundary for River Rch & Prof#=Stream0755,Reach-1,7
Up Type=0
Dn Type=3
Dn Slope=0.005

--- Stream0755.g01 (geometry) ---

Geom Title=Existing Conditions
Program Version=4.10

River Reach=Stream0755      ,Reach-1
Reach XY= 30
        2469225.       13661925.      2468490.21     13661825.23
      2468021.31     13662067.35      2467745.18     13661574.56
      2467323.75     13662021.55      2466868.83     13661867.14
      2466028.45     13660723.75      2466119.66     13660022.26
      2465482.47      13659631.7      2465666.23      13659368.2
      2464932.67     13658831.53      2464792.14     13658141.03
      2463976.46     13658121.46      2463164.76     13657764.65
      2462964.72     13657375.98      2462476.43     13657721.99
      2461985.43     13657085.96      2461288.65     13656888.33
      2461282.79     13655021.57      2461673.51      13654730.9
        2460978.      13654423.6      2460871.88     13652825.99
      2460485.47     13652634.82      2460319.55     13651922.54
      2459975.52     13651714.55      2460322.77     13650480.93
      2459767.25     13649368.45      2459444.22     13649395.59
      2459519.55     13649022.53        2458925.       13648475.

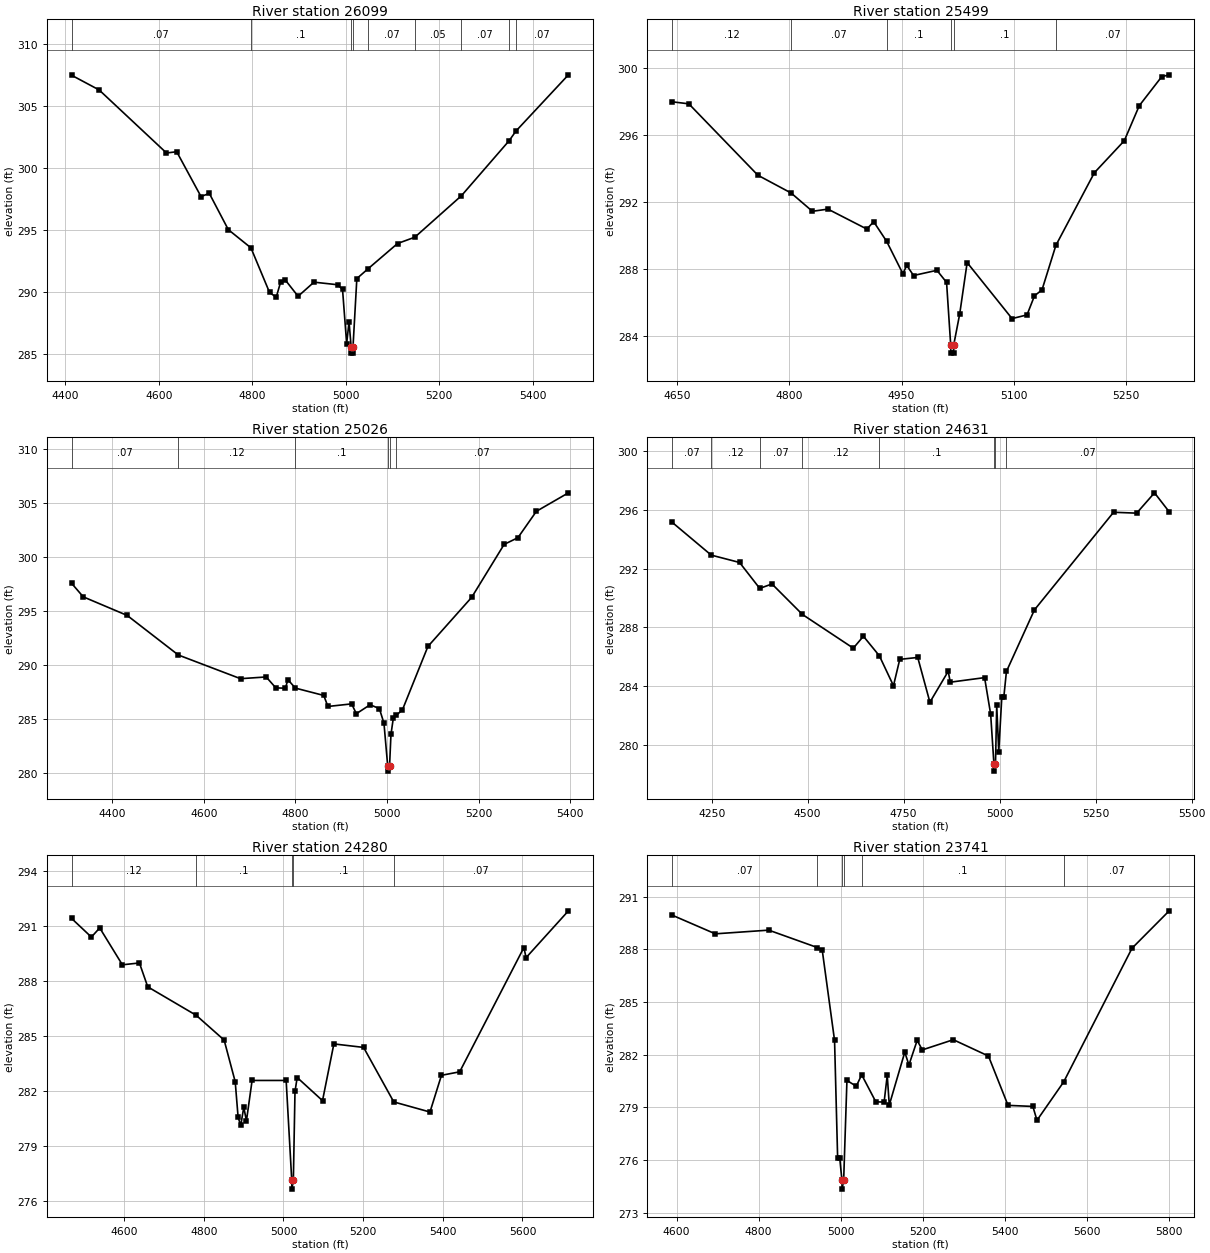
Type RM Length L Ch R = 1 ,26099   ,600,600,600
BEGIN DESCRIPTION:
Stream0755 51.0
END DESCRIPTION:
XS GIS Cut Line= 3
      2469221.85      13661435.5      2469141.54     13661853.11
      2469021.07     13662479.57
#Sta/Elev= 30
  4413.3  307.52  4472.4  306.33  4616.5  301.24  4638.4  301.34  4690.4  297.72
  4708.1  297.98  4748.8  295.05  4797.2  293.58    4837  289.98  4851.3  289.59
  4860.9  290.84    4871  290.97  4898.1  289.67  4932.1  290.81  4983.1   290.6
  4993.2  290.22    5002  285.85  5007.1  287.62  5011.6  285.58  5011.9  285.08
  5015.4  285.08  5015.6  285.58  5023.8   291.1  5048.1   291.9  5110.9  293.93
  5147.9  294.44  5247.6  297.79  5349.4  302.22  5364.5  303.02  5476.5  307.55
#Mann= 9 ,-1 , 0
  4413.3     .07       0  4797.2      .1       0  5011.6     .05       0
  5015.6      .1       0  5048.1     .07       0  5147.9     .05       0
  5247.6     .07       0  5349.4     .05       0  5364.5     .07       0
Bank Sta=5011.6,5015.6
XS Rating Curve= 0 ,0
Exp/Cntr=0.3,0.1

Type RM Length L Ch R = 1 ,25499   ,473,473,473
BEGIN DESCRIPTION:
Stream0755 50.0
END DESCRIPTION:
XS GIS Cut Line= 3
        2468775.     13661574.98        2468675.       13661925.
        2468675.     13662224.98
#Sta/Elev= 30
  4643.7  297.98  4665.8  297.86  4758.1   293.6  4802.5  292.54  4830.9  291.45
  4851.7  291.58  4903.7  290.39  4912.8  290.83  4930.1  289.66  4951.8  287.73
    4957  288.22  4966.1  287.62  4997.3  287.93  5010.2  287.21  5015.7  283.49
    5016  282.99  5019.5  282.99  5019.8  283.49  5027.7  285.31  5037.7  288.39
  5097.7  285.05  5117.7  285.27  5127.7  286.41  5137.7  286.76  5156.3  289.42
  5207.7  293.75  5247.7  295.66  5267.7  297.75  5297.7  299.48  5307.7  299.59
#Mann= 6 ,-1 , 0
  4643.7     .12       0  4802.5     .07       0  4930.1      .1       0
  5015.7     .05       0  5019.8      .1       0  5156.3     .07       0
Bank Sta=5015.7,5019.8
XS Rating Curve= 0 ,0
Exp/Cntr=0.3,0.1

Type RM Length L Ch R = 1 ,25026   ,395,395,395
BEGIN DESCRIPTION:
E21320
END DESCRIPTION:
XS GIS Cut Line= 3
      2468488.54     13661348.82      2468323.38     13661887.37
      2468388.01     13662404.34
#Sta/Elev= 30
  4311.3  297.58  4336.9  296.32  4432.8   294.6  4544.4  290.94  4680.1  288.75
  4736.1  288.91  4757.1   287.9    4778  287.87  4783.5  288.66  4799.7  287.88
  4861.7   287.2  4870.8  286.18  4922.6  286.42  4932.8  285.51  4962.9  286.34
  4983.1  285.98  4993.1  284.63  5001.2   280.7  5001.4   280.2  5005.3   280.7
  5008.4   283.6  5013.5   285.1  5019.8  285.35  5033.5  285.88    5089  291.73
  5184.6  296.28  5255.3  301.17  5285.4  301.79  5325.7  304.23  5395.6  305.94
#Mann= 6 ,-1 , 0
  4311.3     .07       0  4544.4     .12       0  4799.7      .1       0
  5001.2     .05       0  5005.3      .1       0  5019.8     .07       0
Bank Sta=5001.2,5005.3
XS Rating Curve= 0 ,0
Exp/Cntr=0.3,0.1

Type RM Length L Ch R = 1 ,24631   ,351,351,351
BEGIN DESCRIPTION:
Stream0755 49.0
END DESCRIPTION:
XS GIS Cut Line= 3
      2468298.29     13661258.85        2468025.       13662075.
      2468129.65     13662495.58
#Sta/Elev= 30
  4147.4  295.13  4248.8  292.91  4322.6  292.41  4375.1  290.65    4407  290.95
  4486.3  288.88  4618.8  286.59  4645.1   287.4  4686.7  286.07  4723.4  284.04
  4739.8  285.83  4786.6  285.96  4818.3  282.92    4866  285.02  4871.3  284.28
  4960.7  284.59  4976.5  282.11    4985  278.74  4985.2  278.24  4989.1  278.74
  4992.3  282.71  4997.6  279.56  5005.5  283.25  5010.7  283.25  5017.6  285.01
  5090.5  289.19  5296.6  295.82  5356.7  295.76  5403.2  297.14  5441.5  295.85
#Mann= 8 ,-1 , 0
  4147.4     .07       0  4248.8     .12       0  4375.1     .07       0
  4486.3     .12       0  4686.7      .1       0    4985     .05       0
  4989.1      .1       0  5017.6     .07       0
Bank Sta=4985,4989.1
XS Rating Curve= 0 ,0
Exp/Cntr=0.3,0.1

Type RM Length L Ch R = 1 ,24280   ,539,539,539
BEGIN DESCRIPTION:
Stream0755 48.0
END DESCRIPTION:
XS GIS Cut Line= 3
      2468175.02     13661424.97      2467816.44     13661837.05
      2467525.01     13662474.98
#Sta/Elev= 30
  4467.8   291.4  4517.7  290.38  4538.6  290.88  4595.5  288.87  4638.3  288.97
  4659.2  287.67  4780.8  286.12    4851  284.77  4878.8   282.5  4886.1  280.56
  4892.7  280.12  4900.3  281.11    4907  280.37  4921.2  282.57  5006.7  282.57
  5020.7  277.15    5021  276.65  5024.8  277.15  5028.9  281.97  5034.4  282.73
    5098  281.47  5126.5  284.56  5201.1  284.37  5276.9   281.4  5367.8  280.85
  5396.6  282.85  5442.4  283.04  5603.6  289.81  5609.1  289.26  5715.4  291.81
#Mann= 5 ,-1 , 0
  4467.8     .12       0  4780.8      .1       0  5020.7     .05       0
  5024.8      .1       0  5276.9     .07       0
Bank Sta=5020.7,5024.8
XS Rating Curve= 0 ,0
Exp/Cntr=0.3,0.1

Type RM Length L Ch R = 1 ,23741   ,521,521,521
BEGIN DESCRIPTION:
Stream0755 47.0
END DESCRIPTION:
XS GIS Cut Line= 3
      2467607.64     13661170.47        2467575.       13661575.
        2467475.     13662375.03
#Sta/Elev= 30
  4589.6  289.94  4694.5  288.88  4824.9  289.09  4943.3   288.1  4955.3  287.96
  4985.4  282.81  4992.9  276.13    4998  276.13  5003.4  274.84  5003.7  274.34
  5007.6  274.84  5015.6  280.53  5038.3   280.2  5051.6  280.85  5086.1  279.31
  5106.3   279.3  5113.9  280.82  5118.9  279.13  5156.7  282.14  5166.8  281.41
  5186.9  282.81  5199.5  282.27  5275.1  282.85  5360.8  281.92  5408.6  279.11
  5469.1  279.05  5479.2  278.26  5544.4  280.45    5711  288.06  5801.7  290.19
#Mann= 6 ,-1 , 0
  4589.6     .07       0  4943.3     .12       0  5003.4     .05       0
  5007.6     .12       0  5051.6      .1       0  5544.4     .07       0
Bank Sta=5003.4,5007.6
XS Rating Curve= 0 ,0
Exp/Cntr=0.3,0.1

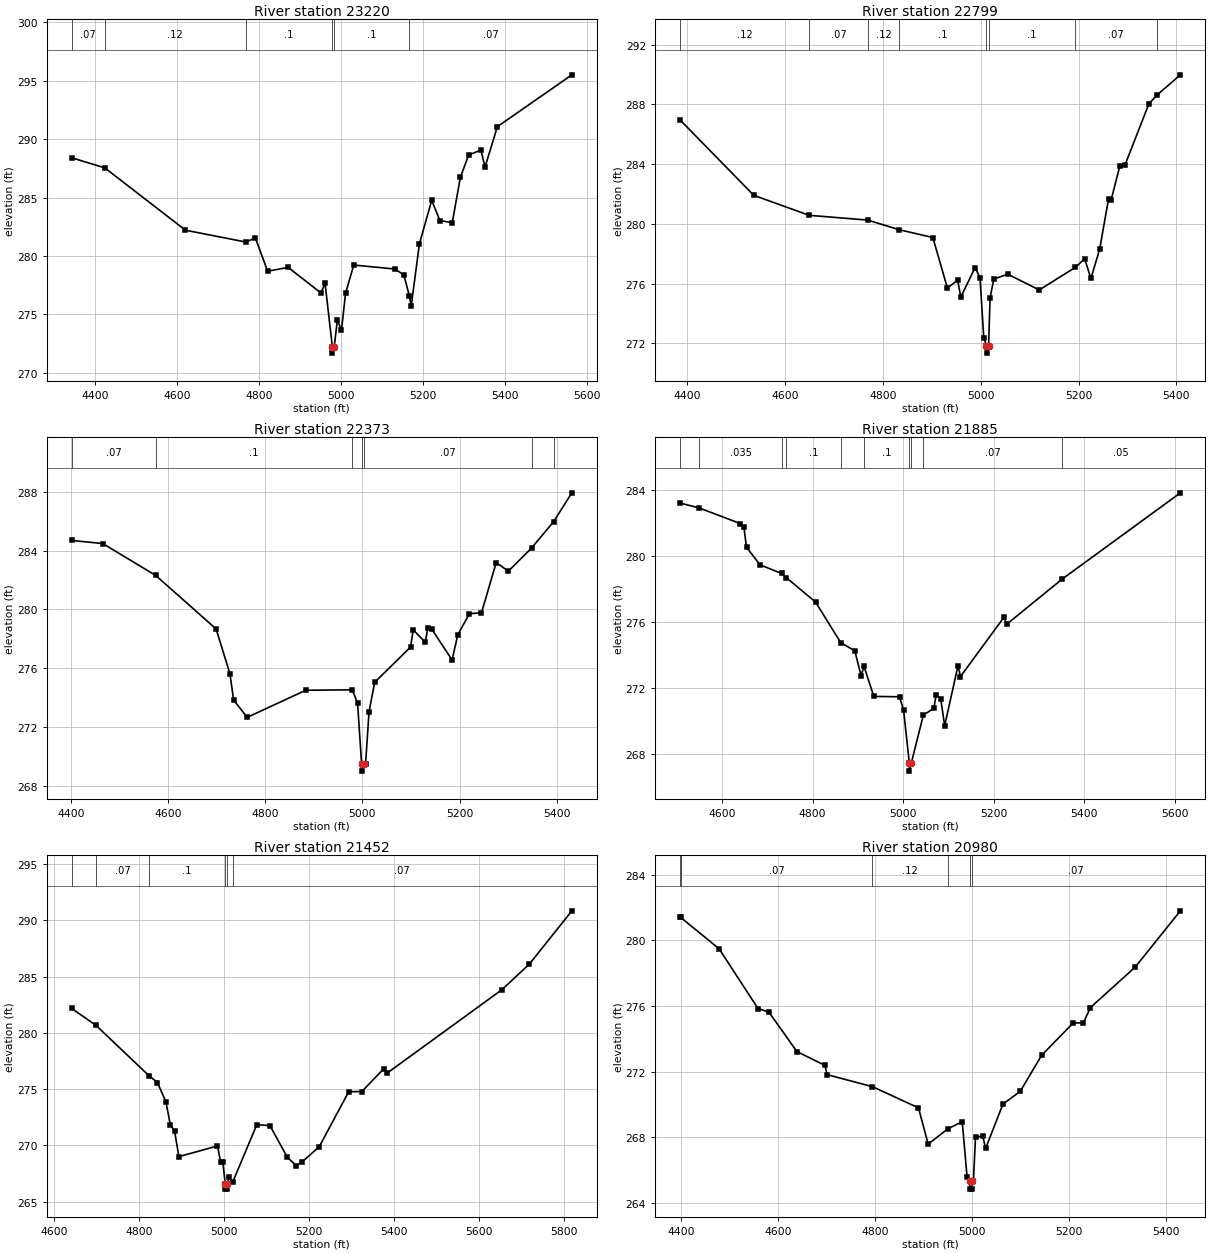
Type RM Length L Ch R = 1 ,23220   ,421,421,421
BEGIN DESCRIPTION:
E21319
END DESCRIPTION:
XS GIS Cut Line= 4
      2467562.21     13661449.39      2467504.79     13661564.24
      2467325.27      13661729.4      2467353.99     13662576.77
#Sta/Elev= 30
  4342.1   288.4  4422.7  287.54  4619.7   282.2  4766.9  281.19  4790.1  281.55
  4820.1  278.69  4870.1  279.02  4950.2  276.83  4960.2  277.66  4978.1  272.18
  4978.3  271.68  4982.4  272.18  4990.2  274.52  5000.2  273.63  5010.2   276.8
  5030.2  279.22  5130.3  278.88  5152.3  278.38  5166.1  276.55  5170.3  275.71
  5190.3  281.03  5220.3  284.75  5240.3  283.03  5270.4  282.84  5290.4  286.75
  5310.4  288.63  5340.4  289.07  5350.4   287.6  5380.4  291.06  5562.3   295.5
#Mann= 6 ,-1 , 0
  4342.1     .07       0  4422.7     .12       0  4766.9      .1       0
  4978.1     .05       0  4982.4      .1       0  5166.1     .07       0
Bank Sta=4978.1,4982.4
XS Rating Curve= 0 ,0
Exp/Cntr=0.3,0.1

Type RM Length L Ch R = 1 ,22799   ,426,426,426
BEGIN DESCRIPTION:
Stream0755 46.0
END DESCRIPTION:
XS GIS Cut Line= 3
      2467474.98     13661525.01        2466975.       13661875.
        2466875.     13662274.98
#Sta/Elev= 30
  4385.7  286.95  4536.1  281.91  4649.4  280.57  4769.2  280.25    4833  279.61
  4902.3  279.08  4931.9   275.7  4952.8  276.22  4959.4   275.1  4988.6  277.07
  4998.6   276.4  5006.3  272.37  5011.8  271.84  5012.1  271.34  5016.2  271.84
  5019.2  275.05  5026.9   276.3  5055.3  276.63  5119.7  275.57  5193.8  277.09
  5212.5  277.66  5225.4  276.34  5243.4  278.32  5261.4  281.67  5266.6  281.59
  5284.6  283.89  5294.9  283.93  5343.9  288.04  5360.3  288.62  5408.3  289.98
#Mann= 8 ,-1 , 0
  4385.7     .12       0  4649.4     .07       0  4769.2     .12       0
    4833      .1       0  5011.8     .05       0  5016.2      .1       0
  5193.8     .07       0  5360.3     .05       0
Bank Sta=5011.8,5016.2
XS Rating Curve= 0 ,0
Exp/Cntr=0.3,0.1

Type RM Length L Ch R = 1 ,22373   ,488,488,488
BEGIN DESCRIPTION:
Stream0755 45.0
END DESCRIPTION:
XS GIS Cut Line= 3
      2467024.97     13661225.03        2466625.       13661675.
      2466475.01     13662074.96
#Sta/Elev= 30
  4401.8  284.69  4465.7  284.48  4574.7  282.31    4699  278.67  4727.5  275.61
    4735  273.83    4763  272.66  4883.4   274.5  4978.8  274.53    4990  273.65
  4998.3   269.5  4998.6     269  5002.7   269.5  5006.5   269.5  5013.6  273.03
  5025.2  275.04  5099.1  277.44  5104.4  278.61  5129.3  277.77  5134.7  278.76
  5142.7  278.66  5184.5  276.56  5196.1  278.26  5220.1  279.71    5245  279.77
  5275.3  283.19  5300.2   282.6  5347.9  284.17  5393.4  285.97    5431  287.93
#Mann= 7 ,-1 , 0
  4401.8     .07       0  4574.7      .1       0  4978.8     .07       0
  4998.3     .05       0  5002.7     .07       0  5347.9     .05       0
  5393.4    .035       0
Bank Sta=4998.3,5002.7
XS Rating Curve= 0 ,0
Exp/Cntr=0.3,0.1

Type RM Length L Ch R = 1 ,21885   ,433,433,433
BEGIN DESCRIPTION:
Stream0755 44.0
END DESCRIPTION:
XS GIS Cut Line= 3
      2466740.32     13660905.44      2466443.16     13661339.13
        2466225.       13661875.
#Sta/Elev= 30
  4507.6  283.18    4550  282.88  4640.4  281.94  4648.1  281.74  4654.1   280.5
    4684  279.44  4731.7  278.92  4741.7  278.67  4806.5  277.19  4862.1  274.73
  4893.1  274.24  4907.1  272.72  4913.3  273.31  4935.1  271.48  4991.9  271.46
  5000.8  270.65  5013.4  267.46  5013.7  266.96  5017.9  267.46  5044.5  270.36
  5067.4  270.75  5072.8  271.58  5082.8  271.32  5091.5  269.71    5121  273.35
  5126.3  272.68  5222.6  276.28    5228  275.84  5350.4  278.57  5611.9   283.8
#Mann= 10 ,-1 , 0
  4507.6     .07       0    4550    .035       0  4731.7     .07       0
  4741.7      .1       0  4862.1    .035       0  4913.3      .1       0
  5013.4     .05       0  5017.9      .1       0  5044.5     .07       0
  5350.4     .05       0
Bank Sta=5013.4,5017.9
XS Rating Curve= 0 ,0
Exp/Cntr=0.3,0.1

Type RM Length L Ch R = 1 ,21452   ,472,472,472
BEGIN DESCRIPTION:
Stream0755 43.0
END DESCRIPTION:
XS GIS Cut Line= 3
      2466674.99       13660925.        2466325.       13660975.
      2465524.96     13661175.01
#Sta/Elev= 30
  4641.2  282.18  4698.6  280.67  4823.5  276.19  4843.2  275.59  4863.4  273.85
  4873.5  271.84  4883.6  271.27  4893.7     269  4984.6  269.95  4992.2  268.49
  4997.3  268.49  5002.8  266.61  5003.1  266.11    5007  266.11  5007.3  266.61
  5012.8  267.15  5020.1   266.7  5077.2  271.84  5108.1  271.76  5149.4  268.93
    5170   268.2  5182.9   268.5  5224.1  269.87  5293.7  274.77  5324.6  274.79
  5376.1  276.81  5383.9  276.42  5654.4  283.84  5718.9  286.11  5819.4  290.86
#Mann= 6 ,-1 , 0
  4641.2    .035       0  4698.6     .07       0  4823.5      .1       0
  5002.8     .05       0  5007.3      .1       0  5020.1     .07       0
Bank Sta=5002.8,5007.3
XS Rating Curve= 0 ,0
Exp/Cntr=0.3,0.1

Type RM Length L Ch R = 1 ,20980   ,261,261,261
BEGIN DESCRIPTION:
Stream0755 42.0
END DESCRIPTION:
XS GIS Cut Line= 3
      2466624.98       13660725.        2466025.       13660675.
      2465674.98     13660925.01
#Sta/Elev= 30
  4397.4  281.39  4398.3  281.39  4477.7  279.48  4557.9  275.84  4580.5  275.62
  4638.2  273.22  4695.9  272.38  4700.9  271.81  4794.2  271.08  4889.1  269.79
  4909.1  267.58  4949.5  268.51  4979.4  268.95  4989.4  265.57  4994.6  265.34
    4995  264.84    4999  264.84  4999.3  265.34  5002.5  265.34  5006.8     268
  5021.6  268.07  5027.7  267.32  5063.4  270.02    5099  270.79  5143.2  272.99
  5208.4  274.96  5229.3  274.97    5244   275.9  5336.2  278.36  5429.6  281.79
#Mann= 6 ,-1 , 0
  4397.4    .035       0  4398.3     .07       0  4794.2     .12       0
  4949.5     .07       0  4994.6     .05       0  4999.3     .07       0
Bank Sta=4994.6,4999.3
XS Rating Curve= 0 ,0
Exp/Cntr=0.3,0.1

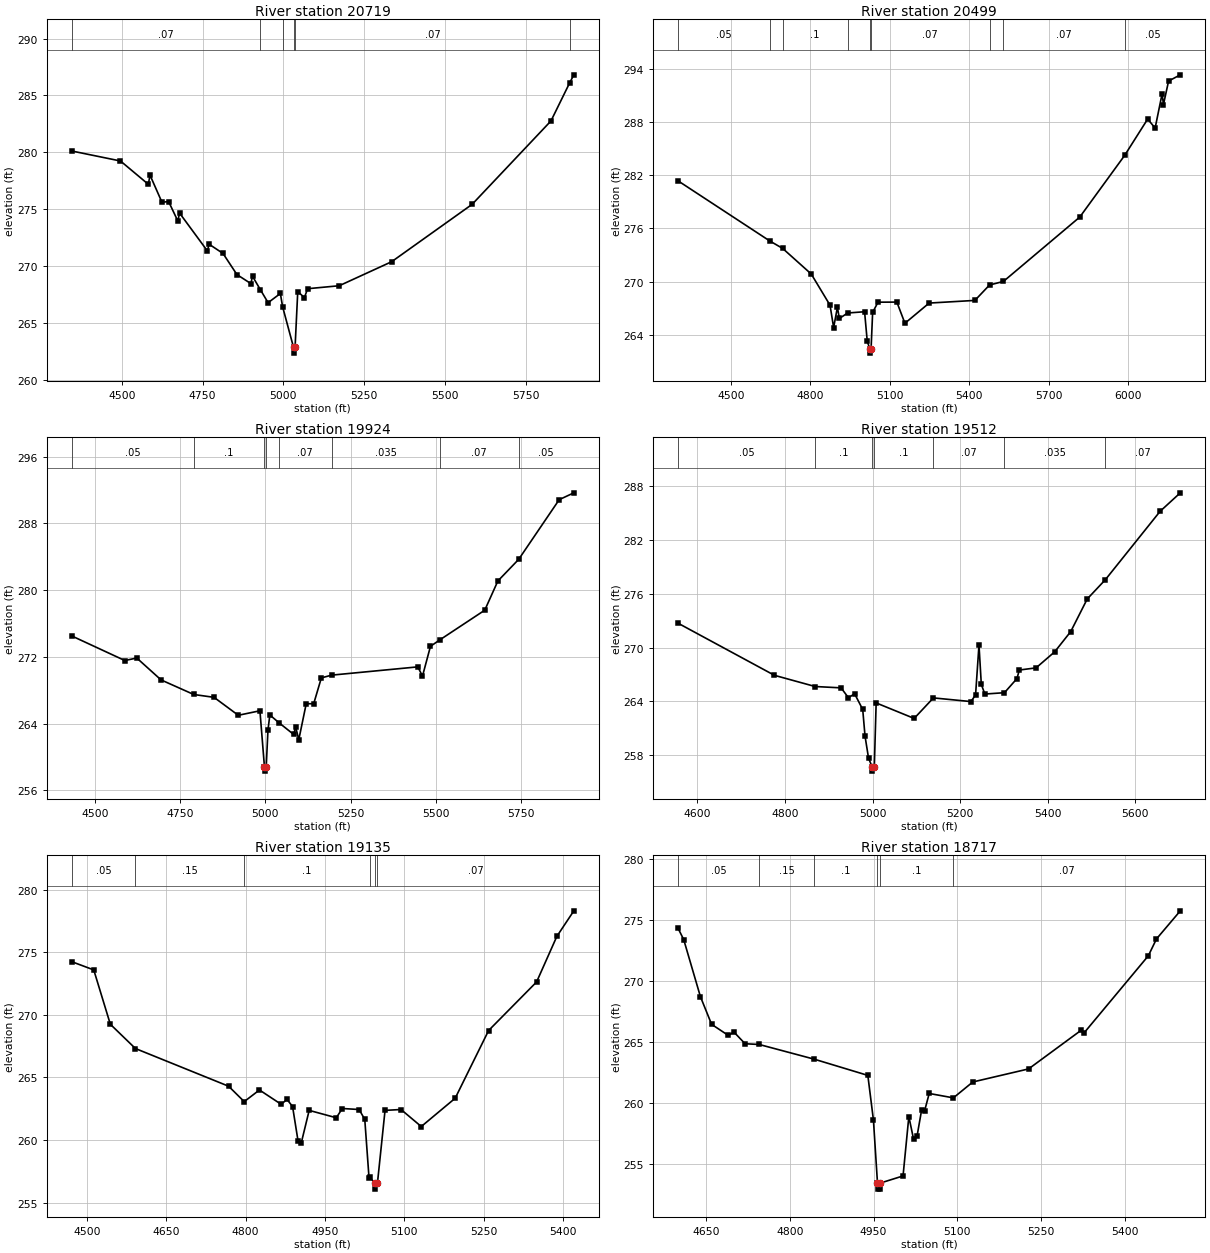
Type RM Length L Ch R = 1 ,20719   ,220,220,220
BEGIN DESCRIPTION:
E21318
END DESCRIPTION:
XS GIS Cut Line= 3
      2466707.77     13660573.32      2465946.58     13660400.97
      2465185.47     13660544.58
#Sta/Elev= 30
  4344.5  280.12  4495.7  279.24    4582  277.19  4587.1     278  4624.2  275.61
  4644.7  275.68  4673.4  273.96  4678.5  274.67  4764.8  271.34    4770  271.93
  4813.1  271.12  4856.3  269.26  4899.4  268.47  4904.5  269.11  4928.7  267.94
  4952.8  266.79  4990.8   267.6  4997.6  266.45  5031.6  262.86    5032  262.36
  5036.3  262.86  5044.6  267.77  5065.1  267.24  5075.3  268.02    5173  268.28
  5335.3  270.39  5584.5  275.43  5828.7  282.76  5886.3  286.09  5899.5  286.81
#Mann= 6 ,-1 , 0
  4344.5     .07       0  4928.7     .12       0  4997.6     .07       0
  5031.6     .05       0  5036.3     .07       0  5886.3     .05       0
Bank Sta=5031.6,5036.3
XS Rating Curve= 0 ,0
Exp/Cntr=0.3,0.1

Type RM Length L Ch R = 1 ,20499   ,575,575,575
BEGIN DESCRIPTION:
Stream0755 41.0
END DESCRIPTION:
XS GIS Cut Line= 3
      2466643.93     13659765.07        2466125.       13660225.
      2464941.42     13660431.63
#Sta/Elev= 30
  4301.5  281.37  4647.8  274.58  4695.9  273.75  4803.8  270.86  4874.7  267.34
  4888.3  264.82  4902.5  267.09    4910  265.84  4941.1  266.46  5005.1   266.6
  5015.2  263.25  5024.9  262.43  5025.2  261.93  5029.6  262.43  5035.5  266.53
  5055.8  267.68  5126.9  267.69  5157.3   265.3  5248.7  267.58  5421.3  267.88
  5476.6  269.62  5528.9  270.02  5817.2  277.29  5986.3  284.24  6073.3  288.35
  6101.4  287.33  6127.8  291.21  6132.8  289.99  6152.2  292.64  6196.4  293.34
#Mann= 9 ,-1 , 0
  4301.5     .05       0  4647.8    .035       0  4695.9      .1       0
  4941.1     .07       0  5024.9     .05       0  5029.6     .07       0
  5476.6    .035       0  5528.9     .07       0  5986.3     .05       0
Bank Sta=5024.9,5029.6
XS Rating Curve= 0 ,0
Exp/Cntr=0.3,0.1

Type RM Length L Ch R = 1 ,19924   ,412,412,412
BEGIN DESCRIPTION:
Stream0755 40.0
END DESCRIPTION:
XS GIS Cut Line= 3
      2466224.98     13659625.02      2465808.72     13659989.94
      2464965.46     13660359.37
#Sta/Elev= 30
  4431.2  274.52  4587.3  271.57  4622.4  271.87  4693.6  269.25  4789.7   267.5
  4849.2  267.16  4920.4  265.01  4983.9  265.55  4997.2  258.82  4997.5  258.32
  5002.3  258.82  5007.5  263.25    5013  265.05  5039.4  264.13  5083.1  262.71
  5088.6  263.63    5098  262.09  5119.8   266.4  5141.7  266.39  5164.2  269.49
  5194.5  269.82  5447.4  270.81  5461.1   269.7  5484.5  273.27  5512.2  274.05
  5643.9   277.6  5682.4   281.1  5743.5  283.69  5862.4  290.84  5905.4  291.66
#Mann= 8 ,-1 , 0
  4431.2     .05       0  4789.7      .1       0  4997.2     .05       0
  5002.3      .1       0  5039.4     .07       0  5194.5    .035       0
  5512.2     .07       0  5743.5     .05       0
Bank Sta=4997.2,5002.3
XS Rating Curve= 0 ,0
Exp/Cntr=0.3,0.1

Type RM Length L Ch R = 1 ,19512   ,377,377,377
BEGIN DESCRIPTION:
Stream0755 39.0
END DESCRIPTION:
XS GIS Cut Line= 3
      2466124.96     13659625.01      2465736.44      13659668.7
      2465024.97     13659925.01
#Sta/Elev= 30
  4555.9  272.72  4775.9  266.91  4868.9  265.66  4928.2  265.51  4945.1   264.4
    4959  264.86  4977.6   263.1  4982.9  260.12  4990.9  257.67  4998.9  256.72
  4999.3  256.22  5004.1  256.72  5008.3  263.83  5095.1   262.1  5139.1  264.39
  5224.8  263.98  5235.4  264.72  5243.2  270.29  5248.5   265.9  5256.6  264.82
  5301.4  264.97    5330  266.55  5335.3   267.5  5373.6  267.74  5416.1  269.53
  5452.8  271.79  5490.5  275.43  5531.9  277.58    5657  285.21  5703.1  287.27
#Mann= 7 ,-1 , 0
  4555.9     .05       0  4868.9      .1       0  4998.9     .05       0
  5004.1      .1       0  5139.1     .07       0  5301.4    .035       0
  5531.9     .07       0
Bank Sta=4998.9,5004.1
XS Rating Curve= 0 ,0
Exp/Cntr=0.3,0.1

Type RM Length L Ch R = 1 ,19135   ,418,418,418
BEGIN DESCRIPTION:
Stream0755 38.0
END DESCRIPTION:
XS GIS Cut Line= 3
      2466025.03     13659374.99        2465525.       13659525.
      2465124.95     13659675.02
#Sta/Elev= 30
  4471.2  274.25    4513  273.59  4544.3  269.25  4591.8  267.31  4767.9   264.3
  4797.4  263.07  4826.2     264  4867.1  262.86  4878.4  263.24  4888.8  262.68
  4899.3  259.89  4905.4   259.8  4920.2  262.37  4971.5  261.78  4982.8  262.52
  5014.6  262.44  5025.3  261.65  5033.3     257  5034.6  257.02  5044.1  256.58
  5044.5  256.08  5049.3  256.58  5063.6  262.37  5093.8  262.44  5132.1  261.08
  5196.2  263.34  5259.4  268.75  5350.1  272.63  5388.4  276.27  5420.5  278.31
#Mann= 6 ,-1 , 0
  4471.2     .05       0  4591.8     .15       0  4797.4      .1       0
  5034.6     .07       0  5044.1     .05       0  5049.3     .07       0
Bank Sta=5044.1,5049.3
XS Rating Curve= 0 ,0
Exp/Cntr=0.3,0.1

Type RM Length L Ch R = 1 ,18717   ,424,424,424
BEGIN DESCRIPTION:
Stream0755 37.0
END DESCRIPTION:
XS GIS Cut Line= 3
      2465924.99       13659275.        2465525.       13659275.
        2465125.       13659575.
#Sta/Elev= 30
  4599.8  274.32  4609.8  273.41  4639.8  268.73  4659.8  266.47  4689.8  265.56
  4699.8  265.84  4719.8  264.88  4745.1  264.82  4843.5  263.62  4939.8  262.29
  4949.8  258.65  4957.1  253.48  4957.5  252.98    4962  252.98  4962.4  253.48
  5002.9  254.06  5013.3  258.92  5021.7  257.08  5027.9  257.29  5036.3  259.49
  5041.5  259.38  5049.8  260.81  5093.1  260.45  5127.9  261.75  5227.9  262.82
  5321.7  265.97  5327.9   265.8  5442.5  272.08  5457.1  273.46  5499.8  275.76
#Mann= 6 ,-1 , 0
  4599.8     .05       0  4745.1     .15       0  4843.5      .1       0
  4957.1     .05       0  4962.4      .1       0  5093.1     .07       0
Bank Sta=4957.1,4962.4
XS Rating Curve= 0 ,0
Exp/Cntr=0.3,0.1

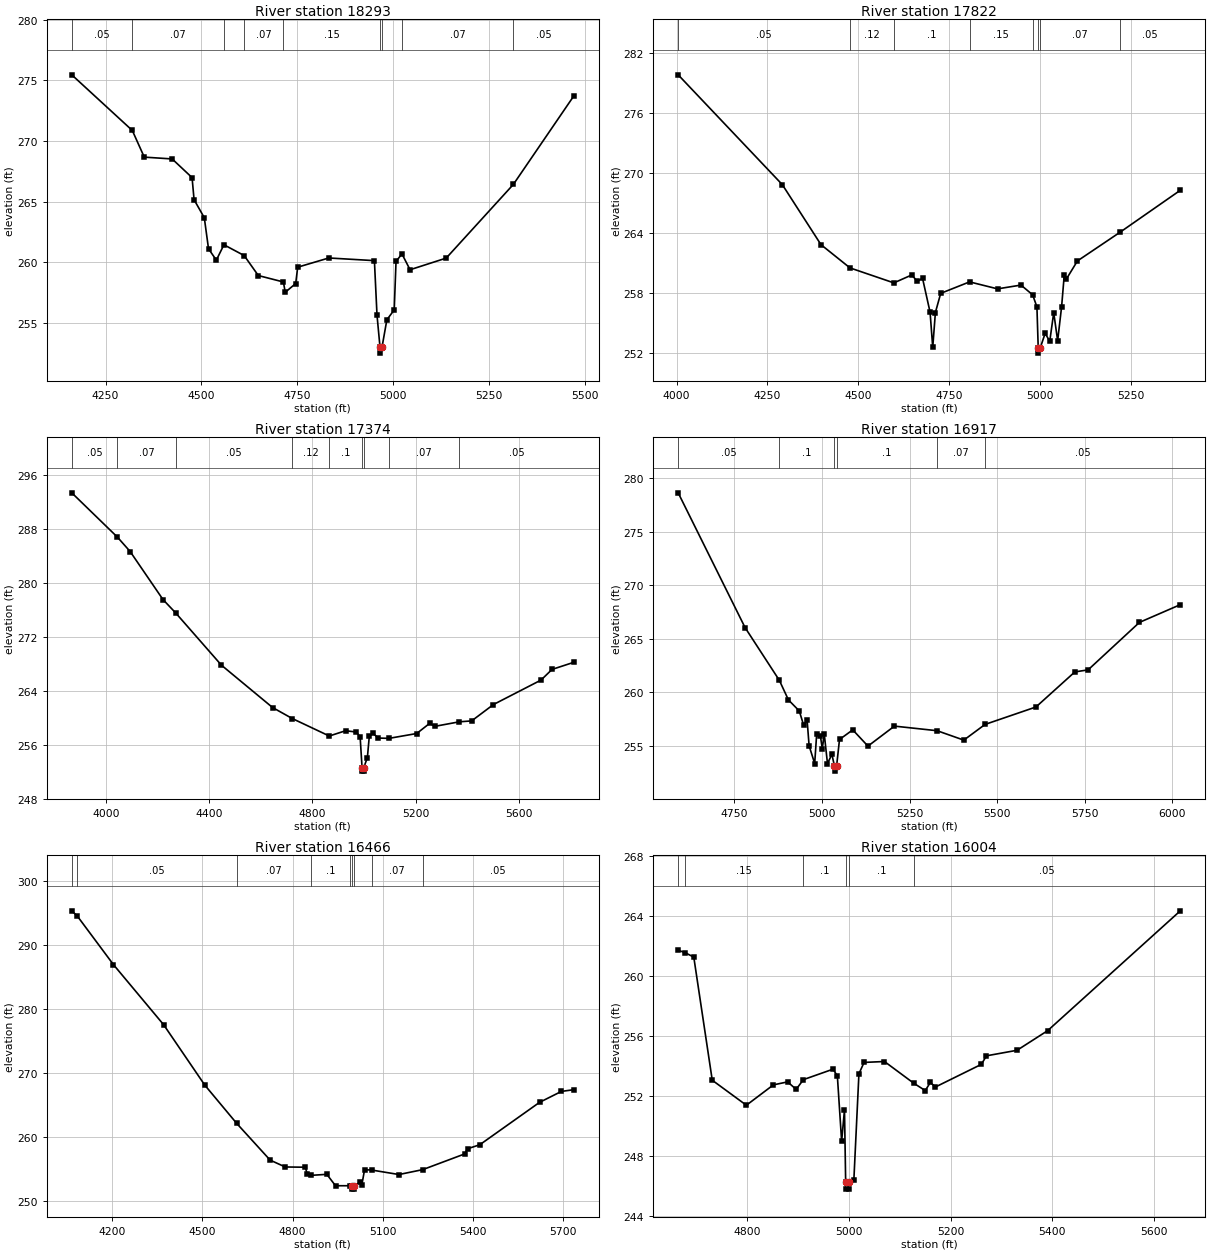
Type RM Length L Ch R = 1 ,18293   ,471,471,471
BEGIN DESCRIPTION:
Stream0755 36.0
END DESCRIPTION:
XS GIS Cut Line= 3
      2465524.99     13658175.02        2465275.       13658975.
      2465025.02     13659374.98
#Sta/Elev= 30
  4161.9  275.46  4319.8  270.87    4351  268.67  4423.8  268.52  4475.7  266.98
  4480.9  265.16  4507.6  263.67  4518.6  261.11    4539  260.17  4558.8  261.44
  4611.6  260.55  4648.5   258.9  4713.9  258.37  4718.7  257.52    4746  258.24
  4751.2  259.59  4832.4  260.35  4951.3  260.13  4958.1  255.63  4965.9     253
  4966.3   252.5  4971.2     253  4983.8  255.25    5003  256.07  5007.7  260.06
  5023.1  260.69  5044.3  259.38  5138.6  260.34  5313.8  266.42  5471.7  273.73
#Mann= 9 ,-1 , 0
  4161.9     .05       0  4319.8     .07       0  4558.8     .12       0
  4611.6     .07       0  4713.9     .15       0  4965.9     .05       0
  4971.2     .15       0  5023.1     .07       0  5313.8     .05       0
Bank Sta=4965.9,4971.2
XS Rating Curve= 0 ,0
Exp/Cntr=0.3,0.1

Type RM Length L Ch R = 1 ,17822   ,448,448,448
BEGIN DESCRIPTION:
Stream0755 35.0
END DESCRIPTION:
XS GIS Cut Line= 3
      2465525.02     13658024.98        2464925.       13658825.
      2464775.01     13659174.98
#Sta/Elev= 30
  4004.4  279.84  4290.9  268.83  4397.1  262.82  4476.9  260.49  4597.5  258.99
  4647.1  259.79  4661.7  259.13  4676.3  259.46  4697.1  256.05  4704.4  252.52
  4711.7  256.02  4726.3  257.94  4805.7  259.09  4882.6  258.39  4947.1  258.77
  4979.2  257.79  4990.9  256.58  4994.5  252.45  4994.9  251.95  4999.8  252.45
  5013.5  253.93  5026.2  253.14  5037.1  256.01  5047.9  253.19  5058.8  256.61
  5066.1  259.79  5071.5  259.35  5102.3  261.19  5219.7  264.07  5385.2  268.27
#Mann= 8 ,-1 , 0
  4004.4     .05       0  4476.9     .12       0  4597.5      .1       0
  4805.7     .15       0  4979.2     .07       0  4994.5     .05       0
  4999.8     .07       0  5219.7     .05       0
Bank Sta=4994.5,4999.8
XS Rating Curve= 0 ,0
Exp/Cntr=0.3,0.1

Type RM Length L Ch R = 1 ,17374   ,457,457,457
BEGIN DESCRIPTION:
Stream0755 34.0
END DESCRIPTION:
XS GIS Cut Line= 3
      2465624.97     13657675.03        2464825.       13658475.
      2464274.97     13659075.03
#Sta/Elev= 30
  3868.2   293.4  4045.2  286.82  4094.4  284.69  4221.7  277.56  4270.3   275.6
    4448  267.83    4646  261.55  4722.6  259.91  4865.8  257.32  4928.8   258.1
  4971.2  257.91  4985.4  257.15  4992.8  252.61  4993.3  252.11  4998.6  252.11
  4999.1  252.61  5013.4  254.11  5020.8  257.27    5035  257.71  5055.9  257.02
  5096.8  256.97  5204.5  257.69  5254.5  259.19  5275.5  258.76  5370.1  259.43
  5417.3  259.56  5501.8  261.99  5686.1  265.62  5728.7   267.2  5813.5  268.26
#Mann= 9 ,-1 , 0
  3868.2     .05       0  4045.2     .07       0  4270.3     .05       0
  4722.6     .12       0  4865.8      .1       0  4992.8     .05       0
  4999.1      .1       0  5096.8     .07       0  5370.1     .05       0
Bank Sta=4992.8,4999.1
XS Rating Curve= 0 ,0
Exp/Cntr=0.3,0.1

Type RM Length L Ch R = 1 ,16917   ,451,451,451
BEGIN DESCRIPTION:
Stream0755 33.0
END DESCRIPTION:
XS GIS Cut Line= 3
      2464925.01     13657774.99        2464725.       13658125.
        2464225.     13659025.01
#Sta/Elev= 30
  4589.8  278.65  4780.6  266.05  4878.5  261.11  4904.4  259.28  4935.3  258.25
  4947.6  256.94  4957.7  257.38  4963.4  254.99  4979.3  253.33    4985  256.11
  4995.8  255.86  5000.9  254.73  5006.7  256.06  5015.8  253.33  5028.4  254.19
  5035.5  253.12    5036  252.62  5041.9  253.12  5050.1  255.58  5087.9  256.48
  5131.3  254.96  5206.8  256.83  5328.6   256.4  5404.8  255.52  5465.5  256.99
  5610.7  258.62  5721.6   261.9  5759.4  262.09  5905.8  266.53  6022.5  268.19
#Mann= 6 ,-1 , 0
  4589.8     .05       0  4878.5      .1       0  5035.5     .05       0
  5041.9      .1       0  5328.6     .07       0  5465.5     .05       0
Bank Sta=5035.5,5041.9
XS Rating Curve= 0 ,0
Exp/Cntr=0.3,0.1

Type RM Length L Ch R = 1 ,16466   ,462,462,462
BEGIN DESCRIPTION:
Stream0755 32.0
END DESCRIPTION:
XS GIS Cut Line= 3
      2464824.98     13657425.03        2464325.       13658225.
      2464124.99     13658925.03
#Sta/Elev= 30
  4064.9  295.39  4083.2  294.58  4203.4     287  4370.9  277.59  4507.7  268.17
  4613.6  262.21  4725.2  256.46  4775.4  255.39  4842.6  255.35  4848.5  254.23
  4861.1  254.08  4913.9  254.24  4942.8  252.46  4991.4  252.46  4997.3  252.43
  4997.8  251.93  5003.3  251.93  5003.8  252.43  5025.2  253.01  5030.4   252.6
  5039.5  254.96  5063.3  254.91  5153.9  254.21  5232.8  254.97  5372.3  257.42
  5382.7  258.24    5423  258.86  5621.9  265.48  5694.7  267.19  5736.3  267.46
#Mann= 9 ,-1 , 0
  4064.9     .07       0  4083.2     .05       0  4613.6     .07       0
  4861.1      .1       0  4991.4     .05       0  4997.3     .05       0
  5003.8     .05       0  5063.3     .07       0  5232.8     .05       0
Bank Sta=4997.3,5003.8
XS Rating Curve= 0 ,0
Exp/Cntr=0.3,0.1

Type RM Length L Ch R = 1 ,16004   ,433,433,433
BEGIN DESCRIPTION:
Stream0755 31.0
END DESCRIPTION:
XS GIS Cut Line= 3
      2464074.98     13657775.04        2463925.       13658075.
        2463975.     13658725.01
#Sta/Elev= 30
  4664.2  261.74  4678.2  261.57  4694.9  261.28  4731.2  253.06  4798.3  251.39
  4851.4  252.75  4879.4  252.95  4896.2  252.45  4910.4   253.1  4968.8   253.8
  4977.2  253.34  4985.6  248.98  4991.2  251.09  4993.5  246.29    4994  245.79
  4999.5  245.79    5000  246.29  5009.6  246.38  5019.6  253.49  5029.7  254.25
  5069.8  254.31  5127.4  252.86    5150  252.37    5160  252.91  5170.1  252.61
  5260.3  254.12  5270.4  254.69  5330.5  255.06  5390.7  256.37  5651.5  264.37
#Mann= 6 ,-1 , 0
  4664.2    .035       0  4678.2     .15       0  4910.4      .1       0
  4993.5     .05       0    5000      .1       0  5127.4     .05       0
Bank Sta=4993.5,5000
XS Rating Curve= 0 ,0
Exp/Cntr=0.3,0.1

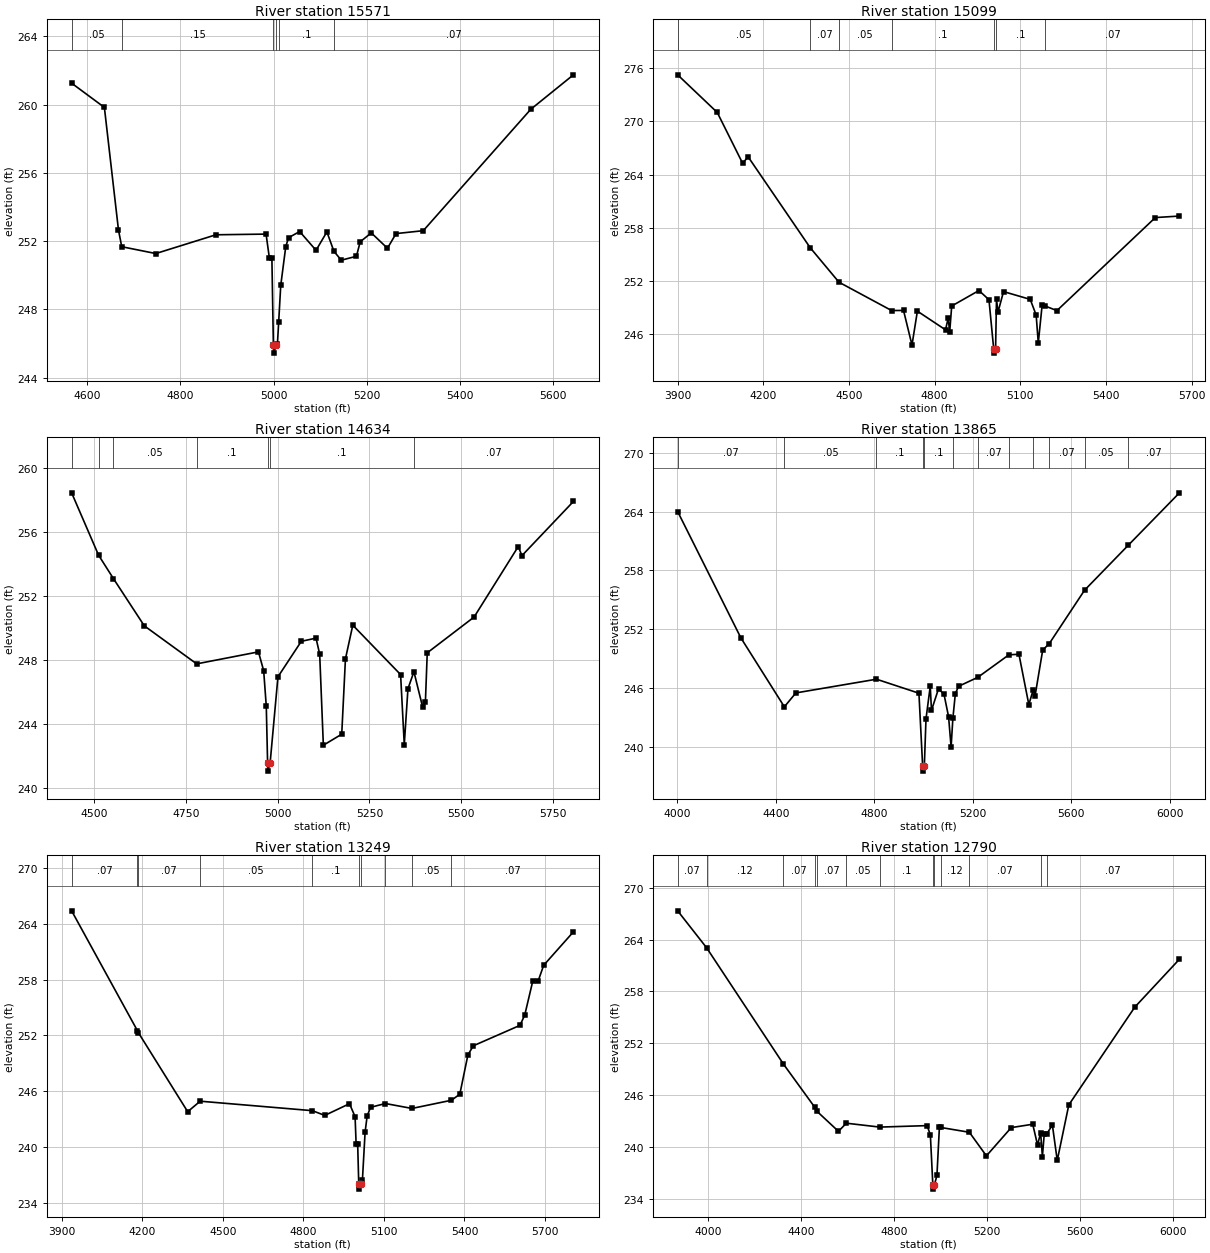
Type RM Length L Ch R = 1 ,15571   ,472,472,472
BEGIN DESCRIPTION:
Stream0755 30.0
END DESCRIPTION:
XS GIS Cut Line= 3
        2464025.       13657725.        2463625.       13657875.
        2463375.       13658475.
#Sta/Elev= 30
  4566.4  261.26  4636.7  259.84    4667  252.64    4674  251.67  4747.1  251.27
  4876.1  252.37  4983.8  252.41  4990.9  251.01  4996.3  251.01  4999.5  245.93
    5000  245.43  5006.1  245.93  5008.2  245.97  5010.9  247.27  5015.3   249.4
  5026.1  251.68  5032.1   252.2  5055.9  252.56  5091.1  251.46  5114.4  252.54
  5129.5   251.4  5145.3  250.88  5177.8  251.11  5185.9  251.96  5209.7  252.48
  5244.4  251.58  5262.8  252.44  5321.3  252.61  5552.1  259.73  5643.6  261.75
#Mann= 6 ,-1 , 0
  4566.4     .05       0    4674     .15       0  4999.5     .05       0
  5006.1     .15       0  5010.9      .1       0  5129.5     .07       0
Bank Sta=4999.5,5006.1
XS Rating Curve= 0 ,0
Exp/Cntr=0.3,0.1

Type RM Length L Ch R = 1 ,15099   ,465,465,465
BEGIN DESCRIPTION:
Stream0755 29.0
END DESCRIPTION:
XS GIS Cut Line= 3
      2463632.33     13656753.51        2463225.       13657775.
      2463046.08     13658407.88
#Sta/Elev= 30
  3899.9  275.26  4038.6  271.01  4127.6  265.26  4146.5  266.01    4364  255.74
  4464.9  251.84  4649.2  248.64    4691  248.65  4720.6  244.74  4739.5  248.57
  4838.1  246.46  4847.3  247.78  4852.7  246.24  4859.7  249.15  4955.1   250.9
  4990.2  249.86  5006.7  244.33  5007.2  243.83  5013.4  244.33  5016.6  249.91
  5021.8  248.46  5041.2  250.78  5134.7   249.9  5155.5  248.13  5162.9  244.98
  5176.3  249.22  5187.9  249.14  5228.2  248.63  5572.9  259.14  5657.3  259.31
#Mann= 7 ,-1 , 0
  3899.9     .05       0    4364     .07       0  4464.9     .05       0
  4649.2      .1       0  5006.7     .05       0  5013.4      .1       0
  5187.9     .07       0
Bank Sta=5006.7,5013.4
XS Rating Curve= 0 ,0
Exp/Cntr=0.3,0.1

Type RM Length L Ch R = 1 ,14634   ,769,769,769
BEGIN DESCRIPTION:
Stream0755 28.0
END DESCRIPTION:
XS GIS Cut Line= 3
      2463475.02     13657124.98        2463075.       13657525.
        2463025.     13658325.03
#Sta/Elev= 30
  4438.5  258.44  4511.9  254.54  4552.5  253.07  4636.5  250.12  4779.2  247.74
  4947.6  248.49  4961.8  247.31  4968.9  245.09  4972.5  241.53    4973  241.03
  4979.3  241.53  5000.7  246.93  5064.3  249.15  5104.4  249.35  5114.4  248.35
  5124.4  242.65  5174.5  243.34  5184.6  248.05  5204.6  250.16  5334.9  247.07
  5344.9  242.69  5354.9  246.18  5371.2  247.25    5395  245.03  5402.5  245.37
  5407.5  248.43  5535.2  250.67  5655.5  255.08  5665.5  254.51  5805.8   257.9
#Mann= 7 ,-1 , 0
  4438.5     .05       0  4511.9     .07       0  4552.5     .05       0
  4779.2      .1       0  4972.5     .05       0  4979.3      .1       0
  5371.2     .07       0
Bank Sta=4972.5,4979.3
XS Rating Curve= 0 ,0
Exp/Cntr=0.3,0.1

Type RM Length L Ch R = 1 ,13865   ,616,616,616
BEGIN DESCRIPTION:
XS7654
END DESCRIPTION:
XS GIS Cut Line= 4
      2463118.36     13656761.53      2462708.79     13657347.77
      2462797.13     13657789.47      2462572.62     13658631.36
#Sta/Elev= 30
  4001.7  264.02  4258.4  251.11  4434.8  244.07  4481.7  245.49  4808.8  246.89
  4981.1  245.46  4996.2     238  4996.7   237.5    5003     238  5009.8  242.84
    5027  246.16  5032.1  243.71  5060.7  245.92  5083.1  245.33  5101.5  243.05
  5111.7  239.96  5118.9  242.89    5129  245.43  5142.3  246.17    5220  247.08
  5346.2  249.38  5387.1  249.44  5427.2   244.3    5445  245.79  5452.4  245.17
  5483.5  249.86  5510.3  250.53  5653.4  255.98  5829.9  260.55  6038.6  265.93
#Mann= 12 ,-1 , 0
  4001.7     .07       0  4434.8     .05       0  4808.8      .1       0
  4996.2     .05       0    5003      .1       0  5118.9     .12       0
    5220     .07       0  5346.2     .12       0    5445     .05       0
  5510.3     .07       0  5653.4     .05       0  5829.9     .07       0
Bank Sta=4996.2,5003
XS Rating Curve= 0 ,0
Exp/Cntr=0.3,0.1

Type RM Length L Ch R = 1 ,13249   ,459,459,459
BEGIN DESCRIPTION:
Stream0755 27.0
END DESCRIPTION:
XS GIS Cut Line= 3
        2463025.       13656725.        2462325.       13657525.
        2462225.     13658324.96
#Sta/Elev= 30
  3936.7  265.39  4181.9  252.49  4185.4  252.28    4369  243.78  4415.6  244.91
  4833.5  243.89  4879.7  243.38  4971.7  244.64  4992.6  243.24  4996.4  240.33
  5002.2  240.33  5006.3  235.95  5006.8  235.45  5013.3  235.95  5019.9  236.42
  5029.9  241.59  5037.5  243.31  5050.1  244.25  5105.5  244.66  5204.4  244.13
  5351.5  245.01  5382.7  245.66  5412.9  249.89  5433.1  250.87  5606.9  253.07
  5624.5  254.17  5654.8  257.87  5674.9  257.87  5695.1  259.53  5805.9  263.13
#Mann= 10 ,-1 , 0
  3936.7     .07       0  4181.9     .12       0  4185.4     .07       0
  4415.6     .05       0  4833.5      .1       0  5006.3     .05       0
  5013.3      .1       0  5105.5      .1       0  5204.4     .05       0
  5351.5     .07       0
Bank Sta=5006.3,5013.3
XS Rating Curve= 0 ,0
Exp/Cntr=0.3,0.1

Type RM Length L Ch R = 1 ,12790   ,449,449,449
BEGIN DESCRIPTION:
Stream0755 26.0
END DESCRIPTION:
XS GIS Cut Line= 3
      2462824.96     13656525.04        2462025.       13657325.
        2461375.       13658125.
#Sta/Elev= 30
  3867.7  267.32  3992.3  263.05  4323.6  249.58  4459.1  244.56  4466.2  244.16
  4560.6   241.8  4594.5  242.74  4738.9  242.29  4942.5  242.46  4956.6  241.39
  4967.2  235.61  4967.7  235.11  4974.2  235.61  4984.9   236.7  4995.5  242.25
  5000.6  242.25  5124.7  241.69    5198  238.96    5305  242.23  5397.7  242.62
  5418.5  240.21  5431.7  241.64  5439.3  238.88  5447.3  241.49  5457.8   241.5
  5482.4  242.52  5503.3  238.43  5553.1  244.86  5837.3  256.17  6029.8  261.72
#Mann= 13 ,-1 , 0
  3867.7     .07       0  3992.3     .12       0  4323.6     .07       0
  4459.1     .12       0  4466.2     .07       0  4594.5     .05       0
  4738.9      .1       0  4967.2     .05       0  4974.2      .1       0
  5000.6     .12       0  5124.7     .07       0  5431.7     .12       0
  5457.8     .07       0
Bank Sta=4967.2,4974.2
XS Rating Curve= 0 ,0
Exp/Cntr=0.3,0.1