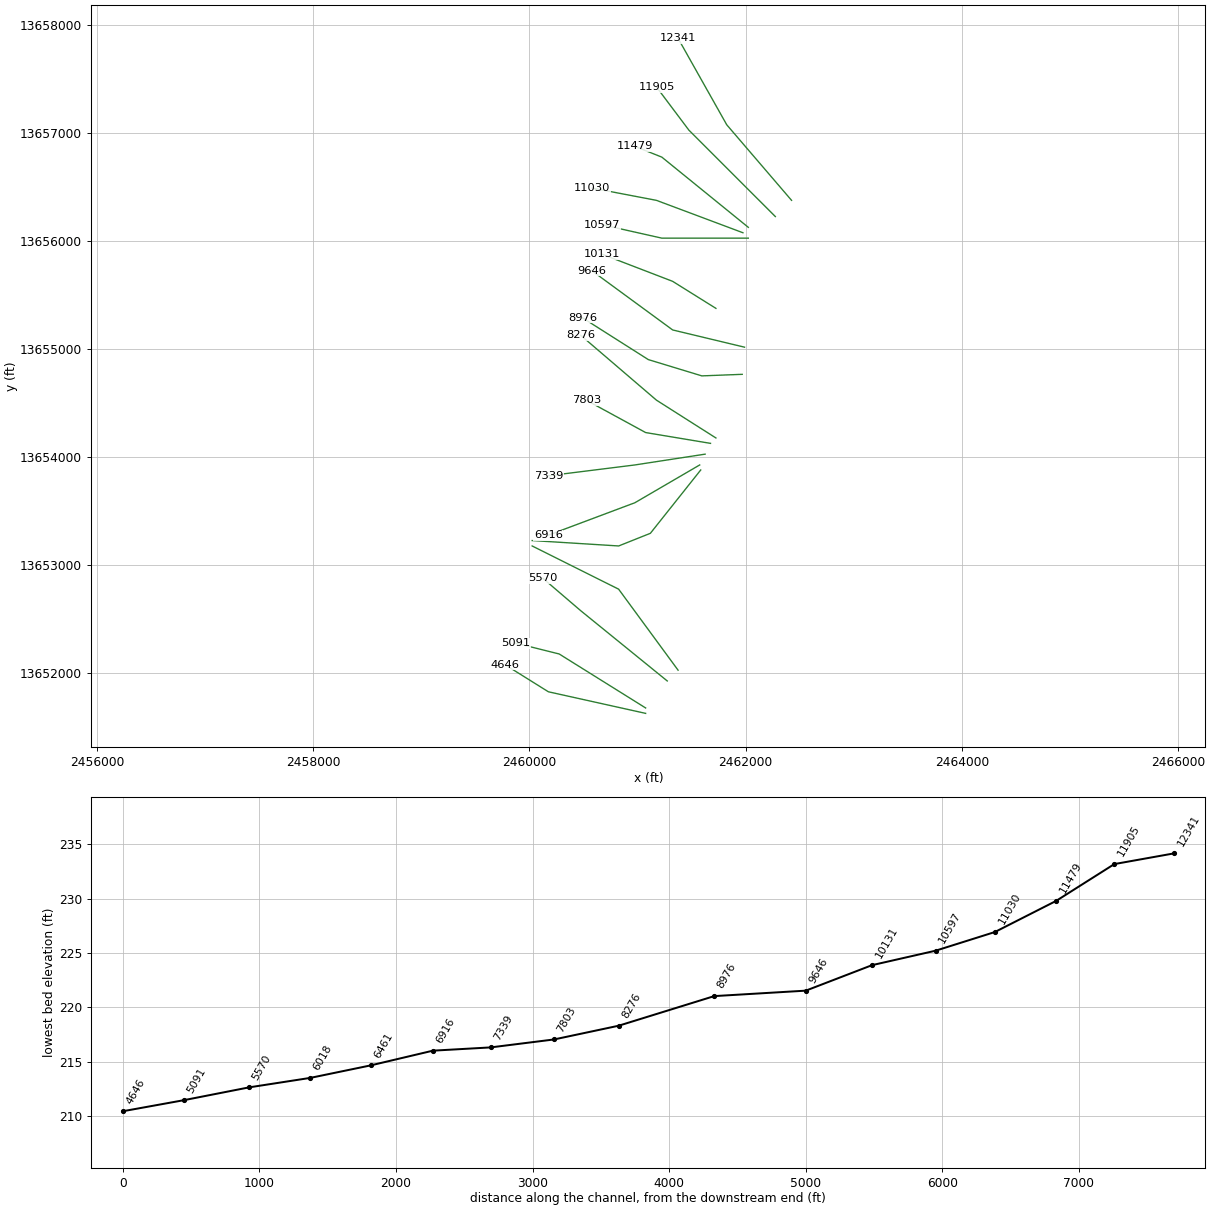
HEC-RAS study Stream0755.prj: Stream0755 Base Level Engineering

--- Stream0755.g01 (geometry) --- (continued)

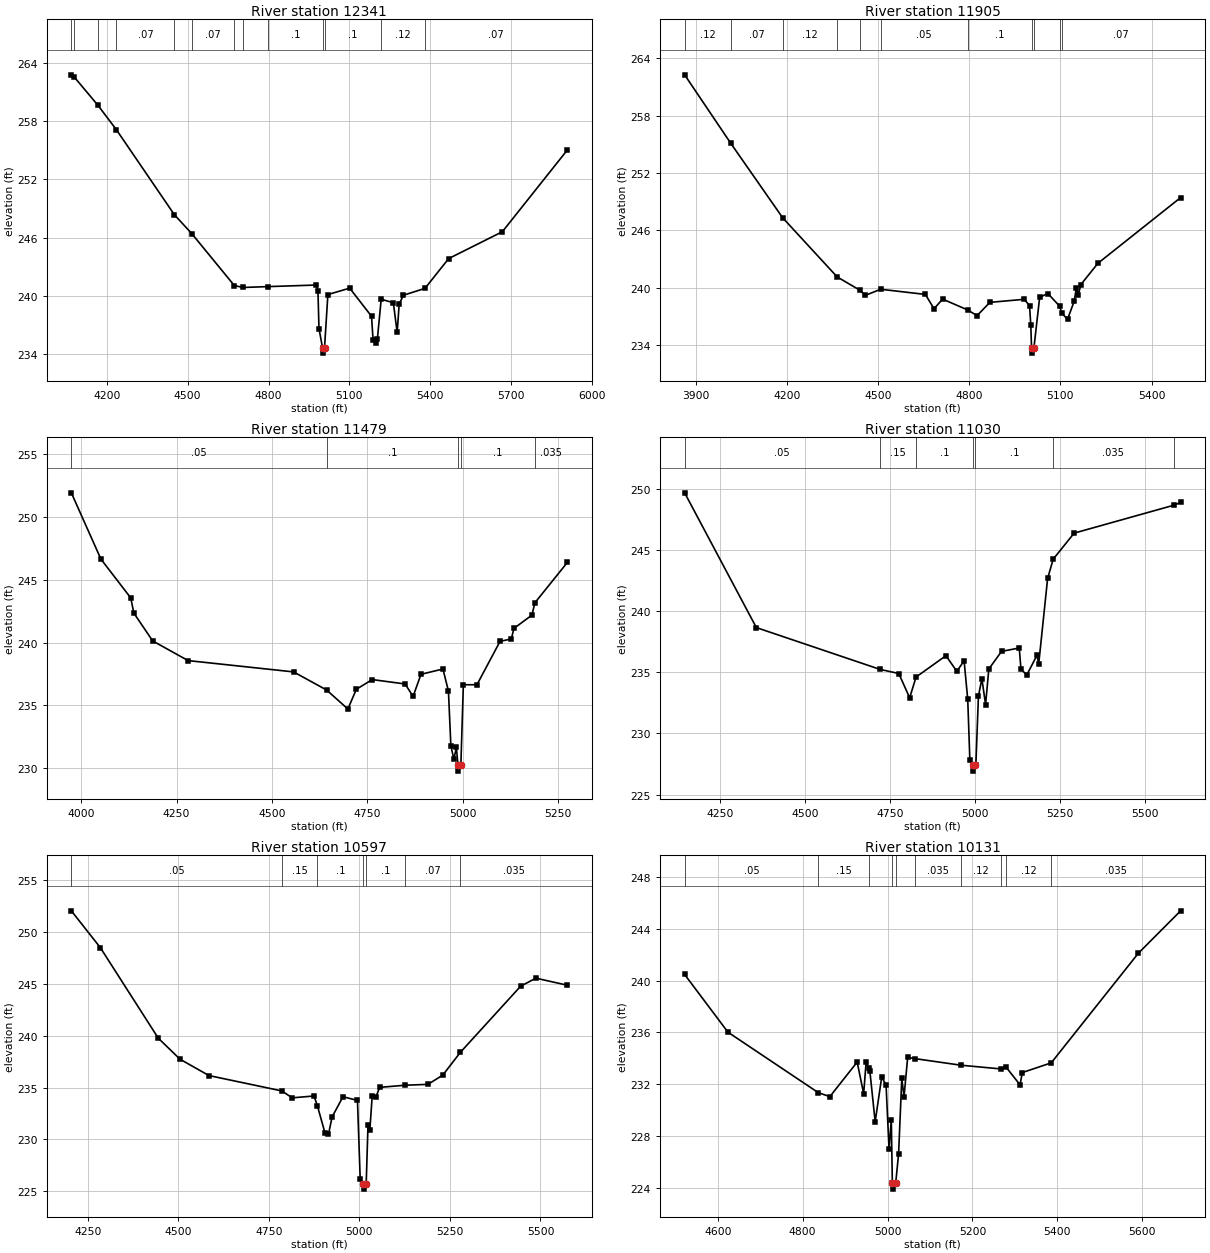
Type RM Length L Ch R = 1 ,12341   ,436,436,436
BEGIN DESCRIPTION:
Stream0755 25.0
END DESCRIPTION:
XS GIS Cut Line= 3
      2462424.97     13656375.03        2461825.       13657075.
        2461375.     13657875.01
#Sta/Elev= 30
  4068.5  262.75  4079.4  262.52  4166.5  259.64  4235.8   257.1  4450.4  248.38
  4515.4  246.42    4673  241.09    4705  240.89  4799.6  240.98  4976.7  241.14
  4983.3  240.54  4987.1  236.67  5000.6  234.64  5001.1  234.14  5007.6  234.64
  5020.1  240.16    5101  240.82    5182  237.93  5187.7  235.53  5196.9  235.21
  5203.6  235.56  5217.9  239.68  5262.9  239.32  5277.2  236.27  5284.6  239.19
  5300.2  240.09  5380.5   240.8  5468.2  243.86  5667.3  246.62  5908.3  255.02
#Mann= 13 ,-1 , 0
  4068.5     .12       0  4079.4     .07       0  4166.5     .12       0
  4235.8     .07       0  4450.4     .12       0  4515.4     .07       0
    4673     .05       0    4705     .07       0  4799.6      .1       0
  5000.6     .05       0  5007.6      .1       0  5217.9     .12       0
  5380.5     .07       0
Bank Sta=5000.6,5007.6
XS Rating Curve= 0 ,0
Exp/Cntr=0.3,0.1

Type RM Length L Ch R = 1 ,11905   ,426,426,426
BEGIN DESCRIPTION:
Stream0755 24.0
END DESCRIPTION:
XS GIS Cut Line= 3
      2462274.99     13656225.01        2461475.       13657025.
      2461174.97     13657425.03
#Sta/Elev= 30
  3864.1  262.27  4016.2  255.09  4186.5  247.32  4365.8  241.13  4440.1  239.75
  4458.1   239.2    4509  239.84    4656   239.3  4684.3   237.8  4712.6  238.81
  4795.5  237.67  4825.8  237.08  4868.2  238.47  4981.3  238.79  4998.6  238.12
  5002.7  236.08  5005.2  233.66  5005.7  233.16  5012.8  233.66  5031.9  239.01
    5059  239.39  5098.5  238.04  5103.9  237.36  5123.6   236.7  5145.5   238.6
  5152.7  239.99    5159  239.27  5167.3  240.33  5223.6  242.56  5495.5  249.43
#Mann= 11 ,-1 , 0
  3864.1     .12       0  4016.2     .07       0  4186.5     .12       0
  4365.8     .05       0  4440.1     .07       0    4509     .05       0
  4795.5      .1       0  5005.2     .05       0  5012.8      .1       0
  5098.5     .12       0  5103.9     .07       0
Bank Sta=5005.2,5012.8
XS Rating Curve= 0 ,0
Exp/Cntr=0.3,0.1

Type RM Length L Ch R = 1 ,11479   ,449,449,449
BEGIN DESCRIPTION:
Stream0755 23.0
END DESCRIPTION:
XS GIS Cut Line= 3
      2462024.99     13656125.01        2461225.       13656775.
      2460975.02     13656874.99
#Sta/Elev= 30
  3974.2  251.91  4051.7  246.64    4130  243.55    4138  242.35  4187.5  240.13
  4280.2  238.57  4556.7  237.67  4643.3  236.23    4699  234.72  4721.3  236.29
  4762.9  237.06  4849.1  236.71  4869.9  235.72  4890.7  237.48  4948.2   237.9
  4962.6  236.15    4969  231.79    4977  230.71  4983.4  231.69  4987.5  230.28
    4988  229.78  4995.2  230.28  5001.7  236.65  5037.3  236.65  5097.9   240.1
  5127.5  240.29  5134.2  241.13  5181.3  242.18  5189.3  243.17  5274.2  246.37
#Mann= 5 ,-1 , 0
  3974.2     .05       0  4643.3      .1       0  4987.5     .05       0
  4995.2      .1       0  5189.3    .035       0
Bank Sta=4987.5,4995.2
XS Rating Curve= 0 ,0
Exp/Cntr=0.3,0.1

Type RM Length L Ch R = 1 ,11030   ,433,433,433
BEGIN DESCRIPTION:
Stream0755 22.0
END DESCRIPTION:
XS GIS Cut Line= 3
      2461975.03     13656074.99        2461175.       13656375.
      2460580.56     13656488.47
#Sta/Elev= 30
  4145.2   249.7  4356.2  238.67    4720  235.25  4775.4  234.91  4807.4  232.92
  4826.2  234.62  4914.2  236.37  4946.2  235.09  4967.6  235.95  4978.3   232.8
  4984.5  227.86  4993.1  227.42  4993.6  226.92  5000.9  227.42  5002.2  227.42
  5009.8  233.07    5020  234.48  5030.8  232.37  5040.4  235.28  5077.8  236.72
  5129.9     237    5135  235.25  5152.3   234.8    5182   236.4  5187.1  235.68
  5213.4  242.69  5229.8  244.27  5291.4   246.4  5584.1  248.68  5604.8  248.91
#Mann= 7 ,-1 , 0
  4145.2     .05       0    4720     .15       0  4826.2      .1       0
  4993.1     .05       0  5000.9      .1       0  5229.8    .035       0
  5584.1     .05       0
Bank Sta=4993.1,5000.9
XS Rating Curve= 0 ,0
Exp/Cntr=0.3,0.1

Type RM Length L Ch R = 1 ,10597   ,466,466,466
BEGIN DESCRIPTION:
Stream0755 21.0
END DESCRIPTION:
XS GIS Cut Line= 3
      2462024.98       13656025.        2461225.       13656025.
      2460669.43     13656149.86
#Sta/Elev= 30
  4204.8  252.07  4284.8  248.52  4444.8  239.78  4504.8  237.75  4584.8  236.17
  4785.7  234.69  4814.8  234.02  4874.8   234.2  4884.1  233.26  4904.8  230.67
  4914.8  230.51  4924.8  232.18  4954.8  234.13  4994.8  233.77  5002.3  226.23
  5011.1  225.71  5011.6  225.21  5018.9  225.71  5023.9   231.4    5029  230.91
  5035.5  234.22  5045.8   234.1    5056  235.03  5126.9  235.24  5189.3  235.32
  5230.3  236.21  5279.1  238.42  5445.5   244.8  5487.6  245.57  5574.2  244.89
#Mann= 7 ,-1 , 0
  4204.8     .05       0  4785.7     .15       0  4884.1      .1       0
  5011.1     .05       0  5018.9      .1       0  5126.9     .07       0
  5279.1    .035       0
Bank Sta=5011.1,5018.9
XS Rating Curve= 0 ,0
Exp/Cntr=0.3,0.1

Type RM Length L Ch R = 1 ,10131   ,485,485,485
BEGIN DESCRIPTION:
Stream0755 20.0
END DESCRIPTION:
XS GIS Cut Line= 3
      2461725.02     13655374.99        2461325.       13655625.
      2460675.04     13655874.99
#Sta/Elev= 30
  4522.1  240.47  4624.1  236.01  4837.2  231.33  4864.1  231.03  4928.4   233.7
  4943.7  231.26  4949.6  233.73  4955.4  233.24  4958.4  232.99  4970.8  229.08
  4986.2  232.54  4996.5  231.93  5003.5  226.95  5008.8  229.26  5011.3  224.38
  5011.8  223.88  5019.3  224.38    5026  226.61  5033.5  232.44  5038.8  231.02
  5047.4  234.07  5063.7  233.97  5172.3  233.46    5267  233.17  5278.9  233.32
    5312  231.94  5317.4  232.89  5385.5  233.64  5590.6  242.11  5690.2  245.39
#Mann= 10 ,-1 , 0
  4522.1     .05       0  4837.2     .15       0  4955.4      .1       0
  5011.3     .05       0  5019.3      .1       0  5063.7    .035       0
  5172.3     .12       0    5267      .1       0  5278.9     .12       0
  5385.5    .035       0
Bank Sta=5011.3,5019.3
XS Rating Curve= 0 ,0
Exp/Cntr=0.3,0.1

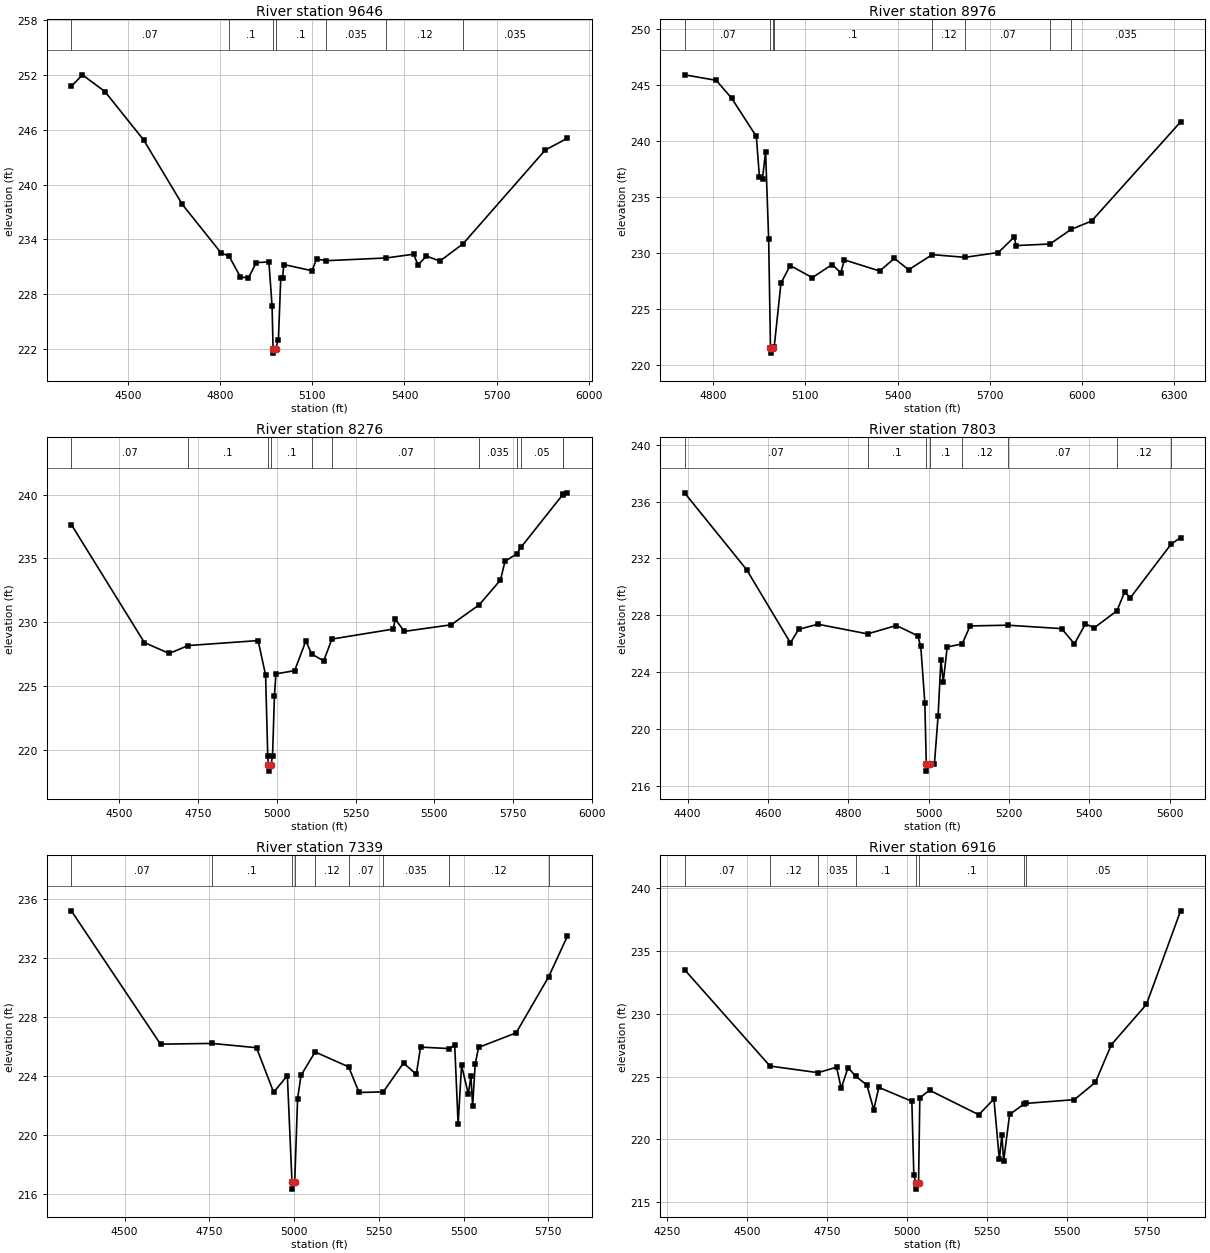
Type RM Length L Ch R = 1 ,9646    ,670,670,670
BEGIN DESCRIPTION:
Stream0755 19.0
END DESCRIPTION:
XS GIS Cut Line= 3
      2461990.01     13655015.46        2461325.       13655175.
      2460575.02     13655724.98
#Sta/Elev= 30
  4316.2  250.77  4352.2  252.04  4425.4  250.21  4551.4   244.9  4677.4  237.83
  4803.4  232.52  4829.3  232.17  4866.4  229.88  4892.5  229.79  4917.8  231.46
  4958.9  231.53  4969.2  226.73  4972.5  222.04    4973  221.54  4980.5  222.04
  4989.8  222.96  4997.5  229.76  5003.2  229.76  5007.4  231.25  5099.3  230.57
  5113.9  231.85    5146  231.67  5340.9  231.97  5429.6  232.38  5444.2   231.2
  5471.3  232.18  5515.3  231.63  5590.5  233.52    5858   243.8  5930.1  245.09
#Mann= 7 ,-1 , 0
  4316.2     .07       0  4829.3      .1       0  4972.5     .05       0
  4980.5      .1       0    5146    .035       0  5340.9     .12       0
  5590.5    .035       0
Bank Sta=4972.5,4980.5
XS Rating Curve= 0 ,0
Exp/Cntr=0.3,0.1

Type RM Length L Ch R = 1 ,8976    ,700,700,700
BEGIN DESCRIPTION:
E21317
END DESCRIPTION:
XS GIS Cut Line= 4
      2461968.48     13654764.13      2461595.08     13654749.77
      2461099.62     13654900.57      2460489.67     13655288.06
#Sta/Elev= 30
  4706.9  245.88    4810  245.39  4860.5  243.78  4940.5  240.38  4950.6  236.76
  4960.6  236.62  4970.6  239.02  4980.6   231.2  4986.5  221.54    4987  221.04
  4994.6  221.54  4998.6  221.59  5020.6  227.28  5050.6  228.86  5122.5  227.78
  5187.4  228.95    5215  228.21    5227  229.36    5342  228.37  5389.7   229.5
  5436.1  228.48  5512.8  229.83  5619.2  229.59  5728.1  230.02  5779.8  231.41
  5785.7  230.64  5896.1  230.78  5964.6  232.08  6031.4  232.83  6321.1  241.68
#Mann= 8 ,-1 , 0
  4706.9     .07       0  4986.5     .05       0  4994.6     .07       0
  4998.6      .1       0  5512.8     .12       0  5619.2     .07       0
  5896.1     .12       0  5964.6    .035       0
Bank Sta=4986.5,4994.6
XS Rating Curve= 0 ,0
Exp/Cntr=0.3,0.1

Type RM Length L Ch R = 1 ,8276    ,473,473,473
BEGIN DESCRIPTION:
Stream0755 18.0
END DESCRIPTION:
XS GIS Cut Line= 3
      2461724.97     13654175.02        2461175.       13654525.
      2460475.03     13655124.98
#Sta/Elev= 30
  4348.4  237.66  4580.3   228.4  4659.1  227.55  4718.7  228.17    4941  228.56
  4964.7  225.85  4971.5   219.5  4973.4  218.82  4973.9  218.32  4981.5  218.82
  4986.7  219.49  4992.7   224.2  4997.3  225.95  5056.8   226.2  5092.5  228.54
  5110.7   227.5    5149  226.97  5175.1  228.68  5369.1  229.46  5376.2  230.23
  5404.7  229.28  5553.5   229.8  5642.1  231.36  5709.9  233.31  5724.1  234.77
    5761  235.36    5775  235.88  5907.5  240.01  5907.9  240.02  5922.2  240.15
#Mann= 11 ,-1 , 0
  4348.4     .07       0  4718.7      .1       0  4973.4     .05       0
  4981.5      .1       0  5110.7     .12       0  5175.1     .07       0
  5642.1    .035       0    5761     .07       0    5775     .05       0
  5907.5    .035       0  5907.9     .05       0
Bank Sta=4973.4,4981.5
XS Rating Curve= 0 ,0
Exp/Cntr=0.3,0.1

Type RM Length L Ch R = 1 ,7803    ,464,464,464
BEGIN DESCRIPTION:
Stream0755 17.0
END DESCRIPTION:
XS GIS Cut Line= 3
        2461675.       13654125.        2461075.       13654225.
      2460524.98     13654525.01
#Sta/Elev= 30
  4392.6  236.61  4547.2  231.21  4656.2  226.07  4676.5  227.02  4724.6  227.38
  4848.2   226.7  4919.8  227.29    4973  226.57  4980.6  225.82  4990.7  221.88
  4994.3  217.56  4994.8  217.06  5002.4  217.56  5014.6  217.57  5023.7  220.93
  5030.8   224.9  5036.5   223.3  5046.4  225.78  5083.8     226  5103.4  227.26
  5197.7  227.31  5331.2  227.07    5363     226  5390.5   227.4  5412.4  227.13
  5468.9  228.32  5488.3  229.66  5502.1  229.23  5603.3  232.99  5627.4  233.47
#Mann= 8 ,-1 , 0
  4392.6     .07       0  4848.2      .1       0  4994.3     .05       0
  5002.4      .1       0  5083.8     .12       0  5197.7     .07       0
  5468.9     .12       0  5603.3     .07       0
Bank Sta=4994.3,5002.4
XS Rating Curve= 0 ,0
Exp/Cntr=0.3,0.1

Type RM Length L Ch R = 1 ,7339    ,423,423,423
BEGIN DESCRIPTION:
Stream0755 16.0
END DESCRIPTION:
XS GIS Cut Line= 3
      2461625.02       13654025.        2460975.       13653925.
        2460175.       13653825.
#Sta/Elev= 30
  4342.6  235.22  4605.7  226.17  4757.2  226.22    4889  225.93  4939.6   222.9
    4980  224.04  4993.7  216.83  4994.2  216.33  5001.8  216.83  5010.3  222.48
  5020.4  224.05    5062  225.64  5160.9  224.63  5191.7  222.89  5263.1  222.93
  5322.8  224.89  5360.6  224.12  5373.1  225.97  5457.3  225.87  5473.9   226.1
    5484  220.74  5494.1  224.73  5514.2  222.77  5521.8  224.03  5526.8  221.95
  5534.4  224.83  5544.5  225.95  5655.3  226.94  5751.1  230.74  5806.5   233.5
#Mann= 9 ,-1 , 0
  4342.6     .07       0  4757.2      .1       0  4993.7     .05       0
  5001.8      .1       0    5062     .12       0  5160.9     .07       0
  5263.1    .035       0  5457.3     .12       0  5751.1     .05       0
Bank Sta=4993.7,5001.8
XS Rating Curve= 0 ,0
Exp/Cntr=0.3,0.1

Type RM Length L Ch R = 1 ,6916    ,455,455,455
BEGIN DESCRIPTION:
Stream0755 15.0
END DESCRIPTION:
XS GIS Cut Line= 3
      2461575.03     13653925.02        2460975.       13653575.
      2460174.96     13653274.99
#Sta/Elev= 30
  4305.3  233.52  4572.1  225.84  4722.5  225.31    4780  225.75  4794.5  224.07
    4816  225.72  4839.5  225.03  4874.7  224.33  4896.2  222.36  4911.9  224.14
  5015.1  223.03  5021.3  217.15  5027.9  216.53  5028.4  216.03  5036.1  216.53
    5040  223.31  5070.3  223.91  5224.2  221.96  5271.4  223.22  5288.3   218.4
  5296.3  220.35  5301.7  218.26  5320.4  221.98  5366.4  222.83  5370.2  222.86
  5522.4  223.16  5588.3  224.54  5638.1  227.54  5747.6  230.75  5854.4  238.21
#Mann= 8 ,-1 , 0
  4305.3     .07       0  4572.1     .12       0  4722.5    .035       0
  4839.5      .1       0  5027.9     .05       0  5036.1      .1       0
  5366.4     .07       0  5370.2     .05       0
Bank Sta=5027.9,5036.1
XS Rating Curve= 0 ,0
Exp/Cntr=0.3,0.1

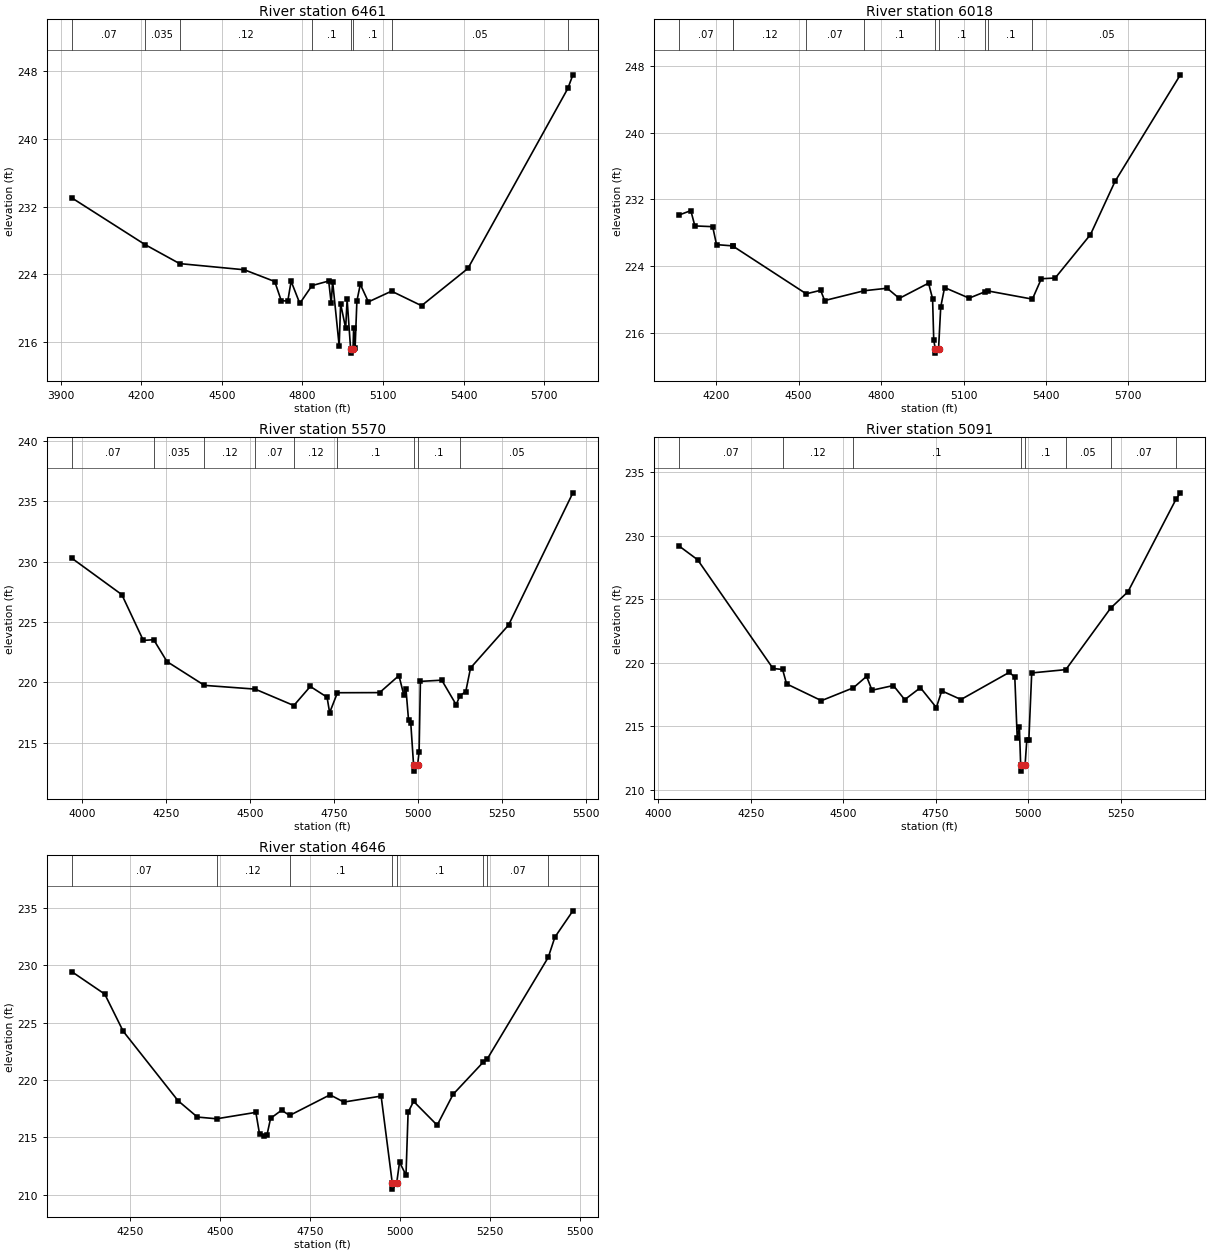
Type RM Length L Ch R = 1 ,6461    ,443,443,443
BEGIN DESCRIPTION:
Stream0755 14.0
END DESCRIPTION:
XS GIS Cut Line= 4
      2461584.49     13653878.46      2461118.67     13653292.16
        2460825.       13653175.      2460024.96       13653225.
#Sta/Elev= 30
  3940.7  233.06  4214.1  227.52  4342.8  225.27  4583.7  224.54  4697.1  223.15
  4721.4  220.88  4745.6  220.84  4758.1  223.18  4790.4  220.56  4835.8  222.67
    4898  223.21  4907.3  220.57  4912.7  223.15    4937  215.54  4942.4  220.51
  4961.2  217.62  4966.6  221.03  4979.6  215.18  4980.1  214.68  4988.7  215.18
  4990.9  217.67  4996.3  215.28    5003  220.85  5015.7  222.82  5045.8  220.74
  5132.1  222.01  5243.7  220.29  5416.5   224.7  5788.5  245.99  5807.3   247.6
#Mann= 8 ,-1 , 0
  3940.7     .07       0  4214.1    .035       0  4342.8     .12       0
  4835.8      .1       0  4979.6     .05       0  4988.7      .1       0
  5132.1     .05       0  5788.5     .07       0
Bank Sta=4979.6,4988.7
XS Rating Curve= 0 ,0
Exp/Cntr=0.3,0.1

Type RM Length L Ch R = 1 ,6018    ,448,448,448
BEGIN DESCRIPTION:
Stream0755 13.0
END DESCRIPTION:
XS GIS Cut Line= 3
      2461374.99     13652025.02        2460825.       13652775.
      2460024.96     13653175.02
#Sta/Elev= 30
  4064.7  230.13  4107.5  230.66  4122.2  228.82    4187  228.73  4201.1  226.57
    4260  226.42  4260.9  226.39  4527.5  220.66  4579.9  221.08  4594.5  219.85
  4738.6  221.03  4822.2  221.33  4866.2  220.11  4972.7  221.94  4987.4  220.08
  4991.6  215.12  4997.2  214.03  4997.7  213.53  5009.1  214.03  5017.1  219.09
  5031.1  221.41  5120.5  220.14    5180  220.93  5189.6     221  5350.7  220.02
  5383.2  222.47  5433.6  222.56  5562.1  227.78  5651.6  234.18  5889.2  246.98
#Mann= 10 ,-1 , 0
  4064.7     .07       0    4260    .035       0  4260.9     .12       0
  4527.5     .07       0  4738.6      .1       0  4997.2     .05       0
  5009.1      .1       0    5180     .05       0  5189.6      .1       0
  5350.7     .05       0
Bank Sta=4997.2,5009.1
XS Rating Curve= 0 ,0
Exp/Cntr=0.3,0.1

Type RM Length L Ch R = 1 ,5570    ,479,479,479
BEGIN DESCRIPTION:
Stream0755 12.0
END DESCRIPTION:
XS GIS Cut Line= 3
      2461275.04     13651924.97        2460475.       13652575.
        2460125.       13652875.
#Sta/Elev= 30
  3968.7   230.3  4118.2  227.27  4182.1  223.48    4213  223.54  4252.5  221.73
  4363.9  219.76  4514.8  219.45    4630  218.09  4679.1  219.67  4728.9  218.78
  4736.6   217.5  4759.8  219.15  4885.3  219.16  4942.8  220.57  4957.2  218.98
  4963.6   219.5  4971.5  216.86    4978  216.66  4986.4  213.16  4986.9  212.66
  4998.3  213.16  5002.8  214.24  5006.7  220.09  5070.3  220.19  5113.1  218.16
  5124.2  218.89  5141.7  219.25  5155.9   221.2    5269  224.75  5460.5   235.7
#Mann= 9 ,-1 , 0
  3968.7     .07       0    4213    .035       0  4363.9     .12       0
  4514.8     .07       0    4630     .12       0  4759.8      .1       0
  4986.4     .05       0  4998.3      .1       0  5124.2     .05       0
Bank Sta=4986.4,4998.3
XS Rating Curve= 0 ,0
Exp/Cntr=0.3,0.1

Type RM Length L Ch R = 1 ,5091    ,445,445,445
BEGIN DESCRIPTION:
Stream0755 11.0
END DESCRIPTION:
XS GIS Cut Line= 3
      2461075.01     13651674.99        2460275.       13652175.
      2459875.02       13652275.
#Sta/Elev= 30
  4056.1  229.18  4106.2   228.1  4310.2  219.55  4336.1  219.47  4346.8  218.34
  4441.1  217.02  4527.4  218.03  4563.2  218.93  4577.9  217.84  4635.7  218.21
  4666.4   217.1  4708.8  218.04  4751.9  216.48  4766.6  217.79  4818.5  217.11
  4949.4  219.25  4964.1  218.86  4970.6   214.1  4976.5  214.92  4979.9  211.98
  4980.4  211.48  4991.9  211.98  4996.6  213.94  5002.1  213.94  5009.8   219.2
  5102.1  219.46  5223.4   224.3  5270.1  225.58  5400.5  232.88  5411.8  233.36
#Mann= 8 ,-1 , 0
  4056.1     .07       0  4336.1     .12       0  4527.4      .1       0
  4979.9     .05       0  4991.9      .1       0  5102.1     .05       0
  5223.4     .07       0  5400.5     .05       0
Bank Sta=4979.9,4991.9
XS Rating Curve= 0 ,0
Exp/Cntr=0.3,0.1

Type RM Length L Ch R = 1 ,4646    ,475,475,475
BEGIN DESCRIPTION:
Stream0755 10.0
END DESCRIPTION:
XS GIS Cut Line= 3
        2461075.       13651625.        2460175.       13651825.
      2459775.04     13652074.97
#Sta/Elev= 30
  4087.5  229.46  4179.7  227.49  4230.9  224.25  4383.3  218.19  4437.1  216.76
  4490.7  216.61  4599.7  217.17  4609.9  215.29  4621.5  215.08  4630.4  215.16
  4640.7  216.65  4671.4  217.36  4693.6   216.9  4805.9   218.7  4844.3  218.07
    4948  218.59  4979.1  210.97  4979.6  210.47  4991.1  210.97  4999.2  212.83
  5017.1  211.69    5023  217.18  5038.3  218.13  5103.8  216.05    5148  218.74
  5232.4  221.57  5243.2  221.84  5412.6   230.7    5431  232.46  5481.1  234.76
#Mann= 8 ,-1 , 0
  4087.5     .07       0  4490.7     .12       0  4693.6      .1       0
  4979.1     .05       0  4991.1      .1       0  5232.4     .05       0
  5243.2     .07       0  5412.6     .05       0
Bank Sta=4979.1,4991.1
XS Rating Curve= 0 ,0
Exp/Cntr=0.3,0.1