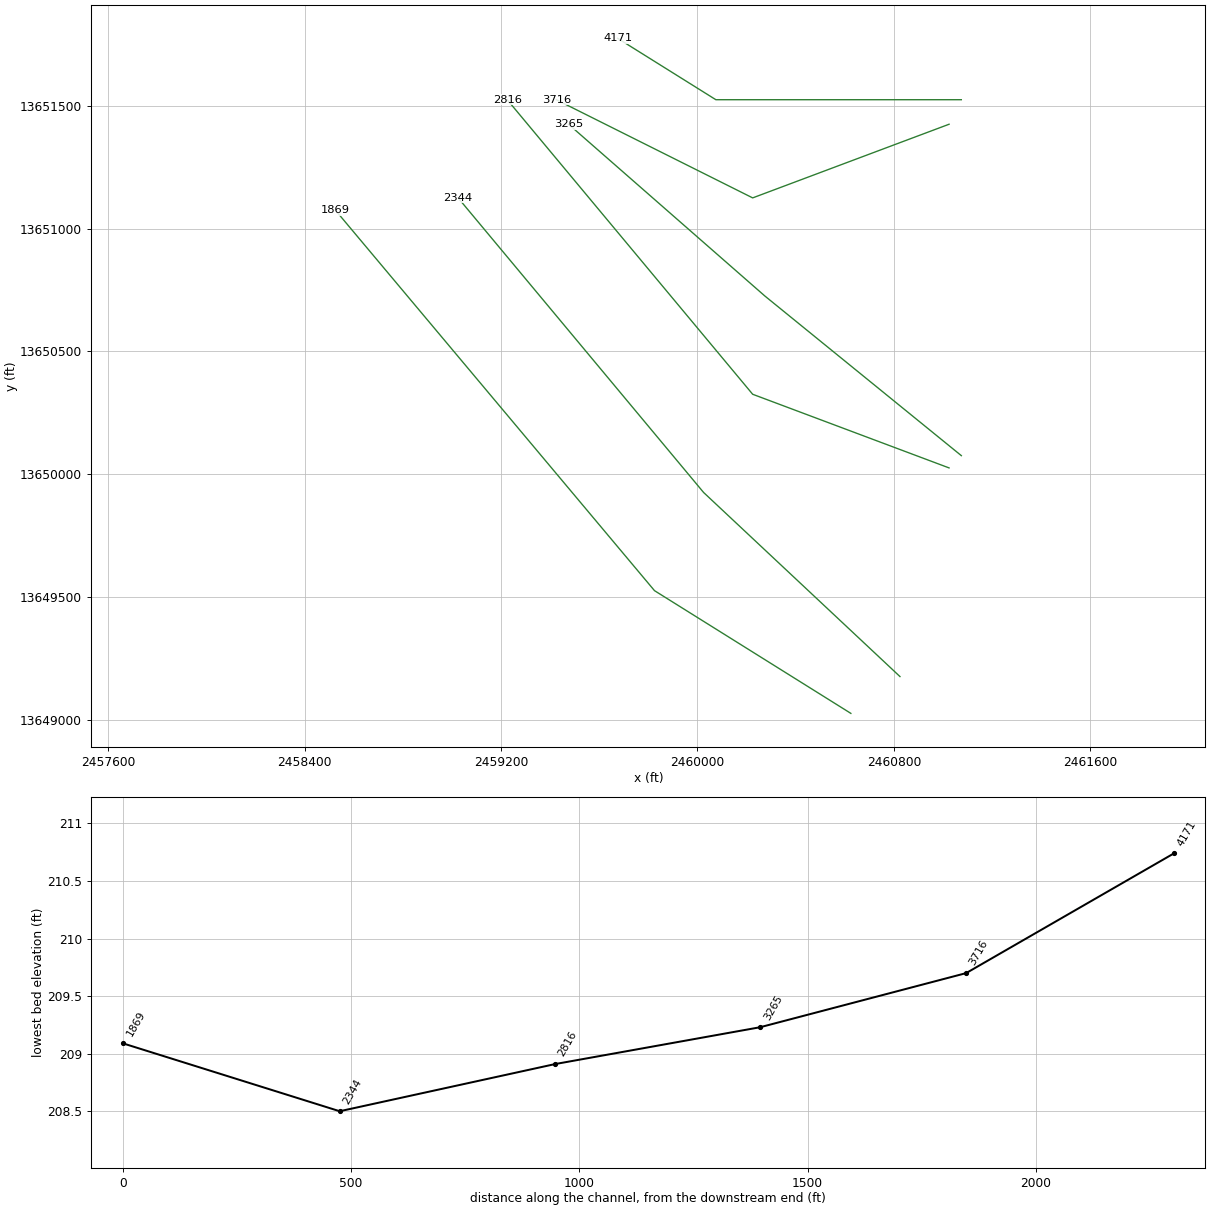
HEC-RAS study Stream0755.prj: Stream0755 Base Level Engineering

--- Stream0755.g01 (geometry) --- (continued)

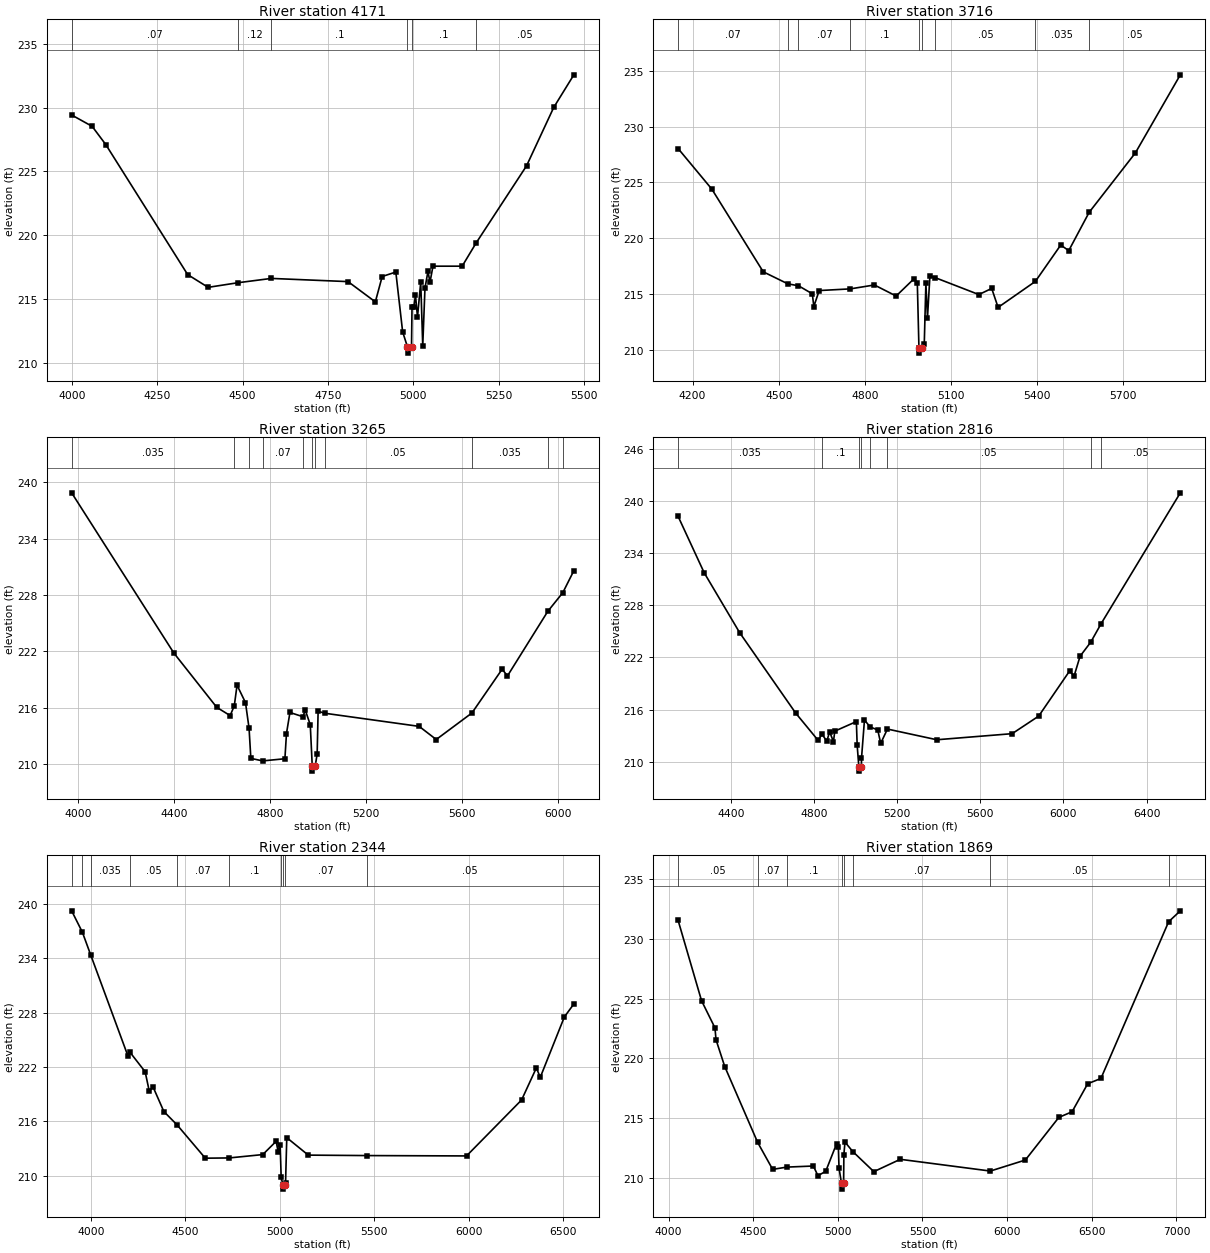
Type RM Length L Ch R = 1 ,4171    ,455,455,455
BEGIN DESCRIPTION:
Stream0755 9.0
END DESCRIPTION:
XS GIS Cut Line= 3
      2461074.98       13651525.        2460075.       13651525.
      2459674.98     13651775.01
#Sta/Elev= 30
    3999  229.42    4059  228.53    4099   227.1    4339   216.9    4399   215.9
  4485.7  216.26  4584.1   216.6    4809  216.35    4889  214.76    4909  216.75
    4949   217.1    4969  212.41    4983  211.24  4983.5  210.74    4995  211.24
  4996.5  214.38  5001.9  214.38  5006.6  215.29  5012.5  213.57    5022  216.31
  5027.9  211.32  5034.4  215.83  5043.2  217.16  5049.1   216.3  5057.9  217.56
  5143.4  217.56  5184.1  219.37  5332.1  225.43  5411.7  230.01  5470.7  232.57
#Mann= 6 ,-1 , 0
    3999     .07       0  4485.7     .12       0  4584.1      .1       0
    4983     .05       0    4995      .1       0  5184.1     .05       0
Bank Sta=4983,4995
XS Rating Curve= 0 ,0
Exp/Cntr=0.3,0.1

Type RM Length L Ch R = 1 ,3716    ,451,451,451
BEGIN DESCRIPTION:
Stream0755 8.0
END DESCRIPTION:
XS GIS Cut Line= 3
        2461025.       13651425.        2460225.       13651125.
      2459425.03     13651524.99
#Sta/Elev= 30
  4149.7  228.04  4267.2   224.4  4446.1  216.99  4531.9  215.91  4568.8  215.74
    4617  215.02  4622.3  213.88    4641  215.31  4749.2  215.46  4833.2  215.81
  4908.9  214.82  4972.1  216.39  4982.7  215.96  4988.3   210.2  4988.8   209.7
  5000.3   210.2  5006.9  210.55  5012.5  215.97  5018.1  212.88  5026.5  216.61
  5045.6  216.46    5197  214.95  5241.7   215.5    5264   213.8  5393.8  216.13
  5482.1  219.39    5510  218.89    5581  222.32    5742  227.65  5898.5  234.65
#Mann= 9 ,-1 , 0
  4149.7     .07       0  4531.9     .12       0  4568.8     .07       0
  4749.2      .1       0  4988.3     .05       0  5000.3      .1       0
  5045.6     .05       0  5393.8    .035       0    5581     .05       0
Bank Sta=4988.3,5000.3
XS Rating Curve= 0 ,0
Exp/Cntr=0.3,0.1

Type RM Length L Ch R = 1 ,3265    ,449,449,449
BEGIN DESCRIPTION:
Stream0755 7.0
END DESCRIPTION:
XS GIS Cut Line= 3
      2461075.01     13650074.99        2460275.       13650725.
        2459475.       13651425.
#Sta/Elev= 30
  3973.2  238.89  4399.2  221.82  4578.1  216.03    4634  215.15  4651.2  216.18
  4662.8  218.39    4698  216.53  4712.9   213.8  4720.3  210.59  4769.6  210.32
  4862.3  210.55  4868.9  213.24  4883.3  215.48  4937.5  215.03  4947.2  215.74
  4968.1  214.17  4976.4  209.73  4976.9  209.23  4988.4  209.73  4996.8  211.06
  5000.8  215.61  5028.1   215.4  5422.1     214  5493.3   212.6  5642.2  215.43
    5768  220.09  5790.3  219.38  5958.4  226.26    6021  228.25    6067  230.59
#Mann= 11 ,-1 , 0
  3973.2    .035       0  4651.2     .07       0  4712.9      .1       0
  4769.6     .07       0  4937.5      .1       0  4976.4     .05       0
  4988.4      .1       0  5028.1     .05       0  5642.2    .035       0
  5958.4     .05       0    6021    .035       0
Bank Sta=4976.4,4988.4
XS Rating Curve= 0 ,0
Exp/Cntr=0.3,0.1

Type RM Length L Ch R = 1 ,2816    ,472,472,472
BEGIN DESCRIPTION:
Stream0755 6.0
END DESCRIPTION:
XS GIS Cut Line= 3
        2461025.       13650025.        2460225.       13650325.
      2459224.97     13651525.04
#Sta/Elev= 30
  4145.6  238.22  4271.1  231.73    4442  224.83  4711.6  215.58  4819.3  212.45
    4838  213.16  4861.2  212.35  4874.5  213.44  4893.2   212.3  4899.4  213.51
  5003.3  214.61  5007.2  211.88  5015.2  209.41  5015.7  208.91  5027.7  209.41
    5028  210.38  5042.3  214.79  5069.9  213.99  5106.1  213.65  5120.4  212.11
  5152.8  213.75  5390.5  212.52    5753  213.22  5880.6  215.24    6029  220.42
  6051.1  219.86  6079.8  222.13  6131.2  223.75  6180.9  225.87  6562.1  240.93
#Mann= 8 ,-1 , 0
  4145.6    .035       0    4838      .1       0  5015.2     .05       0
  5027.7      .1       0  5069.9     .07       0  5152.8     .05       0
  6131.2    .035       0  6180.9     .05       0
Bank Sta=5015.2,5027.7
XS Rating Curve= 0 ,0
Exp/Cntr=0.3,0.1

Type RM Length L Ch R = 1 ,2344    ,475,475,475
BEGIN DESCRIPTION:
Stream0755 5.0
END DESCRIPTION:
XS GIS Cut Line= 3
      2460825.03     13649174.98        2460025.       13649925.
      2459024.98     13651125.02
#Sta/Elev= 30
  3898.6  239.27  3955.5   236.9    3999  234.42  4195.9  223.26  4207.5  223.63
  4287.7  221.48  4309.2  219.36  4330.2  219.77  4386.8  217.08  4456.8   215.6
  4606.2  211.92  4733.1  211.95  4910.5  212.32  4981.3  213.79  4991.8  212.62
  5002.4   213.4  5007.9  209.79    5017     209  5017.5   208.5  5029.5     209
    5031  209.14  5037.5  214.19  5151.4  212.26  5460.4  212.21  5989.1  212.17
  6280.7  218.36  6358.8   221.9  6379.6  220.86  6507.2  227.54  6557.3  228.97
#Mann= 10 ,-1 , 0
  3898.6    .035       0  3955.5     .07       0    3999    .035       0
  4207.5     .05       0  4456.8     .07       0  4733.1      .1       0
  5007.9     .07       0    5017     .05       0  5029.5     .07       0
  5460.4     .05       0
Bank Sta=5017,5029.5
XS Rating Curve= 0 ,0
Exp/Cntr=0.3,0.1

Type RM Length L Ch R = 1 ,1869    ,0,0,0
BEGIN DESCRIPTION:
Stream0755 4.0
END DESCRIPTION:
XS GIS Cut Line= 3
      2460624.98     13649025.01        2459825.       13649525.
      2458524.98     13651075.02
#Sta/Elev= 30
  4056.6  231.53  4195.1  224.82  4274.1  222.56  4280.6  221.56  4331.9  219.33
  4526.5  212.99    4615  210.74  4699.3  210.93  4855.5  211.02  4882.6  210.21
  4928.6  210.58  4992.3  212.87  5003.2  212.58  5007.1  210.83  5021.7  209.59
  5022.2  209.09  5034.2  209.59  5035.7  211.98  5042.3  213.02  5088.2  212.23
  5212.7  210.55  5368.8  211.58  5900.9   210.6  6107.7  211.52  6305.5  215.08
  6383.6  215.55  6475.9  217.89    6554  218.33  6954.1  231.42    7023  232.33
#Mann= 8 ,-1 , 0
  4056.6     .05       0  4526.5     .07       0  4699.3      .1       0
  5021.7     .05       0  5034.2      .1       0  5088.2     .07       0
  5900.9     .05       0  6954.1     .07       0
Bank Sta=5021.7,5034.2
XS Rating Curve= 0 ,0
Exp/Cntr=0.3,0.1

Chan Stop Cuts=-1
Use User Specified Reach Order=0
Composite Channel Slope=5