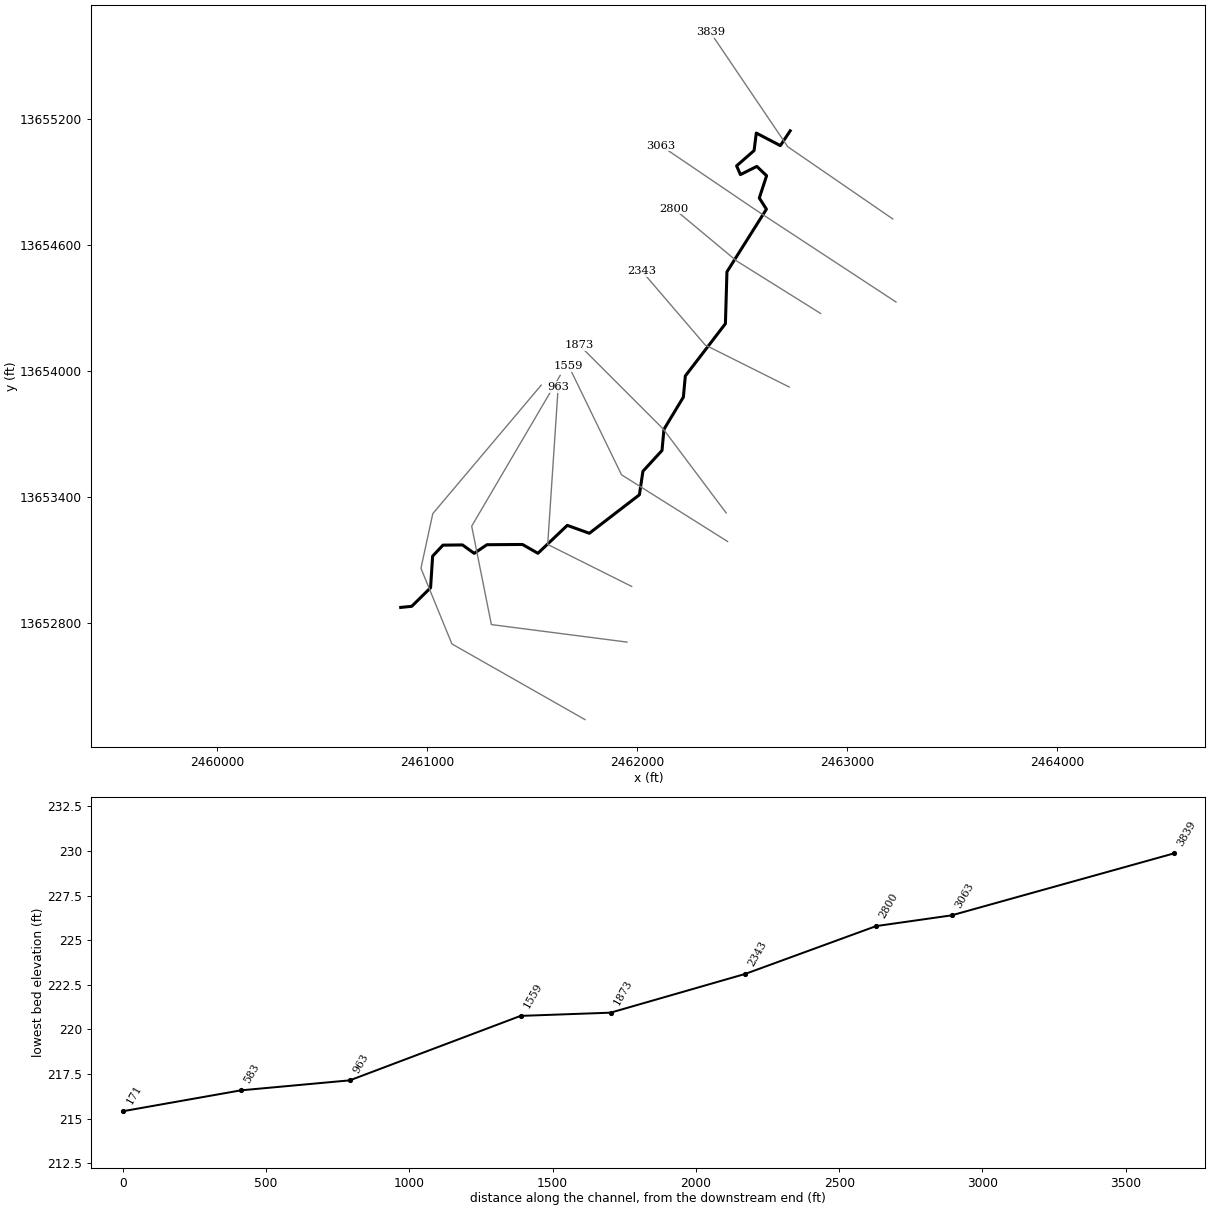
--- Stream0756.prj (project) ---

Proj Title=Stream0756 Base Level Engineering
Current Plan=p01
Default Exp/Contr=0.3,0.1
English Units
Geom File=g01
Flow File=f01
Plan File=p01
BEGIN DESCRIPTION:
Stream0756
END DESCRIPTION:

--- Stream0756.p01 (plan) ---

Plan Title=Multiple Run
Short Identifier=Multiple
Geom File=g01
Flow File=f01
Subcritical Flow
K Sum by GR= 0
Std Step Tol= 0.01
Critical Tol= 0.01
Num of Std Step Trials= 20
Max Error Tol= 0.3
Flow Tol Ratio= 0.001
Split Flow NTrial= 30
Split Flow Tol= 0.02
Split Flow Ratio= 0.02
Log Output Level= 0
Friction Slope Method= 1
Unsteady Friction Slope Method= 2
Unsteady Bridges Friction Slope Method= 1
Parabolic Critical Depth
Global Vel Dist=  1 , 1 , 1
Global Log Level= 0
CheckData=True
Encroach Param= -1, 0, 0, 0
BEGIN DESCRIPTION:
Multiple Run
END DESCRIPTION:

--- Stream0756.f01 (steady flow) ---

Flow Title=Multiple
Number of Profiles=7
Profile Names=10-year,25-year,50-year,1pct_min,100-year,1pct_plu,500-year
River Rch & RM= Stream0756,Reach-1,3839
     711    1145    1537     999    1992    3976    3316
Boundary for River Rch & Prof#=Stream0756,Reach-1,1
Up Type=0
Dn Type=3
Dn Slope=0.005
Boundary for River Rch & Prof#=Stream0756,Reach-1,2
Up Type=0
Dn Type=3
Dn Slope=0.005
Boundary for River Rch & Prof#=Stream0756,Reach-1,3
Up Type=0
Dn Type=3
Dn Slope=0.005
Boundary for River Rch & Prof#=Stream0756,Reach-1,4
Up Type=0
Dn Type=3
Dn Slope=0.005
Boundary for River Rch & Prof#=Stream0756,Reach-1,5
Up Type=0
Dn Type=3
Dn Slope=0.005
Boundary for River Rch & Prof#=Stream0756,Reach-1,6
Up Type=0
Dn Type=3
Dn Slope=0.005
Boundary for River Rch & Prof#=Stream0756,Reach-1,7
Up Type=0
Dn Type=3
Dn Slope=0.005

--- Stream0756.g01 (geometry) ---

Geom Title=Existing Conditions

River Reach=Stream0756,Reach-1
Reach XY= 30
      2462729.95     13655144.79      2462683.07     13655074.48
      2462568.49     13655134.38      2462558.07     13655051.04
      2462474.74     13654978.13      2462492.97     13654936.46
      2462571.09     13654975.52      2462617.60     13654931.07
      2462582.83     13654824.92      2462616.76     13654771.77
      2462428.75     13654473.45      2462421.45     13654226.47
      2462230.54     13653977.42      2462221.17     13653876.59
      2462128.83     13653723.41      2462119.46     13653622.58
      2462028.63     13653523.50      2462011.74     13653411.35
      2461773.35     13653228.16      2461668.27     13653265.85
      2461528.42     13653132.80      2461455.02     13653174.81
      2461285.44     13653173.62      2461225.00     13653132.56
      2461169.10     13653172.64      2461076.25     13653171.64
      2461026.98     13653119.35      2461017.20     13652968.79
      2460927.54     13652880.30      2460875.00     13652875.00

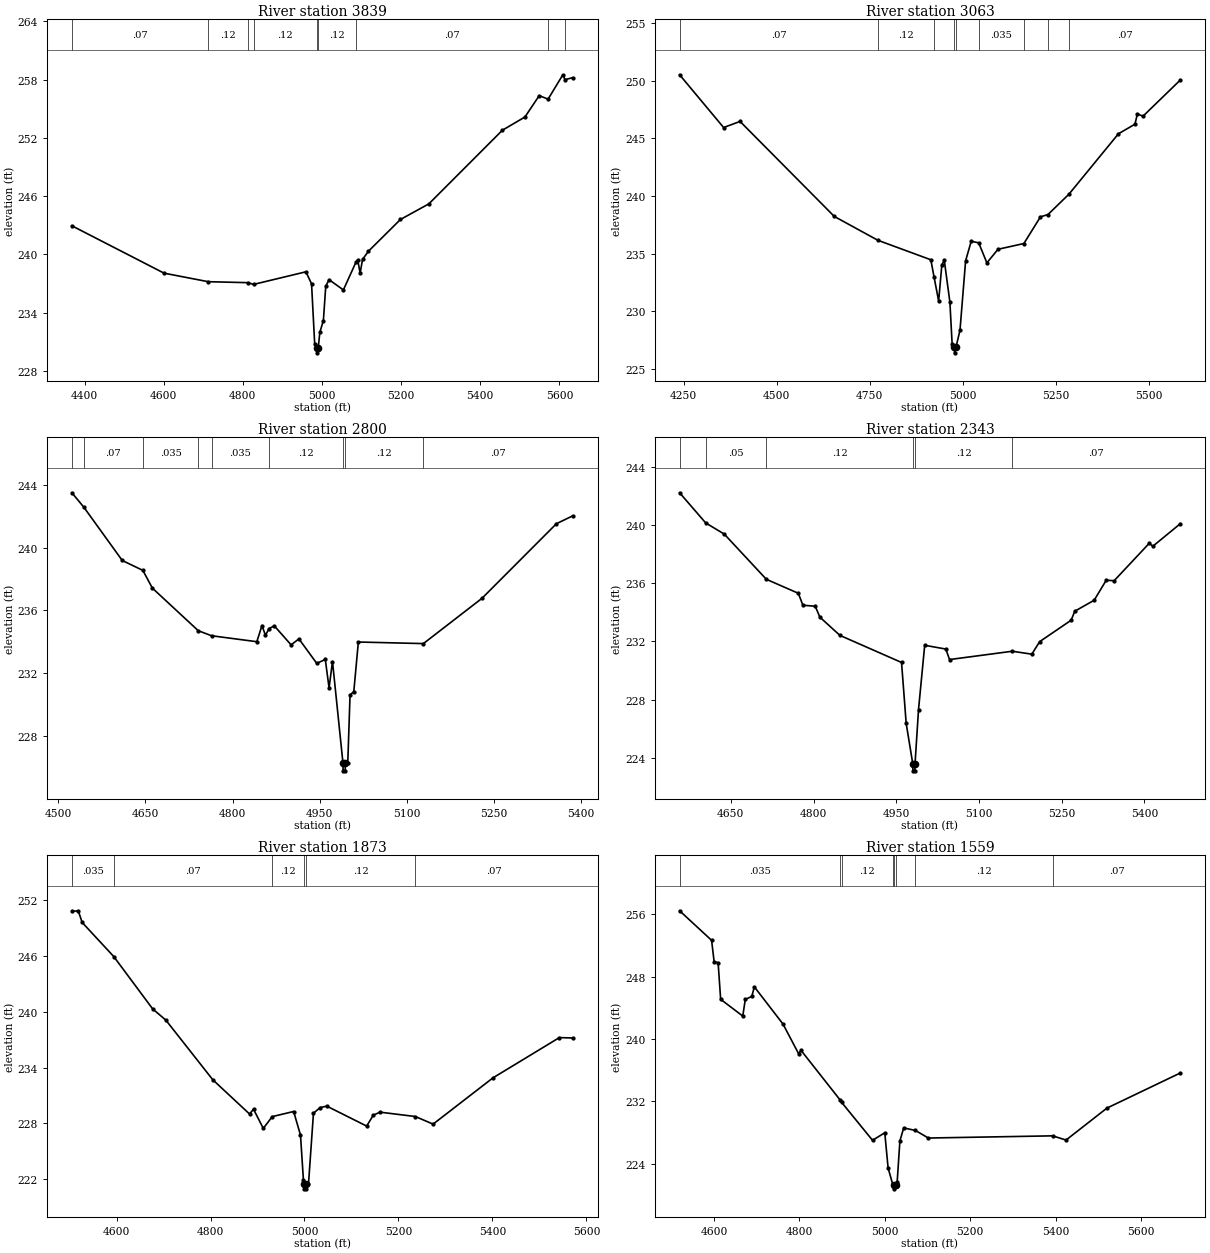
Type RM Length L Ch R = 1,3839,776,776,776
BEGIN DESCRIPTION:
XS7655
END DESCRIPTION:
XS GIS Cut Line= 3
      2463218.24     13654725.51      2462718.23     13655069.27
      2462349.19     13655615.03
#Sta/Elev= 30
  4367.9  242.95  4600.8  238.07  4712.5  237.19  4812.9  237.09  4827.0  236.91
  4959.4  238.21  4973.6  236.97  4981.6  230.72  4986.5  230.36  4986.8  229.86
  4990.5  230.36  4994.5  231.96  5003.5  233.19  5009.5  236.72  5017.8  237.40
  5054.0  236.34  5085.8  239.20  5090.2  239.44  5096.4  238.06  5102.4  239.48
  5117.4  240.33  5198.2  243.60  5270.1  245.21  5456.0  252.80  5512.9  254.16
  5549.0  256.36  5571.4  256.00  5608.7  258.51  5614.1  258.01  5633.5  258.21
#Mann=9,-1,0
  4367.9    0.07       0  4712.5    0.12       0  4812.9    0.07       0
  4827.0    0.12       0  4986.5    0.05       0  4990.5    0.12       0
  5085.8    0.07       0  5571.4   0.035       0  5614.1    0.12       0
Bank Sta=4986.5,4990.5
Exp/Cntr=0.3,0.1

Type RM Length L Ch R = 1,3063,263,263,263
BEGIN DESCRIPTION:
Stream0756 6.0
END DESCRIPTION:
XS GIS Cut Line= 3
      2463233.85     13654329.69      2462567.19     13654767.19
      2462114.05     13655074.49
#Sta/Elev= 30
  4239.1  250.53  4357.3  245.95  4401.4  246.48  4654.6  238.23  4771.7  236.16
  4913.8  234.47  4922.4  232.98  4934.8  230.89  4943.4  234.03  4949.9  234.43
  4965.0  230.79  4971.0  227.15  4977.3  226.89  4977.5  226.39  4981.4  226.89
  4992.1  228.35  5007.2  234.38  5022.3  236.08  5042.4  235.94  5064.3  234.20
  5094.2  235.38  5163.7  235.88  5208.3  238.20  5228.2  238.39  5284.9  240.17
  5417.7  245.41  5462.0  246.24  5468.6  247.14  5483.5  246.93  5584.0  250.08
#Mann=9,-1,0
  4239.1    0.07       0  4771.7    0.12       0  4922.4    0.07       0
  4977.3    0.05       0  4981.4    0.07       0  5042.4   0.035       0
  5163.7    0.07       0  5228.2   0.035       0  5284.9    0.07       0
Bank Sta=4977.3,4981.4
Exp/Cntr=0.3,0.1

Type RM Length L Ch R = 1,2800,457,457,457
BEGIN DESCRIPTION:
Stream0756 5.0
END DESCRIPTION:
XS GIS Cut Line= 3
      2462875.01     13654274.99      2462475.00     13654525.00
      2462175.02     13654774.98
#Sta/Elev= 30
  4523.4  243.49  4544.0  242.57  4610.1  239.18  4645.6  238.55  4662.0  237.42
  4741.0  234.71  4763.8  234.39  4841.8  234.01  4850.7  235.04  4856.6  234.42
  4863.0  234.85  4871.9  235.02  4900.8  233.81  4914.3  234.19  4945.0  232.63
  4959.7  232.88  4966.2  231.07  4972.1  232.75  4990.1  226.29  4990.4  225.79
  4994.0  225.79  4994.2  226.29  4998.4  226.29  5002.3  230.62  5008.8  230.84
  5016.6  233.99  5128.6  233.89  5229.4  236.77  5357.6  241.52  5385.6  242.02
#Mann=9,-1,0
  4523.4    0.05       0  4544.0    0.07       0  4645.6   0.035       0
  4741.0    0.12       0  4763.8   0.035       0  4863.0    0.12       0
  4990.1    0.05       0  4994.2    0.12       0  5128.6    0.07       0
Bank Sta=4990.1,4994.2
Exp/Cntr=0.3,0.1

Type RM Length L Ch R = 1,2343,470,470,470
BEGIN DESCRIPTION:
Stream0756 4.0
END DESCRIPTION:
XS GIS Cut Line= 3
      2462725.03     13653924.98      2462325.00     13654125.00
      2462025.02     13654474.98
#Sta/Elev= 30
  4557.1  242.20  4604.4  240.13  4638.2  239.36  4714.4  236.26  4772.4  235.30
  4780.7  234.48  4803.1  234.41  4811.5  233.66  4847.8  232.41  4959.6  230.55
  4968.0  226.37  4979.9  223.61  4980.2  223.11  4983.8  223.11  4984.1  223.61
  4990.4  227.32  5001.6  231.73  5040.0  231.47  5046.6  230.75  5160.4  231.32
  5195.9  231.12  5210.1  231.98  5267.2  233.45  5273.8  234.07  5308.9  234.82
  5330.9  236.20  5345.1  236.16  5408.8  238.73  5415.4  238.53  5465.3  240.08
#Mann=6,-1,0
  4557.1    0.07       0  4604.4    0.05       0  4714.4    0.12       0
  4979.9    0.05       0  4984.1    0.12       0  5160.4    0.07       0
Bank Sta=4979.9,4984.1
Exp/Cntr=0.3,0.1

Type RM Length L Ch R = 1,1873,314,314,314
BEGIN DESCRIPTION:
Stream0756 3.0
END DESCRIPTION:
XS GIS Cut Line= 3
      2462425.00     13653325.00      2462125.00     13653725.00
      2461724.99     13654125.01
#Sta/Elev= 30
  4505.0  250.83  4518.5  250.89  4526.9  249.63  4594.1  245.96  4676.9  240.32
  4705.0  239.11  4805.0  232.68  4883.1  229.00  4891.5  229.52  4912.3  227.45
  4931.4  228.72  4976.9  229.27  4991.5  226.73  4997.7  221.91  4999.8  221.44
  5000.0  220.94  5003.7  220.94  5004.0  221.44  5008.5  221.44  5019.1  229.09
  5033.3  229.69  5047.4  229.85  5132.3  227.70  5146.4  228.87  5160.6  229.20
  5235.9  228.73  5273.7  227.91  5401.0  232.89  5542.4  237.23  5570.7  237.19
#Mann=6,-1,0
  4505.0   0.035       0  4594.1    0.07       0  4931.4    0.12       0
  4999.8    0.05       0  5004.0    0.12       0  5235.9    0.07       0
Bank Sta=4999.8,5004
Exp/Cntr=0.3,0.1

Type RM Length L Ch R = 1,1559,596,596,596
BEGIN DESCRIPTION:
Stream0756 2.0
END DESCRIPTION:
XS GIS Cut Line= 3
      2462431.75     13653189.08      2461926.56     13653506.77
      2461675.02     13654024.97
#Sta/Elev= 30
  4519.4  256.44  4594.3  252.65  4600.2  249.92  4609.6  249.77  4615.5  245.08
  4667.3  242.93  4673.2  245.06  4688.5  245.45  4694.4  246.68  4761.5  241.91
  4798.0  238.11  4803.9  238.52  4894.8  232.20  4898.8  231.86  4971.2  226.99
  4999.9  227.95  5007.7  223.43  5018.4  221.36  5020.9  221.26  5021.1  220.76
  5025.1  221.26  5028.9  221.63  5035.3  226.90  5044.2  228.58  5071.8  228.25
  5101.9  227.28  5393.0  227.56  5424.4  227.02  5520.2  231.12  5692.2  235.63
#Mann=8,-1,0
  4519.4   0.035       0  4894.8    0.07       0  4898.8    0.12       0
  5018.4   0.035       0  5020.9    0.05       0  5025.1   0.035       0
  5071.8    0.12       0  5393.0    0.07       0
Bank Sta=5020.9,5025.1
Exp/Cntr=0.3,0.1

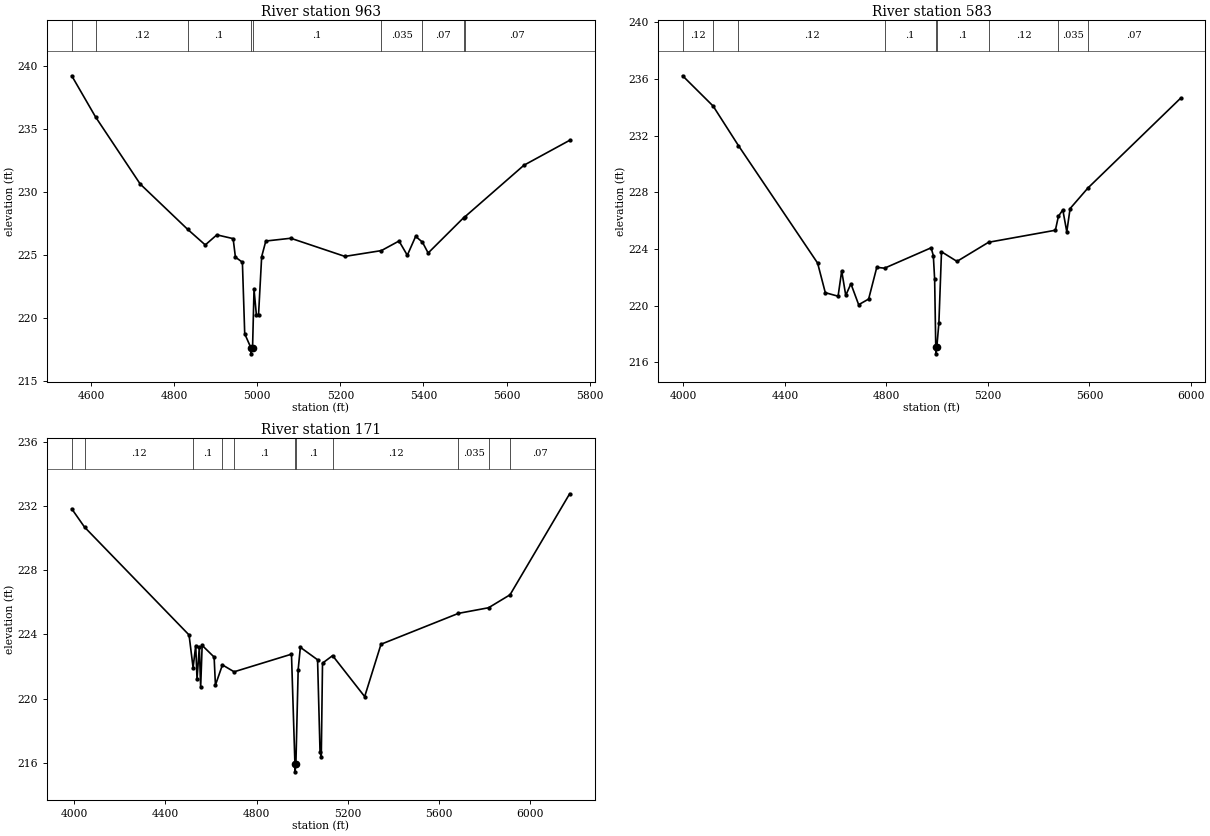
Type RM Length L Ch R = 1,963,380,380,380
BEGIN DESCRIPTION:
Stream0756 1.0
END DESCRIPTION:
XS GIS Cut Line= 3
      2461975.03     13652974.98      2461575.00     13653175.00
      2461625.00     13653924.99
#Sta/Elev= 30
  4553.1  239.21  4610.3  235.95  4718.0  230.62  4832.1  227.03  4874.6  225.79
  4902.5  226.59  4941.7  226.29  4947.2  224.82  4964.0  224.42  4969.6  218.74
  4984.2  217.65  4984.5  217.15  4988.5  217.65  4992.0  222.27  4997.6  220.26
  5002.9  220.26  5010.4  224.86  5020.4  226.10  5080.5  226.32  5210.8  224.88
  5298.6  225.34  5341.1  226.10  5361.1  224.97  5381.2  226.47  5397.5  226.01
  5411.3  225.15  5496.4  227.94  5499.7  228.02  5641.8  232.11  5752.0  234.09
#Mann=9,-1,0
  4553.1   0.035       0  4610.3    0.12       0  4832.1     0.1       0
  4984.2    0.05       0  4988.5     0.1       0  5298.6   0.035       0
  5397.5    0.07       0  5496.4    0.12       0  5499.7    0.07       0
Bank Sta=4984.2,4988.5
Exp/Cntr=0.3,0.1

Type RM Length L Ch R = 1,583,412,412,412
BEGIN DESCRIPTION:
XS7656
END DESCRIPTION:
XS GIS Cut Line= 4
      2461952.63     13652709.89      2461306.77     13652793.23
      2461213.02     13653261.98      2461634.66     13653980.33
#Sta/Elev= 30
  3996.6  236.23  4116.9  234.09  4216.5  231.30  4528.6  223.00  4558.9  220.91
  4609.3  220.66  4623.5  222.45  4639.5  220.72  4659.8  221.54  4690.4  220.06
  4729.7  220.46  4761.8  222.70  4792.3  222.64  4976.0  224.08  4984.7  223.52
  4989.8  221.86  4994.2  217.09  4994.5  216.59  4998.5  217.09  5006.6  218.79
  5016.8  223.80  5077.9  223.12  5202.3  224.47  5465.6  225.32  5477.5  226.30
  5494.9  226.76  5510.6  225.21  5523.6  226.85  5593.7  228.30  5958.8  234.64
#Mann=9,-1,0
  3996.6    0.12       0  4116.9    0.05       0  4216.5    0.12       0
  4792.3     0.1       0  4994.2    0.05       0  4998.5     0.1       0
  5202.3    0.12       0  5477.5   0.035       0  5593.7    0.07       0
Bank Sta=4994.2,4998.5
Exp/Cntr=0.3,0.1

Type RM Length L Ch R = 1,171,0,0,0
BEGIN DESCRIPTION:
E21321
END DESCRIPTION:
XS GIS Cut Line= 5
      2461752.60     13652340.79      2461118.88     13652701.05
      2460971.31     13653061.29      2461027.73     13653321.71
      2461544.22     13653933.68
#Sta/Elev= 30
  3989.0  231.85  4045.0  230.71  4503.9  223.97  4521.6  221.93  4533.2  223.31
  4538.9  221.21  4549.0  223.22  4554.8  220.69  4561.4  223.32  4613.9  222.59
  4619.7  220.84  4650.4  222.10  4701.7  221.67  4953.5  222.77  4968.6  215.92
  4968.9  215.42  4972.9  215.92  4982.9  221.81  4992.4  223.20  5068.0  222.42
  5078.8  216.69  5084.3  216.35  5089.7  222.21  5134.0  222.68  5274.8  220.12
  5346.4  223.39  5686.4  225.32  5818.5  225.67  5912.8  226.48  6174.5  232.79
#Mann=11,-1,0
  3989.0   0.035       0  4045.0    0.12       0  4521.6     0.1       0
  4650.4    0.12       0  4701.7     0.1       0  4968.6    0.05       0
  4972.9     0.1       0  5134.0    0.12       0  5686.4   0.035       0
  5818.5    0.12       0  5912.8    0.07       0
Bank Sta=4968.6,4972.9
Exp/Cntr=0.3,0.1

Chan Stop Cuts=-1