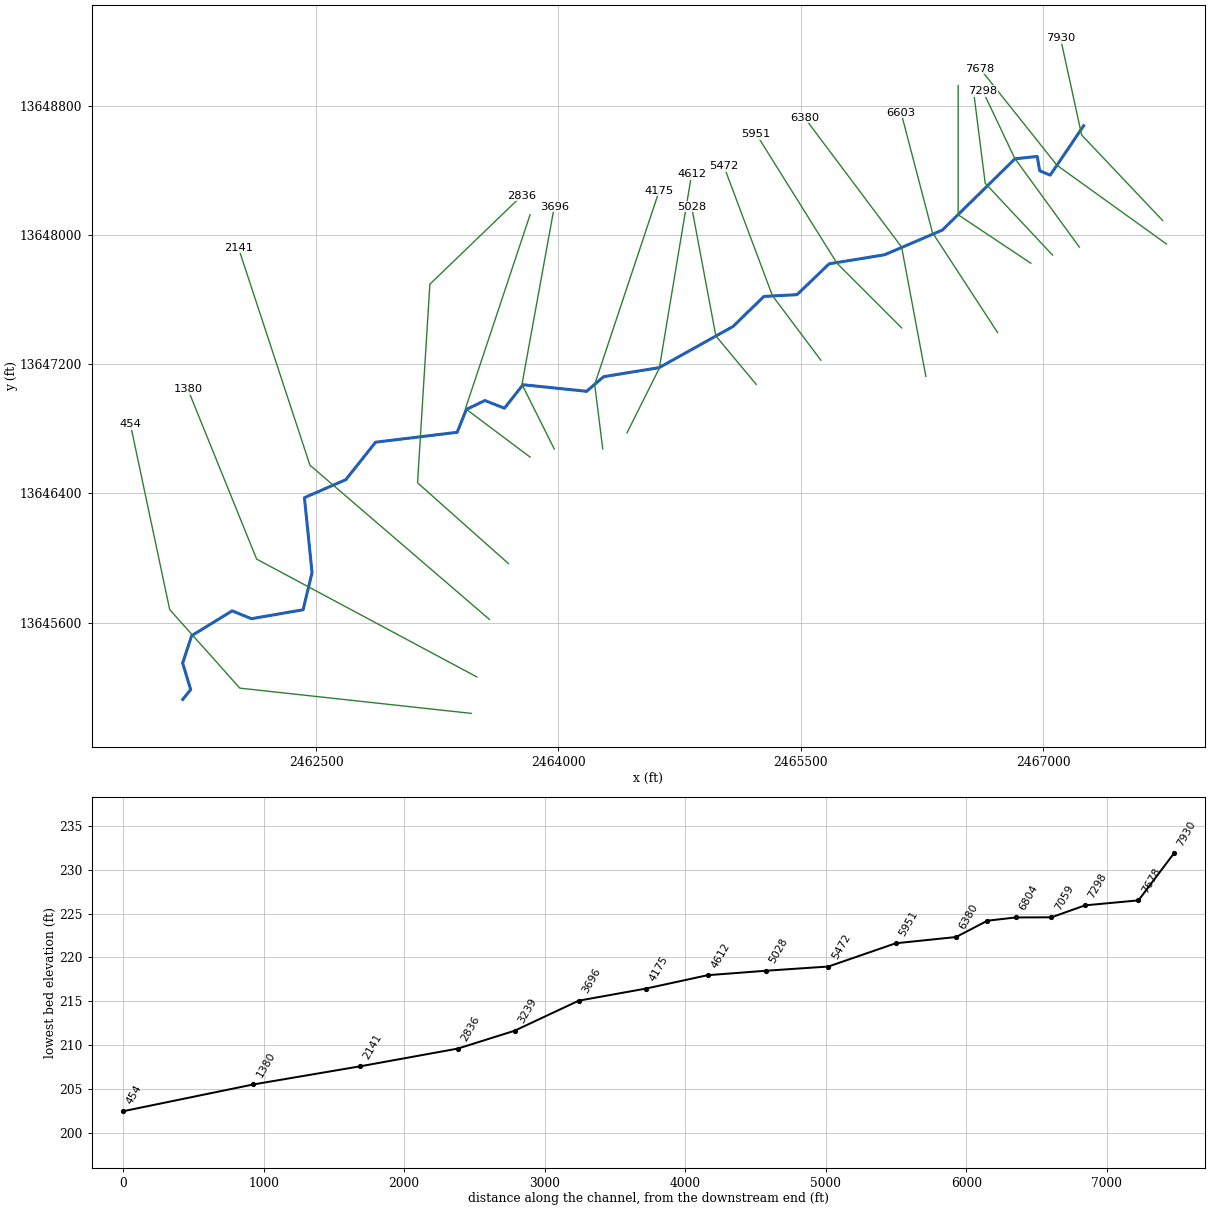
--- Stream0757.prj (project) ---

Proj Title=Stream0757 Base Level Engineering
Current Plan=p01
Default Exp/Contr=0.3,0.1
English Units
Geom File=g01
Flow File=f01
Plan File=p01
BEGIN DESCRIPTION:
Stream0757
END DESCRIPTION:

--- Stream0757.p01 (plan) ---

Plan Title=Multiple Run
Short Identifier=Multiple
Geom File=g01
Flow File=f01
Subcritical Flow
K Sum by GR= 0
Std Step Tol= 0.01
Critical Tol= 0.01
Num of Std Step Trials= 20
Max Error Tol= 0.3
Flow Tol Ratio= 0.001
Split Flow NTrial= 30
Split Flow Tol= 0.02
Split Flow Ratio= 0.02
Log Output Level= 0
Friction Slope Method= 1
Unsteady Friction Slope Method= 2
Unsteady Bridges Friction Slope Method= 1
Parabolic Critical Depth
Global Vel Dist=  1 , 1 , 1
Global Log Level= 0
CheckData=True
Encroach Param= -1, 0, 0, 0
BEGIN DESCRIPTION:
Multiple Run
END DESCRIPTION:

--- Stream0757.f01 (steady flow) ---

Flow Title=Multiple
Number of Profiles=7
Profile Names=10-year,25-year,50-year,1pct_min,100-year,1pct_plu,500-year
River Rch & RM= Stream0757,Reach-1,7930
     884    1459    1992    1318    2629    5246    4534
River Rch & RM= Stream0757,Reach-1,7059
    1519    2560    3542    2367    4723    9424    8324
Boundary for River Rch & Prof#=Stream0757,Reach-1,1
Up Type=0
Dn Type=3
Dn Slope=0.005
Boundary for River Rch & Prof#=Stream0757,Reach-1,2
Up Type=0
Dn Type=3
Dn Slope=0.005
Boundary for River Rch & Prof#=Stream0757,Reach-1,3
Up Type=0
Dn Type=3
Dn Slope=0.005
Boundary for River Rch & Prof#=Stream0757,Reach-1,4
Up Type=0
Dn Type=3
Dn Slope=0.005
Boundary for River Rch & Prof#=Stream0757,Reach-1,5
Up Type=0
Dn Type=3
Dn Slope=0.005
Boundary for River Rch & Prof#=Stream0757,Reach-1,6
Up Type=0
Dn Type=3
Dn Slope=0.005
Boundary for River Rch & Prof#=Stream0757,Reach-1,7
Up Type=0
Dn Type=3
Dn Slope=0.005

--- Stream0757.g01 (geometry) ---

Geom Title=Existing Conditions

River Reach=Stream0757,Reach-1
Reach XY= 30
      2467251.95     13648676.13      2467044.92     13648370.14
      2466979.82     13648397.48      2466964.19     13648486.02
      2466826.45     13648471.50      2466377.43     13648030.52
      2466019.07     13647877.25      2465676.47     13647821.46
      2465477.45     13647630.46      2465272.55     13647619.54
      2465081.06     13647433.14      2464623.53     13647178.55
      2464280.86     13647122.92      2464175.10     13647032.33
      2463780.84     13647072.95      2463666.52     13646927.64
      2463545.17     13646975.29      2463430.25     13646919.56
      2463373.78     13646778.44      2462868.79     13646717.20
      2462684.81     13646485.51      2462428.44     13646373.75
      2462475.43     13645909.82      2462419.99     13645680.00
      2462100.00     13645624.61      2461981.11     13645673.20
      2461730.26     13645519.53      2461674.60     13645350.00
      2461724.18     13645185.46      2461675.00     13645125.00

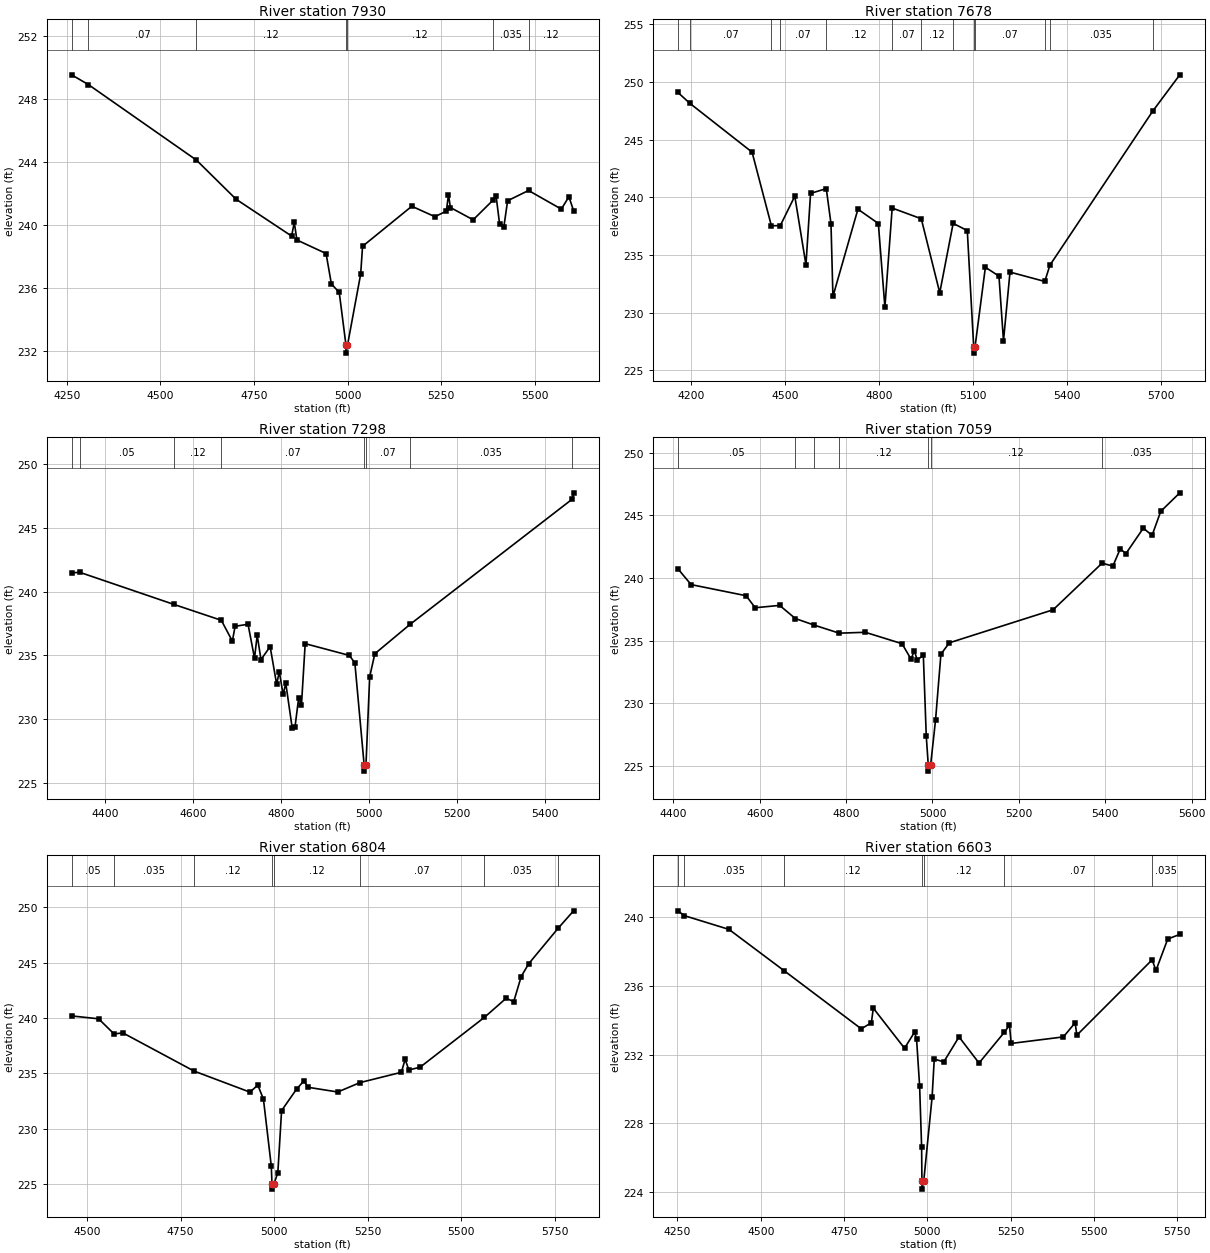
Type RM Length L Ch R = 1,7930,252,252,252
BEGIN DESCRIPTION:
XS7660
END DESCRIPTION:
XS GIS Cut Line= 3
      2467740.56     13648089.55      2467239.58     13648618.75
      2467108.71     13649217.18
#Sta/Elev= 30
  4262.7  249.51  4307.5  248.89  4596.1  244.10  4701.9  241.62  4850.4  239.28
  4857.7  240.14  4864.6  239.03  4942.6  238.17  4956.8  236.24  4977.8  235.70
  4995.8  232.35  4996.1  231.85  4999.8  232.35  5035.0  236.86  5040.1  238.63
  5171.7  241.17  5233.3  240.51  5264.0  240.86  5269.7  241.90  5274.8  241.09
  5335.6  240.31  5389.3  241.57  5397.0  241.81  5406.4  240.02  5417.5  239.84
  5427.7  241.52  5483.6  242.17  5571.1  240.99  5591.5  241.77  5604.0  240.89
#Mann=7,-1,0
  4262.7    0.05       0  4307.5    0.07       0  4596.1    0.12       0
  4995.8    0.05       0  4999.8    0.12       0  5389.3   0.035       0
  5483.6    0.12       0
Bank Sta=4995.8,4999.8
Exp/Cntr=0.3,0.1

Type RM Length L Ch R = 1,7678,380,380,380
BEGIN DESCRIPTION:
XS7661
END DESCRIPTION:
XS GIS Cut Line= 3
      2467764.82     13647943.78      2467086.81     13648431.25
      2466610.02     13649030.05
#Sta/Elev= 30
  4158.9  249.09  4197.2  248.14  4395.6  243.91  4457.2  237.53  4485.6  237.55
  4531.8  240.10  4567.4  234.15  4582.1  240.34  4632.2  240.75  4647.2  237.72
  4653.4  231.41  4733.1  238.97  4798.2  237.73  4819.1  230.48  4842.3  239.07
  4935.1  238.14  4994.0  231.73  5036.7  237.74  5081.8  237.12  5102.3  227.00
  5102.6  226.50  5106.3  227.00  5139.5  233.94  5182.8  233.17  5197.2  227.57
  5218.0  233.52  5328.9  232.71  5345.3  234.12  5673.0  247.46  5759.4  250.61
#Mann=13,-1,0
  4158.9    0.05       0  4197.2    0.07       0  4457.2    0.12       0
  4485.6    0.07       0  4632.2    0.12       0  4842.3    0.07       0
  4935.1    0.12       0  5036.7    0.07       0  5102.3    0.05       0
  5106.3    0.07       0  5328.9    0.12       0  5345.3   0.035       0
  5673.0    0.07       0
Bank Sta=5102.3,5106.3
Exp/Cntr=0.3,0.1

Type RM Length L Ch R = 1,7298,239,239,239
BEGIN DESCRIPTION:
Stream0757 16.0
END DESCRIPTION:
XS GIS Cut Line= 3
      2467224.99     13647925.02      2466825.00     13648475.00
      2466627.89     13648890.79
#Sta/Elev= 30
  4323.9  241.47  4342.4  241.51  4556.6  238.99  4663.9  237.75  4689.0  236.12
  4695.2  237.28  4724.6  237.44  4739.3  234.78  4745.4  236.58  4754.0  234.67
  4774.8  235.69  4789.5  232.75  4795.7  233.71  4804.2  231.94  4810.4  232.80
  4825.0  229.29  4831.2  229.37  4839.7  231.70  4845.9  231.08  4854.4  235.92
  4954.5  235.00  4967.2  234.42  4988.3  226.43  4988.6  225.93  4992.5  226.43
  5000.9  233.32  5012.6  235.13  5092.6  237.43  5461.2  247.25  5464.1  247.74
#Mann=8,-1,0
  4323.9   0.035       0  4342.4    0.05       0  4556.6    0.12       0
  4663.9    0.07       0  4988.3    0.05       0  4992.5    0.07       0
  5092.6   0.035       0  5461.2    0.07       0
Bank Sta=4988.3,4992.5
Exp/Cntr=0.3,0.1

Type RM Length L Ch R = 1,7059,255,255,255
BEGIN DESCRIPTION:
XS7659
END DESCRIPTION:
XS GIS Cut Line= 3
      2467059.04     13647875.68      2466642.36     13648320.14
      2466572.92     13648868.73
#Sta/Elev= 30
  4410.4  240.74  4441.0  239.47  4568.5  238.58  4589.5  237.62  4646.1  237.81
  4682.4  236.76  4726.4  236.23  4784.0  235.59  4844.4  235.66  4929.4  234.75
  4950.4  233.51  4957.8  234.20  4964.6  233.45  4978.8  233.82  4985.6  227.35
  4990.2  225.07  4990.6  224.57  4995.7  225.07  5007.1  228.66  5019.5  233.91
  5039.0  234.82  5279.4  237.46  5392.6  241.18  5417.6  240.95  5434.7  242.32
  5447.9  241.95  5488.2  243.98  5508.4  243.40  5528.5  245.32  5572.6  246.80
#Mann=7,-1,0
  4410.4    0.05       0  4682.4   0.035       0  4726.4    0.07       0
  4784.0    0.12       0  4990.2    0.05       0  4995.7    0.12       0
  5392.6   0.035       0
Bank Sta=4990.2,4995.7
Exp/Cntr=0.3,0.1

Type RM Length L Ch R = 1,6804,201,201,201
BEGIN DESCRIPTION:
Stream0757 15.0
END DESCRIPTION:
XS GIS Cut Line= 3
      2466924.99     13647825.01      2466475.00     13648125.00
      2466475.00     13648924.98
#Sta/Elev= 30
  4459.2  240.19  4531.3  239.93  4572.6  238.56  4595.9  238.66  4786.2  235.21
  4935.4  233.31  4956.5  233.94  4971.5  232.68  4992.5  226.63  4994.3  225.05
  4994.7  224.55  4999.8  225.05  5010.0  226.03  5020.0  231.64  5060.0  233.58
  5080.0  234.34  5090.0  233.75  5170.0  233.32  5229.5  234.17  5340.0  235.10
  5350.0  236.27  5360.0  235.31  5390.0  235.56  5561.8  240.06  5620.0  241.79
  5640.0  241.47  5660.0  243.74  5680.0  244.90  5758.8  248.11  5800.0  249.68
#Mann=8,-1,0
  4459.2    0.05       0  4572.6   0.035       0  4786.2    0.12       0
  4994.3    0.05       0  4999.8    0.12       0  5229.5    0.07       0
  5561.8   0.035       0  5758.8    0.07       0
Bank Sta=4994.3,4999.8
Exp/Cntr=0.3,0.1

Type RM Length L Ch R = 1,6603,223,223,223
BEGIN DESCRIPTION:
XS7658
END DESCRIPTION:
XS GIS Cut Line= 3
      2466718.76     13647396.51      2466315.97     13648014.58
      2466121.53     13648757.63
#Sta/Elev= 30
  4251.4  240.36  4270.9  240.08  4404.8  239.28  4570.8  236.87  4801.6  233.50
  4831.9  233.85  4837.8  234.70  4931.4  232.37  4961.6  233.31  4967.6  232.89
  4976.7  230.17  4982.7  226.63  4983.6  224.68  4984.0  224.18  4989.2  224.68
  5014.1  229.52  5020.6  231.74  5049.3  231.58  5094.9  233.03  5154.9  231.51
  5230.9  233.30  5246.3  233.71  5251.4  232.65  5408.0  233.03  5443.2  233.85
  5448.4  233.13  5674.1  237.51  5685.8  236.90  5721.0  238.72  5757.2  238.99
#Mann=7,-1,0
  4251.4    0.07       0  4270.9   0.035       0  4570.8    0.12       0
  4983.6    0.05       0  4989.2    0.12       0  5230.9    0.07       0
  5674.1   0.035       0
Bank Sta=4983.6,4989.2
Exp/Cntr=0.3,0.1

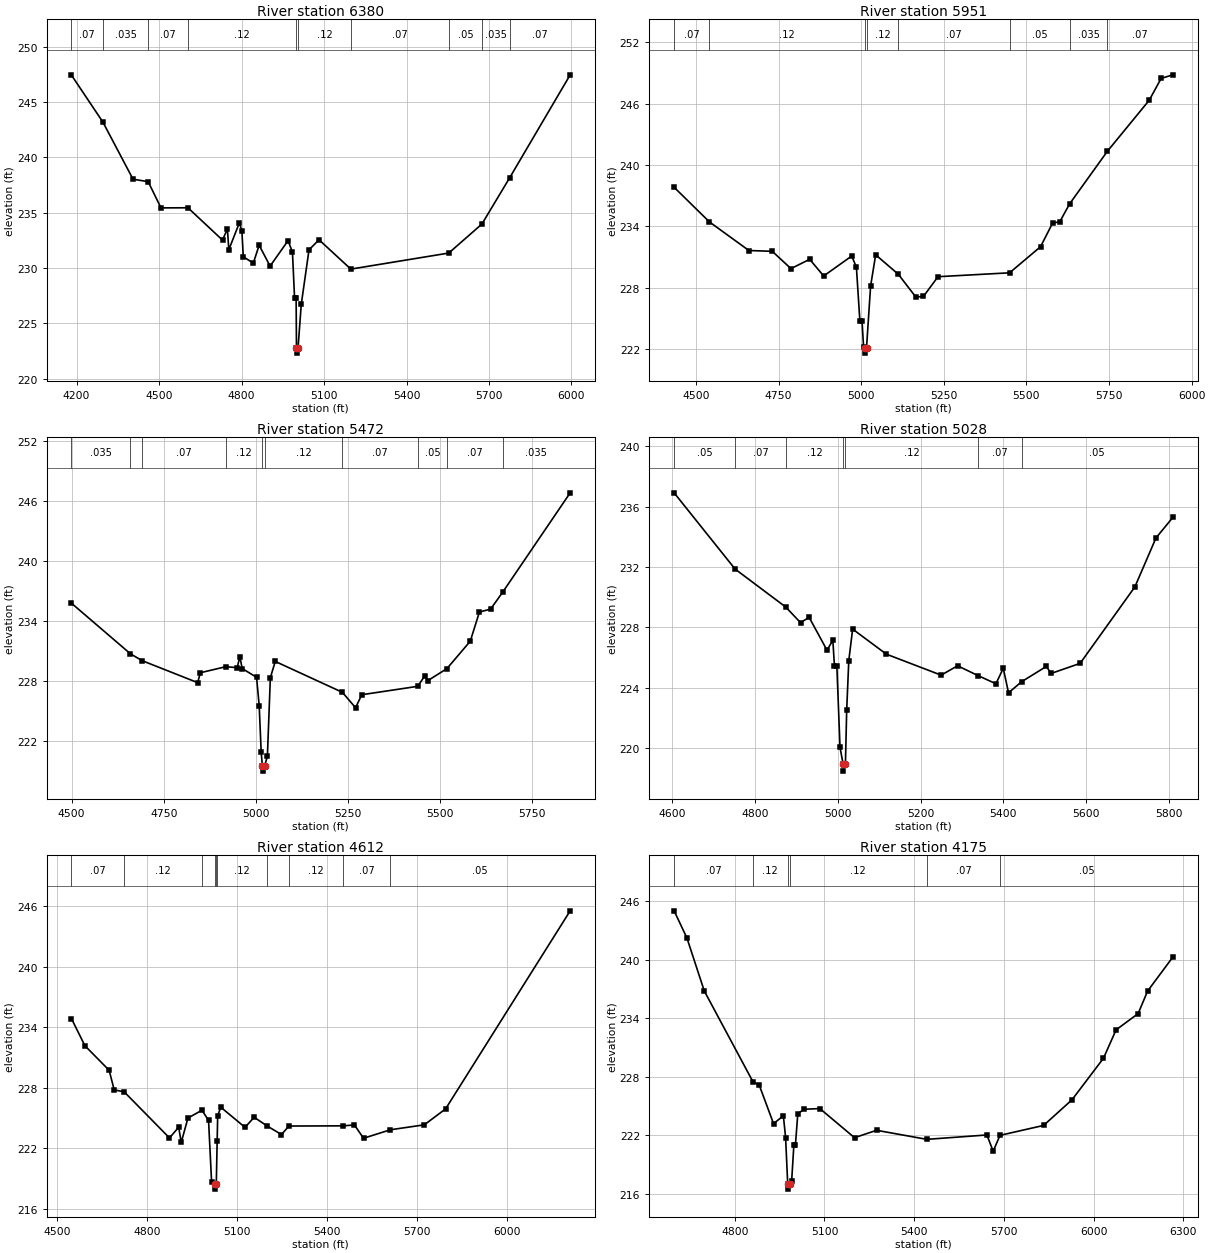
Type RM Length L Ch R = 1,6380,429,429,429
BEGIN DESCRIPTION:
Stream0757 14.0
END DESCRIPTION:
XS GIS Cut Line= 3
      2466275.01     13647124.97      2466125.00     13647925.00
      2465524.98     13648725.02
#Sta/Elev= 30
  4181.3  247.43  4295.6  243.19  4405.2  238.03  4460.2  237.81  4506.9  235.44
  4605.0  235.45  4730.7  232.53  4748.5  233.54  4753.6  231.66  4791.8  234.08
  4801.1  233.39  4806.2  231.03  4842.7  230.45  4863.9  232.07  4903.7  230.18
  4969.0  232.48  4985.1  231.45  4992.7  227.32  4998.4  227.32  4999.7  222.82
  5000.2  222.32  5005.5  222.82  5017.1  226.72  5045.3  231.65  5081.7  232.56
  5197.4  229.91  5553.7  231.36  5674.2  233.98  5775.4  238.17  5995.3  247.46
#Mann=10,-1,0
  4181.3    0.07       0  4295.6   0.035       0  4460.2    0.07       0
  4605.0    0.12       0  4999.7    0.05       0  5005.5    0.12       0
  5197.4    0.07       0  5553.7    0.05       0  5674.2   0.035       0
  5775.4    0.07       0
Bank Sta=4999.7,5005.5
Exp/Cntr=0.3,0.1

Type RM Length L Ch R = 1,5951,479,479,479
BEGIN DESCRIPTION:
Stream0757 13.0
END DESCRIPTION:
XS GIS Cut Line= 3
      2466125.02     13647424.98      2465725.00     13647825.00
      2465225.01     13648624.98
#Sta/Elev= 30
  4433.9  237.82  4540.9  234.43  4660.2  231.64  4730.9  231.56  4787.5  229.87
  4844.1  230.78  4886.5  229.15  4971.3  231.10  4985.5  230.01  4996.1  224.72
  5002.6  224.72  5007.3  222.17  5010.3  222.11  5010.8  221.61  5016.1  222.11
  5028.5  228.17  5043.8  231.22  5112.3  229.32  5165.3  227.09  5188.3  227.15
  5232.5  229.08  5449.1  229.46  5542.7  232.01  5579.2  234.32  5601.0  234.45
  5630.9  236.21  5745.0  241.34  5871.7  246.33  5907.6  248.46  5943.0  248.81
#Mann=8,-1,0
  4433.9    0.07       0  4540.9    0.12       0  5010.3    0.05       0
  5016.1    0.12       0  5112.3    0.07       0  5449.1    0.05       0
  5630.9   0.035       0  5745.0    0.07       0
Bank Sta=5010.3,5016.1
Exp/Cntr=0.3,0.1

Type RM Length L Ch R = 1,5472,444,444,444
BEGIN DESCRIPTION:
Stream0757 12.0
END DESCRIPTION:
XS GIS Cut Line= 3
      2465625.02     13647224.97      2465325.00     13647625.00
      2465025.01     13648424.96
#Sta/Elev= 30
  4499.5  235.75  4659.7  230.69  4691.7  230.00  4842.2  227.81  4849.5  228.80
  4918.4  229.40  4949.5  229.31  4956.8  230.40  4963.1  229.22  5002.2  228.34
  5009.3  225.51  5014.7  220.87  5018.0  219.46  5018.5  218.96  5023.9  219.46
  5031.6  220.46  5039.6  228.30  5052.9  229.93  5235.3  226.84  5271.0  225.30
  5287.9  226.60  5439.9  227.44  5458.8  228.48  5466.8  228.00  5519.1  229.21
  5582.5  231.95  5607.4  234.87  5637.7  235.16  5670.5  236.85  5853.9  246.79
#Mann=10,-1,0
  4499.5   0.035       0  4659.7    0.12       0  4691.7    0.07       0
  4918.4    0.12       0  5018.0    0.05       0  5023.9    0.12       0
  5235.3    0.07       0  5439.9    0.05       0  5519.1    0.07       0
  5670.5   0.035       0
Bank Sta=5018,5023.9
Exp/Cntr=0.3,0.1

Type RM Length L Ch R = 1,5028,416,416,416
BEGIN DESCRIPTION:
Stream0757 11.0
END DESCRIPTION:
XS GIS Cut Line= 3
      2465225.02     13647074.98      2464975.00     13647375.00
      2464825.00     13648175.02
#Sta/Elev= 30
  4604.8  236.92  4752.0  231.87  4874.5  229.35  4910.1  228.32  4930.9  228.67
  4973.9  226.50  4988.2  227.14  4992.1  225.42  4997.9  225.42  5005.5  220.06
  5012.7  218.98  5013.2  218.48  5018.6  218.98  5021.6  222.51  5026.7  225.81
  5036.0  227.89  5117.4  226.23  5249.7  224.84  5289.5  225.46  5339.6  224.80
  5382.0  224.27  5399.8  225.29  5412.5  223.67  5444.4  224.41  5504.0  225.42
  5515.1  224.95  5585.4  225.62  5717.7  230.69  5768.6  233.93  5809.3  235.29
#Mann=7,-1,0
  4604.8    0.05       0  4752.0    0.07       0  4874.5    0.12       0
  5012.7    0.05       0  5018.6    0.12       0  5339.6    0.07       0
  5444.4    0.05       0
Bank Sta=5012.7,5018.6
Exp/Cntr=0.3,0.1

Type RM Length L Ch R = 1,4612,437,437,437
BEGIN DESCRIPTION:
Stream0757 10.0
END DESCRIPTION:
XS GIS Cut Line= 3
      2464425.02     13646775.03      2464625.00     13647175.00
      2464825.00     13648374.97
#Sta/Elev= 30
  4548.1  234.86  4592.8  232.18  4673.8  229.74  4690.6  227.80  4723.8  227.61
  4875.1  223.04  4905.8  224.11  4914.2  222.59  4936.6  225.01  4983.5  225.79
  5005.4  224.77  5015.6  218.64  5025.3  218.47  5025.8  217.97  5031.2  218.47
  5034.1  222.72  5035.8  225.21  5046.0  226.09  5127.1  224.09  5157.5  225.09
  5201.0  224.22  5248.7  223.38  5273.6  224.22  5455.5  224.24  5492.0  224.33
  5522.4  223.01  5612.0  223.85  5725.2  224.34  5796.2  225.92  6211.8  245.54
#Mann=10,-1,0
  4548.1    0.07       0  4723.8    0.12       0  4983.5    0.07       0
  5025.3    0.05       0  5031.2    0.07       0  5034.1    0.12       0
  5201.0    0.07       0  5273.6    0.12       0  5455.5    0.07       0
  5612.0    0.05       0
Bank Sta=5025.3,5031.2
Exp/Cntr=0.3,0.1

Type RM Length L Ch R = 1,4175,479,479,479
BEGIN DESCRIPTION:
Stream0757 9.0
END DESCRIPTION:
XS GIS Cut Line= 3
      2464275.01     13646674.95      2464225.00     13647075.00
      2464625.01     13648275.03
#Sta/Elev= 30
  4597.0  245.02  4639.9  242.23  4697.8  236.80  4860.4  227.49  4881.7  227.13
  4929.6  223.17  4962.4  223.98  4969.9  221.75  4977.0  216.95  4977.5  216.45
  4983.0  216.95  4990.1  217.25  4997.6  221.00  5002.8  221.00  5010.7  224.19
  5031.8  224.65  5084.5  224.72  5200.4  221.73  5274.2  222.49  5442.3  221.56
  5643.2  222.01  5664.2  220.34  5687.0  221.97  5832.9  222.99  5927.8  225.62
  6033.2  229.89  6075.3  232.80  6149.1  234.47  6180.7  236.78  6265.1  240.27
#Mann=6,-1,0
  4597.0    0.07       0  4860.4    0.12       0  4977.0    0.05       0
  4983.0    0.12       0  5442.3    0.07       0  5687.0    0.05       0
Bank Sta=4977,4983
Exp/Cntr=0.3,0.1

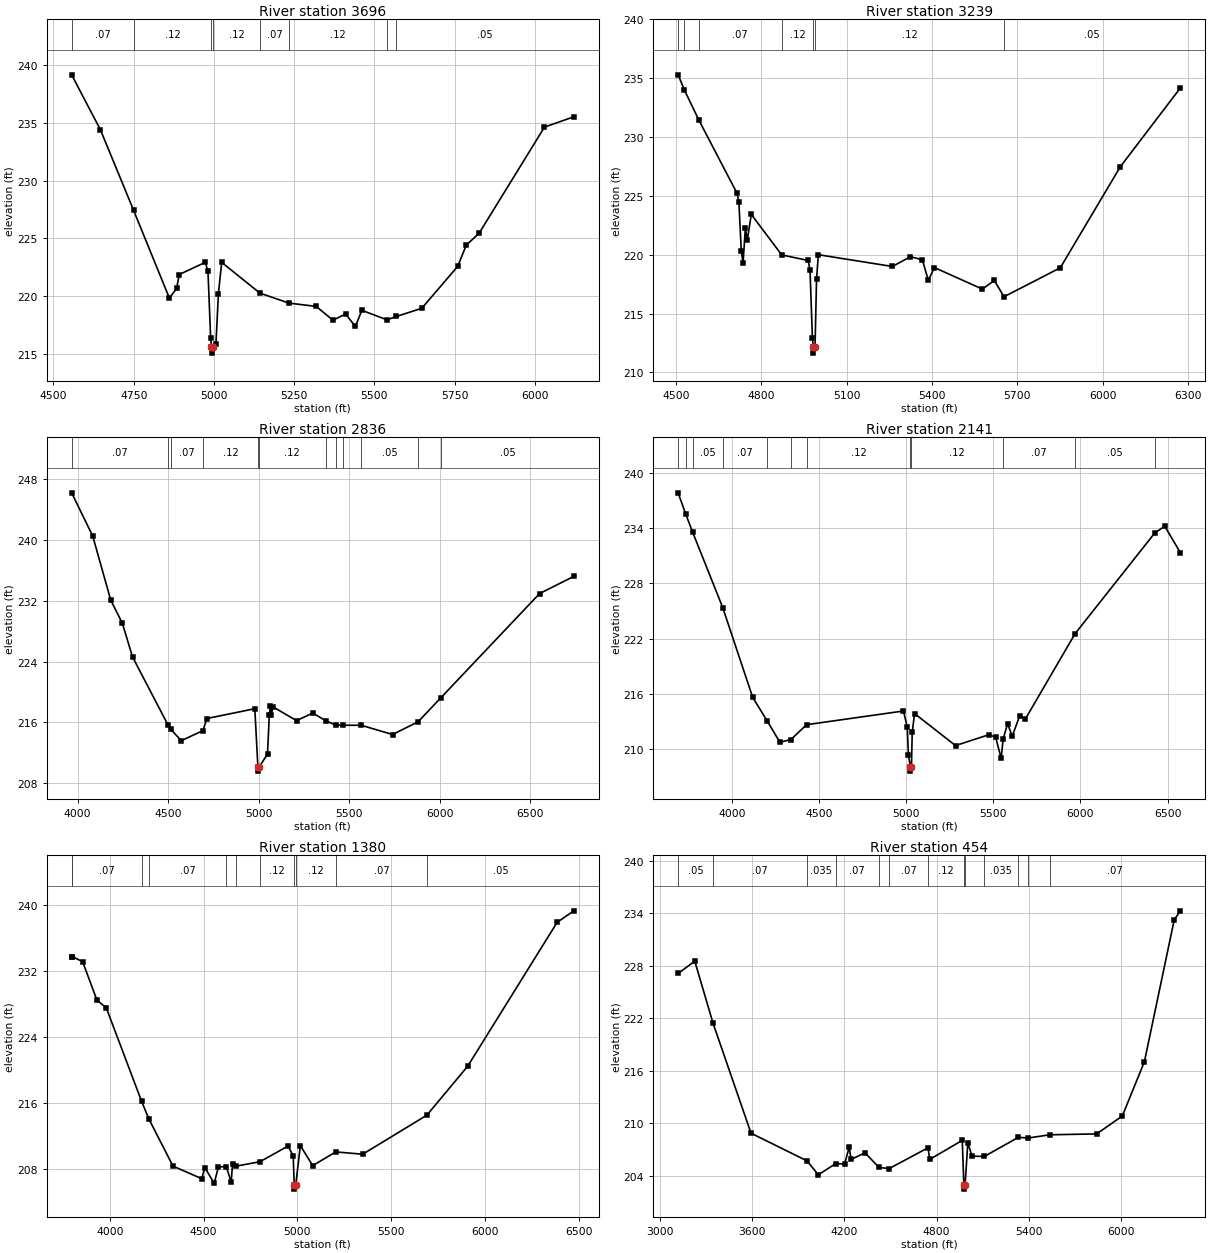
Type RM Length L Ch R = 1,3696,457,457,457
BEGIN DESCRIPTION:
Stream0757 8.0
END DESCRIPTION:
XS GIS Cut Line= 3
      2463975.02     13646674.97      2463775.00     13647075.00
      2463975.00     13648175.02
#Sta/Elev= 30
  4556.6  239.14  4646.1  234.40  4749.7  227.42  4861.3  219.82  4883.7  220.67
  4892.0  221.87  4973.1  222.92  4981.5  222.13  4989.9  216.36  4992.5  215.57
  4993.0  215.07  4998.5  215.57  5006.4  215.89  5014.0  220.20  5024.2  222.92
  5143.4  220.26  5233.5  219.40  5318.9  219.11  5371.0  217.92  5410.4  218.45
  5440.9  217.38  5461.2  218.77  5539.6  217.95  5569.0  218.24  5648.0  218.95
  5759.8  222.57  5786.5  224.40  5827.1  225.46  6030.4  234.62  6121.9  235.51
#Mann=8,-1,0
  4556.6    0.07       0  4749.7    0.12       0  4992.5    0.05       0
  4998.5    0.12       0  5143.4    0.07       0  5233.5    0.12       0
  5539.6    0.07       0  5569.0    0.05       0
Bank Sta=4992.5,4998.5
Exp/Cntr=0.3,0.1

Type RM Length L Ch R = 1,3239,403,403,403
BEGIN DESCRIPTION:
Stream0757 7.0
END DESCRIPTION:
XS GIS Cut Line= 3
      2463825.04     13646624.97      2463425.00     13646925.00
      2463825.01     13648125.04
#Sta/Elev= 30
  4507.8  235.28  4529.1  234.03  4580.6  231.44  4715.1  225.21  4721.4  224.47
  4729.7  220.35  4736.0  219.30  4744.3  222.29  4750.6  221.22  4765.1  223.42
  4872.0  219.98  4965.1  219.51  4971.4  218.67  4979.7  212.96  4983.0  212.14
  4983.5  211.64  4989.0  212.14  4994.3  217.90  5000.6  220.00  5260.8  219.00
  5324.1  219.83  5366.2  219.57  5387.3  217.81  5408.4  218.91  5577.1  217.08
  5619.2  217.81  5653.2  216.43  5851.1  218.89  6061.9  227.47  6272.8  234.16
#Mann=7,-1,0
  4507.8    0.07       0  4529.1    0.12       0  4580.6    0.07       0
  4872.0    0.12       0  4983.0    0.05       0  4989.0    0.12       0
  5653.2    0.05       0
Bank Sta=4983,4989
Exp/Cntr=0.3,0.1

Type RM Length L Ch R = 1,2836,695,695,695
BEGIN DESCRIPTION:
XS7657
END DESCRIPTION:
XS GIS Cut Line= 4
      2463690.94     13645966.00      2463128.47     13646465.97
      2463204.86     13647695.14      2463774.30     13648243.74
#Sta/Elev= 30
  3966.9  246.17  4083.4  240.49  4182.9  232.07  4246.5  229.07  4303.4  224.61
  4498.5  215.71  4514.9  215.10  4572.6  213.61  4692.3  214.93  4713.9  216.52
  4979.0  217.81  4996.0  210.11  4996.5  209.61  5002.0  210.11  5049.1  211.86
  5059.1  217.01  5065.3  218.12  5070.3  217.00  5079.2  218.05  5209.4  216.25
  5299.6  217.24  5369.6  216.24  5427.9  215.64  5468.5  215.64  5567.4  215.63
  5740.4  214.42  5881.6  216.10  6008.2  219.28  6552.1  232.93  6741.7  235.20
#Mann=12,-1,0
  3966.9    0.07       0  4498.5    0.12       0  4514.9    0.07       0
  4692.3    0.12       0  4996.0    0.05       0  5002.0    0.12       0
  5369.6    0.05       0  5427.9    0.12       0  5468.5    0.07       0
  5567.4    0.05       0  5881.6    0.07       0  6008.2    0.05       0
Bank Sta=4996,5002
Exp/Cntr=0.3,0.1

Type RM Length L Ch R = 1,2141,761,761,761
BEGIN DESCRIPTION:
E21324
END DESCRIPTION:
XS GIS Cut Line= 3
      2463573.51     13645620.19      2462462.41     13646575.04
      2462019.94     13647919.80
#Sta/Elev= 30
  3691.9  237.86  3734.5  235.60  3775.2  233.58  3947.8  225.38  4119.8  215.61
  4203.5  213.03  4275.7  210.73  4339.5  211.03  4428.5  212.64  4984.5  214.13
  5006.5  212.38  5013.1  209.31  5024.3  208.09  5024.8  207.59  5030.4  208.09
  5034.8  211.80  5048.2  213.85  5283.2  210.37  5472.7  211.54  5513.1  211.29
  5544.8  208.99  5556.5  211.09  5581.9  212.74  5608.4  211.38  5651.7  213.63
  5683.2  213.24  5969.0  222.54  6426.4  233.50  6483.3  234.23  6572.6  231.36
#Mann=12,-1,0
  3691.9    0.05       0  3734.5   0.035       0  3775.2    0.05       0
  3947.8    0.07       0  4203.5    0.12       0  4339.5    0.07       0
  4428.5    0.12       0  5024.3    0.05       0  5030.4    0.12       0
  5556.5    0.07       0  5969.0    0.05       0  6426.4    0.07       0
Bank Sta=5024.3,5030.4
Exp/Cntr=0.3,0.1

Type RM Length L Ch R = 1,1380,926,926,926
BEGIN DESCRIPTION:
E21323
END DESCRIPTION:
XS GIS Cut Line= 3
      2463495.42     13645264.27      2462132.55     13645993.45
      2461707.19     13647043.81
#Sta/Elev= 30
  3796.2  233.67  3800.5  233.69  3854.9  233.07  3931.3  228.41  3980.9  227.49
  4169.3  216.16  4207.8  214.04  4336.8  208.31  4490.4  206.78  4506.7  208.14
  4556.5  206.22  4579.2  208.22  4621.0  208.24  4647.3  206.39  4654.6  208.60
  4672.2  208.30  4800.9  208.84  4950.4  210.74  4978.0  209.56  4983.5  206.02
  4984.0  205.52  4991.5  206.02  5016.2  210.79  5082.1  208.37  5205.2  210.03
  5348.8  209.75  5691.1  214.48  5909.1  220.42  6386.2  237.85  6475.1  239.24
#Mann=11,-1,0
  3796.2    0.05       0  3800.5    0.07       0  4169.3   0.035       0
  4207.8    0.07       0  4621.0    0.12       0  4672.2    0.07       0
  4800.9    0.12       0  4983.5    0.05       0  4991.5    0.12       0
  5205.2    0.07       0  5691.1    0.05       0
Bank Sta=4983.5,4991.5
Exp/Cntr=0.3,0.1

Type RM Length L Ch R = 1,454,0,0,0
BEGIN DESCRIPTION:
E21322
END DESCRIPTION:
XS GIS Cut Line= 4
      2463460.68     13645038.58      2462028.38     13645194.84
      2461594.35     13645680.95      2461351.30     13646826.77
#Sta/Elev= 30
  3119.8  227.11  3228.1  228.52  3346.3  221.45  3593.6  208.86  3957.3  205.70
  4030.9  204.11  4143.6  205.38  4201.9  205.35  4232.0  207.28  4243.3  205.86
  4334.6  206.62  4425.1  204.95  4491.6  204.82  4744.6  207.20  4754.3  205.86
  4966.6  208.04  4976.8  202.97  4977.3  202.47  4984.9  202.97  5002.6  207.75
  5030.2  206.24  5109.6  206.20  5331.3  208.39  5393.6  208.31  5536.4  208.68
  5840.0  208.78  6006.5  210.82  6150.3  217.03  6343.8  233.22  6383.6  234.27
#Mann=13,-1,0
  3119.8    0.05       0  3346.3    0.07       0  3957.3   0.035       0
  4143.6    0.07       0  4425.1     0.1       0  4491.6    0.07       0
  4744.6    0.12       0  4976.8    0.05       0  4984.9    0.12       0
  5109.6   0.035       0  5331.3    0.07       0  5393.6   0.035       0
  5536.4    0.07       0
Bank Sta=4976.8,4984.9
Exp/Cntr=0.3,0.1

Chan Stop Cuts=-1