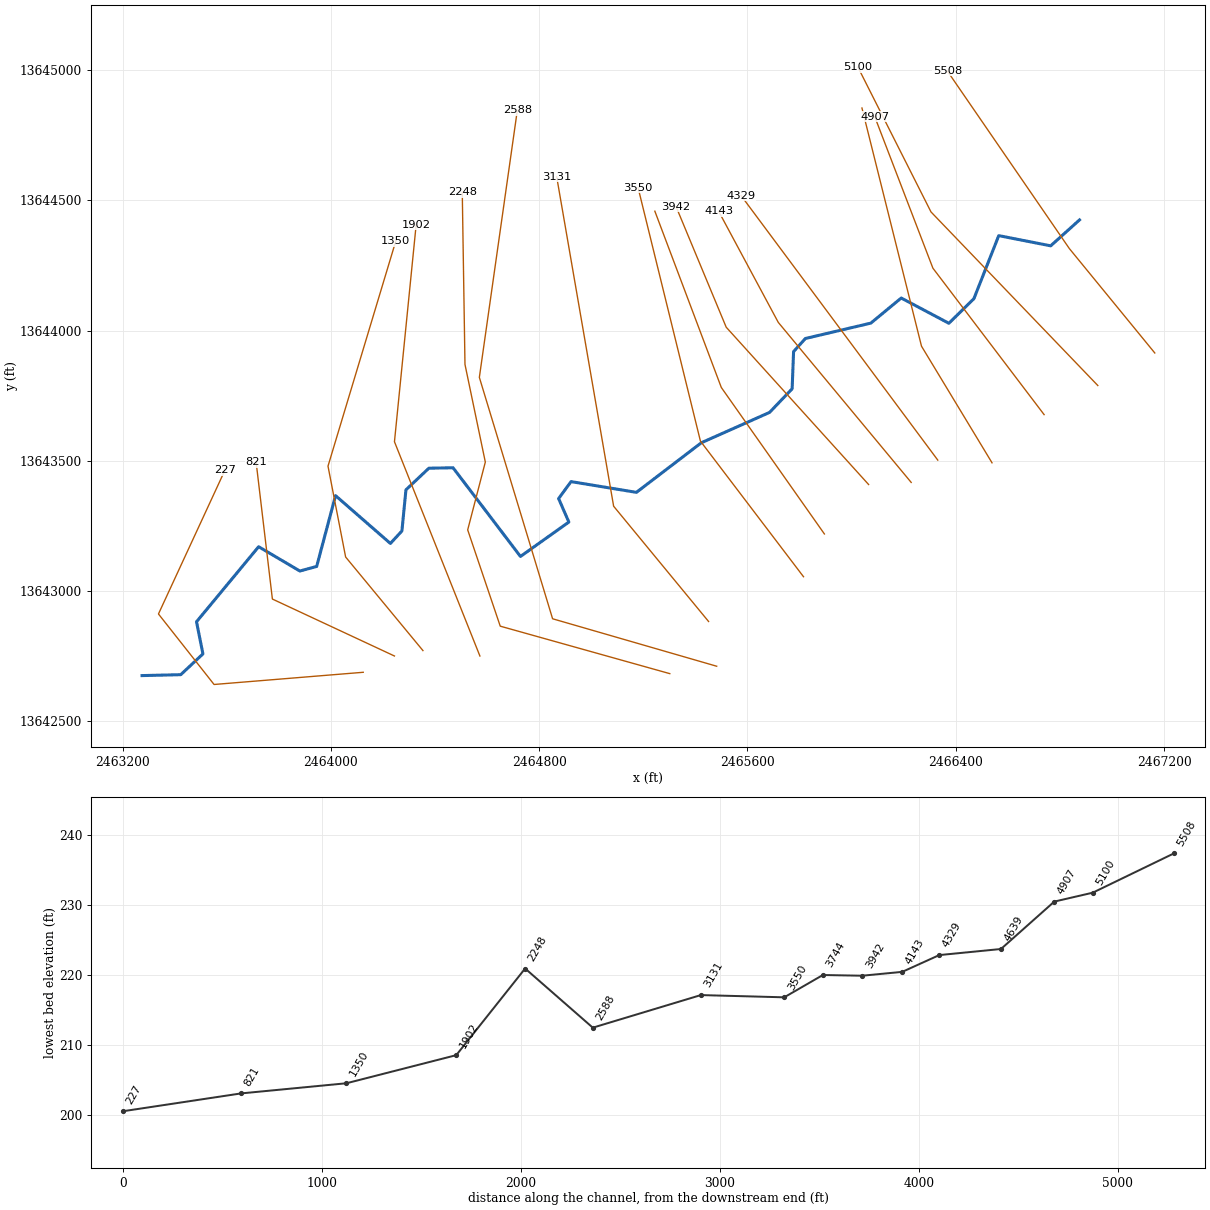
--- Stream0758.prj (project) ---

Proj Title=Stream0758 Base Level Engineering
Current Plan=p01
Default Exp/Contr=0.3,0.1
English Units
Geom File=g01
Flow File=f01
Plan File=p01
BEGIN DESCRIPTION:
Stream0758
END DESCRIPTION:

--- Stream0758.p01 (plan) ---

Plan Title=Multiple Run
Short Identifier=Multiple
Geom File=g01
Flow File=f01
Subcritical Flow
K Sum by GR= 0
Std Step Tol= 0.01
Critical Tol= 0.01
Num of Std Step Trials= 20
Max Error Tol= 0.3
Flow Tol Ratio= 0.001
Split Flow NTrial= 30
Split Flow Tol= 0.02
Split Flow Ratio= 0.02
Log Output Level= 0
Friction Slope Method= 1
Unsteady Friction Slope Method= 2
Unsteady Bridges Friction Slope Method= 1
Parabolic Critical Depth
Global Vel Dist=  1 , 1 , 1
Global Log Level= 0
CheckData=True
Encroach Param= -1, 0, 0, 0
BEGIN DESCRIPTION:
Multiple Run
END DESCRIPTION:

--- Stream0758.f01 (steady flow) ---

Flow Title=Multiple
Number of Profiles=7
Profile Names=10-year,25-year,50-year,1pct_min,100-year,1pct_plu,500-year
River Rch & RM= Stream0758,Reach-1,5508
     776    1267    1718    1128    2251    4492    3828
River Rch & RM= Stream0758,Reach-1,2588
     766    1247    1687    1105    2206    4401    3732
Boundary for River Rch & Prof#=Stream0758,Reach-1,1
Up Type=0
Dn Type=3
Dn Slope=0.005
Boundary for River Rch & Prof#=Stream0758,Reach-1,2
Up Type=0
Dn Type=3
Dn Slope=0.005
Boundary for River Rch & Prof#=Stream0758,Reach-1,3
Up Type=0
Dn Type=3
Dn Slope=0.005
Boundary for River Rch & Prof#=Stream0758,Reach-1,4
Up Type=0
Dn Type=3
Dn Slope=0.005
Boundary for River Rch & Prof#=Stream0758,Reach-1,5
Up Type=0
Dn Type=3
Dn Slope=0.005
Boundary for River Rch & Prof#=Stream0758,Reach-1,6
Up Type=0
Dn Type=3
Dn Slope=0.005
Boundary for River Rch & Prof#=Stream0758,Reach-1,7
Up Type=0
Dn Type=3
Dn Slope=0.005

--- Stream0758.g01 (geometry) ---

Geom Title=Existing Conditions

River Reach=Stream0758,Reach-1
Reach XY= 30
      2466875.00     13644425.00      2466764.38     13644325.55
      2466564.89     13644364.70      2466469.48     13644122.56
      2466373.37     13644028.09      2466190.36     13644125.10
      2466073.50     13644028.62      2465822.29     13643969.60
      2465776.98     13643919.35      2465771.46     13643776.46
      2465684.71     13643685.75      2465422.70     13643569.17
      2465173.44     13643378.74      2464922.38     13643420.01
      2464874.64     13643354.96      2464914.02     13643264.63
      2464728.15     13643132.52      2464469.29     13643473.12
      2464376.49     13643471.55      2464288.36     13643388.35
      2464272.93     13643230.44      2464228.62     13643182.47
      2464018.00     13643366.18      2463945.58     13643094.21
      2463881.09     13643076.57      2463722.70     13643169.94
      2463484.15     13642881.73      2463508.79     13642758.29
      2463423.57     13642678.49      2463275.00     13642675.00

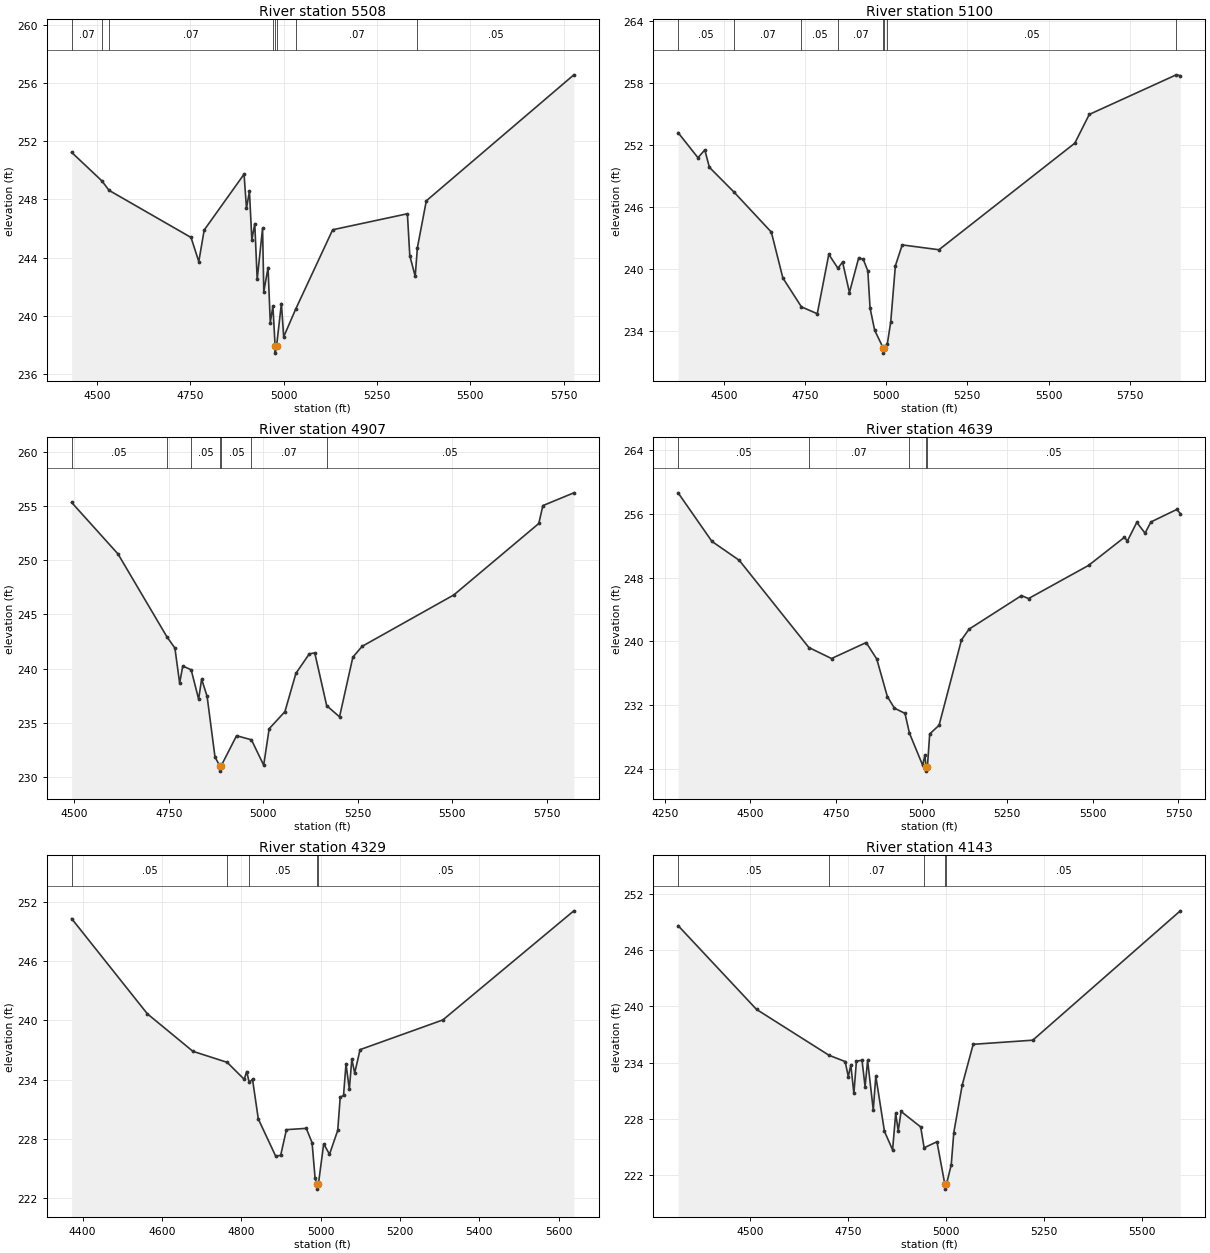
Type RM Length L Ch R = 1,5508,408,408,408
BEGIN DESCRIPTION:
XS7669
END DESCRIPTION:
XS GIS Cut Line= 3
      2467164.06     13643914.06      2466835.94     13644315.10
      2466367.17     13644997.42
#Sta/Elev= 30
  4431.5  251.23  4512.5  249.27  4531.7  248.62  4751.5  245.38  4772.3  243.72
  4786.7  245.89  4893.6  249.73  4900.1  247.39  4908.0  248.55  4914.5  245.21
  4922.3  246.33  4928.8  242.50  4943.2  246.01  4946.5  241.65  4957.9  243.31
  4963.9  239.52  4970.9  240.67  4976.8  237.93  4977.1  237.43  4980.8  237.93
  4993.7  240.84  4999.8  238.55  5031.7  240.44  5131.1  245.91  5331.4  247.01
  5337.8  244.13  5352.3  242.71  5358.2  244.68  5382.1  247.90  5777.5  256.56
#Mann=8,-1,0
  4431.5    0.07       0  4512.5   0.035       0  4531.7    0.07       0
  4970.9   0.033       0  4976.8   0.033       0  4980.8   0.033       0
  5031.7    0.07       0  5358.2    0.05       0
Bank Sta=4976.8,4980.8
Exp/Cntr=0.3,0.1

Type RM Length L Ch R = 1,5100,193,193,193
BEGIN DESCRIPTION:
XS7668
END DESCRIPTION:
XS GIS Cut Line= 3
      2466945.31     13643789.06      2466304.69     13644455.73
      2466024.21     13645011.49
#Sta/Elev= 30
  4358.9  253.20  4420.0  250.77  4441.1  251.52  4455.2  249.84  4531.2  247.43
  4646.1  243.55  4681.6  239.10  4738.8  236.30  4787.6  235.63  4823.1  241.39
  4851.1  240.05  4865.6  240.64  4886.7  237.69  4915.0  241.03  4929.1  240.93
  4943.3  239.79  4950.2  236.19  4964.4  234.03  4990.7  232.31  4990.9  231.81
  4994.7  232.31  5003.6  232.74  5014.0  234.86  5028.2  240.28  5049.3  242.31
  5162.5  241.84  5581.0  252.18  5625.6  254.97  5893.4  258.81  5906.0  258.73
#Mann=8,-1,0
  4358.9    0.05       0  4531.2    0.07       0  4738.8    0.05       0
  4851.1    0.07       0  4990.7    0.05       0  4994.7    0.07       0
  5003.6    0.05       0  5893.4   0.035       0
Bank Sta=4990.7,4994.7
Exp/Cntr=0.3,0.1

Type RM Length L Ch R = 1,4907,268,268,268
BEGIN DESCRIPTION:
E21331
END DESCRIPTION:
XS GIS Cut Line= 3
      2466739.09     13643677.27      2466311.98     13644239.81
      2466088.61     13644821.60
#Sta/Elev= 30
  4492.5  255.33  4615.2  250.58  4744.6  242.94  4765.9  241.89  4778.4  238.66
  4786.7  240.24  4808.9  239.89  4828.7  237.18  4836.6  239.03  4851.1  237.44
  4872.0  231.84  4884.5  231.04  4884.8  230.54  4888.5  231.04  4929.1  233.81
  4968.5  233.43  5000.9  231.09  5015.4  234.45  5057.1  236.03  5086.2  239.56
  5121.6  241.36  5136.1  241.45  5167.7  236.58  5201.7  235.55  5237.0  241.06
  5261.7  242.06  5504.3  246.80  5729.2  253.39  5740.0  255.04  5822.0  256.22
#Mann=7,-1,0
  4492.5    0.05       0  4744.6    0.07       0  4808.9    0.05       0
  4884.5    0.05       0  4888.5    0.05       0  4968.5    0.07       0
  5167.7    0.05       0
Bank Sta=4884.5,4888.5
Exp/Cntr=0.3,0.1

Type RM Length L Ch R = 1,4639,310,310,310
BEGIN DESCRIPTION:
XS7667
END DESCRIPTION:
XS GIS Cut Line= 3
      2466539.05     13643492.22      2466268.23     13643940.10
      2466039.54     13644854.85
#Sta/Elev= 30
  4289.0  258.61  4387.7  252.53  4467.5  250.16  4670.7  239.24  4736.9  237.86
  4838.1  239.86  4869.0  237.80  4899.9  233.10  4920.5  231.65  4951.4  230.99
  4964.4  228.52  5003.0  224.50  5009.7  225.77  5012.8  224.26  5013.1  223.76
  5016.8  224.26  5023.6  228.42  5050.9  229.50  5116.4  240.20  5138.5  241.54
  5291.6  245.74  5312.2  245.37  5487.4  249.52  5592.1  253.04  5600.8  252.58
  5628.2  254.91  5652.4  253.56  5669.4  254.96  5745.1  256.53  5755.3  256.01
#Mann=5,-1,0
  4289.0    0.05       0  4670.7    0.07       0  4964.4    0.05       0
  5012.8    0.05       0  5016.8    0.05       0
Bank Sta=5012.8,5016.8
Exp/Cntr=0.3,0.1

Type RM Length L Ch R = 1,4329,186,186,186
BEGIN DESCRIPTION:
XS7666
END DESCRIPTION:
XS GIS Cut Line= 2
      2466330.72     13643502.62      2465575.53     13644518.22
#Sta/Elev= 30
  4372.6  250.31  4563.4  240.66  4678.2  236.86  4764.6  235.74  4807.5  234.02
  4813.7  234.81  4820.1  233.70  4828.4  234.03  4843.0  230.00  4886.5  226.26
  4899.3  226.30  4913.9  228.92  4963.9  229.05  4978.5  227.60  4986.2  223.97
  4990.4  223.39  4990.7  222.89  4994.4  223.39  5007.8  227.48  5022.4  226.42
  5043.2  228.85  5049.4  232.20  5057.8  232.39  5064.0  235.58  5072.4  233.02
  5078.7  236.06  5085.9  234.66  5099.5  237.03  5308.1  240.04  5638.2  251.10
#Mann=5,-1,0
  4372.6    0.05       0  4764.6    0.07       0  4820.1    0.05       0
  4990.4    0.05       0  4994.4    0.05       0
Bank Sta=4990.4,4994.4
Exp/Cntr=0.3,0.1

Type RM Length L Ch R = 1,4143,201,201,201
BEGIN DESCRIPTION:
E21330
END DESCRIPTION:
XS GIS Cut Line= 3
      2466228.65     13643416.89      2465718.23     13644031.48
      2465489.53     13644457.69
#Sta/Elev= 30
  4316.3  248.62  4516.5  239.68  4701.7  234.78  4743.0  234.11  4750.9  232.50
  4757.4  233.74  4765.2  230.70  4771.7  234.16  4786.0  234.24  4793.8  231.42
  4800.3  234.23  4814.7  228.95  4821.2  232.55  4843.3  226.66  4864.1  224.68
  4872.0  228.58  4878.5  226.71  4885.8  228.78  4935.8  227.13  4944.6  224.90
  4977.4  225.55  4997.6  220.99  4997.8  220.49  5001.6  220.99  5013.9  223.10
  5020.4  226.53  5041.8  231.58  5069.9  235.95  5222.1  236.39  5598.9  250.20
#Mann=5,-1,0
  4316.3    0.05       0  4701.7    0.07       0  4944.6    0.05       0
  4997.6    0.05       0  5001.6    0.05       0
Bank Sta=4997.6,5001.6
Exp/Cntr=0.3,0.1

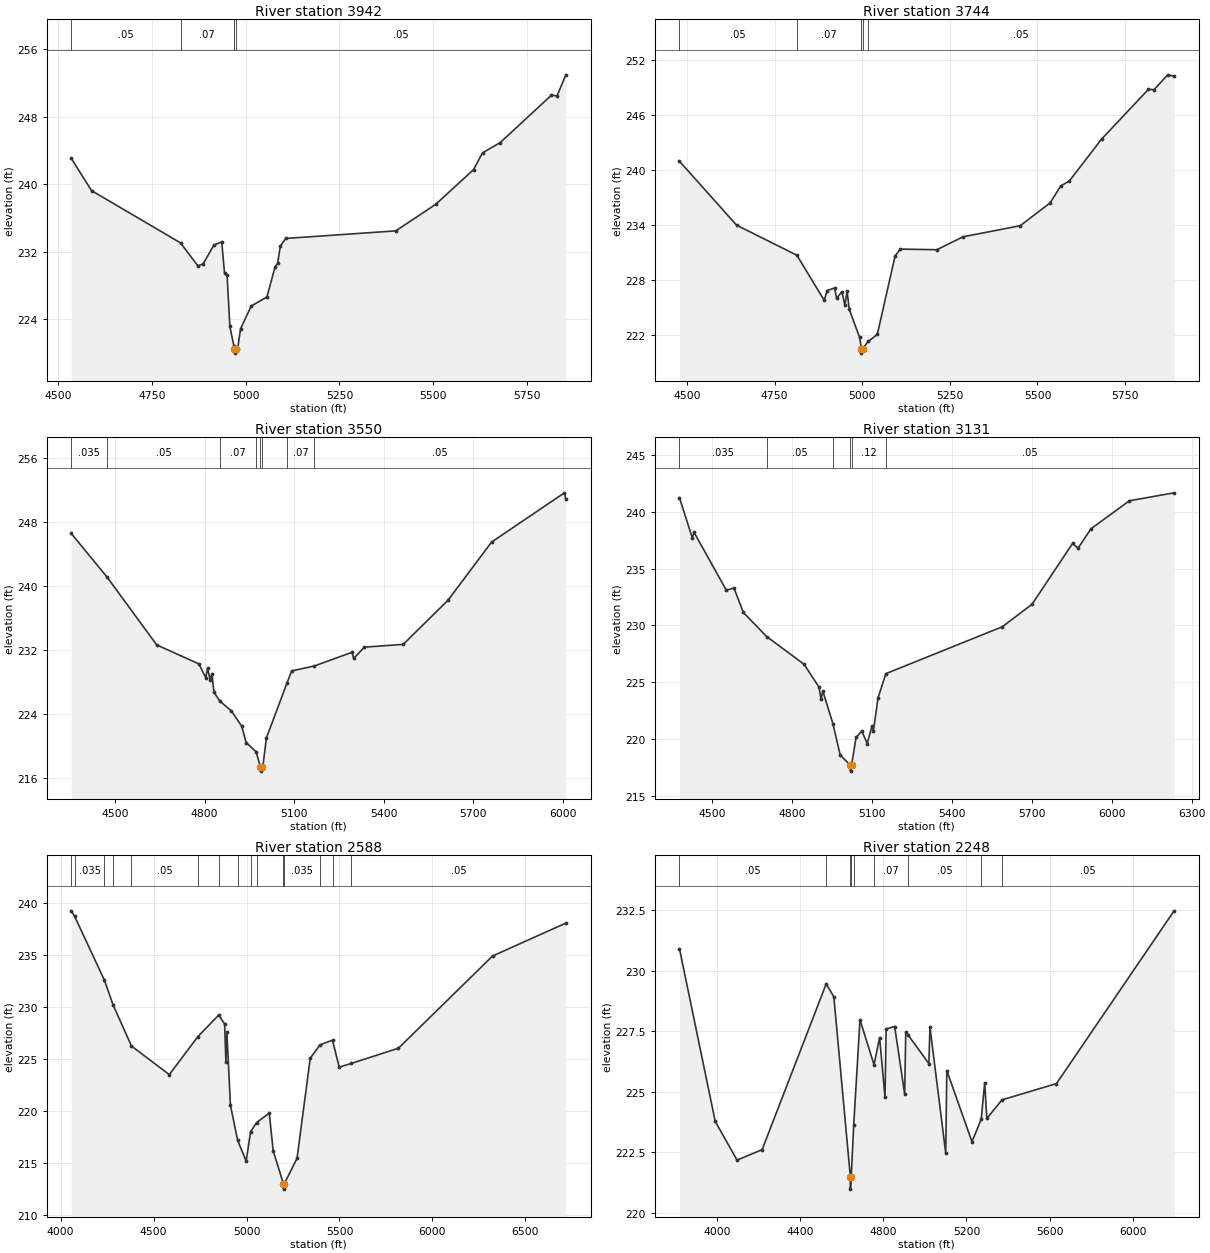
Type RM Length L Ch R = 1,3942,198,198,198
BEGIN DESCRIPTION:
XS7665
END DESCRIPTION:
XS GIS Cut Line= 3
      2466065.13     13643408.82      2465518.23     13644013.02
      2465325.51     13644476.59
#Sta/Elev= 30
  4535.8  243.06  4589.7  239.23  4826.9  233.02  4872.9  230.30  4887.1  230.54
  4915.5  232.77  4936.5  233.13  4943.9  229.44  4950.7  229.16  4958.1  223.11
  4968.8  220.78  4970.3  220.44  4970.6  219.94  4974.3  220.44  4979.0  220.48
  4986.5  222.82  5014.9  225.53  5056.8  226.60  5078.4  230.16  5085.2  230.59
  5092.6  232.66  5106.8  233.55  5399.9  234.45  5506.2  237.60  5607.0  241.72
  5630.9  243.71  5677.8  244.92  5814.1  250.54  5829.4  250.48  5852.8  252.97
#Mann=5,-1,0
  4535.8    0.05       0  4826.9    0.07       0  4968.8    0.05       0
  4970.3    0.05       0  4974.3    0.05       0
Bank Sta=4970.3,4974.3
Exp/Cntr=0.3,0.1

Type RM Length L Ch R = 1,3744,194,194,194
BEGIN DESCRIPTION:
E21329
END DESCRIPTION:
XS GIS Cut Line= 3
      2465895.30     13643218.99      2465499.48     13643781.48
      2465244.26     13644458.58
#Sta/Elev= 30
  4478.5  240.97  4641.4  234.00  4813.5  230.72  4891.4  225.80  4900.1  226.87
  4921.0  227.15  4927.1  226.02  4941.9  226.74  4950.5  225.28  4956.7  226.80
  4962.9  224.82  4992.5  221.75  4997.4  220.54  4997.7  220.04  5001.4  220.54
  5016.9  221.31  5043.0  222.08  5093.5  230.60  5108.3  231.39  5212.8  231.32
  5287.6  232.73  5450.8  233.94  5536.1  236.43  5566.3  238.27  5591.2  238.83
  5683.0  243.39  5816.8  248.82  5832.6  248.78  5871.8  250.40  5889.9  250.26
#Mann=5,-1,0
  4478.5    0.05       0  4813.5    0.07       0  4997.4    0.05       0
  5001.4    0.07       0  5016.9    0.05       0
Bank Sta=4997.4,5001.4
Exp/Cntr=0.3,0.1

Type RM Length L Ch R = 1,3550,419,419,419
BEGIN DESCRIPTION:
XS7664
END DESCRIPTION:
XS GIS Cut Line= 3
      2465815.09     13643054.70      2465419.27     13643575.52
      2465179.84     13644548.84
#Sta/Elev= 30
  4353.2  246.60  4472.5  241.17  4639.4  232.65  4780.8  230.27  4803.7  228.54
  4809.9  229.76  4818.2  228.25  4824.5  229.02  4830.9  226.75  4850.6  225.62
  4888.9  224.41  4924.3  222.46  4938.8  220.43  4972.3  219.28  4986.8  217.35
  4987.0  216.85  4990.8  217.35  4995.0  217.47  5006.8  221.01  5076.1  227.92
  5091.2  229.39  5167.8  230.02  5293.7  231.73  5298.8  230.96  5335.2  232.37
  5465.0  232.72  5614.4  238.22  5760.8  245.52  6004.8  251.69  6009.7  250.86
#Mann=8,-1,0
  4353.2   0.035       0  4472.5    0.05       0  4850.6    0.07       0
  4972.3    0.05       0  4986.8    0.05       0  4990.8    0.05       0
  5076.1    0.07       0  5167.8    0.05       0
Bank Sta=4986.8,4990.8
Exp/Cntr=0.3,0.1

Type RM Length L Ch R = 1,3131,543,543,543
BEGIN DESCRIPTION:
XS7663
END DESCRIPTION:
XS GIS Cut Line= 3
      2465450.53     13642882.80      2465085.94     13643325.52
      2464867.29     13644590.53
#Sta/Elev= 30
  4376.7  241.23  4424.8  237.71  4431.4  238.19  4552.5  233.10  4581.2  233.29
  4616.4  231.14  4703.9  229.02  4844.4  226.58  4900.4  224.57  4908.3  223.49
  4914.8  224.23  4952.7  221.36  4980.1  218.60  5018.7  217.67  5019.0  217.17
  5022.7  217.67  5039.9  220.15  5061.3  220.69  5081.6  219.60  5099.7  221.15
  5104.8  220.70  5122.2  223.61  5151.6  225.75  5589.0  229.88  5700.7  231.86
  5852.9  237.22  5873.2  236.79  5921.7  238.50  6066.0  240.97  6234.0  241.67
#Mann=6,-1,0
  4376.7   0.035       0  4703.9    0.05       0  4952.7    0.12       0
  5018.7    0.05       0  5022.7    0.12       0  5151.6    0.05       0
Bank Sta=5018.7,5022.7
Exp/Cntr=0.3,0.1

Type RM Length L Ch R = 1,2588,340,340,340
BEGIN DESCRIPTION:
XS7662
END DESCRIPTION:
XS GIS Cut Line= 4
      2465481.76     13642710.94      2464851.56     13642893.23
      2464570.31     13643820.31      2464716.15     13644846.36
#Sta/Elev= 30
  4057.0  239.29  4075.3  238.75  4235.5  232.61  4281.9  230.24  4380.9  226.28
  4584.5  223.53  4737.9  227.18  4850.3  229.26  4882.1  228.41  4889.0  224.72
  4894.2  227.61  4913.4  220.59  4952.4  217.19  4998.1  215.21  5021.8  218.03
  5054.4  218.92  5122.4  219.82  5143.3  216.21  5198.7  213.01  5199.0  212.51
  5202.7  213.01  5271.8  215.47  5342.8  225.11  5395.9  226.40  5462.6  226.84
  5498.6  224.25  5564.7  224.61  5817.3  226.07  6323.6  234.94  6718.2  238.11
#Mann=15,-1,0
  4057.0    0.05       0  4075.3   0.035       0  4235.5    0.05       0
  4281.9   0.035       0  4380.9    0.05       0  4737.9   0.035       0
  4850.3    0.05       0  4952.4   0.035       0  5021.8    0.07       0
  5054.4   0.035       0  5198.7   0.035       0  5202.7   0.035       0
  5395.9    0.05       0  5462.6   0.035       0  5564.7    0.05       0
Bank Sta=5198.7,5202.7
Exp/Cntr=0.3,0.1

Type RM Length L Ch R = 1,2248,346,346,346
BEGIN DESCRIPTION:
E21332
END DESCRIPTION:
XS GIS Cut Line= 6
      2465301.56     13642682.52      2464650.52     13642864.81
      2464525.52     13643234.60      2464593.23     13643495.02
      2464515.10     13643870.02      2464504.70     13644530.78
#Sta/Elev= 30
  3819.3  230.90  3991.2  223.77  4096.1  222.17  4216.7  222.60  4525.0  229.45
  4561.8  228.92  4641.4  221.47  4641.6  220.97  4645.4  221.47  4657.6  223.64
  4687.6  227.97  4755.1  226.11  4782.0  227.23  4808.1  224.76  4813.4  227.59
  4854.5  227.69  4902.6  224.90  4907.8  227.46  4919.0  227.34  5019.0  226.16
  5024.2  227.67  5100.1  222.46  5105.3  225.87  5226.3  222.93  5270.9  223.86
  5287.6  225.37  5297.8  223.89  5371.0  224.66  5632.8  225.33  6198.7  232.47
#Mann=9,-1,0
  3819.3    0.05       0  4525.0   0.035       0  4641.4    0.05       0
  4645.4   0.035       0  4657.6    0.05       0  4755.1    0.07       0
  4919.0    0.05       0  5270.9   0.035       0  5371.0    0.05       0
Bank Sta=4641.4,4645.4
Exp/Cntr=0.3,0.1

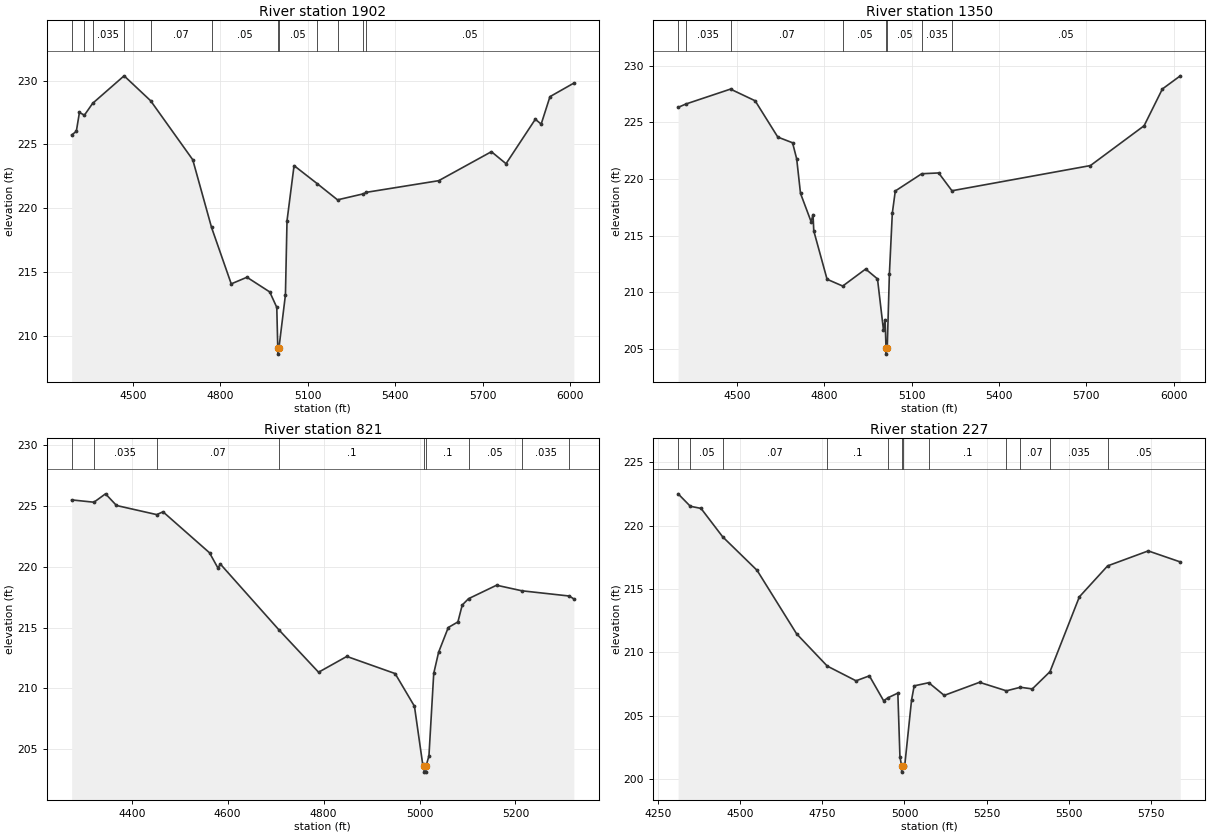
Type RM Length L Ch R = 1,1902,552,552,552
BEGIN DESCRIPTION:
E21328
END DESCRIPTION:
XS GIS Cut Line= 3
      2464572.41     13642750.18      2464244.27     13643573.14
      2464327.61     13644406.52
#Sta/Elev= 30
  4289.6  225.74  4305.6  226.02  4316.3  227.50  4333.4  227.29  4361.8  228.22
  4469.6  230.37  4560.6  228.42  4705.2  223.80  4769.7  218.50  4837.3  214.08
  4891.2  214.60  4969.4  213.45  4993.6  212.24  4997.0  209.08  4997.3  208.58
  5001.1  209.08  5023.3  213.22  5028.7  219.01  5052.9  223.34  5132.8  221.92
  5202.1  220.66  5290.6  221.13  5301.3  221.25  5549.3  222.16  5730.2  224.43
  5780.4  223.49  5880.9  226.97  5901.0  226.59  5931.2  228.74  6013.1  229.80
#Mann=12,-1,0
  4289.6    0.05       0  4333.4    0.07       0  4361.8   0.035       0
  4469.6    0.05       0  4560.6    0.07       0  4769.7    0.05       0
  4997.0    0.05       0  5001.1    0.05       0  5132.8   0.035       0
  5202.1    0.05       0  5290.6   0.035       0  5301.3    0.05       0
Bank Sta=4997,5001.1
Exp/Cntr=0.3,0.1

Type RM Length L Ch R = 1,1350,529,529,529
BEGIN DESCRIPTION:
E21327
END DESCRIPTION:
XS GIS Cut Line= 4
      2464353.65     13642771.06      2464056.77     13643130.43
      2463989.06     13643479.39      2464249.49     13644344.02
#Sta/Elev= 30
  4297.8  226.31  4324.9  226.61  4477.7  227.92  4562.3  226.89  4640.2  223.69
  4690.8  223.19  4705.0  221.77  4718.1  218.73  4754.6  216.23  4761.1  216.86
  4763.7  215.42  4809.3  211.16  4863.1  210.56  4941.8  212.06  4982.5  211.19
  5002.9  206.71  5008.7  207.60  5011.8  205.06  5012.0  204.56  5015.9  205.06
  5023.3  211.60  5033.4  216.98  5043.6  218.94  5134.4  220.46  5192.6  220.53
  5238.2  218.96  5713.7  221.18  5898.1  224.69  5960.8  227.93  6022.4  229.09
#Mann=8,-1,0
  4297.8    0.07       0  4324.9   0.035       0  4477.7    0.07       0
  4863.1    0.05       0  5011.8    0.05       0  5015.9    0.05       0
  5134.4   0.035       0  5238.2    0.05       0
Bank Sta=5011.8,5015.9
Exp/Cntr=0.3,0.1

Type RM Length L Ch R = 1,821,594,594,594
BEGIN DESCRIPTION:
E21326
END DESCRIPTION:
XS GIS Cut Line= 3
      2464244.25     13642750.24      2463775.52     13642968.98
      2463713.02     13643495.02
#Sta/Elev= 30
  4274.7  225.51  4321.2  225.32  4345.3  226.01  4368.2  225.05  4452.1  224.30
  4465.2  224.53  4562.1  221.16  4579.5  219.92  4585.0  220.22  4707.7  214.78
  4789.5  211.33  4848.4  212.63  4949.1  211.22  4989.4  208.53  5006.4  203.81
  5009.4  203.61  5009.6  203.11  5013.2  203.11  5013.5  203.61  5019.6  204.44
  5029.6  211.23  5039.7  212.97  5059.9  215.01  5080.0  215.47  5089.0  216.86
  5102.1  217.38  5160.6  218.49  5213.6  218.03  5312.4  217.60  5321.7  217.36
#Mann=9,-1,0
  4274.7    0.07       0  4321.2   0.035       0  4452.1    0.07       0
  4707.7     0.1       0  5009.4    0.05       0  5013.5     0.1       0
  5102.1    0.05       0  5213.6   0.035       0  5312.4    0.07       0
Bank Sta=5009.4,5013.5
Exp/Cntr=0.3,0.1

Type RM Length L Ch R = 1,227,0,0,0
BEGIN DESCRIPTION:
E21325
END DESCRIPTION:
XS GIS Cut Line= 4
      2464124.45     13642687.72      2463551.56     13642640.85
      2463338.02     13642911.68      2463593.23     13643463.76
#Sta/Elev= 30
  4311.3  222.50  4348.4  221.52  4381.0  221.35  4446.9  219.11  4551.5  216.47
  4671.9  211.46  4765.1  208.92  4852.6  207.76  4893.2  208.15  4936.5  206.19
  4951.2  206.44  4979.8  206.79  4986.2  201.77  4991.2  201.06  4991.5  200.56
  4995.3  201.06  5000.7  201.06  5021.5  206.24  5029.5  207.36  5073.9  207.61
  5120.9  206.61  5228.3  207.64  5310.1  206.97  5352.7  207.25  5388.9  207.12
  5442.7  208.48  5532.1  214.38  5618.1  216.82  5741.6  218.00  5839.2  217.13
#Mann=12,-1,0
  4311.3    0.07       0  4348.4    0.05       0  4446.9    0.07       0
  4765.1     0.1       0  4951.2   0.035       0  4991.2   0.035       0
  4995.3   0.035       0  5073.9     0.1       0  5310.1    0.12       0
  5352.7    0.07       0  5442.7   0.035       0  5618.1    0.05       0
Bank Sta=4991.2,4995.3
Exp/Cntr=0.3,0.1

Chan Stop Cuts=-1