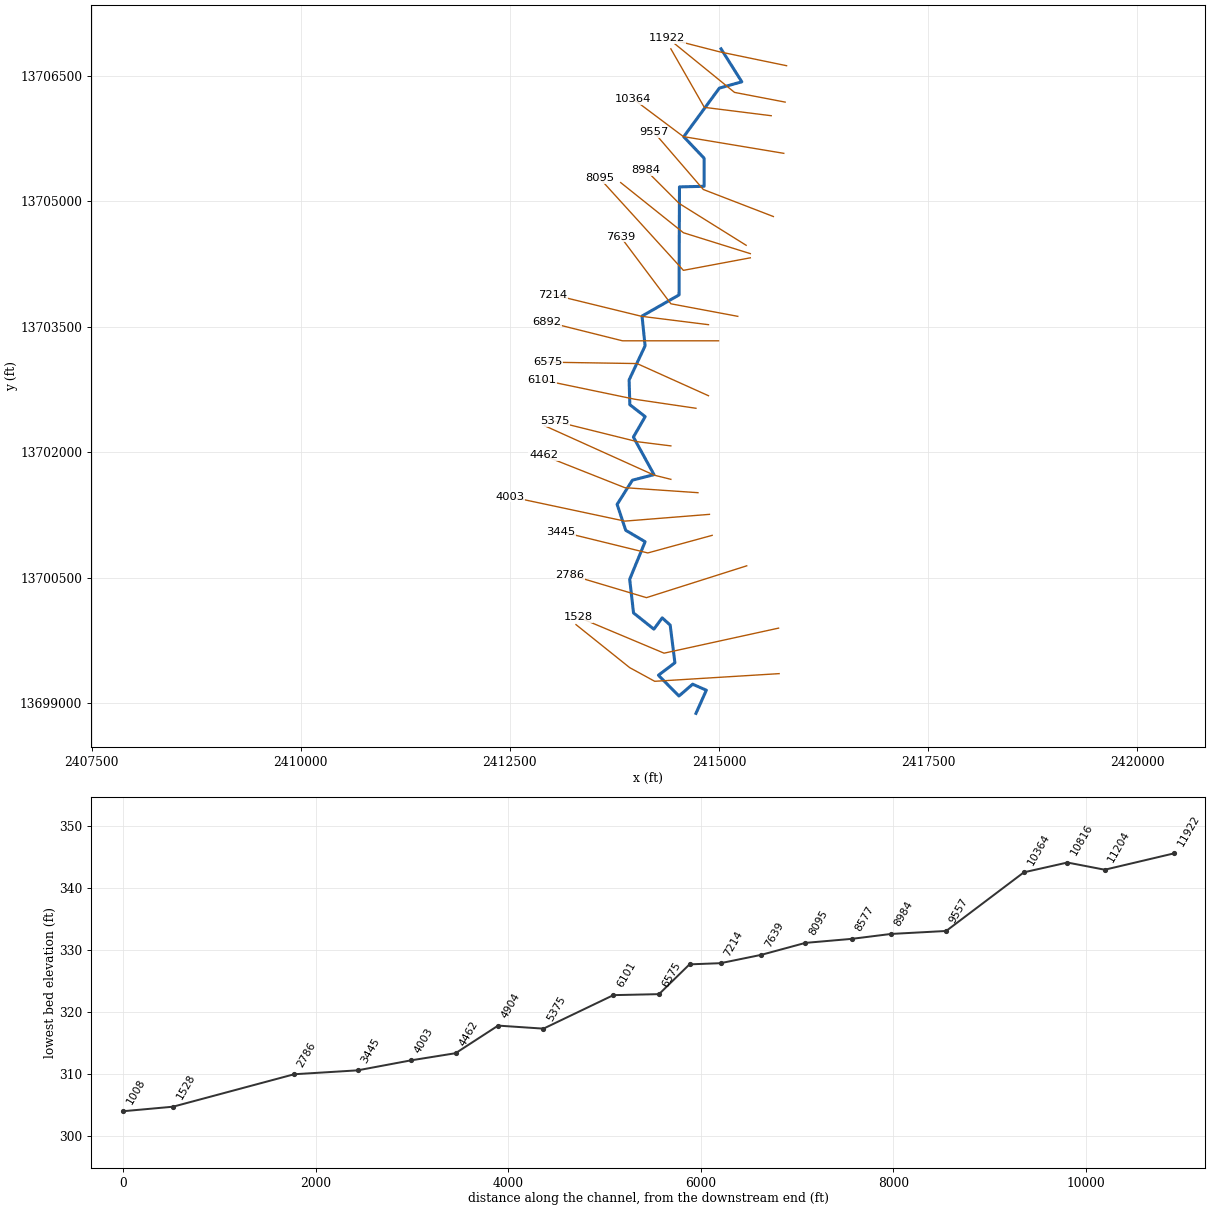
--- Turkey Creek 4.prj (project) ---

Proj Title=Turkey Creek 4 Base Level Engineering
Current Plan=p01
Default Exp/Contr=0.3,0.1
English Units
Geom File=g01
Flow File=f01
Plan File=p01
BEGIN DESCRIPTION:
Turkey Creek 4
END DESCRIPTION:

--- Turkey Creek 4.p01 (plan) ---

Plan Title=Multiple Run
Short Identifier=Multiple
Geom File=g01
Flow File=f01
Subcritical Flow
K Sum by GR= 0
Std Step Tol= 0.01
Critical Tol= 0.01
Num of Std Step Trials= 20
Max Error Tol= 0.3
Flow Tol Ratio= 0.001
Split Flow NTrial= 30
Split Flow Tol= 0.02
Split Flow Ratio= 0.02
Log Output Level= 0
Friction Slope Method= 1
Unsteady Friction Slope Method= 2
Unsteady Bridges Friction Slope Method= 1
Parabolic Critical Depth
Global Vel Dist=  1 , 1 , 1
Global Log Level= 0
CheckData=True
Encroach Param= -1, 0, 0, 0
BEGIN DESCRIPTION:
Multiple Run
END DESCRIPTION:

--- Turkey Creek 4.f01 (steady flow) ---

Flow Title=Multiple
Number of Profiles=7
Profile Names=10-year,25-year,50-year,1pct_min,100-year,1pct_plu,500-year
River Rch & RM= Turkey Creek 4,Reach-1,11922
     773    1266    1717    1128    2251    4492    3834
River Rch & RM= Turkey Creek 4,Reach-1,10816
    1014    1677    2289    1512    3017    6019    5190
River Rch & RM= Turkey Creek 4,Reach-1,6892
    1250    2081    2855    1892    3775    7533    6544
River Rch & RM= Turkey Creek 4,Reach-1,1008
    1325    2209    3033    2011    4012    8005    6961
Boundary for River Rch & Prof#=Turkey Creek 4,Reach-1,1
Up Type=0
Dn Type=3
Dn Slope=0.005
Boundary for River Rch & Prof#=Turkey Creek 4,Reach-1,2
Up Type=0
Dn Type=3
Dn Slope=0.005
Boundary for River Rch & Prof#=Turkey Creek 4,Reach-1,3
Up Type=0
Dn Type=3
Dn Slope=0.005
Boundary for River Rch & Prof#=Turkey Creek 4,Reach-1,4
Up Type=0
Dn Type=3
Dn Slope=0.005
Boundary for River Rch & Prof#=Turkey Creek 4,Reach-1,5
Up Type=0
Dn Type=3
Dn Slope=0.005
Boundary for River Rch & Prof#=Turkey Creek 4,Reach-1,6
Up Type=0
Dn Type=3
Dn Slope=0.005
Boundary for River Rch & Prof#=Turkey Creek 4,Reach-1,7
Up Type=0
Dn Type=3
Dn Slope=0.005

--- Turkey Creek 4.g01 (geometry) ---

Geom Title=Existing Conditions

River Reach=Turkey Creek 4,Reach-1
Reach XY= 30
      2415025.00     13706825.00      2415273.12     13706430.67
      2415004.87     13706355.24      2414578.47     13705773.50
      2414822.16     13705516.99      2414822.95     13705180.44
      2414528.06     13705173.60      2414522.95     13703880.84
      2414080.35     13703627.70      2414116.73     13703271.78
      2413926.04     13702864.56      2413934.14     13702568.25
      2414118.10     13702425.00      2413977.05     13702180.86
      2414223.43     13701731.04      2413965.30     13701664.82
      2413782.50     13701375.00      2413885.48     13701065.15
      2414117.21     13700928.45      2413932.67     13700478.66
      2413978.73     13700076.53      2414221.95     13699882.76
      2414321.43     13700017.52      2414416.88     13699931.09
      2414473.12     13699480.69      2414276.56     13699331.09
      2414521.67     13699082.59      2414685.48     13699224.07
      2414849.31     13699151.76      2414725.00     13698875.00

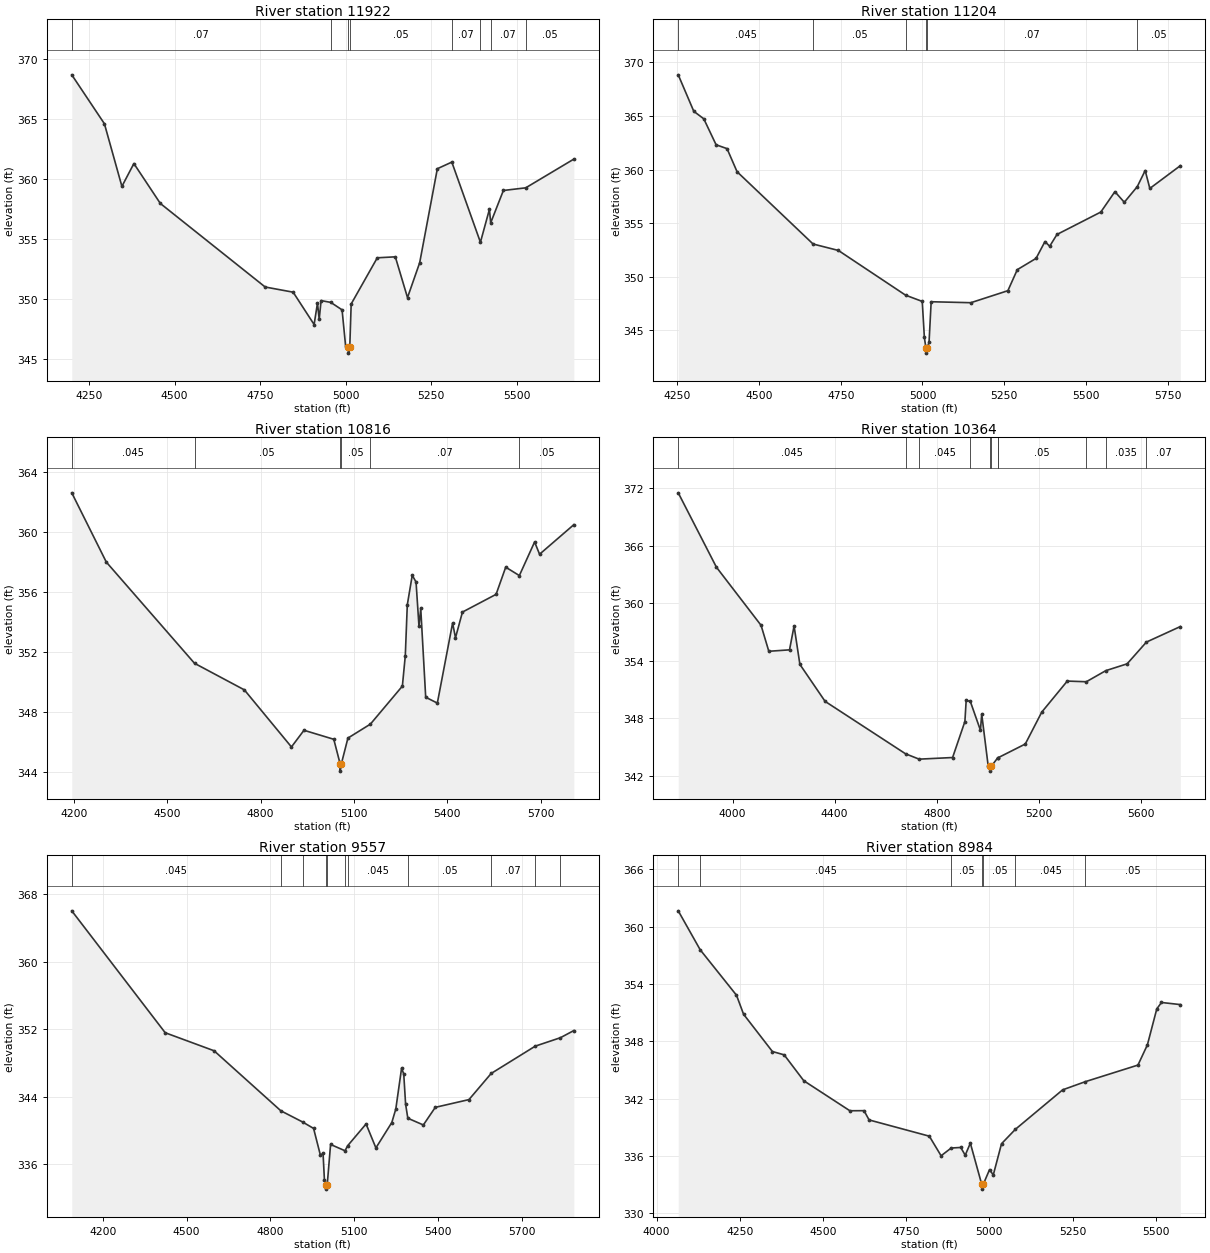
Type RM Length L Ch R = 1,11922,718,718,718
BEGIN DESCRIPTION:
XS7875
END DESCRIPTION:
XS GIS Cut Line= 3
      2415808.42     13706623.31      2415007.78     13706789.25
      2414378.62     13706950.68
#Sta/Elev= 30
  4199.4  368.67  4294.8  364.60  4345.9  359.39  4380.9  361.29  4458.2  357.97
  4764.6  351.02  4846.3  350.59  4907.6  347.90  4917.4  349.68  4922.5  348.34
  4928.0  349.89  4956.3  349.74  4989.3  349.12  4999.5  346.15  5007.6  346.02
  5007.9  345.52  5011.8  346.02  5015.9  349.61  5092.2  353.45  5144.9  353.53
  5180.5  350.14  5216.1  353.04  5267.7  360.86  5310.0  361.41  5393.6  354.74
  5419.9  357.48  5423.6  356.36  5460.7  359.05  5526.0  359.27  5666.6  361.66
#Mann=8,-1,0
  4199.4    0.07       0  4956.3    0.05       0  5007.6    0.05       0
  5011.8    0.05       0  5310.0    0.07       0  5393.6    0.05       0
  5423.6    0.07       0  5526.0    0.05       0
Bank Sta=5007.6,5011.8
Exp/Cntr=0.3,0.1

Type RM Length L Ch R = 1,11204,388,388,388
BEGIN DESCRIPTION:
XS7874
END DESCRIPTION:
XS GIS Cut Line= 3
      2415791.76     13706187.76      2415186.16     13706303.90
      2414472.67     13706884.65
#Sta/Elev= 30
  4252.5  368.83  4300.1  365.43  4330.7  364.73  4368.4  362.31  4401.9  361.95
  4432.5  359.80  4665.2  353.06  4742.6  352.46  4948.4  348.29  4999.3  347.71
  5005.8  344.35  5010.4  343.39  5010.6  342.89  5014.6  343.39  5020.1  343.89
  5026.6  347.68  5148.0  347.59  5261.4  348.71  5290.2  350.67  5347.6  351.72
  5374.9  353.29  5389.3  352.85  5411.6  353.95  5545.8  356.04  5588.9  357.94
  5617.7  356.95  5657.4  358.41  5681.6  359.91  5695.8  358.24  5789.1  360.36
#Mann=6,-1,0
  4252.5   0.045       0  4665.2    0.05       0  4948.4    0.07       0
  5010.4    0.05       0  5014.6    0.07       0  5657.4    0.05       0
Bank Sta=5010.4,5014.6
Exp/Cntr=0.3,0.1

Type RM Length L Ch R = 1,10816,452,452,452
BEGIN DESCRIPTION:
Turkey Creek 4 20.0
END DESCRIPTION:
XS GIS Cut Line= 3
      2415625.04     13706025.00      2414825.00     13706125.00
      2414424.99     13706825.01
#Sta/Elev= 30
  4193.5  362.58  4304.4  357.97  4587.7  351.23  4747.8  349.46  4899.0  345.66
  4939.3  346.77  5035.0  346.17  5055.2  344.55  5055.5  344.05  5059.5  344.55
  5080.4  346.25  5152.6  347.18  5255.3  349.71  5264.7  351.74  5271.1  355.12
  5287.0  357.09  5299.2  356.64  5308.6  353.70  5314.3  354.88  5330.2  348.97
  5367.6  348.58  5416.6  353.91  5425.9  352.93  5448.2  354.64  5556.2  355.82
  5587.2  357.63  5631.0  357.07  5680.0  359.31  5695.9  358.49  5806.0  360.46
#Mann=6,-1,0
  4193.5   0.045       0  4587.7    0.05       0  5055.2    0.05       0
  5059.5    0.05       0  5152.6    0.07       0  5631.0    0.05       0
Bank Sta=5055.2,5059.5
Exp/Cntr=0.3,0.1

Type RM Length L Ch R = 1,10364,807,807,807
BEGIN DESCRIPTION:
Turkey Creek 4 19.0
END DESCRIPTION:
XS GIS Cut Line= 3
      2415774.99     13705575.00      2414575.00     13705775.00
      2413975.03     13706224.97
#Sta/Elev= 30
  3787.4  371.52  3936.9  363.76  4111.8  357.69  4142.2  354.98  4223.3  355.13
  4241.1  357.62  4263.9  353.61  4362.7  349.75  4677.7  344.28  4730.9  343.72
  4862.0  343.89  4910.2  347.65  4915.2  349.86  4931.5  349.74  4971.0  346.74
  4976.1  348.41  5001.4  343.01  5009.0  342.97  5009.3  342.47  5013.4  342.97
  5038.8  343.86  5040.4  343.87  5146.7  345.30  5211.2  348.63  5311.2  351.87
  5385.8  351.80  5462.2  352.96  5545.6  353.67  5621.1  355.94  5753.9  357.56
#Mann=11,-1,0
  3787.4   0.045       0  4677.7    0.05       0  4730.9   0.045       0
  4931.5    0.05       0  5009.0    0.05       0  5013.4    0.05       0
  5038.8    0.07       0  5040.4    0.05       0  5385.8    0.07       0
  5462.2   0.035       0  5621.1    0.07       0
Bank Sta=5009,5013.4
Exp/Cntr=0.3,0.1

Type RM Length L Ch R = 1,9557,573,573,573
BEGIN DESCRIPTION:
Turkey Creek 4 18.0
END DESCRIPTION:
XS GIS Cut Line= 3
      2415650.76     13704818.82      2414812.81     13705142.38
      2414224.98     13705825.02
#Sta/Elev= 30
  4088.4  366.03  4423.2  351.57  4598.4  349.43  4837.6  342.31  4915.2  340.99
  4954.9  340.22  4979.5  337.02  4988.8  337.28  4993.8  334.08  4999.2  333.52
  4999.5  333.02  5003.7  333.52  5015.8  338.32  5067.6  337.57  5076.8  338.16
  5143.0  340.75  5178.2  337.91  5235.2  340.92  5249.5  342.52  5270.3  347.38
  5278.0  346.67  5284.6  343.10  5292.6  341.43  5348.2  340.63  5391.0  342.72
  5511.7  343.64  5591.3  346.74  5749.3  349.98  5839.4  350.98  5887.5  351.83
#Mann=11,-1,0
  4088.4   0.045       0  4837.6    0.05       0  4915.2   0.045       0
  4999.2   0.045       0  5003.7   0.045       0  5067.6    0.05       0
  5076.8   0.045       0  5292.6    0.05       0  5591.3    0.07       0
  5749.3    0.05       0  5839.4    0.07       0
Bank Sta=4999.2,5003.7
Exp/Cntr=0.3,0.1

Type RM Length L Ch R = 1,8984,407,407,407
BEGIN DESCRIPTION:
Turkey Creek 4 17.0
END DESCRIPTION:
XS GIS Cut Line= 3
      2415325.01     13704474.99      2414525.00     13704975.00
      2414125.00     13705375.00
#Sta/Elev= 30
  4064.9  361.66  4130.8  357.59  4240.0  352.83  4261.3  350.84  4347.9  346.94
  4383.3  346.59  4442.3  343.88  4580.8  340.74  4623.3  340.75  4638.6  339.78
  4819.6  338.08  4855.0  336.03  4885.3  336.84  4914.0  336.90  4927.5  336.09
  4942.9  337.35  4977.1  333.04  4977.5  332.54  4981.7  333.04  5000.6  334.58
  5011.8  334.02  5036.6  337.29  5078.3  338.80  5220.4  342.93  5289.0  343.79
  5446.7  345.52  5475.0  347.63  5503.3  351.40  5517.4  352.07  5574.0  351.85
#Mann=7,-1,0
  4064.9    0.05       0  4130.8   0.045       0  4885.3    0.05       0
  4977.1    0.05       0  4981.7    0.05       0  5078.3   0.045       0
  5289.0    0.05       0
Bank Sta=4977.1,4981.7
Exp/Cntr=0.3,0.1

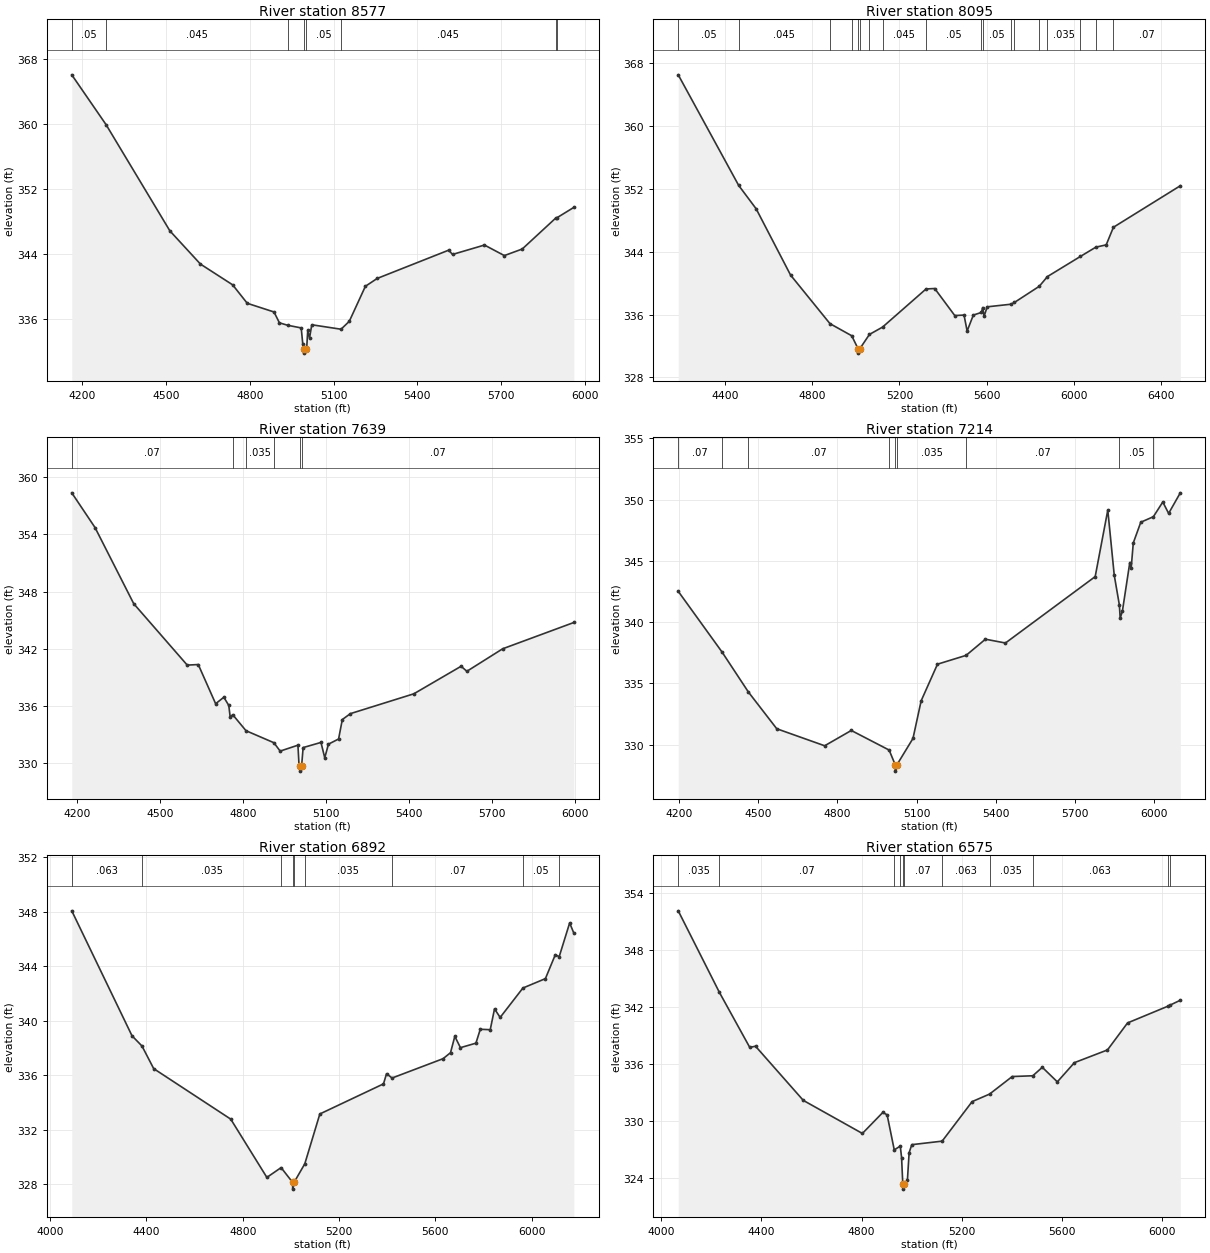
Type RM Length L Ch R = 1,8577,482,482,482
BEGIN DESCRIPTION:
Turkey Creek 4 16.0
END DESCRIPTION:
XS GIS Cut Line= 3
      2415375.04     13704374.99      2414575.00     13704625.00
      2413824.97     13705225.03
#Sta/Elev= 30
  4162.3  366.10  4285.2  359.95  4513.8  346.84  4623.3  342.74  4738.6  340.18
  4791.0  337.90  4886.8  336.83  4906.2  335.49  4935.5  335.19  4984.3  334.86
  4990.0  332.83  4995.6  332.25  4995.9  331.75  5000.2  332.25  5003.7  332.25
  5007.7  334.55  5014.1  333.61  5022.1  335.25  5127.0  334.70  5156.6  335.68
  5214.2  340.00  5256.6  340.97  5512.7  344.46  5526.3  343.93  5640.8  345.09
  5712.0  343.79  5776.1  344.60  5896.1  348.42  5899.6  348.44  5961.0  349.74
#Mann=8,-1,0
  4162.3    0.05       0  4285.2   0.045       0  4935.5    0.05       0
  4995.6    0.05       0  5000.2    0.05       0  5127.0   0.045       0
  5896.1   0.035       0  5899.6   0.045       0
Bank Sta=4995.6,5000.2
Exp/Cntr=0.3,0.1

Type RM Length L Ch R = 1,8095,456,456,456
BEGIN DESCRIPTION:
Turkey Creek 4 15.0
END DESCRIPTION:
XS GIS Cut Line= 3
      2415375.04     13704325.01      2414575.00     13704175.00
      2413574.99     13705275.01
#Sta/Elev= 30
  4186.5  366.50  4463.5  352.43  4543.5  349.46  4701.2  341.03  4881.8  334.85
  4981.4  333.31  5011.6  331.60  5012.0  331.10  5017.1  331.60  5062.7  333.48
  5122.7  334.41  5322.0  339.26  5361.7  339.32  5453.6  335.88  5496.1  335.94
  5510.3  333.91  5538.7  335.94  5576.1  336.28  5581.4  336.90  5588.0  335.79
  5602.2  336.99  5711.1  337.32  5727.2  337.55  5840.8  339.60  5878.4  340.84
  6029.5  343.40  6100.1  344.58  6147.5  344.87  6180.6  347.11  6487.1  352.39
#Mann=18,-1,0
  4186.5    0.05       0  4463.5   0.045       0  4881.8    0.05       0
  4981.4   0.045       0  5011.6   0.045       0  5017.1   0.045       0
  5062.7    0.05       0  5122.7   0.045       0  5322.0    0.05       0
  5576.1   0.035       0  5581.4    0.05       0  5711.1   0.045       0
  5727.2   0.035       0  5840.8   0.045       0  5878.4   0.035       0
  6029.5    0.07       0  6100.1   0.035       0  6180.6    0.07       0
Bank Sta=5011.6,5017.1
Exp/Cntr=0.3,0.1

Type RM Length L Ch R = 1,7639,425,425,425
BEGIN DESCRIPTION:
Turkey Creek 4 14.0
END DESCRIPTION:
XS GIS Cut Line= 3
      2415225.04     13703624.99      2414425.00     13703775.00
      2413824.99     13704575.02
#Sta/Elev= 30
  4181.5  358.37  4265.5  354.73  4405.4  346.74  4598.7  340.30  4638.5  340.36
  4701.3  336.25  4730.9  336.93  4748.8  336.07  4753.8  334.86  4763.0  335.10
  4811.0  333.42  4911.7  332.16  4934.4  331.28  4998.6  331.90  5002.8  329.70
  5006.2  329.68  5006.7  329.18  5011.8  329.68  5017.4  331.65  5081.9  332.19
  5095.5  330.58  5109.0  332.01  5145.5  332.55  5159.0  334.59  5188.2  335.21
  5417.4  337.29  5588.2  340.18  5609.0  339.65  5738.2  342.01  5995.5  344.77
#Mann=6,-1,0
  4181.5    0.07       0  4763.0   0.045       0  4811.0   0.035       0
  4911.7    0.07       0  5006.2    0.05       0  5011.8    0.07       0
Bank Sta=5006.2,5011.8
Exp/Cntr=0.3,0.1

Type RM Length L Ch R = 1,7214,322,322,322
BEGIN DESCRIPTION:
Turkey Creek 4 13.0
END DESCRIPTION:
XS GIS Cut Line= 3
      2414875.02     13703525.00      2414075.00     13703625.00
      2413012.05     13703884.89
#Sta/Elev= 30
  4197.6  342.51  4363.5  337.55  4463.1  334.29  4570.5  331.29  4751.9  329.90
  4852.7  331.15  4995.9  329.55  5019.3  328.33  5019.7  327.83  5024.9  328.33
  5086.2  330.50  5117.1  333.57  5178.9  336.56  5287.2  337.28  5360.4  338.60
  5436.2  338.29  5775.9  343.71  5823.6  349.14  5848.0  343.83  5867.6  341.37
  5870.4  340.31  5878.9  340.89  5906.9  344.86  5912.0  344.38  5920.1  346.46
  5948.5  348.15  5996.1  348.60  6031.8  349.80  6053.9  348.87  6098.1  350.55
#Mann=9,-1,0
  4197.6    0.07       0  4363.5   0.035       0  4463.1    0.07       0
  4995.9   0.035       0  5019.3   0.035       0  5024.9   0.035       0
  5287.2    0.07       0  5867.6    0.05       0  5996.1    0.07       0
Bank Sta=5019.3,5024.9
Exp/Cntr=0.3,0.1

Type RM Length L Ch R = 1,6892,317,317,317
BEGIN DESCRIPTION:
H21508
END DESCRIPTION:
XS GIS Cut Line= 3
      2414995.18     13703332.22      2413846.50     13703332.22
      2412938.13     13703559.31
#Sta/Elev= 30
  4089.9  348.08  4340.1  338.90  4381.5  338.15  4430.1  336.49  4750.1  332.78
  4900.1  328.50  4959.2  329.22  5006.9  328.14  5007.4  327.64  5013.2  328.14
  5057.6  329.50  5120.1  333.16  5384.4  335.37  5397.1  336.12  5420.0  335.80
  5631.8  337.22  5662.7  337.66  5680.6  338.86  5704.0  338.03  5768.2  338.36
  5786.4  339.38  5827.7  339.35  5845.5  340.88  5868.9  340.25  5963.4  342.41
  6056.8  343.10  6098.0  344.86  6114.0  344.71  6157.5  347.19  6174.9  346.44
#Mann=9,-1,0
  4089.9   0.063       0  4381.5   0.035       0  4959.2    0.07       0
  5006.9    0.05       0  5013.2    0.07       0  5057.6   0.035       0
  5420.0    0.07       0  5963.4    0.05       0  6114.0    0.07       0
Bank Sta=5006.9,5013.2
Exp/Cntr=0.3,0.1

Type RM Length L Ch R = 1,6575,474,474,474
BEGIN DESCRIPTION:
Turkey Creek 4 12.0
END DESCRIPTION:
XS GIS Cut Line= 3
      2414874.98     13702675.01      2414020.49     13703059.94
      2412954.40     13703076.53
#Sta/Elev= 30
  4068.3  352.13  4232.1  343.57  4353.6  337.76  4376.7  337.88  4567.3  332.18
  4803.1  328.70  4884.6  330.91  4901.8  330.66  4930.3  326.97  4954.3  327.37
  4959.5  326.16  4964.4  323.34  4964.9  322.84  4970.8  323.34  4982.7  323.75
  4989.6  326.67  5000.3  327.52  5121.4  327.89  5241.0  332.05  5310.4  332.84
  5401.0  334.69  5483.1  334.77  5521.0  335.66  5581.0  334.13  5649.1  336.15
  5781.1  337.49  5861.1  340.33  6021.1  342.08  6028.7  342.18  6071.7  342.72
#Mann=11,-1,0
  4068.3   0.035       0  4232.1    0.07       0  4930.3    0.12       0
  4954.3    0.07       0  4964.4    0.05       0  4970.8    0.07       0
  5121.4   0.063       0  5310.4   0.035       0  5483.1   0.063       0
  6021.1    0.07       0  6028.7   0.063       0
Bank Sta=4964.4,4970.8
Exp/Cntr=0.3,0.1

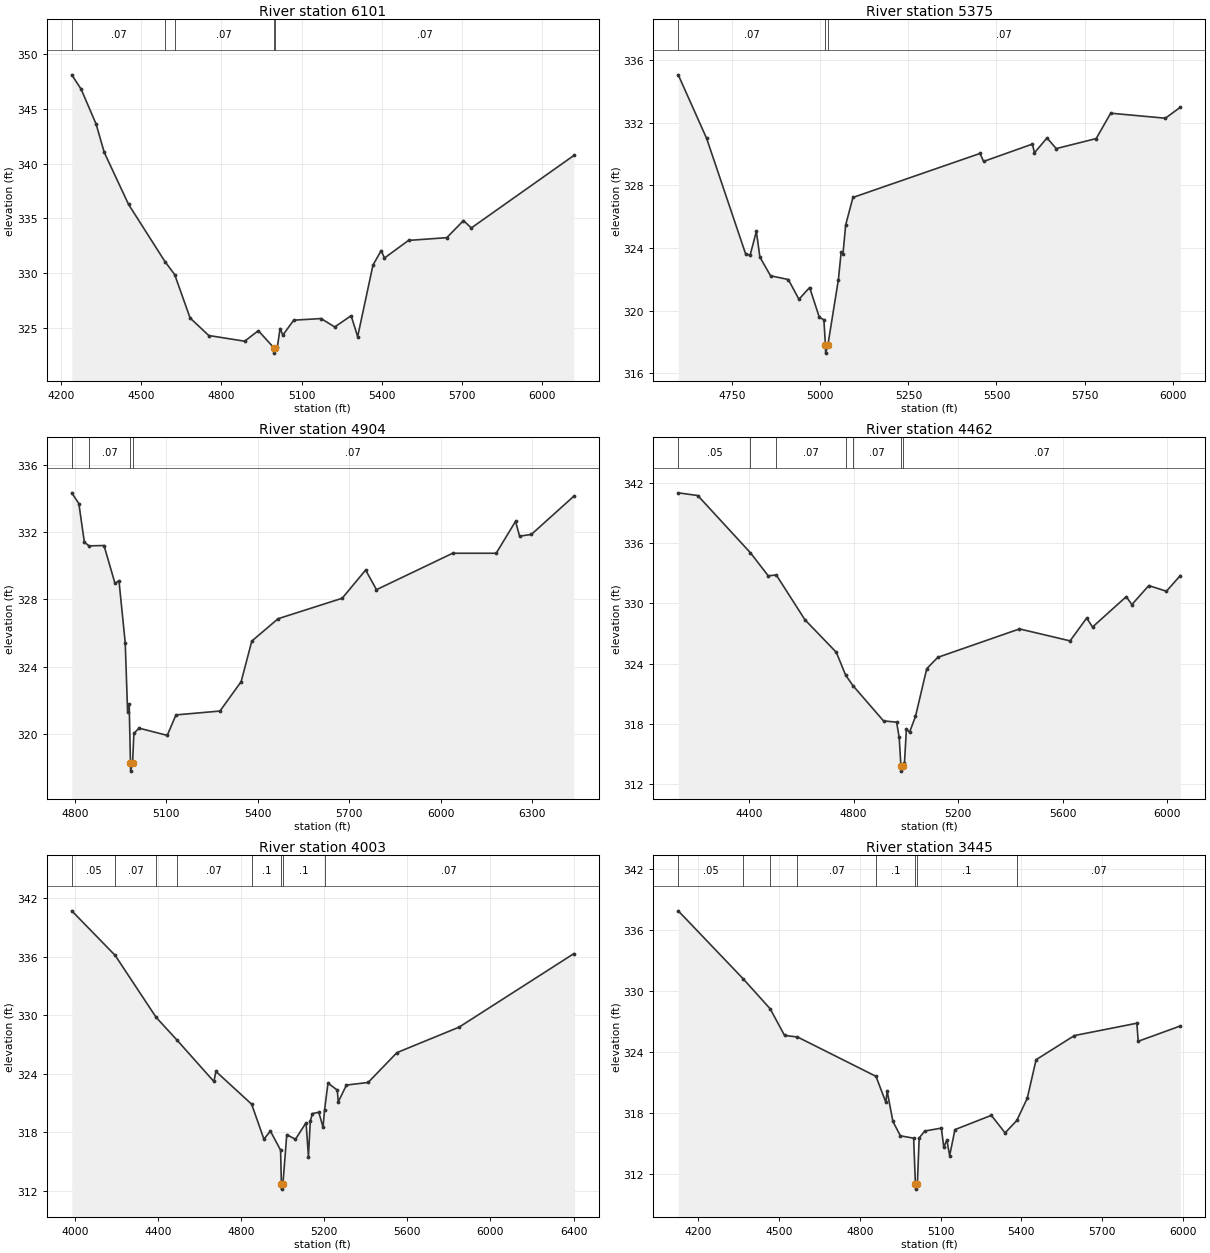
Type RM Length L Ch R = 1,6101,726,726,726
BEGIN DESCRIPTION:
Turkey Creek 4 11.0
END DESCRIPTION:
XS GIS Cut Line= 3
      2414725.02     13702525.00      2413995.60     13702632.66
      2412879.85     13702864.94
#Sta/Elev= 30
  4240.9  348.11  4275.7  346.81  4331.9  343.61  4362.2  341.03  4453.2  336.27
  4589.2  331.05  4625.6  329.86  4683.3  325.89  4753.0  324.29  4887.2  323.77
  4938.4  324.73  4996.0  323.18  4996.5  322.68  5002.5  323.18  5009.3  323.22
  5019.7  324.93  5029.9  324.33  5070.8  325.69  5172.9  325.84  5224.0  325.07
  5285.3  326.10  5309.7  324.19  5367.0  330.73  5397.6  332.05  5409.9  331.37
  5499.8  332.98  5642.8  333.23  5705.2  334.79  5734.7  334.12  6117.9  340.74
#Mann=5,-1,0
  4240.9    0.07       0  4589.2    0.12       0  4625.6    0.07       0
  4996.0    0.05       0  5002.5    0.07       0
Bank Sta=4996,5002.5
Exp/Cntr=0.3,0.1

Type RM Length L Ch R = 1,5375,471,471,471
BEGIN DESCRIPTION:
Turkey Creek 4 10.0
END DESCRIPTION:
XS GIS Cut Line= 3
      2414424.99     13702075.00      2414025.00     13702125.00
      2413033.23     13702371.31
#Sta/Elev= 30
  4596.8  335.05  4677.4  330.99  4788.3  323.60  4800.9  323.54  4818.5  325.05
  4828.6  323.41  4858.8  322.22  4909.2  321.98  4939.4  320.72  4969.7  321.47
  4997.4  319.56  5010.2  319.41  5014.6  317.78  5015.1  317.28  5021.4  317.78
  5051.4  321.98  5059.3  323.75  5064.5  323.64  5072.0  325.46  5092.6  327.22
  5453.3  330.03  5463.6  329.52  5602.1  330.63  5607.8  330.07  5643.4  331.02
  5669.6  330.34  5783.0  330.98  5824.2  332.60  5979.4  332.28  6021.8  332.98
#Mann=3,-1,0
  4596.8    0.07       0  5014.6    0.05       0  5021.4    0.07       0
Bank Sta=5014.6,5021.4
Exp/Cntr=0.3,0.1

Type RM Length L Ch R = 1,4904,442,442,442
BEGIN DESCRIPTION:
Turkey Creek 4 9.0
END DESCRIPTION:
XS GIS Cut Line= 3
      2414425.04     13701674.99      2414225.00     13701725.00
      2412912.93     13702317.38
#Sta/Elev= 30
  4790.3  334.35  4813.5  333.71  4831.6  331.41  4846.9  331.19  4896.0  331.21
  4932.1  328.95  4945.0  329.12  4965.6  325.40  4973.3  321.30  4978.5  321.77
  4982.7  318.27  4983.2  317.77  4989.6  318.27  4993.9  320.02  5010.8  320.33
  5103.3  319.90  5131.9  321.12  5276.1  321.35  5345.5  323.10  5380.5  325.52
  5466.6  326.85  5676.8  328.07  5753.6  329.75  5789.1  328.58  6038.8  330.75
  6181.5  330.75  6244.9  332.65  6258.3  331.77  6296.7  331.87  6436.1  334.15
#Mann=4,-1,0
  4790.3   0.063       0  4846.9    0.07       0  4982.7    0.05       0
  4989.6    0.07       0
Bank Sta=4982.7,4989.6
Exp/Cntr=0.3,0.1

Type RM Length L Ch R = 1,4462,459,459,459
BEGIN DESCRIPTION:
Turkey Creek 4 8.0
END DESCRIPTION:
XS GIS Cut Line= 3
      2414748.83     13701515.17      2413875.00     13701575.00
      2412902.66     13701960.38
#Sta/Elev= 30
  4128.7  341.01  4203.5  340.74  4405.2  335.04  4473.3  332.75  4504.0  332.84
  4613.7  328.38  4733.9  325.14  4769.2  322.88  4797.4  321.83  4914.4  318.32
  4964.5  318.19  4974.5  316.67  4981.1  313.82  4981.6  313.32  4988.0  313.82
  4994.6  314.14  5002.1  317.51  5014.1  317.19  5036.8  318.76  5079.9  323.51
  5122.1  324.64  5434.9  327.47  5628.5  326.28  5692.1  328.55  5714.5  327.66
  5843.6  330.68  5865.1  329.89  5929.7  331.78  5997.4  331.22  6050.5  332.78
#Mann=7,-1,0
  4128.7    0.05       0  4405.2   0.063       0  4504.0    0.07       0
  4769.2    0.12       0  4797.4    0.07       0  4981.1    0.05       0
  4988.0    0.07       0
Bank Sta=4981.1,4988
Exp/Cntr=0.3,0.1

Type RM Length L Ch R = 1,4003,558,558,558
BEGIN DESCRIPTION:
Turkey Creek 4 7.0
END DESCRIPTION:
XS GIS Cut Line= 3
      2414886.50     13701255.94      2413875.00     13701175.00
      2412504.81     13701466.57
#Sta/Elev= 30
  3985.6  340.72  4194.4  336.15  4391.4  329.80  4490.0  327.51  4669.3  323.22
  4679.3  324.25  4851.0  320.89  4910.0  317.31  4941.4  318.13  4990.3  316.18
  4994.2  312.68  4994.7  312.18  5001.4  312.68  5020.0  317.77  5061.7  317.29
  5112.8  318.99  5124.3  315.52  5133.2  319.16  5143.5  319.93  5174.1  320.06
  5194.6  318.53  5201.6  320.27  5218.3  323.05  5262.8  322.34  5267.9  321.13
  5307.0  322.85  5411.6  323.12  5550.1  326.18  5848.9  328.79  6401.2  336.33
#Mann=8,-1,0
  3985.6    0.05       0  4194.4    0.07       0  4391.4   0.035       0
  4490.0    0.07       0  4851.0     0.1       0  4994.2    0.05       0
  5001.4     0.1       0  5201.6    0.07       0
Bank Sta=4994.2,5001.4
Exp/Cntr=0.3,0.1

Type RM Length L Ch R = 1,3445,659,659,659
BEGIN DESCRIPTION:
XS7873
END DESCRIPTION:
XS GIS Cut Line= 3
      2414918.89     13701004.80      2414149.32     13700794.19
      2413112.91     13701048.40
#Sta/Elev= 30
  4125.7  337.87  4366.2  331.22  4467.4  328.25  4520.6  325.64  4568.7  325.49
  4860.2  321.63  4896.7  319.10  4901.8  320.17  4923.2  317.20  4950.9  315.79
  5000.1  315.56  5006.7  311.06  5007.2  310.56  5014.0  311.06  5020.7  315.58
  5041.3  316.26  5103.1  316.55  5112.0  314.68  5123.6  315.38  5133.9  313.85
  5153.6  316.40  5288.7  317.80  5339.9  316.08  5383.5  317.30  5422.2  319.48
  5455.0  323.26  5597.3  325.63  5829.2  326.84  5834.4  325.07  5990.7  326.57
#Mann=8,-1,0
  4125.7    0.05       0  4366.2    0.07       0  4467.4   0.035       0
  4568.7    0.07       0  4860.2     0.1       0  5006.7    0.05       0
  5014.0     0.1       0  5383.5    0.07       0
Bank Sta=5006.7,5014
Exp/Cntr=0.3,0.1

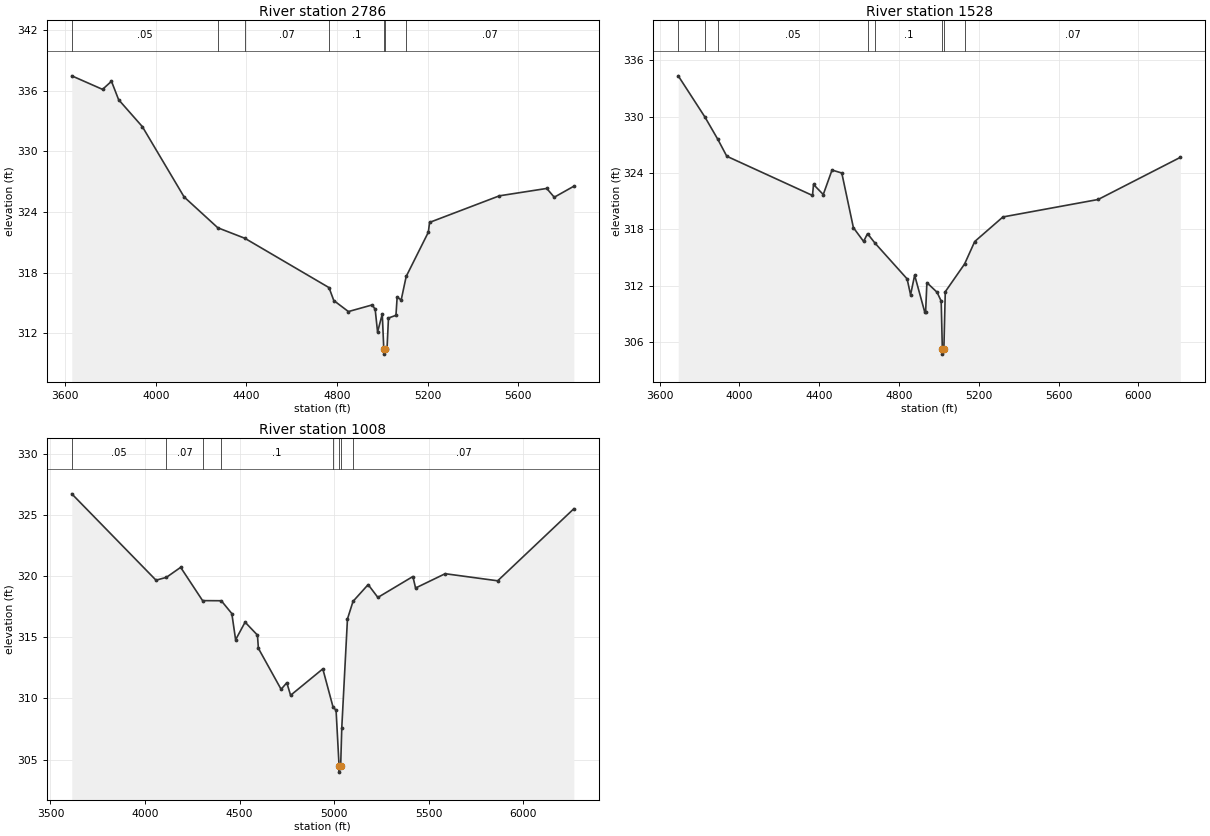
Type RM Length L Ch R = 1,2786,1258,1258,1258
BEGIN DESCRIPTION:
XS7872
END DESCRIPTION:
XS GIS Cut Line= 3
      2415332.09     13700640.28      2414133.12     13700259.52
      2413214.76     13700534.08
#Sta/Elev= 30
  3629.2  337.46  3765.0  336.12  3804.5  336.92  3836.0  335.10  3940.9  332.43
  4125.1  325.48  4273.8  322.43  4393.3  321.39  4764.8  316.51  4786.0  315.23
  4850.5  314.14  4955.9  314.80  4968.7  314.35  4979.2  312.11  5000.0  313.90
  5006.7  310.43  5007.2  309.93  5014.2  310.43  5020.9  310.44  5027.3  313.50
  5060.4  313.77  5065.6  315.56  5083.5  315.29  5105.5  317.61  5203.3  321.99
  5208.8  322.96  5517.0  325.59  5726.1  326.32  5759.2  325.45  5845.7  326.54
#Mann=7,-1,0
  3629.2    0.05       0  4273.8   0.035       0  4393.3    0.07       0
  4764.8     0.1       0  5006.7    0.05       0  5014.2     0.1       0
  5105.5    0.07       0
Bank Sta=5006.7,5014.2
Exp/Cntr=0.3,0.1

Type RM Length L Ch R = 1,1528,520,520,520
BEGIN DESCRIPTION:
XS7871
END DESCRIPTION:
XS GIS Cut Line= 3
      2415712.80     13699894.97      2414343.75     13699595.24
      2413315.13     13700027.17
#Sta/Elev= 30
  3693.1  334.36  3827.1  329.96  3891.9  327.58  3936.5  325.79  4366.2  321.61
  4371.3  322.78  4420.2  321.71  4464.1  324.32  4513.1  324.00  4571.2  318.18
  4622.4  316.71  4642.1  317.54  4679.2  316.54  4840.5  312.72  4857.9  311.02
  4878.3  313.11  4928.2  309.24  4933.3  309.18  4939.7  312.32  4990.9  311.29
  5011.4  310.35  5017.2  305.20  5017.7  304.70  5024.8  305.20  5031.9  311.35
  5128.8  314.31  5179.5  316.70  5321.0  319.32  5798.2  321.18  6210.2  325.67
#Mann=8,-1,0
  3693.1    0.05       0  3827.1    0.07       0  3891.9    0.05       0
  4642.1   0.035       0  4679.2     0.1       0  5017.2    0.05       0
  5024.8     0.1       0  5128.8    0.07       0
Bank Sta=5017.2,5024.8
Exp/Cntr=0.3,0.1

Type RM Length L Ch R = 1,1008,0,0,0
BEGIN DESCRIPTION:
H21507
END DESCRIPTION:
XS GIS Cut Line= 4
      2415719.50     13699350.42      2414231.94     13699258.69
      2413932.83     13699422.20      2413290.78     13699936.64
#Sta/Elev= 30
  3612.6  326.72  4057.9  319.66  4112.5  319.89  4188.2  320.71  4304.1  317.99
  4403.1  317.98  4458.7  316.93  4478.7  314.79  4528.8  316.23  4594.1  315.17
  4599.1  314.09  4719.2  310.74  4749.3  311.28  4769.3  310.25  4939.6  312.41
  4993.2  309.32  5009.8  309.01  5025.6  304.47  5026.1  303.97  5034.0  304.47
  5039.8  307.57  5069.9  316.49  5099.4  317.93  5179.3  319.30  5230.7  318.25
  5415.7  319.96  5430.0  319.02  5586.4  320.19  5864.0  319.61  6266.6  325.50
#Mann=8,-1,0
  3612.6    0.05       0  4112.5    0.07       0  4304.1   0.035       0
  4403.1     0.1       0  4993.2    0.12       0  5025.6    0.05       0
  5034.0    0.12       0  5099.4    0.07       0
Bank Sta=5025.6,5034
Exp/Cntr=0.3,0.1

Chan Stop Cuts=-1